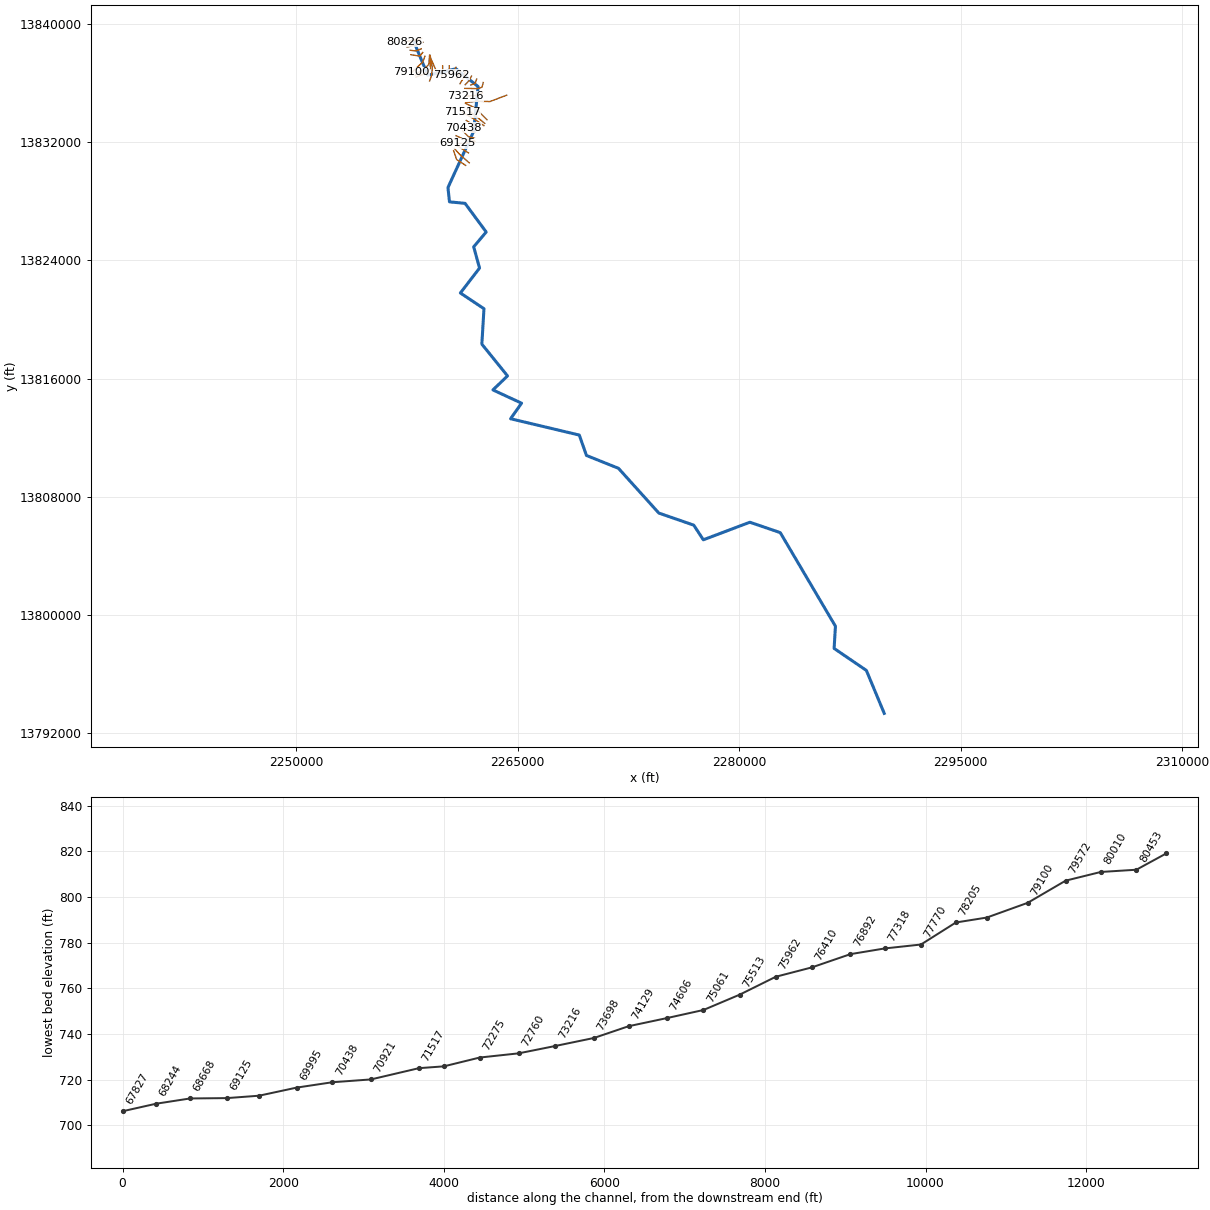
--- ALLIGATOR CREEK.prj (project) ---

Proj Title=ALLIGATOR CREEK Base Level Engineering
Current Plan=p01
Default Exp/Contr=0.3,0.1
English Units
Geom File=g01
Flow File=f01
Plan File=p01
Y Axis Title=Elevation
X Axis Title(PF)=Main Channel Distance
X Axis Title(XS)=Station
BEGIN DESCRIPTION:
ALLIGATOR CREEK
END DESCRIPTION:
DSS Export Rating Curves= 0
DSS Export Rating Curve Sorted= 0
DSS Export Volume Flow Curves= 0
DXF OffsetX= 0
DXF OffsetY= 0
DXF ScaleX= 1
DXF ScaleY= 10

--- ALLIGATOR CREEK.p01 (plan) ---

Plan Title=Multiple Run
Short Identifier=Multiple
Geom File=g01
Flow File=f01
Subcritical Flow
K Sum by GR= 0
Std Step Tol= 0.01
Critical Tol= 0.01
Num of Std Step Trials= 20
Max Error Tol= 0.3
Flow Tol Ratio= 0.001
Split Flow NTrial= 30
Split Flow Tol= 0.02
Split Flow Ratio= 0.02
Log Output Level= 0
Friction Slope Method= 1
Unsteady Friction Slope Method= 2
Unsteady Bridges Friction Slope Method= 1
Parabolic Critical Depth
Global Vel Dist=  1 , 1 , 1
Global Log Level= 0
CheckData=True
Encroach Param= -1, 0, 0, 0
BEGIN DESCRIPTION:
Multiple Run
END DESCRIPTION:

--- ALLIGATOR CREEK.f01 (steady flow) ---

Flow Title=Multiple
Number of Profiles=7
Profile Names=10-year,25-year,50-year,1pct_min,100-year,1pct_plu,500-year
River Rch & RM= ALLIGATOR CREEK,Reach-1,80826
    1106    1857    2564    1714    3421    6825    6022
River Rch & RM= ALLIGATOR CREEK,Reach-1,79100
    1687    2895    4057    2748    5484   10942    9919
River Rch & RM= ALLIGATOR CREEK,Reach-1,75061
    1675    2879    4037    2736    5459   10893    9887
River Rch & RM= ALLIGATOR CREEK,Reach-1,72760
    2620    4595    6531    4479    8936   17831   16577
River Rch & RM= ALLIGATOR CREEK,Reach-1,67827
    2627    4607    6548    4491    8960   17877   16621
River Rch & RM= ALLIGATOR CREEK,Reach-1,67393
    3110    5497    7854    5411   10797   21543   20219
River Rch & RM= ALLIGATOR CREEK,Reach-1,66914
    3700    6524    9302    6389   12747   25434   23718
River Rch & RM= ALLIGATOR CREEK,Reach-1,56430
    3663    6417    9107    6224   12418   24778   22876
River Rch & RM= ALLIGATOR CREEK,Reach-1,47475
    3922    6886    9789    6699   13366   26668   24688
River Rch & RM= ALLIGATOR CREEK,Reach-1,45897
    3856    6738    9546    6509   12987   25913   23817
River Rch & RM= ALLIGATOR CREEK,Reach-1,40389
    4266    7464   10583    7218   14403   28737   26431
River Rch & RM= ALLIGATOR CREEK,Reach-1,37153
    4480    7853   11149    7614   15191   30311   27942
River Rch & RM= ALLIGATOR CREEK,Reach-1,31680
    4452    7775   11010    7497   14959   29848   27361
River Rch & RM= ALLIGATOR CREEK,Reach-1,26807
    4491    7824   11062    7519   15003   29934   27340
River Rch & RM= ALLIGATOR CREEK,Reach-1,23818
    4475    7770   10957    7428   14821   29572   26864
River Rch & RM= ALLIGATOR CREEK,Reach-1,18001
    4746    8240   11620    7875   15712   31350   28458
River Rch & RM= ALLIGATOR CREEK,Reach-1,12805
    4703    8153   11485    7775   15512   30951   28034
River Rch & RM= ALLIGATOR CREEK,Reach-1,10077
    4461    7713   10848    7337   14640   29210   26433
River Rch & RM= ALLIGATOR CREEK,Reach-1,6841
    5045    8751   12334    8352   16664   33248   30129
River Rch & RM= ALLIGATOR CREEK,Reach-1,5111
    4555    7861   11042    7457   14880   29689   26787
Boundary for River Rch & Prof#=ALLIGATOR CREEK,Reach-1,1
Up Type=0
Dn Type=3
Dn Slope=0.005
Boundary for River Rch & Prof#=ALLIGATOR CREEK,Reach-1,2
Up Type=0
Dn Type=3
Dn Slope=0.005
Boundary for River Rch & Prof#=ALLIGATOR CREEK,Reach-1,3
Up Type=0
Dn Type=3
Dn Slope=0.005
Boundary for River Rch & Prof#=ALLIGATOR CREEK,Reach-1,4
Up Type=0
Dn Type=3
Dn Slope=0.005
Boundary for River Rch & Prof#=ALLIGATOR CREEK,Reach-1,5
Up Type=0
Dn Type=3
Dn Slope=0.005
Boundary for River Rch & Prof#=ALLIGATOR CREEK,Reach-1,6
Up Type=0
Dn Type=3
Dn Slope=0.005
Boundary for River Rch & Prof#=ALLIGATOR CREEK,Reach-1,7
Up Type=0
Dn Type=3
Dn Slope=0.005

--- ALLIGATOR CREEK.g01 (geometry) ---

Geom Title=Existing Conditions
Program Version=4.10

River Reach=ALLIGATOR CREEK ,Reach-1
Reach XY= 30
        2257925.       13838925.      2258918.79      13836532.8
      2260819.14     13836972.95      2262322.83     13835769.56
      2262022.77      13832730.9      2260282.53     13828925.01
      2260388.22     13827961.33      2261441.67     13827858.61
      2262872.74     13825919.06      2262026.22      13824914.5
      2262421.46     13823476.47      2261125.08      13821790.4
      2262721.56     13820723.78      2262578.75     13818326.55
      2264317.68      13816174.9      2263328.53     13815226.46
      2265267.19     13814328.41        2264525.       13813275.
      2269177.45     13812169.54      2269661.76     13810788.61
      2271831.05      13809917.5       2274561.7      13806888.4
      2276927.43     13806069.48      2277576.45     13805078.53
        2280725.     13806267.44       2282784.7     13805564.24
      2286521.45     13799223.53       2286430.8      13797722.7
      2288614.48     13796234.79        2289825.       13793325.

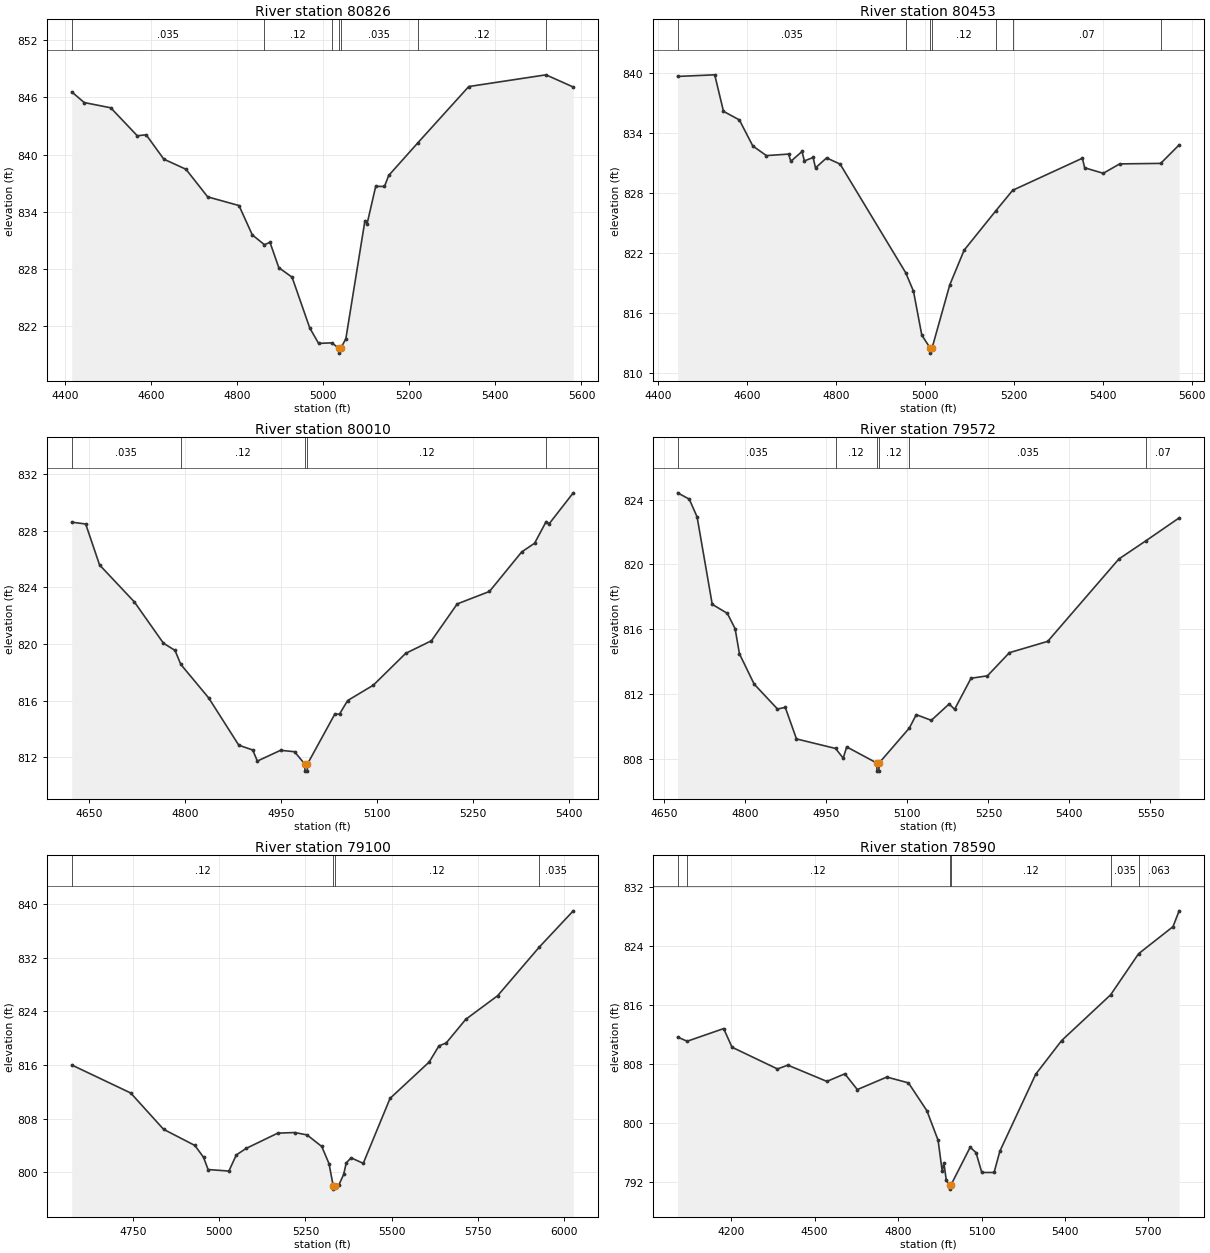
Type RM Length L Ch R = 1 ,80826   ,373,373,373
BEGIN DESCRIPTION:
X18024
END DESCRIPTION:
XS GIS Cut Line= 3
      2258493.22     13839033.33      2257873.42      13838887.5
      2257352.62     13838798.96
#Sta/Elev= 30
    4416  846.58    4445  845.46  4506.6  844.91  4568.3  841.97  4588.8  842.08
  4629.9  839.52  4681.3  838.46  4731.8  835.56  4804.5  834.65  4835.4  831.57
  4863.6  830.54  4876.5  830.79    4897  828.13  4927.8  827.13  4968.9   821.8
  4989.5  820.18  5020.1  820.24  5036.7  819.66    5037  819.16  5040.7  819.66
  5052.7  820.66  5097.1  833.07  5102.2  832.76  5122.1  836.67  5142.4  836.65
  5152.3  837.81  5219.3   841.2  5338.2  847.14  5517.6  848.37    5581  847.09
#Mann= 7 ,-1 , 0
    4416    .035       0  4863.6     .12       0  5020.1    .035       0
  5036.7     .05       0  5040.7    .035       0  5219.3     .12       0
  5517.6    .035       0
Bank Sta=5036.7,5040.7
XS Rating Curve= 0 ,0
Exp/Cntr=0.3,0.1

Type RM Length L Ch R = 1 ,80453   ,443,443,443
BEGIN DESCRIPTION:
ALLIGATOR CREEK 196.0
END DESCRIPTION:
XS GIS Cut Line= 3
      2258592.19     13838767.71        2258075.       13838575.
      2257514.92     13838439.79
#Sta/Elev= 30
  4443.8  839.69  4527.3  839.85    4547   836.2  4582.7  835.34    4613  832.73
  4643.6  831.77  4693.3  831.92  4698.6   831.2  4723.6  832.18    4729  831.24
  4748.6  831.58    4754  830.54  4778.9  831.54  4809.3  830.92  4956.9  820.05
  4974.4   818.2  4993.1   813.8  5012.1  812.51  5012.3  812.01  5016.1  812.51
    5056  818.84  5088.3  822.31  5159.4  826.24  5197.5   828.3  5354.3  831.51
  5359.4  830.55  5401.3     830  5438.1  830.94  5530.4  830.99  5571.9  832.84
#Mann= 7 ,-1 , 0
  4443.8    .035       0  4956.9     .12       0  5012.1     .05       0
  5016.1     .12       0  5159.4    .035       0  5197.5     .07       0
  5530.4    .035       0
Bank Sta=5012.1,5016.1
XS Rating Curve= 0 ,0
Exp/Cntr=0.3,0.1

Type RM Length L Ch R = 1 ,80010   ,438,438,438
BEGIN DESCRIPTION:
ALLIGATOR CREEK 195.0
END DESCRIPTION:
XS GIS Cut Line= 3
      2258475.01       13838325.        2258125.       13838175.
      2257725.01       13838225.
#Sta/Elev= 30
    4623   828.6  4644.8  828.47  4666.5  825.58  4720.9  822.97  4766.3  820.06
  4784.4  819.55  4793.5  818.56    4837   816.2  4884.1  812.86  4905.9  812.52
  4913.1  811.74  4949.4   812.5  4971.2   812.4  4987.2  811.53  4987.5  811.03
  4991.1  811.03  4991.4  811.53    5034  815.04  5041.6  815.06  5054.2  816.01
  5094.5   817.1  5144.9  819.34  5185.2  820.23  5225.5  822.83  5275.9  823.71
  5326.3   826.5  5346.4  827.11  5364.5  828.64  5369.1  828.48  5406.9  830.67
#Mann= 5 ,-1 , 0
    4623    .035       0  4793.5     .12       0  4987.2     .05       0
  4991.4     .12       0  5364.5    .035       0
Bank Sta=4987.2,4991.4
XS Rating Curve= 0 ,0
Exp/Cntr=0.3,0.1

Type RM Length L Ch R = 1 ,79572   ,472,472,472
BEGIN DESCRIPTION:
ALLIGATOR CREEK 194.0
END DESCRIPTION:
XS GIS Cut Line= 3
      2258575.02     13838075.03        2258375.       13837825.
      2257774.97     13837925.01
#Sta/Elev= 30
  4674.6  824.42  4696.2  824.03  4710.7  822.93  4738.7  817.53  4766.7  816.97
  4781.1  816.02  4789.1  814.47  4816.3   812.6  4859.5  811.06  4873.9  811.16
  4894.7  809.21  4967.1  808.62  4981.2  808.02  4987.6  808.72  5043.4  807.72
  5043.7  807.22  5047.3  807.22  5047.6  807.72  5103.8  809.89  5116.4  810.71
  5144.3  810.36  5177.3  811.37  5187.4  811.04  5217.8  812.96  5248.2  813.11
  5288.8  814.54  5359.8  815.24  5491.5  820.33  5541.3  821.45  5603.1  822.87
#Mann= 6 ,-1 , 0
  4674.6    .035       0  4967.1     .12       0  5043.4     .05       0
  5047.6     .12       0  5103.8    .035       0  5541.3     .07       0
Bank Sta=5043.4,5047.6
XS Rating Curve= 0 ,0
Exp/Cntr=0.3,0.1

Type RM Length L Ch R = 1 ,79100   ,510,510,510
BEGIN DESCRIPTION:
ALLIGATOR CREEK 193.0
END DESCRIPTION:
XS GIS Cut Line= 3
      2258724.99     13837824.97        2258575.       13837425.
      2257824.99     13836724.99
#Sta/Elev= 30
  4572.8  816.01  4743.6  811.84  4838.9  806.43  4929.7  804.02  4954.6  802.26
  4967.9  800.44  5028.1  800.21  5049.6  802.61  5077.9  803.58  5169.7  805.86
  5219.1  805.95  5254.7  805.59  5297.2  803.87  5318.2  801.32  5330.3  798.02
  5330.6  797.52  5334.5  798.02  5346.6  798.13  5360.7  799.72  5368.1  801.43
  5382.2  802.18  5417.4  801.36  5495.1  811.04  5608.4  816.45  5636.8  818.86
  5657.8  819.29  5714.4  822.81  5806.8  826.33  5926.9  833.54  6025.9  838.97
#Mann= 4 ,-1 , 0
  4572.8     .12       0  5330.3     .05       0  5334.5     .12       0
  5926.9    .035       0
Bank Sta=5330.3,5334.5
XS Rating Curve= 0 ,0
Exp/Cntr=0.3,0.1

Type RM Length L Ch R = 1 ,78590   ,385,385,385
BEGIN DESCRIPTION:
ALLIGATOR CREEK 192.0
END DESCRIPTION:
XS GIS Cut Line= 4
      2259039.32     13837900.04      2258986.79     13837262.37
      2258805.71     13837085.41      2258066.14     13836554.17
#Sta/Elev= 30
  4007.1   811.7  4041.5  811.13  4172.7  812.85  4202.8  810.32  4366.3  807.37
  4403.5  807.89  4543.9  805.68  4608.5  806.71  4653.4  804.57  4759.5  806.27
  4837.3  805.48  4903.6   801.7  4943.9  797.69  4958.6  793.51  4964.8  794.58
  4973.3  792.29  4985.1  791.56  4985.3  791.06  4989.3  791.56  5059.3  796.75
  5080.2  796.02    5101  793.32  5145.2  793.32  5166.1  796.22    5295  806.66
  5388.3  811.23  5564.3  817.43  5664.9  823.01  5788.6  826.68  5810.7  828.83
#Mann= 6 ,-1 , 0
  4007.1    .035       0  4041.5     .12       0  4985.1     .05       0
  4989.3     .12       0  5564.3    .035       0  5664.9    .063       0
Bank Sta=4985.1,4989.3
XS Rating Curve= 0 ,0
Exp/Cntr=0.3,0.1

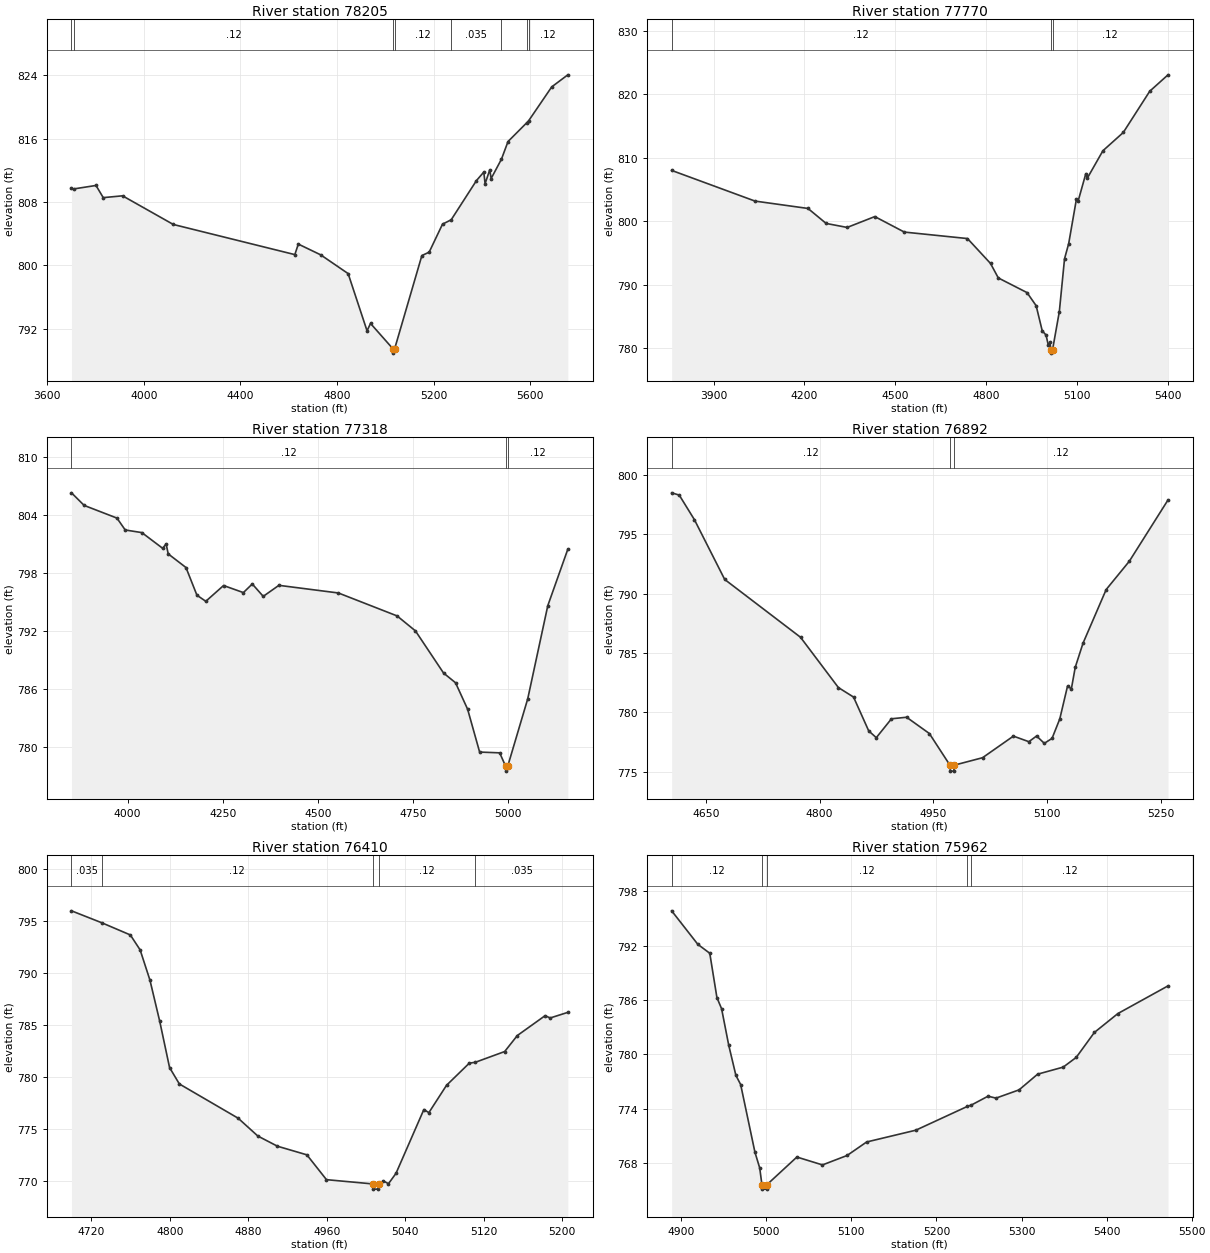
Type RM Length L Ch R = 1 ,78205   ,435,435,435
BEGIN DESCRIPTION:
ALLIGATOR CREEK 191.0
END DESCRIPTION:
XS GIS Cut Line= 4
      2259080.98     13837876.54      2259089.11     13837001.81
        2258825.       13836675.      2258113.05     13836408.35
#Sta/Elev= 30
  3700.5  809.71  3709.9  809.65    3802  810.09    3832  808.55    3912  808.78
  4122.1  805.16  4625.3  801.35  4639.7  802.68  4732.4  801.32    4846  798.95
  4924.3  791.72  4938.7  792.65  5032.9   789.4  5033.3   788.9  5038.1   789.4
  5151.3  801.23  5181.5  801.66  5236.8   805.2  5272.7  805.75  5377.4  810.71
  5407.7  811.78  5413.1  810.31  5432.6  812.08    5438  810.96  5480.8  813.41
    5508  815.64  5585.8  818.02  5593.3  818.26  5689.1  822.55  5755.7  824.07
#Mann= 8 ,-1 , 0
  3700.5    .035       0  3709.9     .12       0  5032.9     .05       0
  5038.1     .12       0  5272.7    .035       0  5480.8    .063       0
  5585.8    .035       0  5593.3     .12       0
Bank Sta=5032.9,5038.1
XS Rating Curve= 0 ,0
Exp/Cntr=0.3,0.1

Type RM Length L Ch R = 1 ,77770   ,452,452,452
BEGIN DESCRIPTION:
ALLIGATOR CREEK 190.0
END DESCRIPTION:
XS GIS Cut Line= 4
      2259104.42     13837746.35      2259225.27     13837040.77
        2259175.       13836525.      2259040.08     13836142.67
#Sta/Elev= 30
  3761.8  808.02  4037.1  803.19  4212.1  802.03  4272.1  799.67  4341.5  799.04
  4432.8  800.75  4530.3  798.31  4738.9  797.29    4815  793.37  4840.7  791.09
  4935.6  788.78  4965.7  786.72  4985.8  782.77  4998.5  782.09    5006  780.47
  5011.3  780.97  5014.4  779.75  5014.8  779.25  5019.8  779.75  5042.3  785.78
  5059.5  794.11  5073.2  796.49  5098.8  803.51  5104.1  803.14  5129.8  807.51
  5135.1  806.83  5186.3  811.12  5253.5  813.99    5341  820.49  5401.3  823.07
#Mann= 3 ,-1 , 0
  3761.8     .12       0  5014.4     .05       0  5019.8     .12       0
Bank Sta=5014.4,5019.8
XS Rating Curve= 0 ,0
Exp/Cntr=0.3,0.1

Type RM Length L Ch R = 1 ,77318   ,426,426,426
BEGIN DESCRIPTION:
ALLIGATOR CREEK 189.0
END DESCRIPTION:
XS GIS Cut Line= 4
      2259138.28     13837634.35      2259483.05     13836850.86
        2259575.       13836575.        2259525.     13836424.99
#Sta/Elev= 30
  3852.6  806.29  3885.9  804.99  3972.1  803.68  3993.9  802.45  4037.6  802.18
  4092.2  800.56  4101.4  801.01  4106.9  799.98  4153.6  798.57  4182.4  795.71
  4205.7  795.08  4252.4  796.71  4304.5  795.98  4327.9  796.87  4356.7  795.59
  4397.9  796.73  4554.3  795.94  4708.6  793.57  4756.9  792.02  4830.7  787.67
  4862.3  786.66    4894  783.93  4925.6   779.5  4978.3  779.42    4994  778.03
  4994.4  777.53  4999.4  778.03  5052.1  785.01  5104.8  794.63  5157.5  800.47
#Mann= 3 ,-1 , 0
  3852.6     .12       0    4994     .05       0  4999.4     .12       0
Bank Sta=4994,4999.4
XS Rating Curve= 0 ,0
Exp/Cntr=0.3,0.1

Type RM Length L Ch R = 1 ,76892   ,482,482,482
BEGIN DESCRIPTION:
ALLIGATOR CREEK 188.0
END DESCRIPTION:
XS GIS Cut Line= 3
        2259925.     13837174.96        2259925.       13836775.
        2259875.     13836525.01
#Sta/Elev= 30
  4604.7  798.49  4614.7   798.3  4634.7  796.23  4674.7  791.19  4774.7  786.32
  4824.7  782.08  4844.7  781.28  4864.7  778.43  4874.7  777.86  4894.7  779.45
  4914.7  779.58  4944.7  778.21  4971.9  775.54  4972.4  775.04    4977  775.04
  4977.4  775.54  5014.9  776.17  5055.6  777.99    5076  777.52  5086.2     778
  5096.4  777.38  5106.6   777.8  5116.8  779.44    5127   782.2  5132.1  781.98
  5137.2  783.79  5147.4  785.81    5178  790.34  5208.6  792.73  5259.6  797.89
#Mann= 3 ,-1 , 0
  4604.7     .12       0  4971.9     .05       0  4977.4     .12       0
Bank Sta=4971.9,4977.4
XS Rating Curve= 0 ,0
Exp/Cntr=0.3,0.1

Type RM Length L Ch R = 1 ,76410   ,448,448,448
BEGIN DESCRIPTION:
ALLIGATOR CREEK 187.0
END DESCRIPTION:
XS GIS Cut Line= 3
        2260375.     13837174.99        2260375.       13836875.
      2260325.01     13836675.04
#Sta/Elev= 30
  4699.6     796  4730.5  794.85  4759.6  793.68  4769.6  792.24  4779.6  789.33
  4789.6  785.36  4799.6  780.92  4809.6  779.34  4869.6  776.04  4889.6  774.33
  4909.6  773.35  4939.6  772.52  4959.6  770.13  5006.9  769.72  5007.4  769.22
  5012.3  769.22  5012.8  769.72  5017.6  770.01  5022.8  769.74  5030.5  770.74
  5058.9  776.88    5064  776.58    5082  779.21  5105.2  781.34  5111.5  781.43
  5141.3  782.46  5154.2     784  5182.5  785.91  5187.7  785.69  5205.7  786.23
#Mann= 5 ,-1 , 0
  4699.6    .035       0  4730.5     .12       0  5006.9     .05       0
  5012.8     .12       0  5111.5    .035       0
Bank Sta=5006.9,5012.8
XS Rating Curve= 0 ,0
Exp/Cntr=0.3,0.1

Type RM Length L Ch R = 1 ,75962   ,449,449,449
BEGIN DESCRIPTION:
ALLIGATOR CREEK 186.0
END DESCRIPTION:
XS GIS Cut Line= 3
      2260825.02     13837075.04        2260775.       13836975.
      2260525.02     13836575.04
#Sta/Elev= 30
  4888.7  795.83  4919.5  792.13  4933.5  791.15  4941.9  786.26  4947.4  785.03
  4955.8     781  4964.2  777.68  4969.8  776.67  4986.6   769.2  4992.2  767.47
  4994.8  765.63  4995.3  765.13  5000.3  765.13  5000.8  765.63  5035.9  768.67
    5066   767.8  5094.9  768.84  5117.9  770.33  5175.7  771.63  5236.2  774.25
  5241.1  774.41  5260.6  775.38    5270  775.17  5297.1  776.08  5318.9  777.81
    5349  778.59  5364.3  779.66  5385.6  782.41  5413.3   784.5  5472.2  787.55
#Mann= 5 ,-1 , 0
  4888.7     .12       0  4994.8     .05       0  5000.8     .12       0
  5236.2    .035       0  5241.1     .12       0
Bank Sta=4994.8,5000.8
XS Rating Curve= 0 ,0
Exp/Cntr=0.3,0.1

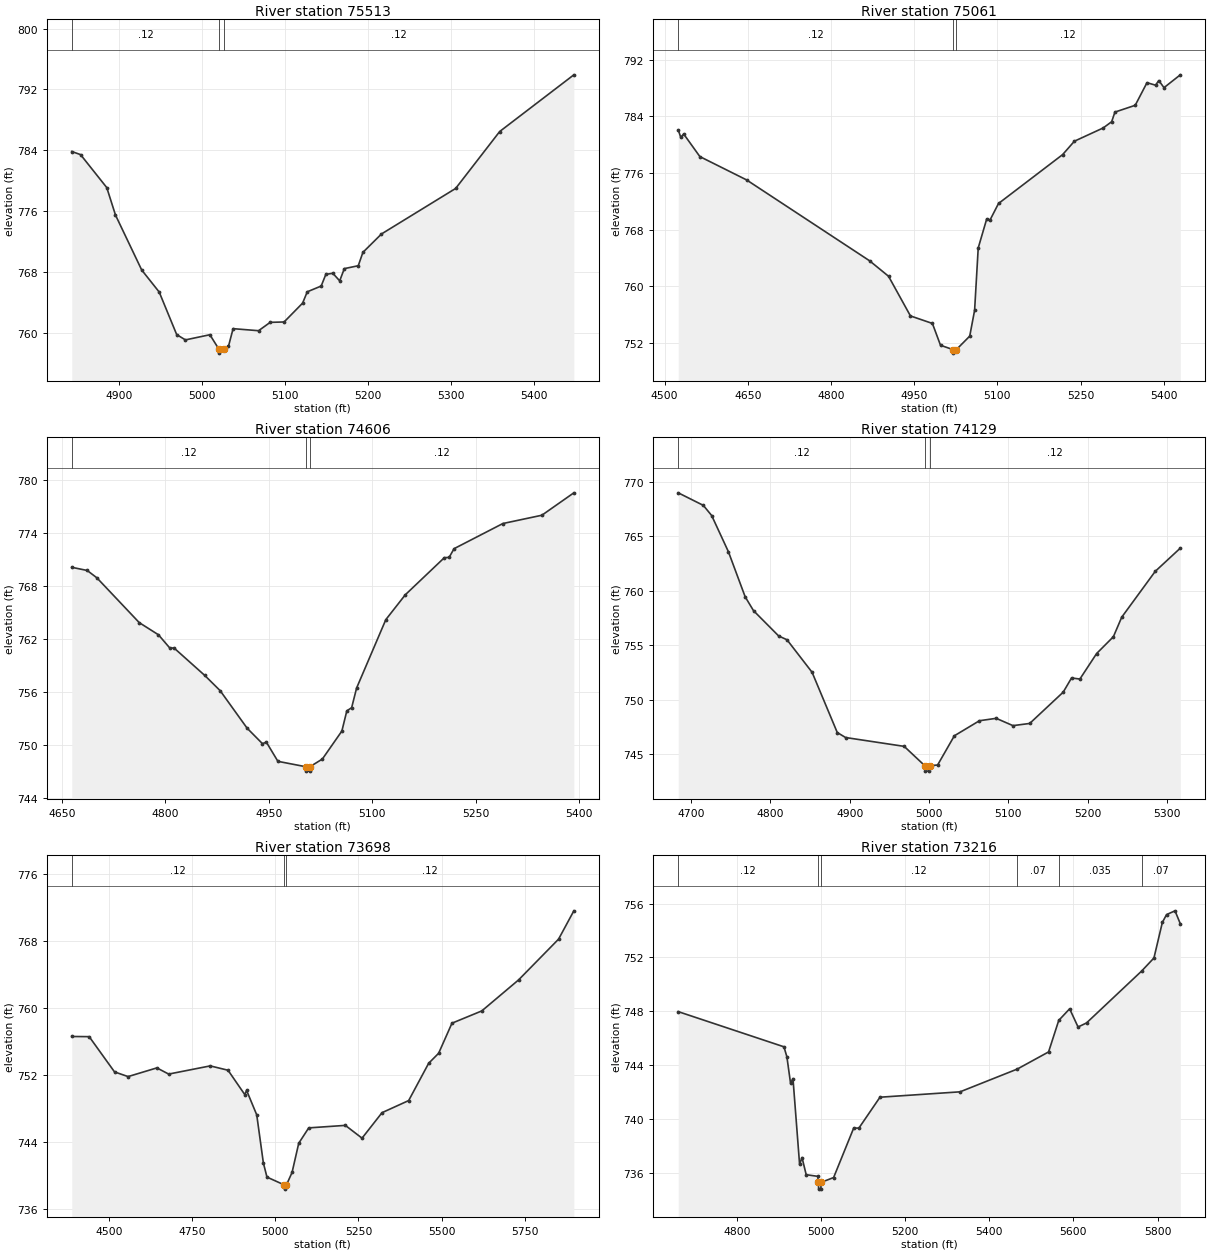
Type RM Length L Ch R = 1 ,75513   ,452,452,452
BEGIN DESCRIPTION:
ALLIGATOR CREEK 185.0
END DESCRIPTION:
XS GIS Cut Line= 3
        2261125.     13836825.01        2261075.       13836675.
      2260875.02     13836275.04
#Sta/Elev= 30
  4842.9  783.83  4853.5  783.42  4885.1  779.08  4895.6  775.47  4927.2  768.24
  4948.3  765.34  4969.4  759.74  4979.9  759.04  5009.4  759.72  5020.4   757.8
  5020.9   757.3  5026.4   757.8  5031.8  758.19  5037.4  760.52  5068.1  760.25
  5082.1  761.35  5098.9   761.4  5121.2  763.88  5126.8  765.37  5143.6  766.13
  5149.2  767.66  5157.6  767.81  5165.9  766.81  5171.5  768.42  5188.3   768.8
  5193.9  770.56  5216.3  772.98  5305.7  778.97  5358.8  786.46  5448.2  793.92
#Mann= 3 ,-1 , 0
  4842.9     .12       0  5020.4     .05       0  5026.4     .12       0
Bank Sta=5020.4,5026.4
XS Rating Curve= 0 ,0
Exp/Cntr=0.3,0.1

Type RM Length L Ch R = 1 ,75061   ,455,455,455
BEGIN DESCRIPTION:
ALLIGATOR CREEK 184.0
END DESCRIPTION:
XS GIS Cut Line= 3
      2261451.54     13836783.31        2261325.       13836325.
      2261097.36     13835960.38
#Sta/Elev= 30
  4524.5  782.07  4529.1  781.02  4534.3   781.5  4563.5  778.31  4647.7  775.02
  4869.4  763.61  4903.7  761.42  4943.2  755.82  4982.8  754.76  4997.4  751.68
  5019.9  751.07  5020.4  750.57    5026  751.07  5050.1  752.97  5058.9  756.62
  5065.4  765.41  5080.8  769.53  5086.7  769.36    5102  771.69  5217.6  778.59
  5238.8  780.48  5290.7  782.35    5306  783.23  5311.9  784.59  5348.5  785.55
  5369.7  788.74  5385.1  788.39    5391  789.04  5400.4  788.04  5429.8  789.85
#Mann= 3 ,-1 , 0
  4524.5     .12       0  5019.9     .05       0    5026     .12       0
Bank Sta=5019.9,5026
XS Rating Curve= 0 ,0
Exp/Cntr=0.3,0.1

Type RM Length L Ch R = 1 ,74606   ,477,477,477
BEGIN DESCRIPTION:
ALLIGATOR CREEK 183.0
END DESCRIPTION:
XS GIS Cut Line= 3
      2261875.01     13836475.03        2261725.       13836175.
      2261451.52     13835892.68
#Sta/Elev= 30
  4664.1  770.13  4686.5  769.77  4700.5  768.94    4762  763.86  4789.9  762.48
  4806.7  760.95  4812.3     761    4857  757.88  4879.4  756.15  4918.5   751.9
  4940.8  750.14  4946.4  750.32  4963.2  748.14  5003.5  747.53    5004  747.03
  5009.2  747.03  5009.7  747.53  5027.7   748.4    5056  751.57  5063.2  753.86
  5070.2  754.22  5077.4  756.45  5119.8   764.2  5148.1  767.02  5204.7  771.22
  5211.6  771.25  5218.8  772.24  5289.6  775.09  5346.2  776.03  5392.6  778.57
#Mann= 3 ,-1 , 0
  4664.1     .12       0  5003.5     .05       0  5009.7     .12       0
Bank Sta=5003.5,5009.7
XS Rating Curve= 0 ,0
Exp/Cntr=0.3,0.1

Type RM Length L Ch R = 1 ,74129   ,431,431,431
BEGIN DESCRIPTION:
ALLIGATOR CREEK 182.0
END DESCRIPTION:
XS GIS Cut Line= 3
      2262224.99     13836274.97        2262125.       13835975.
      2261825.03     13835875.01
#Sta/Elev= 30
  4684.1  768.98  4715.7  767.83  4726.2   766.9  4747.3  763.58  4768.4  759.45
  4778.9  758.18  4810.6  755.86  4821.1  755.51  4852.7  752.53  4884.4  747.01
  4894.9  746.55  4968.7  745.74  4994.6  743.97  4995.1  743.47  5000.3  743.47
  5000.8  743.97  5010.8  744.03  5031.9  746.71  5063.5  748.09  5084.6  748.31
  5105.7  747.64  5126.8  747.84    5169  750.71  5179.5  752.01    5190  751.91
  5211.1  754.25  5232.2  755.79  5242.7  757.58  5284.9  761.78  5316.5  763.91
#Mann= 3 ,-1 , 0
  4684.1     .12       0  4994.6     .05       0  5000.8     .12       0
Bank Sta=4994.6,5000.8
XS Rating Curve= 0 ,0
Exp/Cntr=0.3,0.1

Type RM Length L Ch R = 1 ,73698   ,482,482,482
BEGIN DESCRIPTION:
ALLIGATOR CREEK 181.0
END DESCRIPTION:
XS GIS Cut Line= 6
      2262672.93     13836041.19      2262592.19     13835728.65
      2262330.94     13835632.92        2262325.       13835625.
      2262317.55     13835627.98      2261429.08     13835645.29
#Sta/Elev= 30
  4389.1  756.59  4441.4  756.57  4517.5  752.35  4558.2  751.79  4644.6  752.83
  4680.1  752.09  4804.8  753.07  4858.3  752.55  4908.7  749.63    4914  750.14
  4944.5  747.21  4964.4  741.46  4975.2  739.76  5027.5  738.82    5028  738.32
  5033.7  738.82  5050.6  740.32  5070.6  743.81  5100.6  745.65  5210.6  745.95
  5260.7  744.42  5320.7  747.47  5400.7  748.92  5460.7  753.38  5490.7  754.58
  5530.7  758.18  5620.3  759.65  5730.7  763.36  5850.8  768.24  5896.7  771.63
#Mann= 3 ,-1 , 0
  4389.1     .12       0  5027.5     .05       0  5033.7     .12       0
Bank Sta=5027.5,5033.7
XS Rating Curve= 0 ,0
Exp/Cntr=0.3,0.1

Type RM Length L Ch R = 1 ,73216   ,456,456,456
BEGIN DESCRIPTION:
ALLIGATOR CREEK 180.0
END DESCRIPTION:
XS GIS Cut Line= 3
      2262618.22     13835345.83        2262325.       13835175.
      2261472.41     13835121.87
#Sta/Elev= 30
  4660.6  747.98  4911.9  745.37  4918.9  744.63  4927.6  742.67  4933.4  743.01
  4949.1  736.65  4954.9  737.15  4964.8  735.88  4992.1  735.76  4993.9  735.31
  4994.4  734.81  4999.7  734.81  5000.2  735.31    5030  735.67  5077.7  739.34
  5090.1  739.34  5140.2  741.63  5330.6  742.03  5466.7  743.72    5541  744.99
  5565.2  747.33  5591.1  748.19  5611.1  746.84  5631.2  747.14  5762.2  750.99
  5791.5  751.96  5811.5   754.6  5821.5  755.18  5841.6  755.46  5854.2   754.5
#Mann= 6 ,-1 , 0
  4660.6     .12       0  4993.9     .05       0  5000.2     .12       0
  5466.7     .07       0  5565.2    .035       0  5762.2     .07       0
Bank Sta=4993.9,5000.2
XS Rating Curve= 0 ,0
Exp/Cntr=0.3,0.1

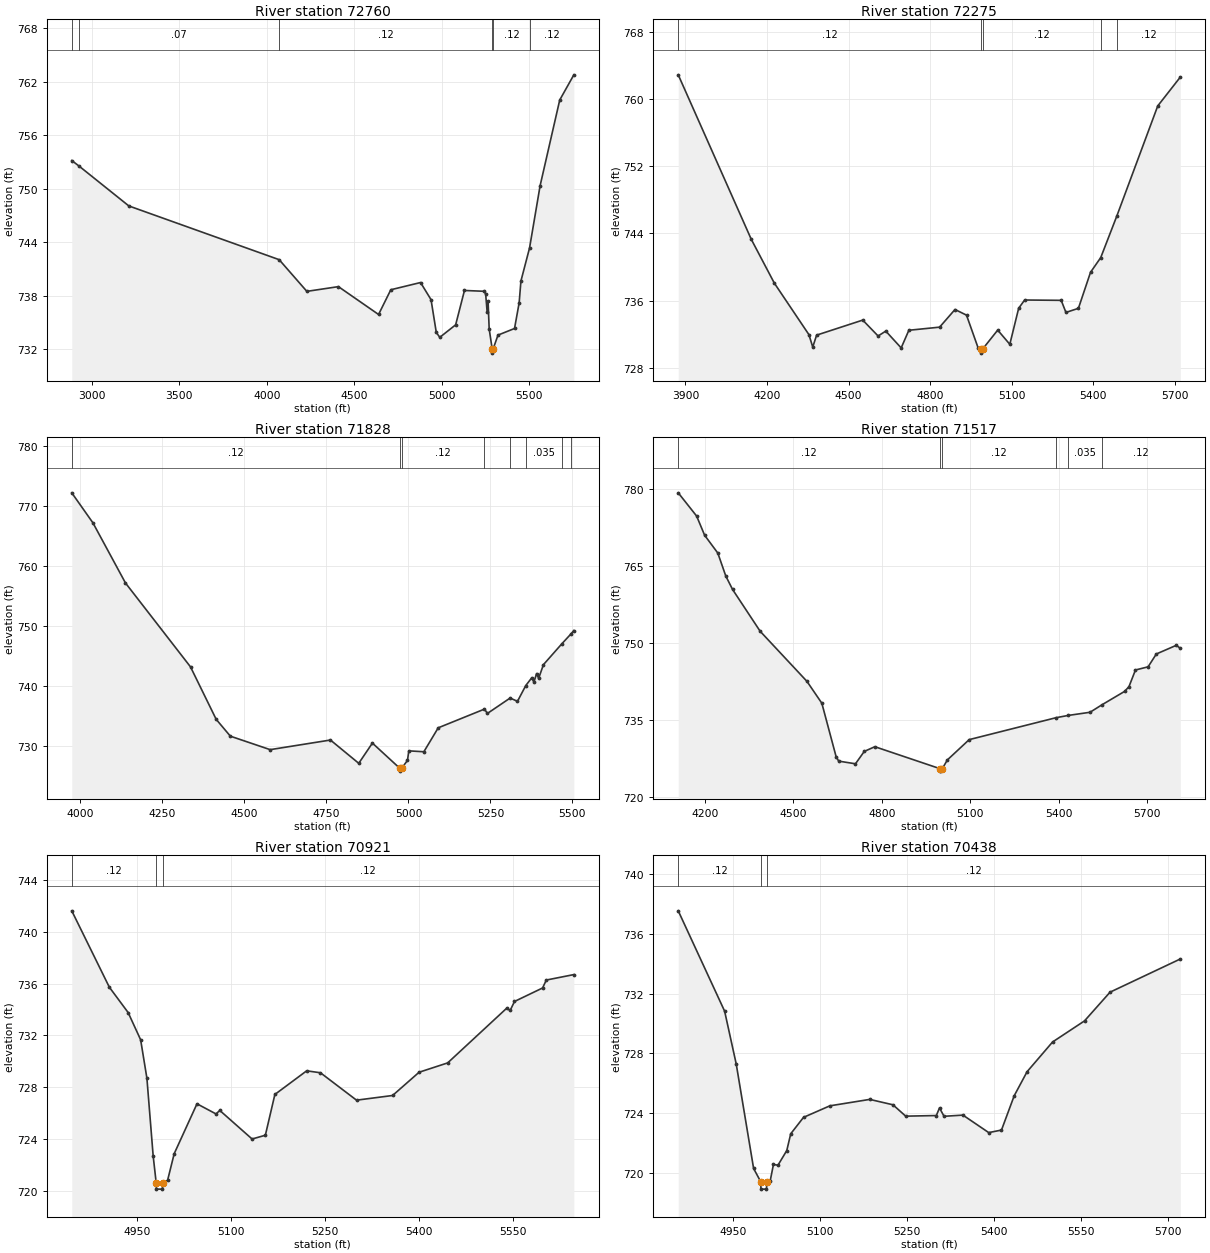
Type RM Length L Ch R = 1 ,72760   ,485,485,485
BEGIN DESCRIPTION:
ALLIGATOR CREEK 179.0
END DESCRIPTION:
XS GIS Cut Line= 4
      2264260.15     13835183.33      2263124.63     13834752.29
        2262225.       13834775.      2261475.03       13834675.
#Sta/Elev= 30
  2885.1  753.17  2928.5  752.52  3211.5  748.08  4071.1  742.06  4229.4  738.51
  4409.9  739.04  4639.5  735.92  4709.5  738.69  4879.6   739.5  4939.6  737.58
  4969.6  733.91  4989.6  733.36  5080.3  734.76  5130.7  738.61  5241.7  738.52
  5251.8  738.24  5260.6  736.15  5265.7  737.46    5272   734.3    5289  732.09
  5289.5  731.59  5295.3  732.09  5322.4  733.61    5417  734.35  5443.5  737.23
  5453.6  739.67    5503  743.38  5563.3  750.35  5675.5  759.95  5756.2  762.77
#Mann= 6 ,-1 , 0
  2885.1     .12       0  2928.5     .07       0  4071.1     .12       0
    5289     .05       0  5295.3     .12       0    5503     .12       0
Bank Sta=5289,5295.3
XS Rating Curve= 0 ,0
Exp/Cntr=0.3,0.1

Type RM Length L Ch R = 1 ,72275   ,447,447,447
BEGIN DESCRIPTION:
ALLIGATOR CREEK 178.0
END DESCRIPTION:
XS GIS Cut Line= 3
      2262924.97     13833525.03        2262125.       13834325.
      2261475.02     13834624.99
#Sta/Elev= 30
  3873.3  762.86    4142  743.29  4226.8  738.08  4354.1  731.95  4368.2  730.47
  4382.4  731.89  4552.1  733.68  4608.6  731.79  4636.9  732.37  4693.5  730.37
  4721.8  732.47  4834.9  732.84  4891.5  734.94  4933.9  734.27  4976.3   730.4
  4987.3  730.25  4987.8  729.75  4993.6  730.25  5048.7  732.49  5093.2   730.8
  5125.8  735.09  5147.8  736.07  5282.3  736.03  5299.7  734.59  5345.6  735.08
  5390.1  739.36  5427.8  741.12  5486.9  746.06  5637.5  759.16  5720.5  762.59
#Mann= 5 ,-1 , 0
  3873.3     .12       0  4987.3     .05       0  4993.6     .12       0
  5427.8    .035       0  5486.9     .12       0
Bank Sta=4987.3,4993.6
XS Rating Curve= 0 ,0
Exp/Cntr=0.3,0.1

Type RM Length L Ch R = 1 ,71828   ,311,311,311
BEGIN DESCRIPTION:
ALLIGATOR CREEK 177.0
END DESCRIPTION:
XS GIS Cut Line= 3
      2262775.03     13833274.98        2261975.       13833925.
      2261575.01     13834224.99
#Sta/Elev= 30
  3973.5  772.15    4038  767.16  4137.3  757.16  4335.5  743.22  4413.8   734.5
    4457   731.7  4578.4  729.46  4762.2  731.06  4848.5  727.19  4890.1  730.55
  4973.1  726.39  4973.6  725.89  4979.5  726.39  4997.1  727.67  5001.1  729.26
    5047  729.11  5090.8  733.09  5231.8   736.2  5240.8  735.48  5310.1  738.04
  5332.4  737.49  5357.8  740.12  5376.2  741.42  5382.4  740.67  5390.8  742.11
    5397  741.31  5411.6  743.59  5467.8  747.06  5494.4  748.63  5504.3  749.26
#Mann= 8 ,-1 , 0
  3973.5     .12       0  4973.1     .05       0  4979.5     .12       0
  5231.8    .035       0  5310.1     .12       0  5357.8    .035       0
  5467.8     .12       0  5494.4    .035       0
Bank Sta=4973.1,4979.5
XS Rating Curve= 0 ,0
Exp/Cntr=0.3,0.1

Type RM Length L Ch R = 1 ,71517   ,596,596,596
BEGIN DESCRIPTION:
ALLIGATOR CREEK 176.0
END DESCRIPTION:
XS GIS Cut Line= 3
      2262717.21     13833121.85      2262159.88     13833502.08
      2261275.02     13834024.99
#Sta/Elev= 30
    4110  779.33  4172.4   774.8  4199.5  771.06  4244.2  767.59  4271.3  763.11
  4294.3  760.49  4387.8  752.35  4546.4  742.59  4596.9  738.33  4645.3  727.92
  4654.1  727.04    4711  726.52  4740.8  728.93  4776.7  729.85  4996.5  725.59
    4997  725.09  5005.6  725.59  5022.7  727.28  5096.6  731.23  5390.9   735.5
  5431.8  735.94  5506.3  736.56  5548.3  738.07  5623.3  740.62  5638.3  741.54
  5660.4   744.8  5703.3  745.42  5731.2  747.92  5798.9  749.61  5812.5  749.03
#Mann= 6 ,-1 , 0
    4110     .12       0  4996.5     .05       0  5005.6     .12       0
  5390.9    .063       0  5431.8    .035       0  5548.3     .12       0
Bank Sta=4996.5,5005.6
XS Rating Curve= 0 ,0
Exp/Cntr=0.3,0.1

Type RM Length L Ch R = 1 ,70921   ,483,483,483
BEGIN DESCRIPTION:
ALLIGATOR CREEK 175.0
END DESCRIPTION:
XS GIS Cut Line= 3
      2262225.01       13833125.        2262075.       13833125.
      2261525.02     13833474.99
#Sta/Elev= 30
  4845.3   741.6  4905.3  735.72  4935.3  733.77  4955.3  731.67  4965.3  728.71
  4975.3  722.73  4980.1  720.67  4980.6  720.17    4990  720.17  4990.5  720.67
  4998.3  720.84  5008.9   722.9  5045.3  726.74  5075.7  725.96  5081.7  726.23
  5133.3  724.03  5154.5  724.32  5169.7  727.46  5220.5  729.28  5242.5  729.13
  5300.1  727.02  5357.7  727.38    5400  729.17  5445.7  729.89  5539.7  734.09
  5545.6  733.94  5552.4  734.62  5597.3  735.66  5603.2  736.27  5647.2  736.69
#Mann= 3 ,-1 , 0
  4845.3     .12       0  4980.1     .05       0  4990.5     .12       0
Bank Sta=4980.1,4990.5
XS Rating Curve= 0 ,0
Exp/Cntr=0.3,0.1

Type RM Length L Ch R = 1 ,70438   ,443,443,443
BEGIN DESCRIPTION:
ALLIGATOR CREEK 174.0
END DESCRIPTION:
XS GIS Cut Line= 3
      2262124.99       13832675.        2261975.       13832675.
      2261324.98     13832975.01
#Sta/Elev= 30
  4855.4  737.53  4935.4  730.82  4955.4  727.29  4985.4   720.3  4997.6  719.42
  4998.1  718.92  5007.6  718.92  5008.1  719.42  5014.1  719.49  5019.6  720.57
  5027.4  720.52  5042.6   721.5  5049.4  722.62  5071.5  723.72  5116.9  724.49
  5185.7  724.92  5225.7  724.56  5247.7   723.8  5300.5  723.84    5306  724.35
  5313.8  723.79  5346.4  723.87  5390.9   722.7  5412.9  722.87  5434.9  725.17
    5457  726.77    5501  728.76  5556.1  730.17  5600.1  732.09  5721.3  734.31
#Mann= 3 ,-1 , 0
  4855.4     .12       0  4997.6     .05       0  5008.1     .12       0
Bank Sta=4997.6,5008.1
XS Rating Curve= 0 ,0
Exp/Cntr=0.3,0.1

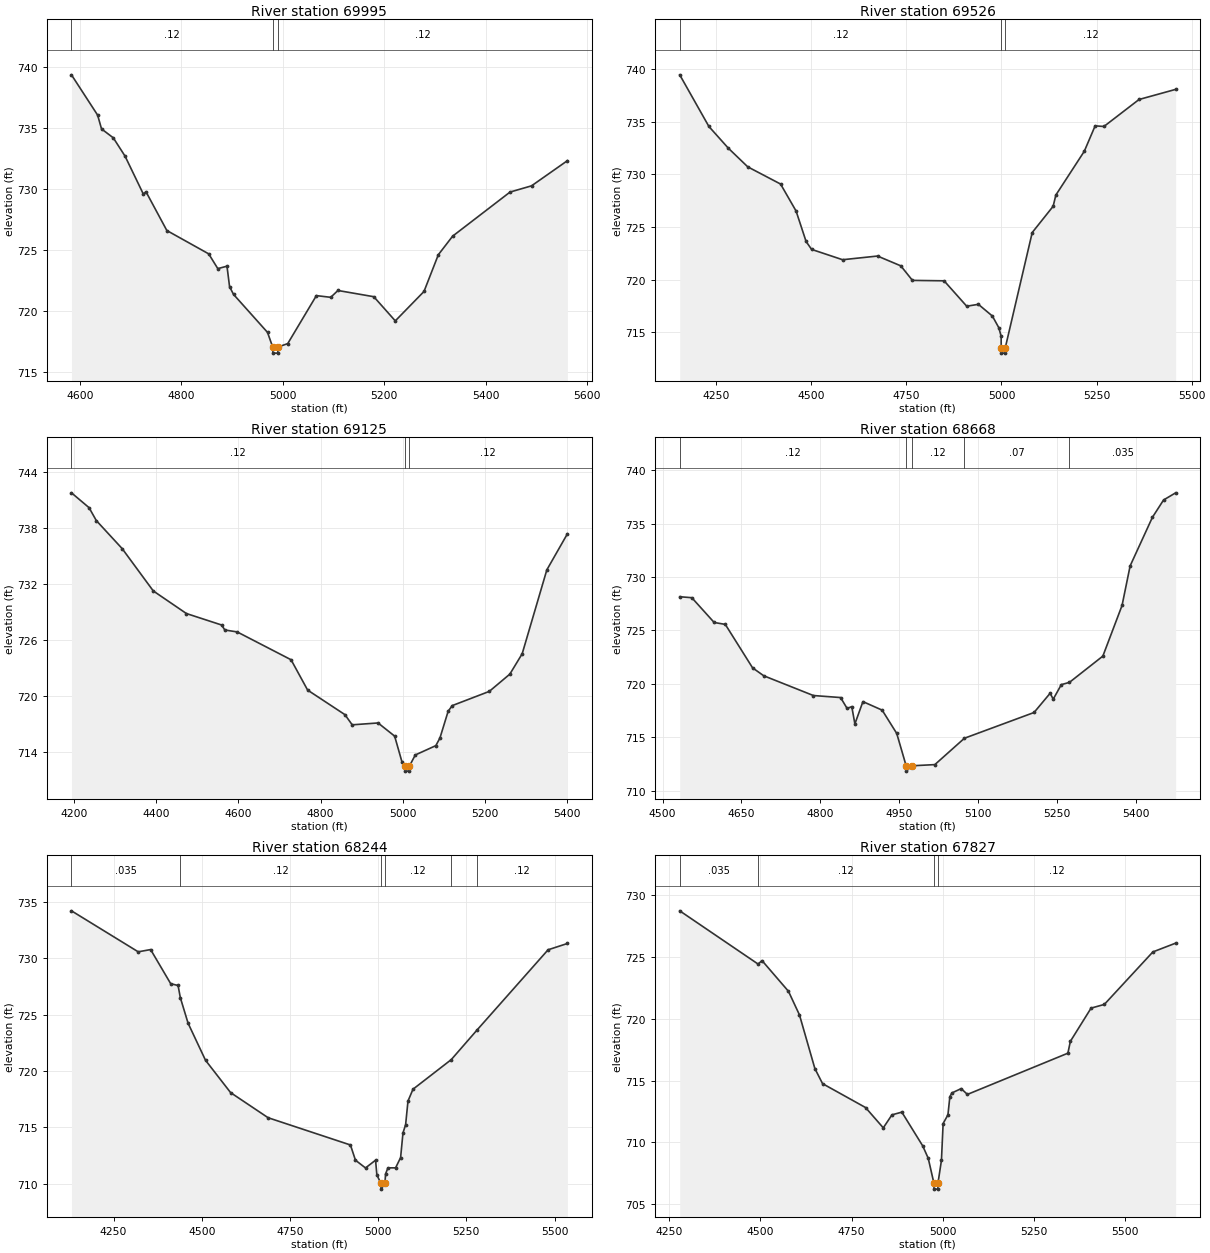
Type RM Length L Ch R = 1 ,69995   ,469,469,469
BEGIN DESCRIPTION:
ALLIGATOR CREEK 173.0
END DESCRIPTION:
XS GIS Cut Line= 3
      2262075.03     13832274.99        2261675.       13832375.
      2261275.02     13832774.98
#Sta/Elev= 30
  4583.4  739.37    4635  736.07  4642.7  734.94  4665.9  734.21  4689.1  732.71
  4725.2   729.6  4730.3   729.8  4771.5  726.62    4854  724.71    4872   723.5
  4890.1   723.7  4895.2  722.02    4903  721.39    4970  718.28  4980.2  717.08
  4980.7  716.58  4990.2  716.58  4990.7  717.08  5009.9  717.36  5066.4  721.29
  5094.7  721.15  5108.9  721.71  5179.6   721.2    5222  719.22  5278.6  721.63
  5306.9  724.64  5335.1  726.16  5448.3  729.77  5490.7  730.28  5561.4  732.34
#Mann= 3 ,-1 , 0
  4583.4     .12       0  4980.2     .05       0  4990.7     .12       0
Bank Sta=4980.2,4990.7
XS Rating Curve= 0 ,0
Exp/Cntr=0.3,0.1

Type RM Length L Ch R = 1 ,69526   ,401,401,401
BEGIN DESCRIPTION:
ALLIGATOR CREEK 172.0
END DESCRIPTION:
XS GIS Cut Line= 3
        2262075.       13832075.      2261290.09     13832231.25
      2260831.73     13832439.59
#Sta/Elev= 30
  4154.2  739.43  4230.9  734.53    4282  732.47  4333.1   730.7  4419.3  729.07
  4460.1  726.51  4486.4  723.62  4500.9  722.87  4582.4  721.89  4674.2  722.24
  4735.4  721.31    4766  719.93  4849.2  719.89  4908.7  717.48  4939.3  717.66
  4976.1  716.55  4993.1  715.44  4999.2  714.63  4999.4  713.53  4999.9  713.03
  5009.5  713.03    5010  713.53  5080.9  724.47  5135.9  726.96  5143.1  728.03
  5217.8  732.18  5246.3  734.59  5269.4  734.53  5361.7  737.09    5458  738.05
#Mann= 3 ,-1 , 0
  4154.2     .12       0  4999.4     .05       0    5010     .12       0
Bank Sta=4999.4,5010
XS Rating Curve= 0 ,0
Exp/Cntr=0.3,0.1

Type RM Length L Ch R = 1 ,69125   ,457,457,457
BEGIN DESCRIPTION:
ALLIGATOR CREEK 171.0
END DESCRIPTION:
XS GIS Cut Line= 3
      2262124.98       13832025.        2261325.       13831925.
        2260925.       13831925.
#Sta/Elev= 30
  4194.1  741.79  4236.9   740.2  4254.5  738.82  4317.5  735.81  4393.1  731.28
  4473.7  728.86  4559.4  727.63    4567   727.1  4597.2  726.89  4728.2  723.91
  4768.5  720.66  4859.2  718.03  4876.9  716.94  4939.8  717.14  4980.1  715.73
  4997.8  712.99    5005  712.48  5005.5  711.98  5015.1  711.98  5015.6  712.48
  5030.3  713.71  5080.3  714.71  5090.3  715.53  5110.3   718.4  5120.3     719
  5210.3  720.52  5260.3  722.37  5290.3  724.55  5350.3  733.54  5400.3   737.4
#Mann= 3 ,-1 , 0
  4194.1     .12       0    5005     .05       0  5015.6     .12       0
Bank Sta=5005,5015.6
XS Rating Curve= 0 ,0
Exp/Cntr=0.3,0.1

Type RM Length L Ch R = 1 ,68668   ,424,424,424
BEGIN DESCRIPTION:
ALLIGATOR CREEK 170.0
END DESCRIPTION:
XS GIS Cut Line= 3
      2261675.03     13831274.98        2261275.       13831525.
      2260875.03     13831774.98
#Sta/Elev= 30
  4532.7  728.16  4555.7  728.07  4598.2  725.75  4619.4  725.57  4671.3   721.5
  4692.5  720.76  4786.9  718.91  4838.7  718.72  4851.1   717.7    4860  717.87
  4865.9  716.25  4881.2  718.34  4917.8  717.54  4945.5  715.36  4963.4  712.33
  4963.9  711.83  4974.7  712.33    5018  712.44  5074.3  714.91  5206.7  717.32
  5237.3  719.12  5243.2  718.57  5258.6  719.93    5274  720.14  5337.6   722.6
  5374.1  727.34  5389.5  731.05  5431.9   735.6  5453.1  737.22  5476.1  737.89
#Mann= 5 ,-1 , 0
  4532.7     .12       0  4963.4     .05       0  4974.7     .12       0
  5074.3     .07       0    5274    .035       0
Bank Sta=4963.4,4974.7
XS Rating Curve= 0 ,0
Exp/Cntr=0.3,0.1

Type RM Length L Ch R = 1 ,68244   ,417,417,417
BEGIN DESCRIPTION:
ALLIGATOR CREEK 169.0
END DESCRIPTION:
XS GIS Cut Line= 3
      2261727.58     13830601.05        2261075.       13831175.
      2260717.15     13831575.03
#Sta/Elev= 30
  4130.7  734.23  4319.9  730.59  4355.1  730.79    4412  727.76  4432.9   727.6
  4439.3  726.52  4461.3  724.25  4510.7  720.96  4581.8  718.09  4688.1  715.86
  4921.5  713.44  4935.7  712.09  4964.2   711.4  4992.7  712.09  4996.4  710.79
  5007.9  710.02  5008.4  709.52  5019.2  710.02  5021.1  710.87  5027.8  711.41
  5049.5  711.41  5063.7  712.32  5070.4  714.51  5077.9  715.24  5084.6  717.34
  5098.8  718.39  5207.3  721.02    5281  723.67  5481.7  730.77  5536.5  731.33
#Mann= 6 ,-1 , 0
  4130.7    .035       0  4439.3     .12       0  5007.9     .05       0
  5019.2     .12       0  5207.3     .07       0    5281     .12       0
Bank Sta=5007.9,5019.2
XS Rating Curve= 0 ,0
Exp/Cntr=0.3,0.1

Type RM Length L Ch R = 1 ,67827   ,434,434,434
BEGIN DESCRIPTION:
ALLIGATOR CREEK 168.0
END DESCRIPTION:
XS GIS Cut Line= 3
      2261482.78     13830429.18        2260875.       13830825.
      2260665.08     13831423.97
#Sta/Elev= 30
  4278.8  728.71  4493.7  724.41  4504.5  724.69    4577  722.21  4607.2   720.3
  4649.4  715.97  4670.5  714.75  4788.4  712.82    4837  711.18  4860.8  712.23
  4887.9  712.45  4945.2  709.72  4960.3  708.72  4975.7  706.73  4976.2  706.23
  4986.6  706.23  4987.1  706.73  4996.5  708.55  5001.1  711.53  5014.3  712.23
  5019.6   713.7  5025.3     714  5050.6  714.35  5067.7  713.88  5343.2  717.21
  5350.1  718.17  5406.8  720.85  5443.2  721.15  5576.3  725.39  5638.8   726.1
#Mann= 4 ,-1 , 0
  4278.8    .035       0  4493.7     .12       0  4975.7     .05       0
  4987.1     .12       0
Bank Sta=4975.7,4987.1
XS Rating Curve= 0 ,0
Exp/Cntr=0.3,0.1