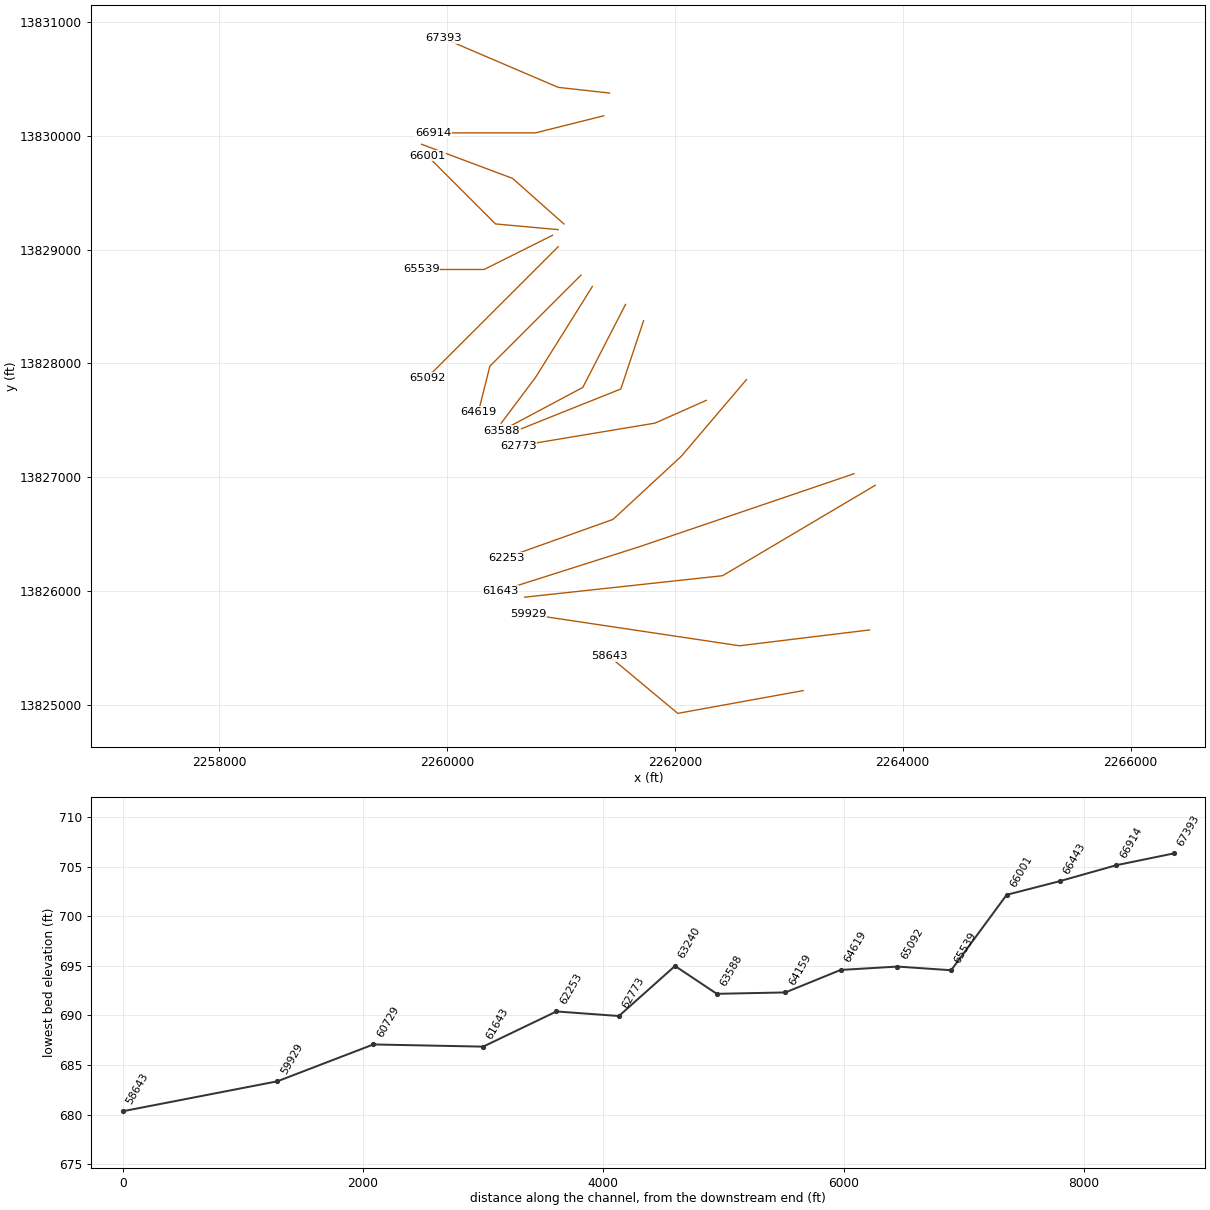
HEC-RAS study ALLIGATOR CREEK.prj: ALLIGATOR CREEK Base Level Engineering

--- ALLIGATOR CREEK.g01 (geometry) --- (continued)

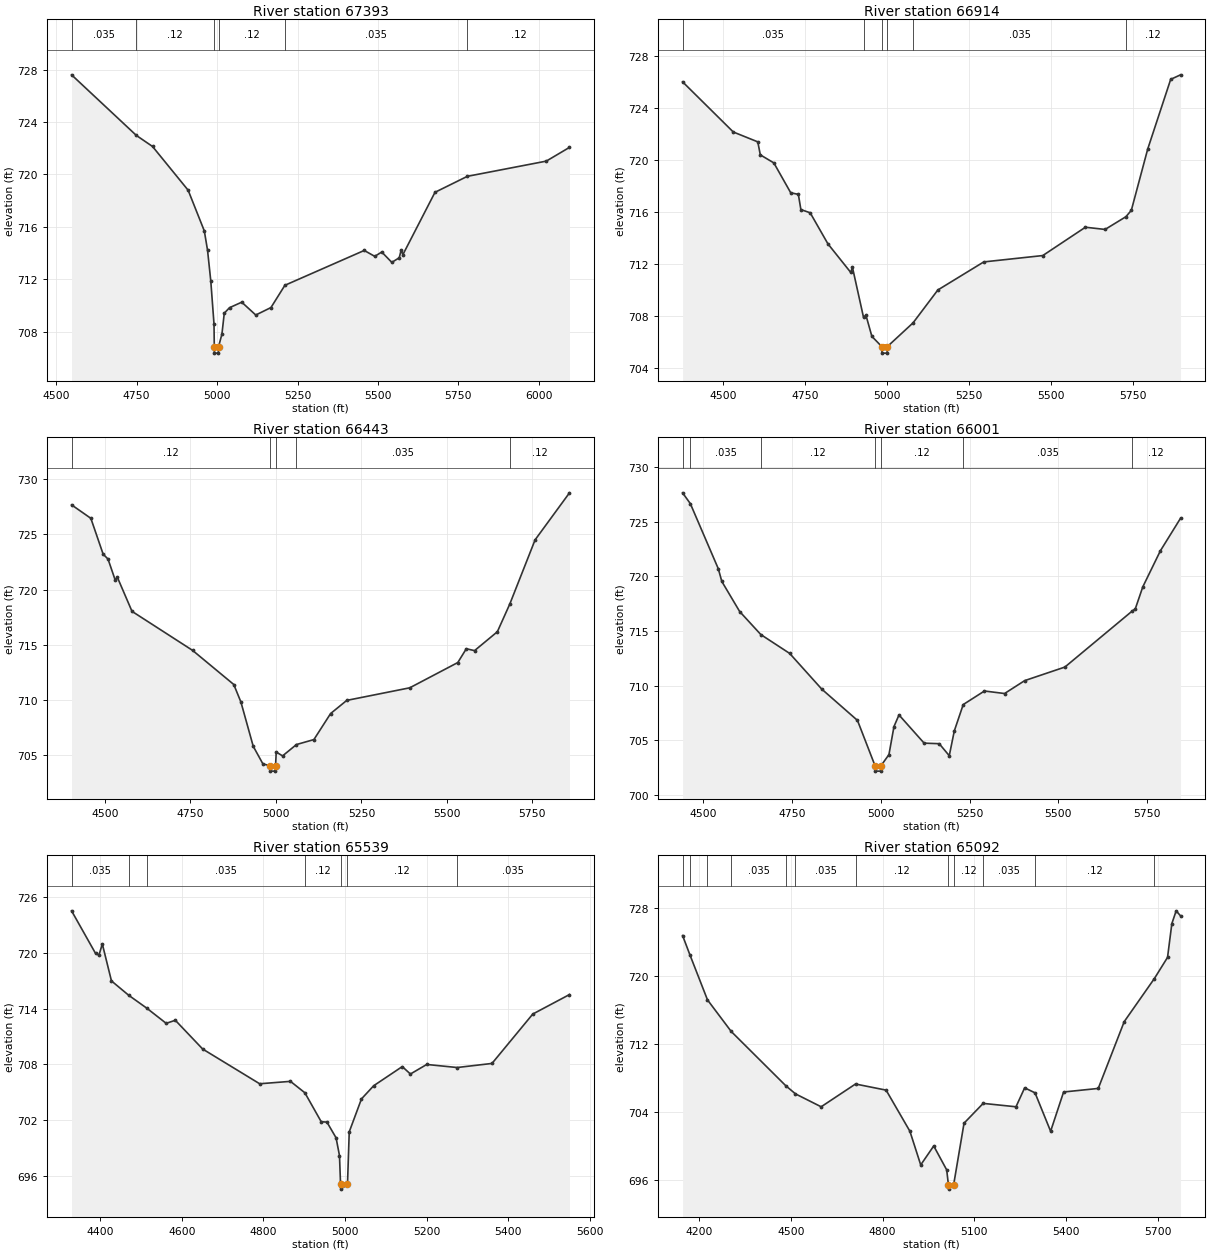
Type RM Length L Ch R = 1 ,67393   ,479,479,479
BEGIN DESCRIPTION:
ALLIGATOR CREEK 167.0
END DESCRIPTION:
XS GIS Cut Line= 3
      2261425.04       13830375.        2260975.       13830425.
      2259968.58     13830855.65
#Sta/Elev= 30
  4547.7   727.6  4749.2  722.97  4799.3  722.13    4910  718.79  4960.3  715.68
  4970.3  714.21  4980.4  711.86  4990.4  708.57  4991.3  706.85  4991.8  706.35
  5004.1  706.35  5004.6  706.85    5015   707.8  5022.3   709.4  5038.6  709.82
  5076.6  710.24  5120.2  709.26  5167.4  709.83  5210.7  711.53  5457.3  714.19
    5490  713.74  5511.7  714.07    5543  713.28  5566.1  713.63    5572  714.22
  5577.4  713.87  5677.2  718.63  5777.8  719.85    6023  721.01  6095.2  722.06
#Mann= 6 ,-1 , 0
  4547.7    .035       0  4749.2     .12       0  4991.3     .05       0
  5004.6     .12       0  5210.7    .035       0  5777.8     .12       0
Bank Sta=4991.3,5004.6
XS Rating Curve= 0 ,0
Exp/Cntr=0.3,0.1

Type RM Length L Ch R = 1 ,66914   ,471,471,471
BEGIN DESCRIPTION:
ALLIGATOR CREEK 166.0
END DESCRIPTION:
XS GIS Cut Line= 3
      2261374.96     13830174.99        2260775.       13830025.
      2259875.03       13830025.
#Sta/Elev= 30
    4377  726.04  4531.6  722.18  4606.3  721.42    4614  720.42  4655.3   719.8
  4706.8   717.5    4730  717.38  4737.7  716.21  4766.1  715.96  4820.2  713.57
  4889.8  711.37  4894.9  711.77  4928.7  707.92  4936.2  708.07  4954.2  706.45
  4984.5  705.66    4985  705.16  5000.8  705.16  5001.3  705.66  5079.8  707.49
  5155.4  710.02  5295.4  712.18  5475.4  712.67  5605.4  714.85  5665.4  714.68
  5728.9  715.66  5745.4  716.15  5795.4  720.87  5865.4  726.23  5895.4  726.58
#Mann= 6 ,-1 , 0
    4377    .035       0  4928.7     .12       0  4984.5     .05       0
  5001.3     .12       0  5079.8    .035       0  5728.9     .12       0
Bank Sta=4984.5,5001.3
XS Rating Curve= 0 ,0
Exp/Cntr=0.3,0.1

Type RM Length L Ch R = 1 ,66443   ,442,442,442
BEGIN DESCRIPTION:
ALLIGATOR CREEK 165.0
END DESCRIPTION:
XS GIS Cut Line= 3
      2261024.98     13829225.02        2260575.       13829625.
      2259774.96     13829925.02
#Sta/Elev= 30
  4402.2  727.68  4458.6  726.46  4494.6  723.21  4508.8  722.77  4529.7  720.88
  4536.4   721.1    4579  718.03  4756.3  714.49  4876.7   711.4  4897.6  709.81
  4933.6   705.8    4962   704.2    4982  704.05  4982.5  703.55  4998.4  703.55
  4998.9  704.05  5000.9  705.28  5019.4  704.93  5060.1  705.96  5111.1  706.41
    5160  708.77  5207.2  709.96  5391.4   711.1    5532  713.39  5556.9  714.64
    5581  714.47  5647.7  716.18  5684.2   718.7  5758.1  724.51  5858.7  728.77
#Mann= 5 ,-1 , 0
  4402.2     .12       0    4982     .05       0  4998.9     .12       0
  5060.1    .035       0  5684.2     .12       0
Bank Sta=4982,4998.9
XS Rating Curve= 0 ,0
Exp/Cntr=0.3,0.1

Type RM Length L Ch R = 1 ,66001   ,462,462,462
BEGIN DESCRIPTION:
ALLIGATOR CREEK 164.0
END DESCRIPTION:
XS GIS Cut Line= 3
      2260974.99       13829175.        2260425.       13829225.
      2259824.99     13829825.01
#Sta/Elev= 30
  4442.7  727.63  4464.5  726.64  4543.1  720.69  4553.1  719.52  4603.3  716.77
  4662.9  714.66  4743.9  712.94  4834.3  709.67  4934.7  706.81    4984  702.67
  4984.5  702.17  5000.4  702.17  5000.9  702.67  5023.2  703.68  5037.4  706.25
  5051.5  707.31  5122.2  704.73  5164.7  704.68  5192.9  703.58  5207.1  705.85
  5232.2  708.26  5291.9   709.5  5348.5  709.27  5405.1  710.45  5518.2  711.69
  5707.4  716.81  5716.2  717.01  5737.4  719.03  5786.9  722.33  5843.5   725.3
#Mann= 7 ,-1 , 0
  4442.7     .12       0  4464.5    .035       0  4662.9     .12       0
    4984     .05       0  5000.9     .12       0  5232.2    .035       0
  5707.4     .12       0
Bank Sta=4984,5000.9
XS Rating Curve= 0 ,0
Exp/Cntr=0.3,0.1

Type RM Length L Ch R = 1 ,65539   ,447,447,447
BEGIN DESCRIPTION:
ALLIGATOR CREEK 163.0
END DESCRIPTION:
XS GIS Cut Line= 3
      2260925.02     13829125.01        2260325.       13828825.
      2259775.04       13828825.
#Sta/Elev= 30
  4329.5  724.54  4388.2  719.96  4396.6  719.77    4405  720.96  4427.3  716.99
  4469.4  715.45  4513.7  714.06  4561.5  712.42  4583.9  712.75    4651  709.65
  4790.7  705.91  4866.2  706.17  4901.5  704.94  4941.6  701.82  4955.6  701.78
    4978  700.09  4986.4  698.17    4989  695.06  4989.5  694.56    5006  695.06
  5010.3  700.73  5040.3  704.28  5070.3   705.7  5140.3  707.76  5160.3  706.96
  5200.3  707.99  5274.9  707.66  5360.3   708.1  5460.3  713.42  5550.3  715.52
#Mann= 7 ,-1 , 0
  4329.5    .035       0  4469.4     .07       0  4513.7    .035       0
  4901.5     .12       0    4989     .05       0    5006     .12       0
  5274.9    .035       0
Bank Sta=4989,5006
XS Rating Curve= 0 ,0
Exp/Cntr=0.3,0.1

Type RM Length L Ch R = 1 ,65092   ,473,473,473
BEGIN DESCRIPTION:
ALLIGATOR CREEK 162.0
END DESCRIPTION:
XS GIS Cut Line= 3
      2260975.02     13829025.02        2260375.       13828425.
      2259824.98     13827874.98
#Sta/Elev= 30
  4146.9  724.77  4170.6  722.52  4228.2   717.2  4305.8  713.48  4483.6  707.11
  4515.6  706.14  4599.5  704.62  4711.7   707.3  4811.6  706.58  4889.4  701.74
  4924.7  697.78  4967.2  700.01  5009.6  697.19  5015.2  695.43  5015.7  694.93
  5032.2  695.43  5066.2  702.69  5128.7  705.02  5235.9  704.62  5264.2  706.85
  5298.1  706.26    5349  701.74  5391.4  706.36  5504.6  706.78  5589.4  714.64
  5687.9  719.71  5730.9   722.2    5745  726.18  5759.1  727.68  5773.3  727.09
#Mann= 12 ,-1 , 0
  4146.9     .12       0  4170.6    .035       0  4228.2     .07       0
  4305.8    .035       0  4483.6     .07       0  4515.6    .035       0
  4711.7     .12       0  5015.2     .05       0  5032.2     .12       0
  5128.7    .035       0  5298.1     .12       0  5687.9    .035       0
Bank Sta=5015.2,5032.2
XS Rating Curve= 0 ,0
Exp/Cntr=0.3,0.1

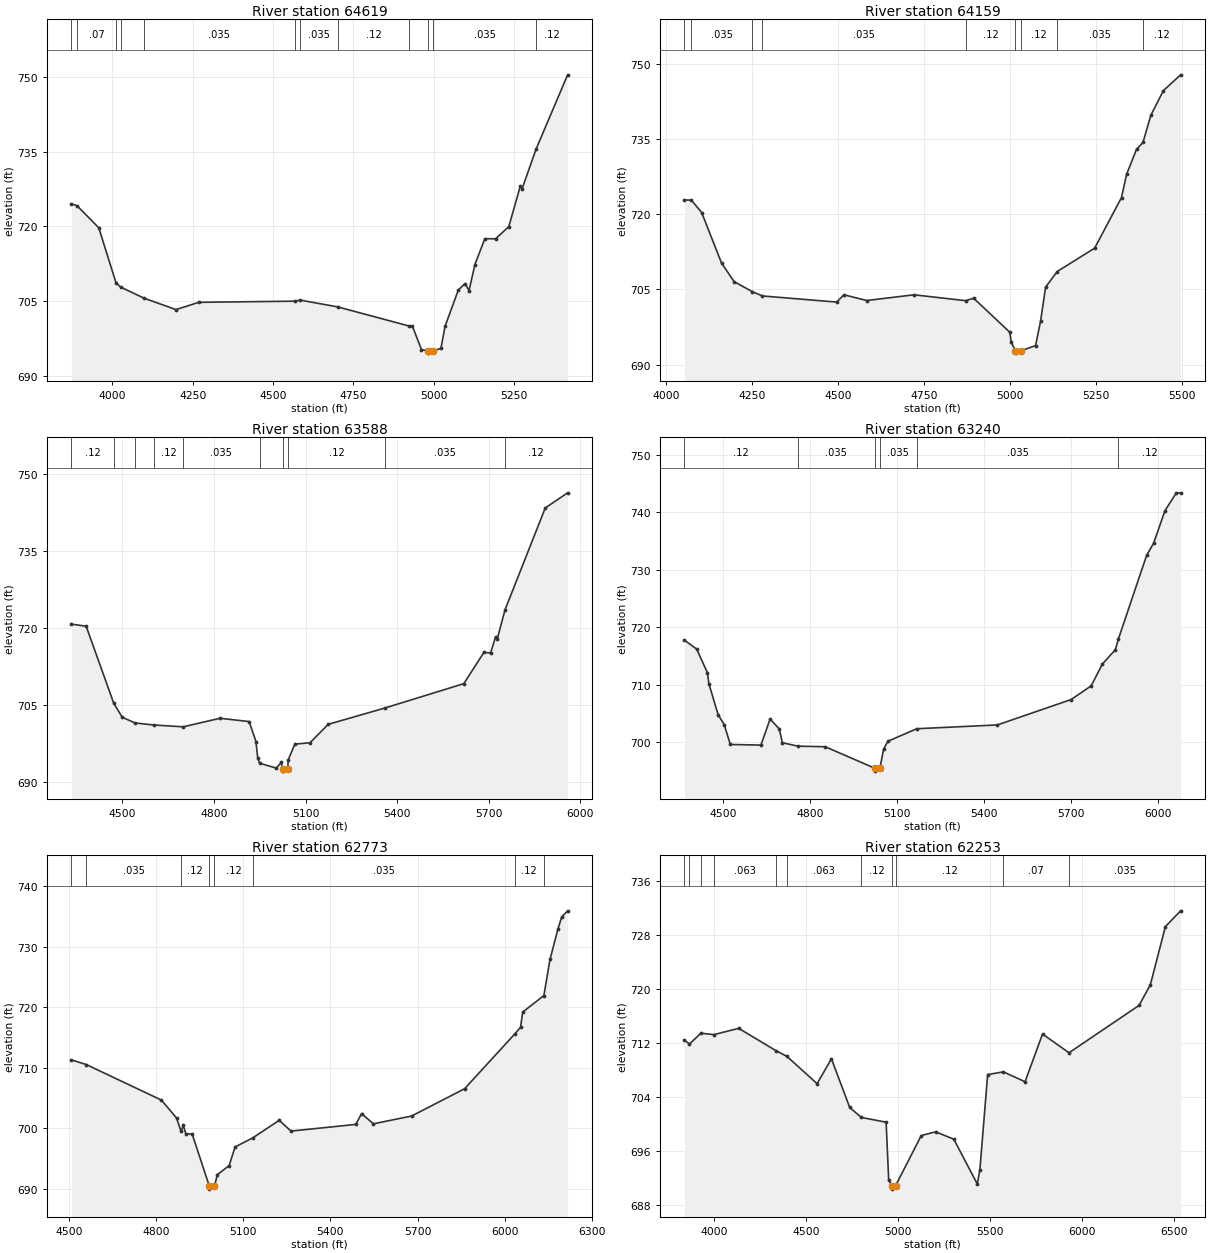
Type RM Length L Ch R = 1 ,64619   ,460,460,460
BEGIN DESCRIPTION:
ALLIGATOR CREEK 161.0
END DESCRIPTION:
XS GIS Cut Line= 3
      2261175.02     13828775.02        2260375.       13827975.
        2260275.       13827575.
#Sta/Elev= 30
  3872.7  724.55  3890.2  724.14  3957.6  719.74  4011.2   708.7  4025.5  707.84
  4098.9   705.6    4198  703.32  4268.7  704.78  4566.7  705.01  4584.9  705.22
  4701.9  703.85  4922.4  700.04  4933.4  700.01  4961.7  695.29  4981.3  695.09
  4981.8  694.59  4998.6  695.09  5022.1  695.52    5035  699.96  5076.2  707.23
  5096.9  708.54  5109.7  707.15  5127.8  712.33  5158.7  717.54  5192.2  717.52
  5233.4  719.97  5269.5  728.17  5274.7  727.54  5318.5  735.56  5416.4  750.41
#Mann= 12 ,-1 , 0
  3872.7     .12       0  3890.2     .07       0  4011.2    .035       0
  4025.5     .07       0  4098.9    .035       0  4566.7     .07       0
  4584.9    .035       0  4701.9     .12       0  4922.4    .035       0
  4981.3    .035       0  4998.6    .035       0  5318.5     .12       0
Bank Sta=4981.3,4998.6
XS Rating Curve= 0 ,0
Exp/Cntr=0.3,0.1

Type RM Length L Ch R = 1 ,64159   ,571,571,571
BEGIN DESCRIPTION:
ALLIGATOR CREEK 160.0
END DESCRIPTION:
XS GIS Cut Line= 3
      2261274.99     13828674.98        2260775.       13827875.
      2260474.98     13827474.98
#Sta/Elev= 30
  4052.4  722.84  4072.6  722.79  4102.5  720.33  4160.3  710.27  4196.8  706.57
    4250  704.56  4279.3  703.71  4495.2  702.49  4516.4  703.94    4583   702.8
  4720.4  703.94  4870.4  702.77  4893.8  703.25  4998.9  696.48  5003.1  694.48
  5015.2  692.82  5015.7  692.32  5032.5  692.82  5073.9  693.82  5088.5  698.72
  5103.1  705.48  5136.9  708.58  5245.8  713.24  5323.9  723.32  5338.5  727.91
  5367.6  732.93  5386.3  734.28  5409.3  739.72  5445.8  744.62  5495.8  747.76
#Mann= 9 ,-1 , 0
  4052.4     .12       0  4072.6    .035       0    4250     .07       0
  4279.3    .035       0  4870.4     .12       0  5015.2     .05       0
  5032.5     .12       0  5136.9    .035       0  5386.3     .12       0
Bank Sta=5015.2,5032.5
XS Rating Curve= 0 ,0
Exp/Cntr=0.3,0.1

Type RM Length L Ch R = 1 ,63588   ,348,348,348
BEGIN DESCRIPTION:
X18023
END DESCRIPTION:
XS GIS Cut Line= 3
      2261566.15     13828517.75      2261191.13     13827788.54
      2260480.33     13827409.79
#Sta/Elev= 30
  4333.2  720.83  4381.3  720.42  4471.7  705.41  4499.5  702.68  4541.3  701.57
  4602.7  701.17  4699.4  700.82  4819.8  702.48  4915.3  701.84  4937.5  697.95
  4943.5   694.7  4949.5  693.72    5004  692.77  5020.5  693.87  5024.8  692.68
  5025.3  692.18  5042.2  692.68  5042.7   694.3  5064.9  697.44  5114.9  697.72
  5174.2   701.3  5360.5  704.49  5618.5  709.23  5684.4  715.33  5706.3  715.21
  5722.6  718.37  5728.3     718  5753.7  723.65  5885.3  743.47  5958.6  746.42
#Mann= 10 ,-1 , 0
  4333.2     .12       0  4471.7     .07       0  4541.3    .035       0
  4602.7     .12       0  4699.4    .035       0  4949.5     .12       0
  5024.8     .05       0  5042.2     .12       0  5360.5    .035       0
  5753.7     .12       0
Bank Sta=5024.8,5042.2
XS Rating Curve= 0 ,0
Exp/Cntr=0.3,0.1

Type RM Length L Ch R = 1 ,63240   ,467,467,467
BEGIN DESCRIPTION:
ALLIGATOR CREEK 159.0
END DESCRIPTION:
XS GIS Cut Line= 3
        2261725.     13828374.99        2261525.       13827775.
      2260524.98     13827374.99
#Sta/Elev= 30
  4367.8  717.76    4410   716.2  4446.9   712.1  4452.1  710.17  4483.7  704.82
  4504.8  703.07  4525.9  699.62  4631.3  699.52  4662.9  704.04  4694.6  702.33
  4705.1  699.93    4759  699.33  4852.7  699.23  5023.8  695.49  5024.3  694.99
  5041.3  695.49  5054.1  698.84  5068.9  700.18  5168.2  702.36  5445.9  703.02
  5700.3  707.44    5769  709.81    5808  713.62  5852.5   716.1  5863.3  718.01
  5960.2   732.5  5984.4  734.62  6023.4  740.27  6062.5  743.36  6077.3  743.37
#Mann= 6 ,-1 , 0
  4367.8     .12       0    4759    .035       0  5023.8    .035       0
  5041.3    .035       0  5168.2    .035       0  5863.3     .12       0
Bank Sta=5023.8,5041.3
XS Rating Curve= 0 ,0
Exp/Cntr=0.3,0.1

Type RM Length L Ch R = 1 ,62773   ,520,520,520
BEGIN DESCRIPTION:
ALLIGATOR CREEK 158.0
END DESCRIPTION:
XS GIS Cut Line= 3
      2262275.01       13827675.        2261825.       13827475.
        2260625.       13827275.
#Sta/Elev= 30
  4508.1  711.29  4558.7  710.53  4817.9  704.65  4869.9   701.7  4885.7  699.47
  4893.2  700.48  4902.1  699.09  4923.9  699.03  4982.9  690.44  4983.4  689.94
  5000.5  690.44  5010.7  692.34  5051.2  693.83  5071.5   696.9  5133.1  698.42
  5223.6  701.31  5264.1  699.53  5487.2  700.63  5507.4  702.42    5548  700.73
  5679.8  702.02  5862.3  706.53  6034.5  715.55  6054.9  716.67  6062.5   719.2
  6135.3  721.92  6156.3  727.88  6184.2  732.99  6196.8  734.92  6217.1  735.92
#Mann= 8 ,-1 , 0
  4508.1    .063       0  4558.7    .035       0  4885.7     .12       0
  4982.9     .05       0  5000.5     .12       0  5133.1    .035       0
  6034.5     .12       0  6135.3    .063       0
Bank Sta=4982.9,5000.5
XS Rating Curve= 0 ,0
Exp/Cntr=0.3,0.1

Type RM Length L Ch R = 1 ,62253   ,610,610,610
BEGIN DESCRIPTION:
X18022
END DESCRIPTION:
XS GIS Cut Line= 4
      2262628.51     13827857.84      2262056.87     13827184.85
      2261456.84     13826629.42      2260518.15     13826293.59
#Sta/Elev= 30
  3839.9   712.5  3867.1   711.9    3929  713.51  3999.6   713.3    4135  714.23
    4337  710.93  4396.9  710.08  4561.1  706.03  4639.1  709.72  4738.5   702.5
  4801.3  701.03  4936.4  700.32  4950.6  691.68  4970.1   690.9  4970.6   690.4
  4987.7   690.9  5127.5  698.34  5205.2   698.9  5304.4   697.8  5431.9  691.17
  5446.1  693.25  5488.5  707.38  5573.8  707.78  5691.9  706.32  5786.8  713.39
  5930.7  710.61  6311.6  717.63  6373.1  720.69  6454.8  729.32  6537.5  731.65
#Mann= 11 ,-1 , 0
  3839.9    .035       0  3867.1    .063       0    3929    .035       0
  3999.6    .063       0    4337    .035       0  4396.9    .063       0
  4801.3     .12       0  4970.1     .05       0  4987.7     .12       0
  5573.8     .07       0  5930.7    .035       0
Bank Sta=4970.1,4987.7
XS Rating Curve= 0 ,0
Exp/Cntr=0.3,0.1

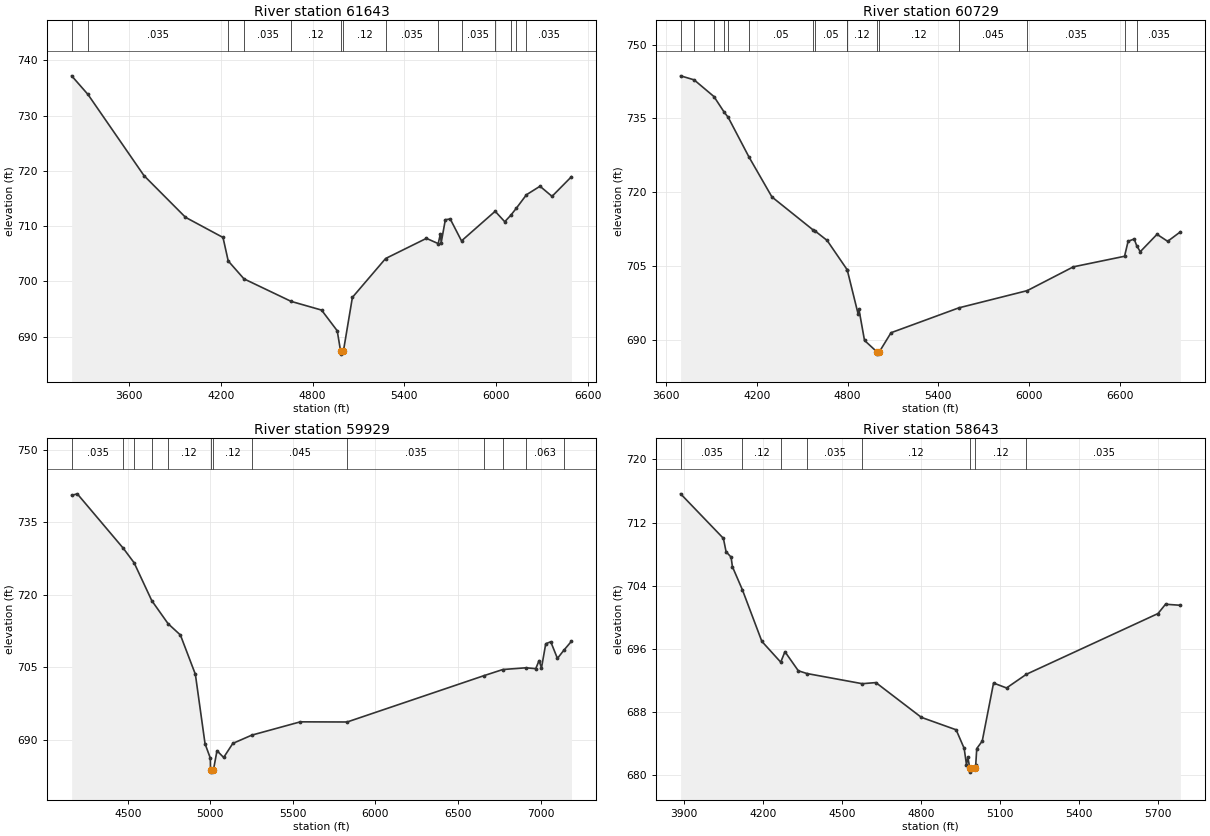
Type RM Length L Ch R = 1 ,61643   ,914,914,914
BEGIN DESCRIPTION:
X18021
END DESCRIPTION:
XS GIS Cut Line= 3
      2263573.12     13827030.78      2261691.99     13826390.22
       2260468.8     13826001.39
#Sta/Elev= 30
  3223.4  737.21  3330.1  733.84  3696.8  719.15  3968.3  711.61  4213.8  707.96
  4247.9  703.71    4351  700.47    4660  696.39  4858.8  694.82  4961.1  691.08
  4983.6  687.35  4984.1  686.85  5001.4  687.35  5060.5  697.12  5277.8  704.15
  5544.9   707.8    5622  706.85  5636.4  708.61  5641.7  707.04  5668.7  711.17
  5700.6  711.31  5774.5  707.34  5994.6   712.7  6057.4  710.81    6097  711.98
  6132.9  713.24  6199.4  715.69  6288.2  717.23  6366.8   715.4  6494.1  718.96
#Mann= 14 ,-1 , 0
  3223.4     .05       0  3330.1    .035       0  4247.9     .12       0
    4351    .035       0    4660     .12       0  4983.6     .05       0
  5001.4     .12       0  5277.8    .035       0    5622     .07       0
  5774.5    .035       0  5994.6     .07       0    6097    .035       0
  6132.9     .07       0  6199.4    .035       0
Bank Sta=4983.6,5001.4
XS Rating Curve= 0 ,0
Exp/Cntr=0.3,0.1

Type RM Length L Ch R = 1 ,60729   ,800,800,800
BEGIN DESCRIPTION:
X18020
END DESCRIPTION:
XS GIS Cut Line= 3
      2263758.43     13826928.64      2262418.29     13826134.48
      2260681.07     13825945.87
#Sta/Elev= 30
  3695.5  743.66  3784.9  742.84  3916.2  739.44  3984.3  736.24    4010  735.23
    4147  727.19  4299.5  719.03  4572.6   712.3  4583.8  712.13  4664.3  710.19
  4797.2  704.22  4797.7  704.16  4868.7  695.32  4874.5  696.24  4911.6  689.86
  4992.4  687.57  4992.9  687.07  5010.3  687.57    5087  691.42  5535.4  696.48
  5987.7  699.98  6292.6  704.82  6631.3  706.97  6654.7  710.02    6695  710.48
  6711.5  709.12  6735.2   707.9  6845.9  711.43  6916.3  710.01  7000.7  711.94
#Mann= 16 ,-1 , 0
  3695.5     .07       0  3784.9     .05       0  3916.2    .035       0
  3984.3     .05       0    4010    .035       0    4147     .05       0
  4572.6    .035       0  4583.8     .05       0  4797.2     .07       0
  4797.7     .12       0  4992.4     .05       0  5010.3     .12       0
  5535.4    .045       0  5987.7    .035       0  6631.3    .063       0
  6711.5    .035       0
Bank Sta=4992.4,5010.3
XS Rating Curve= 0 ,0
Exp/Cntr=0.3,0.1

Type RM Length L Ch R = 1 ,59929   ,1286,1286,1286
BEGIN DESCRIPTION:
X18019
END DESCRIPTION:
XS GIS Cut Line= 3
      2263708.74     13825657.99      2262567.19     13825519.02
      2260710.86     13825796.97
#Sta/Elev= 30
  4160.3  740.59  4194.3  740.91  4473.9  729.61  4538.7  726.64  4645.5  718.82
  4744.3  714.05  4818.9  711.71  4909.5  703.59  4968.1  689.22  5000.2  686.23
  5001.3  683.85  5001.8  683.35  5019.2  683.85  5040.5  687.78  5080.8  686.38
  5136.4  689.29  5251.2     691  5545.1  693.75  5828.8  693.72  6659.7  703.33
  6771.5  704.57  6911.7  704.93  6970.8  704.75    6991  706.41  7005.7  704.91
  7031.4   709.9  7061.8  710.31  7102.2  706.87  7142.6  708.62  7187.3  710.42
#Mann= 13 ,-1 , 0
  4160.3    .035       0  4473.9     .07       0  4538.7    .035       0
  4645.5     .07       0  4744.3     .12       0  5001.3     .05       0
  5019.2     .12       0  5251.2    .045       0  5828.8    .035       0
  6659.7    .045       0  6771.5    .035       0  6911.7    .063       0
  7142.6    .035       0
Bank Sta=5001.3,5019.2
XS Rating Curve= 0 ,0
Exp/Cntr=0.3,0.1

Type RM Length L Ch R = 1 ,58643   ,545,545,545
BEGIN DESCRIPTION:
ALLIGATOR CREEK 153.0
END DESCRIPTION:
XS GIS Cut Line= 3
      2263124.98       13825125.        2262025.       13824925.
      2261425.03     13825424.98
#Sta/Elev= 30
  3887.1  715.64  4049.7  709.99  4059.9  708.29  4078.9  707.61    4084  706.39
  4121.8  703.47  4195.8  696.92  4267.5  694.28  4283.5  695.61  4334.3  693.19
  4367.1  692.84  4577.2  691.55    4629  691.69  4801.8  687.28    4934   685.7
  4964.5  683.34  4973.3  681.26  4978.4  682.23  4985.9  680.83  4986.4  680.33
    5004  680.83  5008.4  681.23  5012.3  683.32  5033.1  684.27  5076.1  691.63
  5125.5  691.01  5201.1  692.75  5700.9  700.45  5729.5  701.63  5786.1   701.5
#Mann= 8 ,-1 , 0
  3887.1    .035       0  4121.8     .12       0  4267.5     .07       0
  4367.1    .035       0  4577.2     .12       0  4985.9     .05       0
    5004     .12       0  5201.1    .035       0
Bank Sta=4985.9,5004
XS Rating Curve= 0 ,0
Exp/Cntr=0.3,0.1