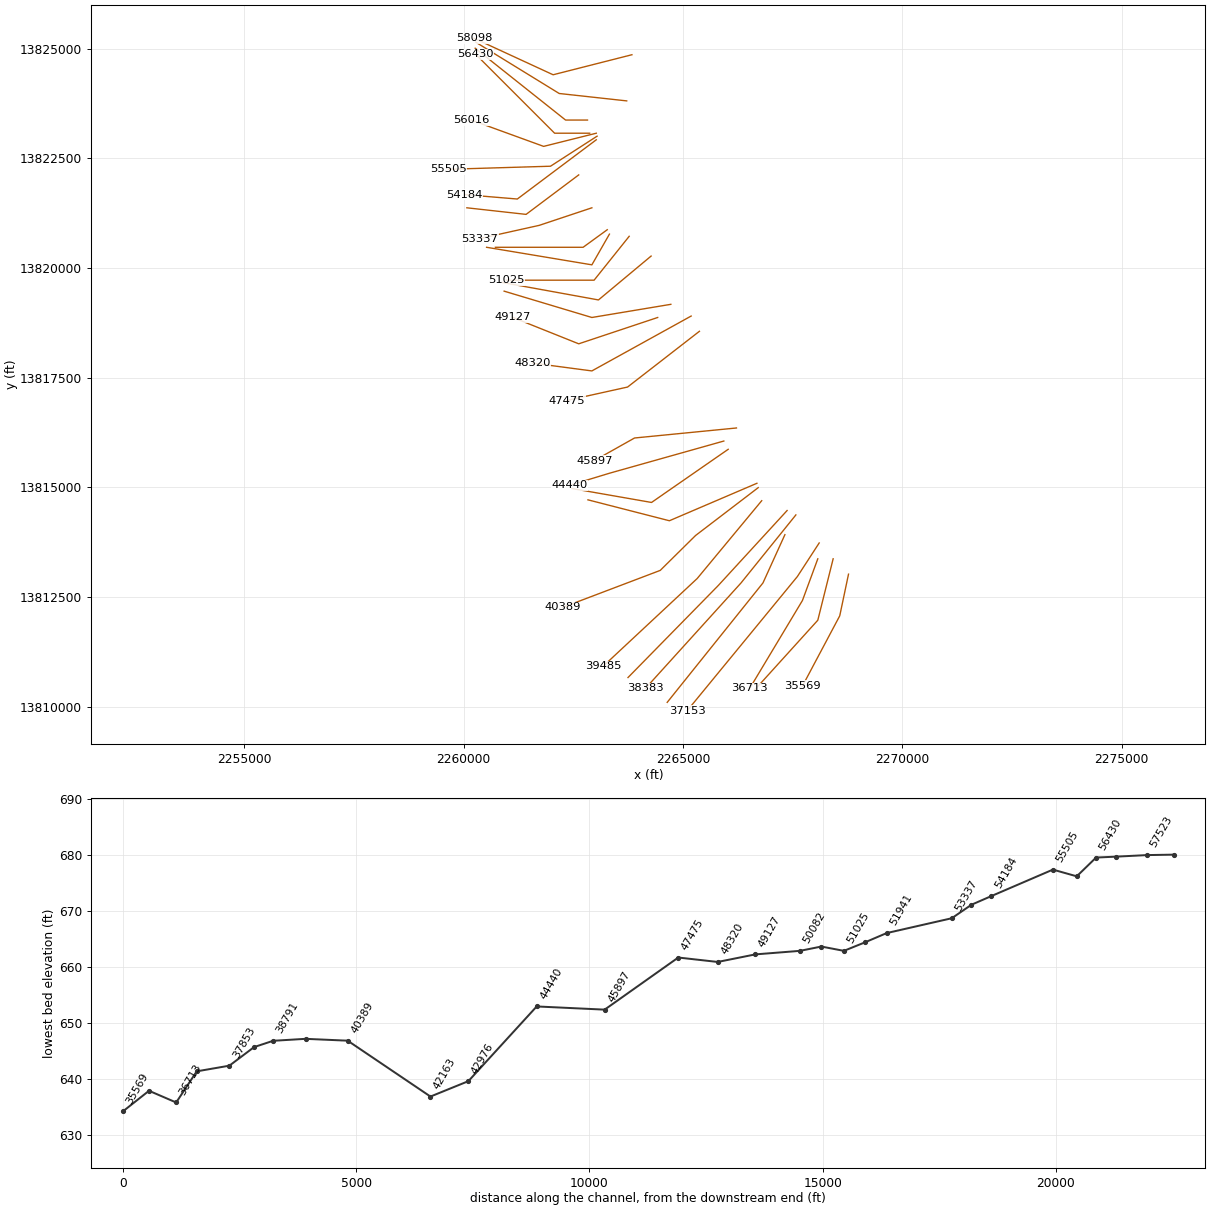
HEC-RAS study ALLIGATOR CREEK.prj: ALLIGATOR CREEK Base Level Engineering

--- ALLIGATOR CREEK.g01 (geometry) --- (continued)

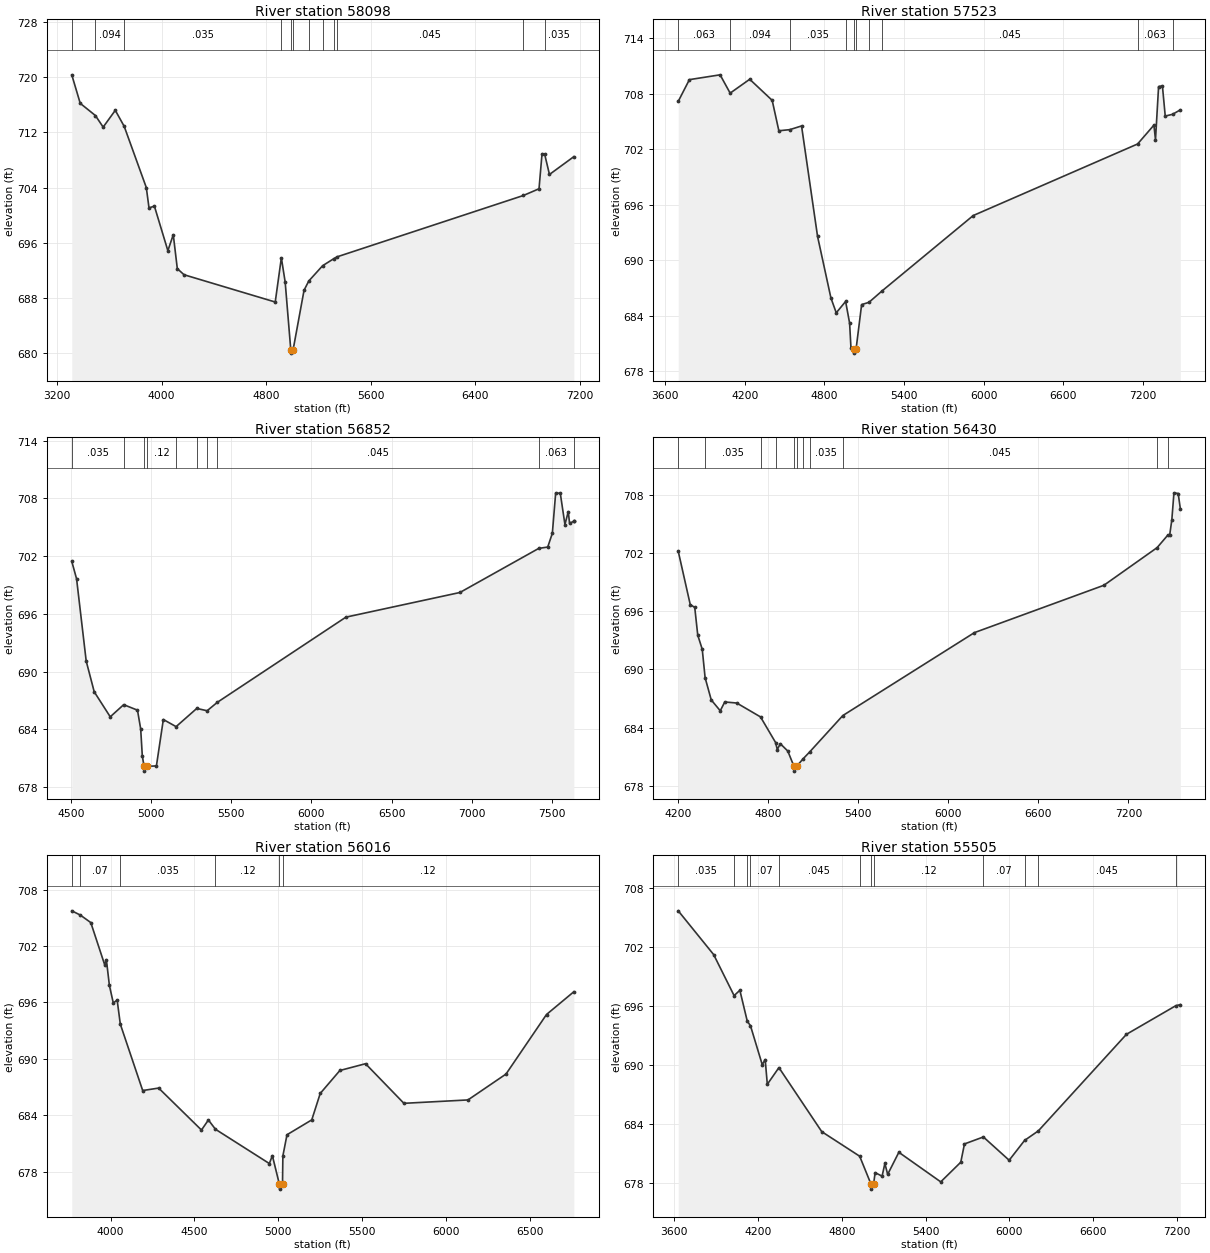
Type RM Length L Ch R = 1 ,58098   ,575,575,575
BEGIN DESCRIPTION:
X18018
END DESCRIPTION:
XS GIS Cut Line= 3
      2263837.85     13824863.86      2262041.07     13824407.22
      2260235.59     13825240.52
#Sta/Elev= 30
  3312.4  720.33  3377.2   716.2    3493  714.44  3552.7  712.76  3645.5  715.19
  3713.6  712.87  3882.8  704.01  3903.5  701.06  3944.7  701.32  4047.9  694.86
  4089.2  697.18  4120.1  692.26  4171.7  691.38  4869.5  687.43  4916.4  693.83
  4945.6  690.32  4988.4  680.53  4988.9  680.03  5006.5  680.53    5090  689.13
    5126  690.47  5232.3  692.69  5317.1   693.7  5342.3  693.97  6768.9  702.86
  6888.3  703.83  6911.3   708.9  6930.9  708.88  6968.2   705.9  7154.8  708.48
#Mann= 12 ,-1 , 0
  3312.4    .035       0    3493    .094       0  3713.6    .035       0
  4916.4     .12       0  4988.4     .05       0  5006.5     .12       0
    5126     .07       0  5232.3    .045       0  5317.1     .07       0
  5342.3    .045       0  6768.9    .063       0  6930.9    .035       0
Bank Sta=4988.4,5006.5
XS Rating Curve= 0 ,0
Exp/Cntr=0.3,0.1

Type RM Length L Ch R = 1 ,57523   ,671,671,671
BEGIN DESCRIPTION:
X18017
END DESCRIPTION:
XS GIS Cut Line= 3
      2263718.65     13823811.62      2262180.04     13823980.37
      2260275.51     13825150.87
#Sta/Elev= 30
    3699  707.18  3783.1  709.53  4014.5  710.05  4090.2  708.07  4237.7  709.57
  4406.9  707.29  4457.2     704  4539.1  704.12  4628.2  704.52  4748.9  692.57
  4849.5  685.92  4889.7  684.31  4960.3  685.54  4990.3   683.2  5000.4  680.55
  5021.5  680.45    5022  679.95  5039.6  680.45  5080.9   685.2  5135.7  685.44
  5235.1  686.68  5921.8  694.83  7160.4  702.57  7283.4  704.61  7295.3  703.03
  7318.6  708.78  7347.4  708.86  7368.7  705.59  7423.8  705.78  7482.3  706.26
#Mann= 10 ,-1 , 0
    3699    .063       0  4090.2    .094       0  4539.1    .035       0
  4960.3     .12       0  5021.5     .05       0  5039.6     .12       0
  5135.7     .07       0  5235.1    .045       0  7160.4    .063       0
  7423.8    .035       0
Bank Sta=5021.5,5039.6
XS Rating Curve= 0 ,0
Exp/Cntr=0.3,0.1

Type RM Length L Ch R = 1 ,56852   ,422,422,422
BEGIN DESCRIPTION:
ALLIGATOR CREEK 152.0
END DESCRIPTION:
XS GIS Cut Line= 3
      2262825.05       13823375.        2262325.       13823375.
      2260264.17     13825012.76
#Sta/Elev= 30
  4504.7  701.45  4534.7  699.64  4594.7   691.1  4644.7  687.91  4744.7  685.31
  4828.6  686.57  4914.7     686  4934.7  684.05  4944.7  681.26  4955.6  680.17
  4956.1  679.67  4973.9  680.17  5032.8  680.21    5076  685.03  5155.6  684.29
  5284.5  686.18  5349.2  685.94  5413.3  686.82    6215  695.66  6926.3  698.22
  7418.2   702.8  7474.2  702.94    7503  704.37  7523.8  708.57  7552.7  708.51
  7581.5  705.28  7602.3  706.62  7610.3  705.42    7636   705.6  7637.1   705.6
#Mann= 10 ,-1 , 0
  4504.7    .035       0  4828.6     .12       0  4955.6     .05       0
  4973.9     .12       0  5155.6    .035       0  5284.5     .07       0
  5349.2    .035       0  5413.3    .045       0  7418.2    .063       0
    7636    .035       0
Bank Sta=4955.6,4973.9
XS Rating Curve= 0 ,0
Exp/Cntr=0.3,0.1

Type RM Length L Ch R = 1 ,56430   ,414,414,414
BEGIN DESCRIPTION:
ALLIGATOR CREEK 151.0
END DESCRIPTION:
XS GIS Cut Line= 3
      2262875.04       13823075.        2262075.       13823075.
      2260275.02     13824874.98
#Sta/Elev= 30
  4199.7  702.18  4279.7  696.68  4309.7  696.39  4329.7  693.53  4359.7  692.07
  4378.8  689.14  4419.7  686.85  4479.7  685.73  4509.7  686.64  4589.7  686.53
  4747.9   685.1  4848.4  682.46  4859.7  681.73  4879.7  682.34  4929.7  681.58
  4970.6  680.01  4971.1  679.51  4988.9  680.01  5031.2  680.77  5077.5  681.52
  5296.5  685.24  6173.5  693.79  7036.2  698.67  7390.7  702.55  7463.7  703.87
  7474.6  703.85  7488.8  705.42  7502.9   708.2  7531.2  708.13  7545.3  706.58
#Mann= 11 ,-1 , 0
  4199.7     .07       0  4378.8    .035       0  4747.9     .12       0
  4848.4    .035       0  4970.6    .035       0  4988.9    .035       0
  5031.2     .12       0  5077.5    .035       0  5296.5    .045       0
  7390.7    .035       0  7463.7    .063       0
Bank Sta=4970.6,4988.9
XS Rating Curve= 0 ,0
Exp/Cntr=0.3,0.1

Type RM Length L Ch R = 1 ,56016   ,511,511,511
BEGIN DESCRIPTION:
ALLIGATOR CREEK 150.0
END DESCRIPTION:
XS GIS Cut Line= 3
      2263025.04     13823075.01        2261825.       13822775.
      2260174.98     13823375.01
#Sta/Elev= 30
  3768.9  705.74  3819.8  705.29  3882.3  704.49  3964.8  700.02  3975.1  700.55
  3993.1  697.82  4016.3  695.95  4039.5  696.25  4058.2   693.7  4191.6  686.64
  4286.9   686.9    4542  682.44  4583.3  683.51  4625.6  682.52  4946.6  678.88
  4964.6  679.72  5006.7  676.66  5007.2  676.16    5025  676.66  5027.2  679.69
  5051.8  681.94  5199.4  683.52  5249.9  686.33    5367  688.77  5519.9  689.49
  5748.7  685.28  6130.5  685.64  6357.2  688.39  6598.6  694.72  6761.6  697.14
#Mann= 6 ,-1 , 0
  3768.9    .035       0  3819.8     .07       0  4058.2    .035       0
  4625.6     .12       0  5006.7     .05       0    5025     .12       0
Bank Sta=5006.7,5025
XS Rating Curve= 0 ,0
Exp/Cntr=0.3,0.1

Type RM Length L Ch R = 1 ,55505   ,1321,1321,1321
BEGIN DESCRIPTION:
ALLIGATOR CREEK 149.0
END DESCRIPTION:
XS GIS Cut Line= 3
      2263043.69     13823007.56      2261981.51      13822322.6
      2259649.33     13822253.13
#Sta/Elev= 30
  3627.5  705.69  3881.5  701.23  4027.7  697.06    4069   697.6  4122.2  694.45
  4144.9     694  4229.4  690.03  4250.5  690.55  4265.7  688.03  4348.8  689.73
  4655.8  683.21  4927.4  680.71  5008.8  677.86  5009.3  677.36  5027.2  677.86
    5038  679.04    5088  678.68    5108  679.97    5128  678.86    5208  681.11
  5508.2   678.1  5651.8   680.1  5678.2  681.96  5813.6  682.67  5998.4   680.3
    6109  682.32  6207.5  683.29  6838.8  693.12  7192.1  696.03  7224.6  696.14
#Mann= 12 ,-1 , 0
  3627.5    .035       0  4027.7     .07       0  4122.2    .035       0
  4144.9     .07       0  4348.8    .045       0  4927.4     .12       0
  5008.8     .05       0  5027.2     .12       0  5813.6     .07       0
    6109    .035       0  6207.5    .045       0  7192.1    .035       0
Bank Sta=5008.8,5027.2
XS Rating Curve= 0 ,0
Exp/Cntr=0.3,0.1

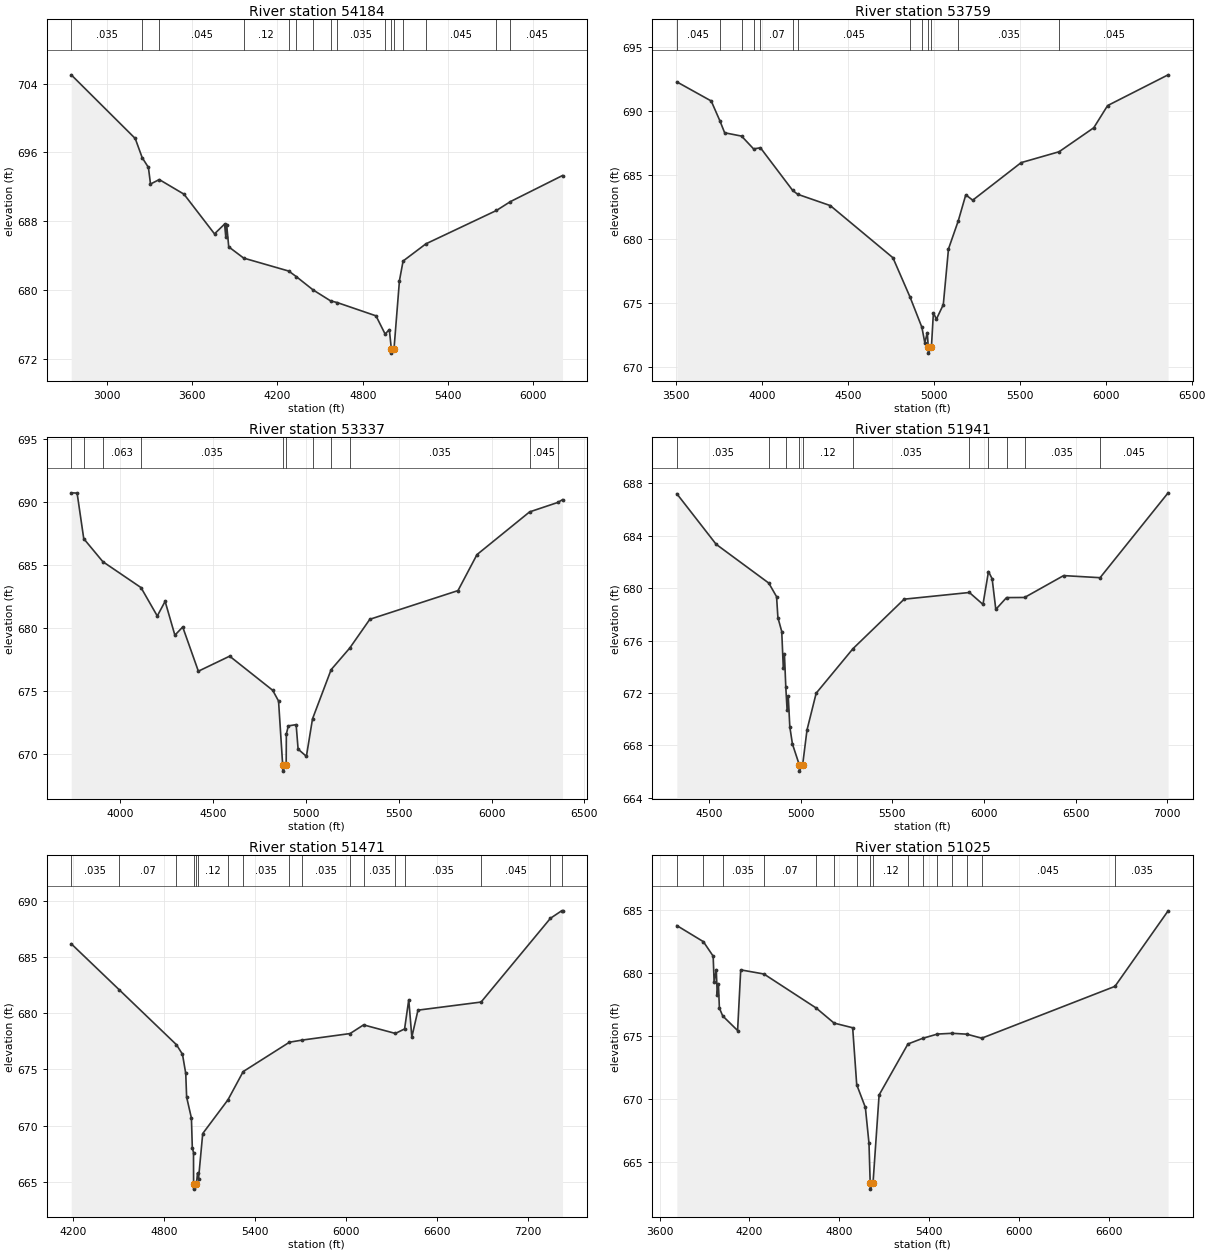
Type RM Length L Ch R = 1 ,54184   ,425,425,425
BEGIN DESCRIPTION:
ALLIGATOR CREEK 148.0
END DESCRIPTION:
XS GIS Cut Line= 3
      2263024.97     13822924.98        2261225.       13821575.
      2260025.02       13821675.
#Sta/Elev= 30
    2750  705.02    3200  697.61  3248.6  695.39  3292.7  694.24  3307.3  692.31
  3369.1  692.83  3542.7  691.13  3757.3  686.51  3828.1  687.65  3836.4   686.2
  3842.7   687.6  3857.3     685  3962.5  683.69  4279.5  682.18  4332.7  681.53
  4450.2  679.99  4573.6  678.71    4621  678.51  4892.7  676.97  4956.9  674.85
  4986.4  675.37  5000.6  673.13  5001.1  672.63  5019.4  673.13  5057.7  681.08
  5083.3  683.35  5243.7  685.35  5739.2  689.23  5838.3  690.27  6204.1   693.3
#Mann= 16 ,-1 , 0
    2750    .035       0  3248.6     .07       0  3369.1    .045       0
  3962.5     .12       0  4279.5     .07       0  4332.7     .12       0
  4450.2     .07       0  4573.6     .12       0    4621    .035       0
  4956.9     .12       0  5000.6     .05       0  5019.4     .12       0
  5083.3    .035       0  5243.7    .045       0  5739.2    .035       0
  5838.3    .045       0
Bank Sta=5000.6,5019.4
XS Rating Curve= 0 ,0
Exp/Cntr=0.3,0.1

Type RM Length L Ch R = 1 ,53759   ,422,422,422
BEGIN DESCRIPTION:
ALLIGATOR CREEK 147.0
END DESCRIPTION:
XS GIS Cut Line= 3
      2262625.03     13822125.02        2261425.       13821225.
      2260075.05     13821374.99
#Sta/Elev= 30
  3504.7  692.25  3704.7  690.76  3755.3  689.21  3782.9  688.28  3881.4  688.02
  3951.4  687.02  3991.1  687.11  4178.8  683.78  4207.9  683.48  4397.4   682.6
    4762  678.53  4861.9  675.45  4930.6   673.1  4947.4   671.9    4962  672.69
  4967.2  671.59  4967.7  671.09    4986  671.59  4997.4  674.24  5014.8  673.74
    5055  674.87  5085.2  679.22  5142.4  681.42  5185.8  683.44  5226.1  683.02
  5507.8  685.95  5728.7   686.8  5930.4  688.67  6010.9   690.4    6363   692.8
#Mann= 13 ,-1 , 0
  3504.7    .045       0  3755.3     .12       0  3881.4     .07       0
  3951.4     .12       0  3991.1     .07       0  4178.8    .035       0
  4207.9    .045       0  4861.9    .035       0  4930.6     .07       0
  4967.2     .05       0    4986     .07       0  5142.4    .035       0
  5728.7    .045       0
Bank Sta=4967.2,4986
XS Rating Curve= 0 ,0
Exp/Cntr=0.3,0.1

Type RM Length L Ch R = 1 ,53337   ,1396,1396,1396
BEGIN DESCRIPTION:
ALLIGATOR CREEK 146.0
END DESCRIPTION:
XS GIS Cut Line= 3
      2262925.04     13821375.01        2261725.       13820975.
      2260374.98       13820675.
#Sta/Elev= 30
  3734.5  690.71  3766.2  690.69    3802  687.08  3904.9  685.26  4110.5  683.21
  4198.3  680.96  4240.5  682.12  4293.2  679.44  4335.4  680.09  4419.7  676.59
  4588.4  677.78  4820.3  675.08  4851.9  674.23  4874.1  669.18  4874.6  668.68
    4893  669.18    4894  671.62  4904.6  672.26  4946.7  672.36  4957.3  670.42
    5002  669.85    5035  672.82  5135.2  676.71  5235.5  678.42  5343.9   680.7
    5819  682.97  5921.4  685.82    6205   689.2  6357.3  689.95  6382.4  690.17
#Mann= 11 ,-1 , 0
  3734.5    .063       0    3802    .035       0  3904.9    .063       0
  4110.5    .035       0  4874.1    .035       0    4893    .035       0
    5035     .12       0  5135.2     .07       0  5235.5    .035       0
    6205    .045       0  6357.3    .035       0
Bank Sta=4874.1,4893
XS Rating Curve= 0 ,0
Exp/Cntr=0.3,0.1

Type RM Length L Ch R = 1 ,51941   ,470,470,470
BEGIN DESCRIPTION:
ALLIGATOR CREEK 145.0
END DESCRIPTION:
XS GIS Cut Line= 3
      2263275.03     13820875.02        2262725.       13820475.
      2260725.01       13820475.
#Sta/Elev= 30
  4323.9  687.21  4538.4  683.35  4825.4  680.39    4868  679.35  4875.3  677.75
  4896.2  676.69  4904.7  673.91  4910.9  674.96  4918.4  672.42  4925.6  670.66
  4931.8  671.73  4940.3   669.4  4954.6   668.1  4991.5  666.53    4992  666.03
  5010.4  666.53    5034  669.17    5084  671.98  5284.8  675.38    5564  679.16
  5919.8  679.67    5994  678.76    6024  681.27    6044  680.72    6064  678.38
  6122.5  679.28    6221  679.29    6434  680.96  6632.9   680.8    7004  687.28
#Mann= 11 ,-1 , 0
  4323.9    .035       0  4825.4     .07       0  4918.4     .12       0
  4991.5     .05       0  5010.4     .12       0  5284.8    .035       0
  5919.8     .07       0    6024    .035       0  6122.5     .07       0
    6221    .035       0  6632.9    .045       0
Bank Sta=4991.5,5010.4
XS Rating Curve= 0 ,0
Exp/Cntr=0.3,0.1

Type RM Length L Ch R = 1 ,51471   ,446,446,446
BEGIN DESCRIPTION:
ALLIGATOR CREEK 144.0
END DESCRIPTION:
XS GIS Cut Line= 3
      2263324.99     13820774.98        2262925.       13820075.
      2260525.01       13820475.
#Sta/Elev= 30
  4189.1  686.17    4505  682.09  4882.8   677.2  4922.6  676.35  4944.2  674.64
    4950  672.54  4981.6  670.67  4987.4  668.06  4995.3  667.61  4995.9  664.86
  4996.4  664.36  5014.9  664.86  5021.8  665.78  5028.3  665.26  5056.1   669.3
  5222.5   672.3  5322.9  674.81  5627.9  677.42  5712.1  677.61  6027.7  678.19
  6116.7  678.96  6326.5   678.2  6387.1   678.6  6414.6   681.2  6434.9  677.88
  6475.4  680.27  6891.5  680.99    7349  688.44  7422.4   689.1  7428.4   689.1
#Mann= 17 ,-1 , 0
  4189.1    .035       0    4505     .07       0  4882.8    .035       0
  4995.9    .035       0  5014.9    .035       0  5021.8     .12       0
  5222.5     .07       0  5322.9    .035       0  5627.9    .045       0
  5712.1    .035       0  6027.7    .045       0  6116.7    .035       0
  6326.5     .07       0  6387.1    .035       0  6891.5    .045       0
    7349    .035       0  7422.4    .045       0
Bank Sta=4995.9,5014.9
XS Rating Curve= 0 ,0
Exp/Cntr=0.3,0.1

Type RM Length L Ch R = 1 ,51025   ,483,483,483
BEGIN DESCRIPTION:
ALLIGATOR CREEK 143.0
END DESCRIPTION:
XS GIS Cut Line= 3
      2263775.02     13820725.03        2262975.       13819725.
      2260974.96       13819725.
#Sta/Elev= 30
    3715   683.8  3892.3  682.52  3957.6  681.37    3964  679.31  3978.4   680.3
  3984.8  678.29  3992.8  679.13  3999.2  677.24  4021.4  676.62  4120.8  675.46
  4141.6  680.28  4296.7  679.95  4645.3  677.25  4765.1  676.05  4889.2  675.68
  4916.2  671.16    4974  669.35  4998.2   666.5  5006.2  663.36  5006.7  662.86
  5025.2  663.36  5065.7  670.34  5258.2  674.39  5356.7  674.84  5455.2  675.18
  5553.8  675.24  5652.3  675.17  5750.8  674.85  6640.8  678.97  6995.7  684.97
#Mann= 16 ,-1 , 0
    3715    .035       0  3892.3     .07       0  4021.4    .035       0
  4296.7     .07       0  4645.3    .035       0  4765.1     .07       0
  4916.2     .12       0  5006.2     .05       0  5025.2     .12       0
  5258.2    .035       0  5356.7     .12       0  5455.2    .035       0
  5553.8     .12       0  5652.3     .07       0  5750.8    .045       0
  6640.8    .035       0
Bank Sta=5006.2,5025.2
XS Rating Curve= 0 ,0
Exp/Cntr=0.3,0.1

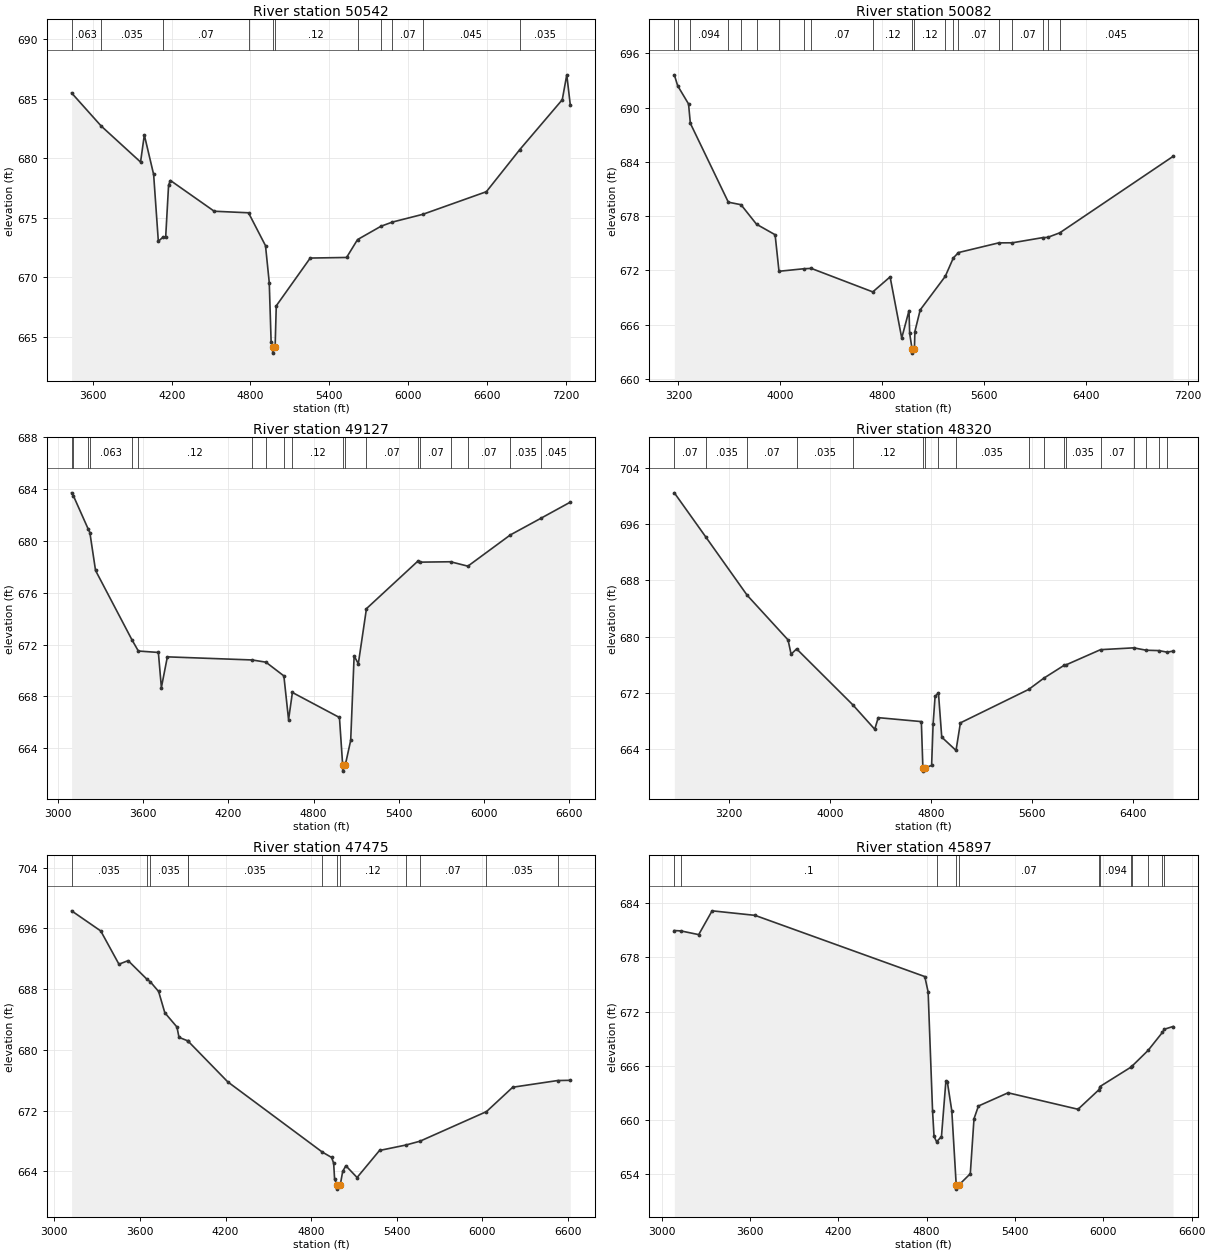
Type RM Length L Ch R = 1 ,50542   ,460,460,460
BEGIN DESCRIPTION:
ALLIGATOR CREEK 142.0
END DESCRIPTION:
XS GIS Cut Line= 3
      2264274.98     13820274.99        2263075.       13819275.
        2260875.       13819675.
#Sta/Elev= 30
    3438  685.47  3663.5  682.69  3963.2  679.67  3991.9  681.94  4062.8  678.63
  4098.6  673.02  4132.9  673.35  4154.6  673.37  4176.7  677.74    4191  678.12
  4524.3  675.54  4785.4  675.41  4914.8  672.65  4943.4  669.55  4957.7  664.55
    4969  664.13  4969.5  663.63    4988  664.13  4996.8   667.6  5255.4  671.61
  5532.4  671.66  5615.8  673.16  5794.4  674.28    5881  674.63  6112.7  675.28
    6597  677.18    6852  680.72  7175.1   684.9  7209.4  686.99  7236.1  684.47
#Mann= 11 ,-1 , 0
    3438    .063       0  3663.5    .035       0  4132.9     .07       0
  4785.4     .12       0    4969     .05       0    4988     .12       0
  5615.8     .07       0  5794.4     .12       0    5881     .07       0
  6112.7    .045       0    6852    .035       0
Bank Sta=4969,4988
XS Rating Curve= 0 ,0
Exp/Cntr=0.3,0.1

Type RM Length L Ch R = 1 ,50082   ,955,955,955
BEGIN DESCRIPTION:
ALLIGATOR CREEK 141.0
END DESCRIPTION:
XS GIS Cut Line= 3
      2264724.96     13819174.99        2262925.       13818875.
      2260925.05     13819474.99
#Sta/Elev= 30
  3168.3  693.63  3194.5  692.42  3279.8  690.41  3293.9  688.27    3592  679.55
  3691.4  679.27  3813.3  677.11    3959  675.95  3989.5  671.91  4185.2  672.19
  4242.3  672.23  4725.4  669.63  4861.3  671.29  4952.5  664.53  5009.6  667.56
  5014.8  665.05  5033.1  663.36  5033.6  662.86  5052.3  663.36  5055.7  665.25
  5097.5  667.64  5294.1  671.35  5357.7  673.39  5397.9  673.98  5713.3  675.05
  5820.8  675.06  6058.1  675.63  6097.8  675.66  6192.4  676.16  7081.1  684.61
#Mann= 20 ,-1 , 0
  3168.3    .035       0  3194.5    .063       0  3293.9    .094       0
    3592    .063       0  3691.4    .035       0  3813.3    .063       0
  3989.5    .035       0  4185.2     .12       0  4242.3     .07       0
  4725.4     .12       0  5033.1     .05       0  5052.3     .12       0
  5294.1     .07       0  5357.7    .035       0  5397.9     .07       0
  5713.3    .035       0  5820.8     .07       0  6058.1    .045       0
  6097.8     .07       0  6192.4    .045       0
Bank Sta=5033.1,5052.3
XS Rating Curve= 0 ,0
Exp/Cntr=0.3,0.1

Type RM Length L Ch R = 1 ,49127   ,807,807,807
BEGIN DESCRIPTION:
ALLIGATOR CREEK 140.0
END DESCRIPTION:
XS GIS Cut Line= 3
      2264424.96     13818874.99        2262625.       13818275.
      2261124.98     13818875.01
#Sta/Elev= 30
  3095.8  683.71  3108.9  683.47  3211.7  680.94  3224.5  680.64  3264.4  677.72
  3520.2  672.38  3566.1   671.5  3707.1  671.39  3728.2  668.68  3770.4  671.05
  4367.7  670.81  4464.5  670.64  4591.1  669.58  4624.2   666.2  4651.2   668.3
  4982.6  666.37  5005.1  662.73  5005.6  662.23  5024.3  662.73  5061.8   664.6
    5086  671.12  5115.6  670.52  5172.9  674.77  5536.2  678.45  5552.5  678.36
  5765.1  678.39  5887.3  678.05  6186.4  680.46  6400.8  681.74  6608.7  682.99
#Mann= 19 ,-1 , 0
  3095.8    .035       0  3108.9    .063       0  3211.7    .094       0
  3224.5    .063       0  3520.2    .035       0  3566.1     .12       0
  4367.7     .07       0  4464.5     .12       0  4591.1     .07       0
  4651.2     .12       0  5005.1     .05       0  5024.3     .12       0
  5172.9     .07       0  5536.2    .035       0  5552.5     .07       0
  5765.1    .035       0  5887.3     .07       0  6186.4    .035       0
  6400.8    .045       0
Bank Sta=5005.1,5024.3
XS Rating Curve= 0 ,0
Exp/Cntr=0.3,0.1

Type RM Length L Ch R = 1 ,48320   ,845,845,845
BEGIN DESCRIPTION:
X18016
END DESCRIPTION:
XS GIS Cut Line= 3
      2265187.82     13818907.77      2262924.55     13817657.02
       2261574.5      13817835.7
#Sta/Elev= 30
  2765.5  700.43  3014.7  694.15  3342.2  685.87  3665.6  679.53  3689.9   677.5
  3733.7  678.25  4177.5  670.32    4352  666.83  4379.7  668.48  4720.9  667.92
    4733  661.38  4733.5  660.88  4752.3  661.38  4802.2  661.68  4813.9  667.54
  4829.7  671.49  4856.2  672.02  4882.4  665.71  4995.4  663.82  5030.2  667.74
  5571.4   672.5  5688.9  674.07  5850.4  675.91  5867.6  675.99  6139.3  678.14
  6401.7   678.4  6501.5  678.06  6601.2  678.01  6665.7  677.79  6713.2  677.93
#Mann= 18 ,-1 , 0
  2765.5     .07       0  3014.7    .035       0  3342.2     .07       0
  3733.7    .035       0  4177.5     .12       0    4733    .035       0
  4752.3     .12       0  4856.2     .07       0  4995.4    .035       0
  5571.4     .07       0  5688.9    .035       0  5850.4     .07       0
  5867.6    .035       0  6139.3     .07       0  6401.7    .035       0
  6501.5     .07       0  6601.2    .035       0  6665.7    .045       0
Bank Sta=4733,4752.3
XS Rating Curve= 0 ,0
Exp/Cntr=0.3,0.1

Type RM Length L Ch R = 1 ,47475   ,1578,1578,1578
BEGIN DESCRIPTION:
X18015
END DESCRIPTION:
XS GIS Cut Line= 3
      2265376.44     13818560.33      2263738.55     13817289.72
      2262349.35     13816982.12
#Sta/Elev= 30
    3121  698.32  3325.3  695.67    3453  691.29  3517.3  691.76  3649.3  689.31
  3671.7     689  3730.9   687.7  3774.4   684.9  3859.5  683.02  3873.9  681.66
  3936.4  681.19  3937.6  681.16  4216.1  675.79  4878.4  666.55  4943.9  665.84
    4958  665.08  4964.7  662.98  4983.5  662.17    4984  661.67  5003.8  662.17
  5021.3     664  5043.5  664.75  5122.2   663.2  5279.5  666.76  5462.6  667.47
  5562.9  667.98  6029.4  671.88  6213.5  675.09    6528  675.97  6616.8     676
#Mann= 12 ,-1 , 0
    3121    .035       0  3649.3     .07       0  3671.7    .035       0
  3936.4     .07       0  3937.6    .035       0  4878.4     .12       0
  4983.5     .05       0  5003.8     .12       0  5462.6    .035       0
  5562.9     .07       0  6029.4    .035       0    6528    .045       0
Bank Sta=4983.5,5003.8
XS Rating Curve= 0 ,0
Exp/Cntr=0.3,0.1

Type RM Length L Ch R = 1 ,45897   ,1457,1457,1457
BEGIN DESCRIPTION:
ALLIGATOR CREEK 139.0
END DESCRIPTION:
XS GIS Cut Line= 3
      2266220.28     13816356.61      2263897.38     13816128.29
      2262980.13     13815612.34
#Sta/Elev= 30
  3086.9  680.96  3131.2  680.92  3252.3  680.51  3343.4  683.14  3634.8  682.64
  4787.8  675.87  4810.4  674.17  4840.6  660.97  4850.6  658.19    4868  657.61
  4900.9  658.17    4931  664.31  4941.1   664.2  4971.2  661.02    5001  652.87
  5001.5  652.37  5021.8  652.87  5096.8  654.07  5121.9  660.15  5152.1  661.56
  5353.1  663.02  5828.3   661.2  5970.4  663.36  5977.1  663.71    6189  665.87
  6192.7  665.93  6303.8   667.7    6401  669.69    6415  670.05  6473.4  670.35
#Mann= 12 ,-1 , 0
  3086.9    .094       0  3131.2      .1       0    4868     .07       0
    5001     .05       0  5021.8     .07       0  5970.4      .1       0
  5977.1    .094       0    6189     .07       0  6192.7    .094       0
  6303.8      .1       0    6401    .094       0    6415      .1       0
Bank Sta=5001,5021.8
XS Rating Curve= 0 ,0
Exp/Cntr=0.3,0.1

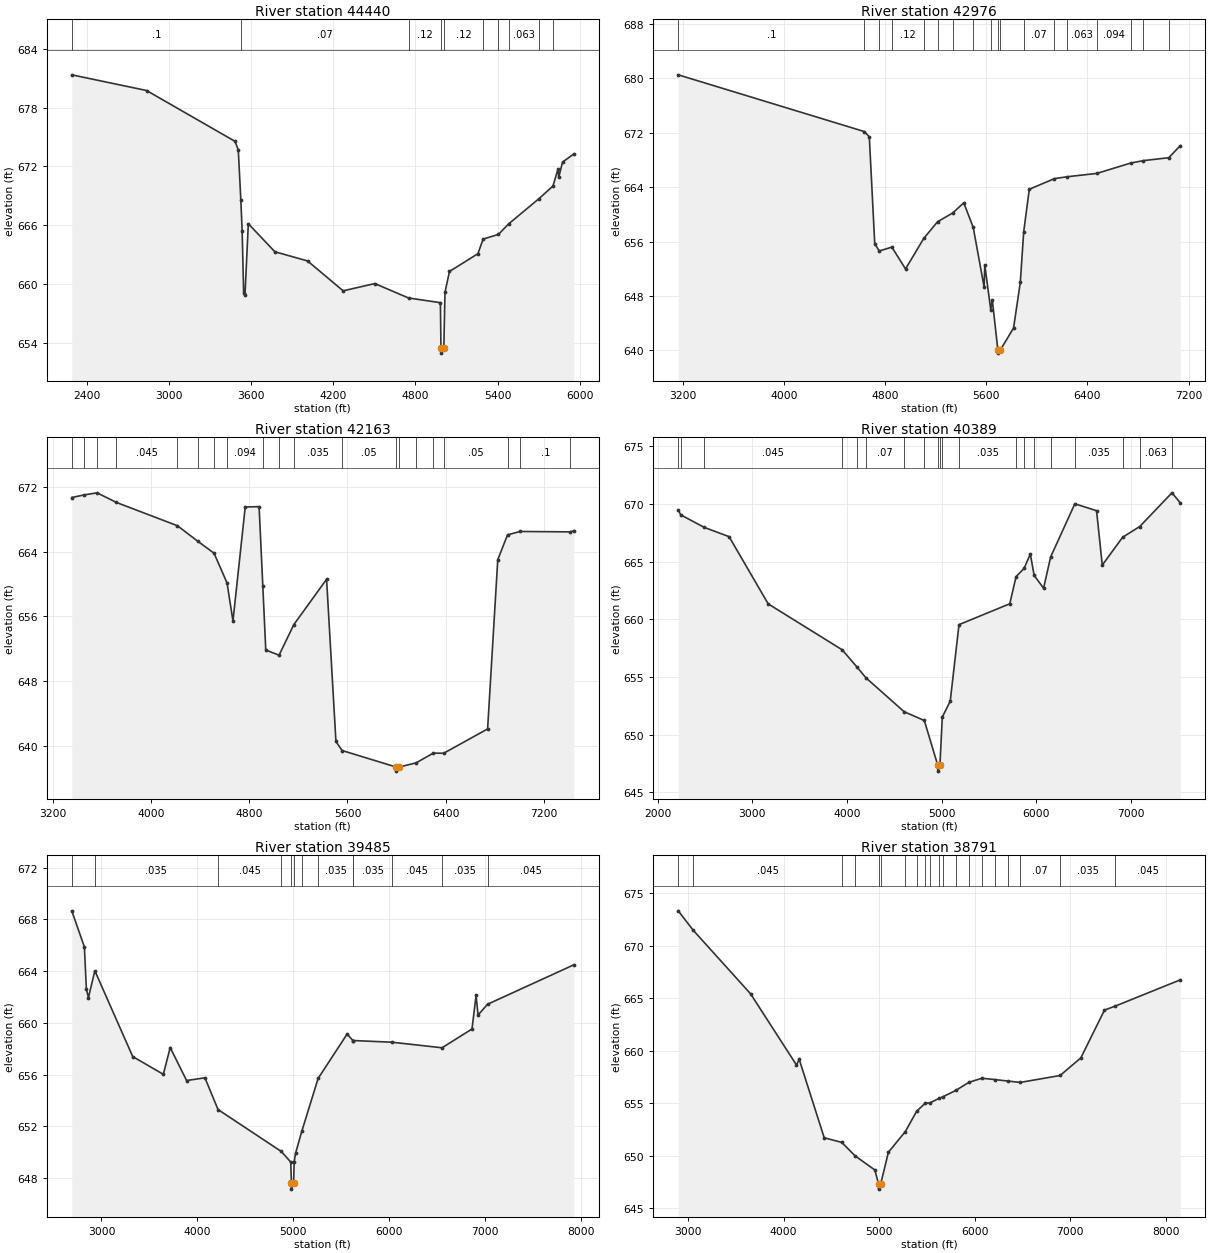
Type RM Length L Ch R = 1 ,44440   ,1464,1464,1464
BEGIN DESCRIPTION:
ALLIGATOR CREEK 138.0
END DESCRIPTION:
XS GIS Cut Line= 3
      2265932.34      13816058.8        2263325.       13815325.
      2262409.14     13815046.51
#Sta/Elev= 30
  2291.2  681.35  2837.1  679.75  3483.1  674.56    3507  673.69  3525.7  668.55
  3535.1  665.44  3546.2  659.11  3555.8  658.84  3580.3  666.15    3774  663.29
  4012.9  662.35  4272.6   659.3  4503.9  660.04  4749.9  658.57  4982.8  658.09
  4986.8  653.44  4987.3  652.94  5007.7  653.44  5016.3  659.16  5049.1  661.28
  5256.8  663.09  5294.6  664.58  5406.6  665.06  5482.3  666.15  5702.7  668.71
  5804.8     670  5841.6  671.74  5846.8  670.89  5874.5  672.44  5957.1  673.27
#Mann= 10 ,-1 , 0
  2291.2      .1       0  3525.7     .07       0  4749.9     .12       0
  4986.8     .05       0  5007.7     .12       0  5294.6    .063       0
  5406.6    .094       0  5482.3    .063       0  5702.7    .094       0
  5804.8      .1       0
Bank Sta=4986.8,5007.7
XS Rating Curve= 0 ,0
Exp/Cntr=0.3,0.1

Type RM Length L Ch R = 1 ,42976   ,813,813,813
BEGIN DESCRIPTION:
X18013
END DESCRIPTION:
XS GIS Cut Line= 3
      2266031.64      13815870.2      2264284.52     13814659.13
      2262468.99      13814976.6
#Sta/Elev= 30
  3165.3  680.51  4636.8  672.17  4675.7   671.4  4718.7   655.7  4754.2  654.62
    4854  655.19  4962.1  651.98  5106.5  656.48  5214.9  658.91  5334.2   660.2
  5422.6   661.7  5497.3  658.08  5583.2  649.33  5588.3  652.57  5635.7  645.99
  5647.8  647.46  5691.7  640.11  5692.2  639.61  5712.6  640.11  5816.1   643.3
  5869.3     650  5896.2  657.44  5940.3  663.69  6138.4  665.25  6238.9  665.53
  6473.9  666.02  6741.5  667.54    6842   667.9  7043.1  668.33  7134.2  670.11
#Mann= 18 ,-1 , 0
  3165.3      .1       0  4636.8    .094       0  4754.2    .035       0
    4854     .12       0  5106.5     .07       0  5214.9    .035       0
  5334.2     .05       0  5497.3     .07       0  5635.7     .05       0
  5691.7     .05       0  5712.6     .05       0  5896.2     .07       0
  6138.4    .035       0  6238.9    .063       0  6473.9    .094       0
  6741.5      .1       0    6842    .063       0  7043.1    .094       0
Bank Sta=5691.7,5712.6
XS Rating Curve= 0 ,0
Exp/Cntr=0.3,0.1

Type RM Length L Ch R = 1 ,42163   ,1774,1774,1774
BEGIN DESCRIPTION:
X18012
END DESCRIPTION:
XS GIS Cut Line= 3
      2266686.83     13815095.92      2264691.52     13814242.21
      2262835.17      13814718.7
#Sta/Elev= 30
  3355.7   670.7  3455.9  671.02  3561.7  671.28  3719.4  670.09  4215.9  667.21
  4383.3  665.27  4513.9  663.81  4619.7  660.13  4667.8  655.43  4767.6  669.53
  4880.5  669.57  4910.7  659.76  4934.8  651.84  5042.9   651.2  5163.1  654.98
  5429.8  660.59    5506  640.53    5556  639.41  5997.2  637.36  5997.7  636.86
  6018.1  637.36    6158  637.88  6299.3  639.09  6382.9  639.07  6740.6  642.08
  6823.2  663.01  6902.7  666.08  7005.2   666.5  7415.1  666.45  7442.5  666.59
#Mann= 20 ,-1 , 0
  3355.7     .07       0  3455.9     .05       0  3561.7    .035       0
  3719.4    .045       0  4215.9    .035       0  4383.3      .1       0
  4513.9      .1       0  4619.7    .094       0  4910.7    .035       0
  5042.9     .12       0  5163.1    .035       0    5556     .05       0
  5997.2    .035       0  6018.1    .035       0    6158     .05       0
  6299.3    .035       0  6382.9     .05       0  6902.7    .063       0
  7005.2      .1       0  7415.1    .063       0
Bank Sta=5997.2,6018.1
XS Rating Curve= 0 ,0
Exp/Cntr=0.3,0.1

Type RM Length L Ch R = 1 ,40389   ,904,904,904
BEGIN DESCRIPTION:
X18011
END DESCRIPTION:
XS GIS Cut Line= 4
      2266716.58     13814996.64      2265287.12     13813904.69
      2264483.05     13813110.55      2262259.77      13812266.9
#Sta/Elev= 30
    2217  669.47  2243.6  669.05  2490.3  667.97  2754.4  667.16    3168  661.33
  3949.8  657.35  4103.7  655.88  4201.2  654.92  4604.7  651.98  4817.9  651.22
  4960.4  647.33  4960.9  646.83    4983  647.33  5008.2  651.52  5091.9  652.89
  5184.5  659.53  5721.4  661.34  5787.7  663.69  5872.7  664.41  5938.7  665.65
    5979   663.8  6078.7  662.69  6153.3   665.4  6409.2  670.01  6638.6  669.41
  6698.9  664.69  6914.5  667.11  7095.5  668.04  7435.4  670.96  7523.9  670.09
#Mann= 20 ,-1 , 0
    2217     .05       0  2243.6    .035       0  2490.3    .045       0
  3949.8    .045       0  4103.7    .045       0  4201.2     .07       0
  4604.7      .1       0  4817.9      .1       0  4960.4     .05       0
    4983      .1       0  5008.2    .045       0  5184.5    .035       0
  5787.7    .063       0  5872.7    .035       0    5979    .035       0
  6153.3    .045       0  6409.2    .035       0  6914.5    .094       0
  7095.5    .063       0  7435.4    .094       0
Bank Sta=4960.4,4983
XS Rating Curve= 0 ,0
Exp/Cntr=0.3,0.1

Type RM Length L Ch R = 1 ,39485   ,694,694,694
BEGIN DESCRIPTION:
ALLIGATOR CREEK 137.0
END DESCRIPTION:
XS GIS Cut Line= 3
      2266795.98     13814698.82        2265325.       13812925.
      2263182.63     13810926.65
#Sta/Elev= 30
  2690.5  668.66    2822  665.87  2842.9  662.61  2864.4  661.96    2931  664.03
    3326   657.4  3645.1  656.03  3716.7   658.1  3887.3  655.55  4078.7  655.76
    4215  653.31  4874.8  650.07  4973.4  649.25  4979.9  647.66  4980.4  647.16
  5003.3  647.66  5008.8  649.26    5023  649.92  5090.6  651.68  5258.6  655.71
  5560.9  659.14  5622.6  658.63  5625.7  658.64  6028.5  658.51  6550.5  658.08
  6862.8  659.53  6905.3  662.12  6926.3  660.61  7024.6  661.44  7924.6  664.49
#Mann= 13 ,-1 , 0
  2690.5     .05       0    2931    .035       0    4215    .045       0
  4874.8     .12       0  4979.9     .05       0  5003.3     .12       0
  5090.6     .07       0  5258.6    .035       0  5622.6     .07       0
  5625.7    .035       0  6028.5    .045       0  6550.5    .035       0
  7024.6    .045       0
Bank Sta=4979.9,5003.3
XS Rating Curve= 0 ,0
Exp/Cntr=0.3,0.1

Type RM Length L Ch R = 1 ,38791   ,408,408,408
BEGIN DESCRIPTION:
ALLIGATOR CREEK 136.0
END DESCRIPTION:
XS GIS Cut Line= 3
        2267375.       13814475.      2265803.32     13812763.12
      2263748.51      13810668.6
#Sta/Elev= 30
  2896.1  673.31    3053  671.46  3653.6  665.41  4134.5  658.63  4162.9  659.17
  4424.9   651.7  4608.6  651.26  4749.3  649.97  4955.8  648.63  4993.4  647.31
  4993.9  646.81  5016.8  647.31    5097  650.32  5274.3  652.29  5393.9  654.24
  5483.1  654.99  5530.5  655.02  5625.1  655.44    5667   655.6  5803.5  656.21
    5940  656.98  6076.5  657.37  6213.1  657.24  6349.6   657.1  6477.1  656.97
  6895.6  657.63  7112.6  659.31  7360.2  663.86  7471.1  664.23  8154.2  666.74
#Mann= 20 ,-1 , 0
  2896.1    .035       0    3053    .045       0  4608.6    .035       0
  4749.3     .12       0  4993.4     .05       0  5016.8     .12       0
  5274.3     .07       0  5393.9    .035       0  5483.1     .07       0
  5530.5    .035       0  5625.1     .07       0    5667    .035       0
  5803.5    .035       0    5940    .035       0  6076.5    .035       0
  6213.1    .035       0  6349.6    .035       0  6477.1     .07       0
  6895.6    .035       0  7471.1    .045       0
Bank Sta=4993.4,5016.8
XS Rating Curve= 0 ,0
Exp/Cntr=0.3,0.1

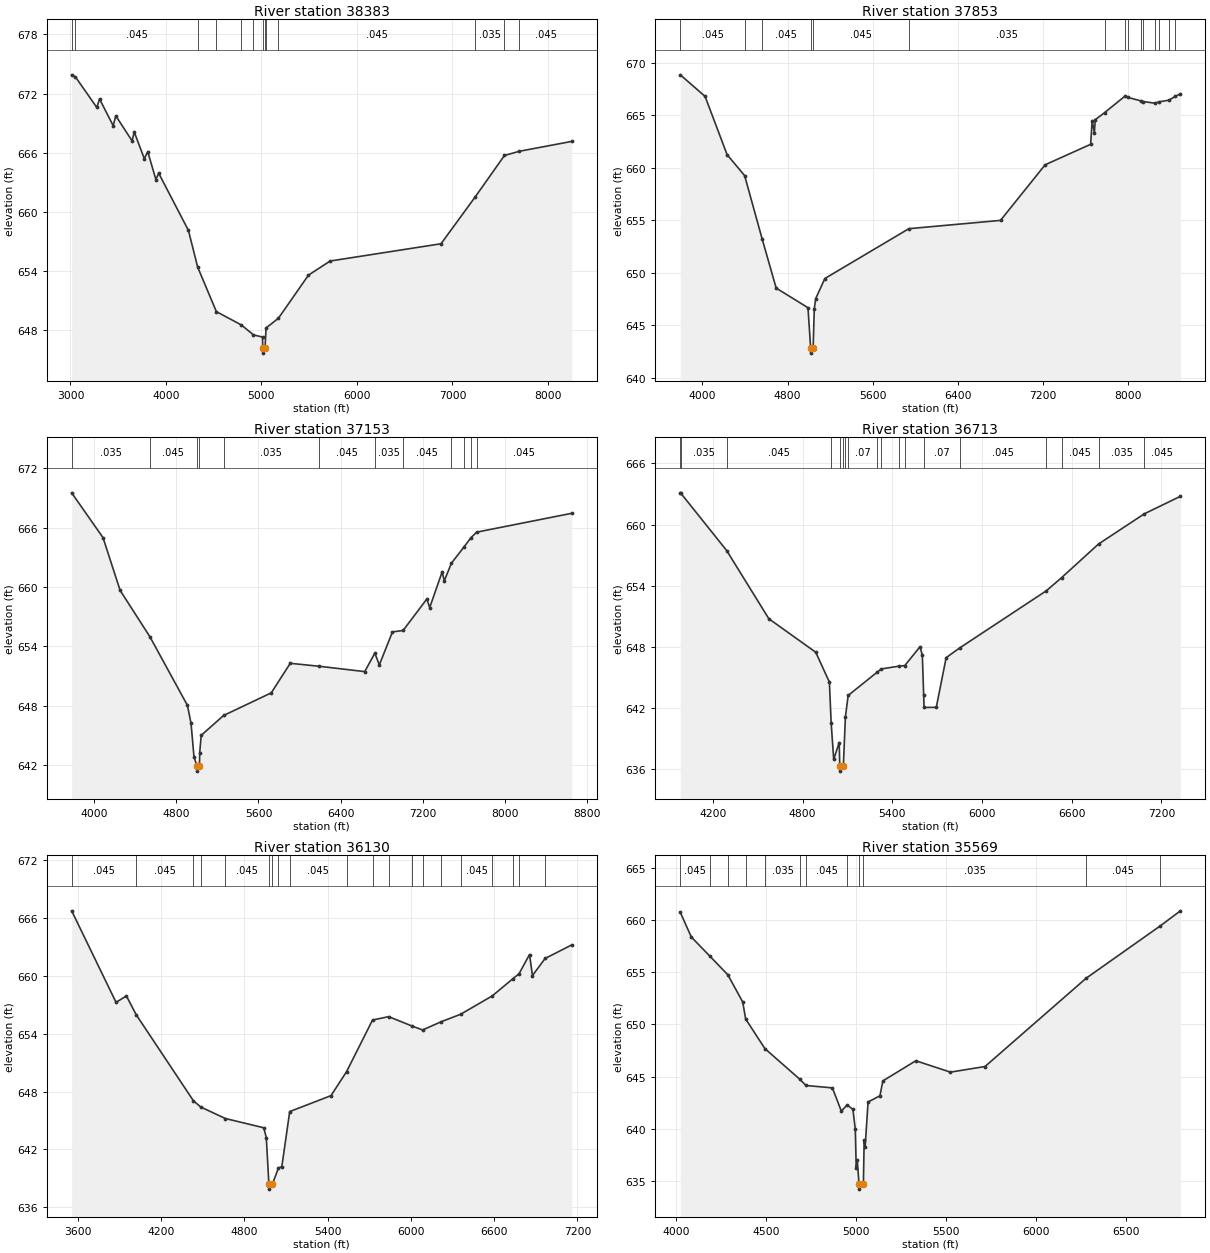
Type RM Length L Ch R = 1 ,38383   ,530,530,530
BEGIN DESCRIPTION:
ALLIGATOR CREEK 135.0
END DESCRIPTION:
XS GIS Cut Line= 3
        2267575.       13814375.        2266325.       13812825.
      2264145.51     13810420.36
#Sta/Elev= 30
  3013.1  673.91  3052.8   673.7  3276.2   670.6    3305  671.46  3447.3  668.76
  3475.6  669.75  3645.7  667.21    3668  668.12  3773.6  665.41  3809.6  666.12
  3895.1  663.29  3923.9  663.94  4235.8  658.13  4332.1  654.42  4528.2   649.9
  4790.7  648.54  4916.7  647.54  5011.4  647.32  5013.8  646.19  5014.3  645.69
  5037.5  646.19  5048.5  648.24  5178.1  649.23  5492.6   653.6  5719.6  655.03
  6880.3  656.78  7240.7  661.56  7544.4  665.73  7700.9  666.16  8249.7  667.16
#Mann= 13 ,-1 , 0
  3013.1    .035       0  3052.8    .045       0  4332.1    .035       0
  4528.2    .045       0  4790.7    .035       0  4916.7     .07       0
  5013.8     .05       0  5037.5     .07       0  5048.5     .12       0
  5178.1    .045       0  7240.7    .035       0  7544.4     .07       0
  7700.9    .045       0
Bank Sta=5013.8,5037.5
XS Rating Curve= 0 ,0
Exp/Cntr=0.3,0.1

Type RM Length L Ch R = 1 ,37853   ,700,700,700
BEGIN DESCRIPTION:
ALLIGATOR CREEK 134.0
END DESCRIPTION:
XS GIS Cut Line= 3
      2267324.99     13813924.98        2266825.       13812825.
      2264641.88     13810102.74
#Sta/Elev= 30
  3791.7  668.85  4024.5   666.8  4231.1  661.26  4396.1  659.26  4559.7  653.27
  4692.4  648.56  4991.2  646.69  5016.1  642.87  5016.6  642.37  5039.8  642.87
  5050.4  646.59  5064.1  647.56  5149.6  649.47  5938.6  654.21  6799.6     655
  7218.9  660.29  7646.2  662.24  7660.6   664.5  7681.4  663.33  7689.4  664.58
  7777.1  665.25  7972.1  666.85  7994.5   666.7  8123.7  666.36  8137.2  666.31
  8252.9  666.15    8289  666.28  8382.2  666.44  8440.8   666.8  8489.5  667.04
#Mann= 15 ,-1 , 0
  3791.7    .045       0  4396.1    .035       0  4559.7    .045       0
  5016.1    .045       0  5039.8    .045       0  5938.6    .035       0
  7777.1     .07       0  7972.1    .035       0  7994.5     .07       0
  8123.7    .045       0  8137.2     .07       0  8252.9    .045       0
    8289    .035       0  8382.2    .045       0  8440.8    .035       0
Bank Sta=5016.1,5039.8
XS Rating Curve= 0 ,0
Exp/Cntr=0.3,0.1

Type RM Length L Ch R = 1 ,37153   ,440,440,440
BEGIN DESCRIPTION:
ALLIGATOR CREEK 133.0
END DESCRIPTION:
XS GIS Cut Line= 3
      2268106.35     13813735.98      2267609.99     13812971.58
      2265099.29     13809915.07
#Sta/Elev= 30
    3782  669.52  4087.3  664.98  4253.4  659.65  4542.6  654.97  4908.2  648.02
  4943.4  646.22  4972.1  642.82  5001.8  641.86  5002.3  641.36  5025.6  641.86
  5028.1  643.23  5042.4  644.98  5260.3  646.99  5724.3  649.28  5909.2  652.27
  6191.6  651.97  6633.9  651.43  6732.1   653.3    6776  652.11  6903.7  655.45
  7007.2  655.59  7238.4  658.78  7266.1  657.91  7387.3  661.52  7408.1  660.62
    7478  662.41    7596  663.99  7667.6  664.98    7723  665.54  8648.9  667.45
#Mann= 12 ,-1 , 0
    3782    .035       0  4542.6    .045       0  5001.8    .045       0
  5025.6    .045       0  5260.3    .035       0  6191.6    .045       0
  6732.1    .035       0  7007.2    .045       0    7478    .035       0
    7596    .045       0  7667.6    .035       0    7723    .045       0
Bank Sta=5001.8,5025.6
XS Rating Curve= 0 ,0
Exp/Cntr=0.3,0.1

Type RM Length L Ch R = 1 ,36713   ,583,583,583
BEGIN DESCRIPTION:
ALLIGATOR CREEK 132.0
END DESCRIPTION:
XS GIS Cut Line= 3
        2268075.       13813375.        2267725.       13812425.
        2266525.       13810425.
#Sta/Elev= 30
  3981.9  663.12  3986.2  663.07  4292.3  657.45  4574.1  650.76  4887.8  647.47
  4979.1  644.54  4990.9  640.56  5007.9  636.96  5044.9  638.61  5048.5   636.3
    5049   635.8  5072.4   636.3  5086.3  641.12  5104.7  643.23  5300.8  645.54
  5325.8  645.83  5442.6   646.1  5483.2  646.16  5585.2  648.01  5600.7  647.18
  5609.6  643.28  5612.4  642.05    5694  642.06  5760.1  646.94  5850.2  647.89
  6429.7   653.5  6532.6   654.8  6779.5   658.1  7085.4  661.06  7326.7  662.78
#Mann= 18 ,-1 , 0
  3981.9    .045       0  3986.2    .035       0  4292.3    .045       0
  4990.9     .07       0  5048.5     .05       0  5072.4     .07       0
  5086.3    .045       0  5104.7     .07       0  5300.8    .045       0
  5325.8     .07       0  5442.6    .045       0  5483.2    .035       0
  5609.6     .07       0  5850.2    .045       0  6429.7     .07       0
  6532.6    .045       0  6779.5    .035       0  7085.4    .045       0
Bank Sta=5048.5,5072.4
XS Rating Curve= 0 ,0
Exp/Cntr=0.3,0.1

Type RM Length L Ch R = 1 ,36130   ,561,561,561
BEGIN DESCRIPTION:
ALLIGATOR CREEK 131.0
END DESCRIPTION:
XS GIS Cut Line= 3
      2268425.01     13813375.02        2268075.       13811975.
        2266625.       13810375.
#Sta/Elev= 30
  3556.6  666.74  3876.2  657.25  3950.9  657.92  4021.3  655.97  4433.5  647.05
  4486.7   646.4  4663.8  645.21  4940.4  644.25  4958.5  643.23  4977.3  638.39
  4977.8  637.89  5001.6  638.39  5046.1  640.08  5070.3  640.22  5127.1  645.93
  5424.5  647.58  5537.1  650.08  5723.7  655.42  5840.2  655.77  6007.7   654.8
  6084.4  654.39  6217.8  655.24  6358.5  656.02    6586  657.92  6735.4  659.71
  6779.1  660.22  6854.5  662.21  6875.6  660.03  6966.5   661.8    7159  663.21
#Mann= 20 ,-1 , 0
  3556.6    .045       0  4021.3    .045       0  4433.5    .035       0
  4486.7    .045       0  4663.8    .045       0  4977.3    .045       0
  5001.6    .045       0  5046.1     .07       0  5127.1    .045       0
  5537.1    .035       0  5723.7    .045       0  5840.2    .035       0
  6007.7    .035       0  6084.4    .045       0  6217.8     .07       0
  6358.5    .045       0    6586    .035       0  6735.4    .045       0
  6779.1    .035       0  6966.5    .045       0
Bank Sta=4977.3,5001.6
XS Rating Curve= 0 ,0
Exp/Cntr=0.3,0.1

Type RM Length L Ch R = 1 ,35569   ,537,537,537
BEGIN DESCRIPTION:
ALLIGATOR CREEK 130.0
END DESCRIPTION:
XS GIS Cut Line= 3
        2268775.     13813025.01        2268575.       13812075.
        2267725.       13810475.
#Sta/Elev= 30
  4021.1  660.75  4082.4  658.38  4184.7  656.56  4285.9  654.75  4368.6  652.14
  4384.7  650.52  4491.8  647.68  4687.2  644.72  4720.5  644.14  4867.4  643.91
  4917.2  641.68  4949.7  642.28  4981.7  641.84  4994.8  639.96  5000.1  636.19
  5005.8  636.99  5015.6   634.7  5016.1   634.2  5039.9   634.7  5044.1  638.87
  5049.7  638.27    5066  642.56    5132  643.15  5148.3  644.58  5331.6  646.51
  5524.1  645.42  5716.6  645.96  6278.8  654.42  6692.9  659.46  6803.7  660.89
#Mann= 12 ,-1 , 0
  4021.1    .045       0  4184.7     .07       0  4285.9    .035       0
  4384.7    .045       0  4491.8    .035       0  4687.2     .07       0
  4720.5    .045       0  4949.7    .035       0  5015.6    .035       0
  5039.9    .035       0  6278.8    .045       0  6692.9    .035       0
Bank Sta=5015.6,5039.9
XS Rating Curve= 0 ,0
Exp/Cntr=0.3,0.1