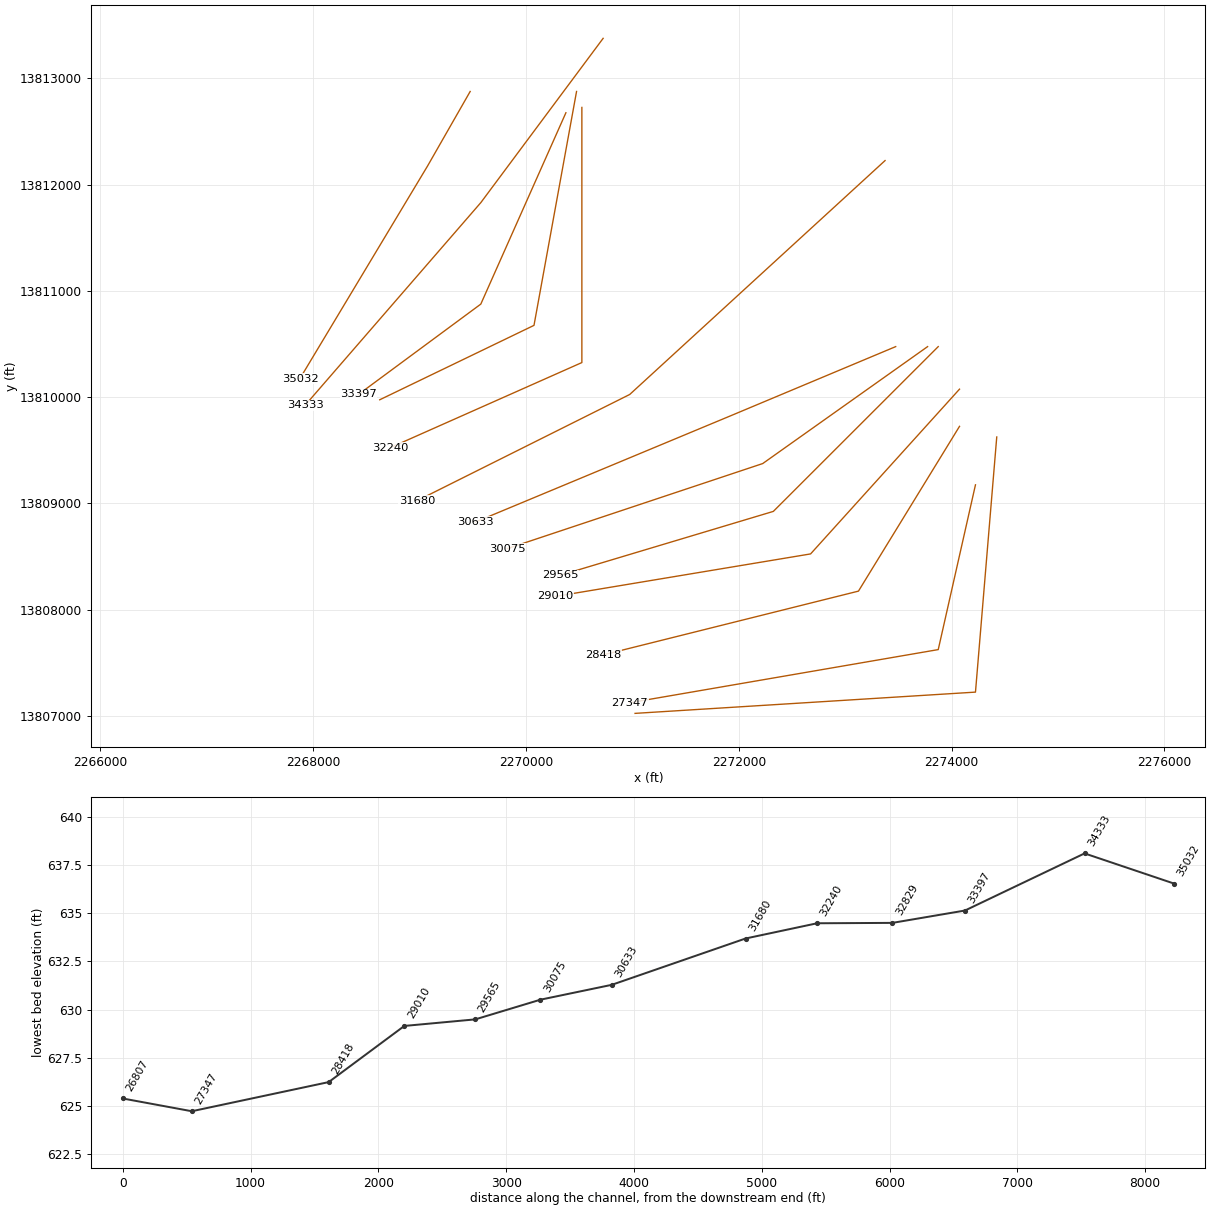
HEC-RAS study ALLIGATOR CREEK.prj: ALLIGATOR CREEK Base Level Engineering

--- ALLIGATOR CREEK.g01 (geometry) --- (continued)

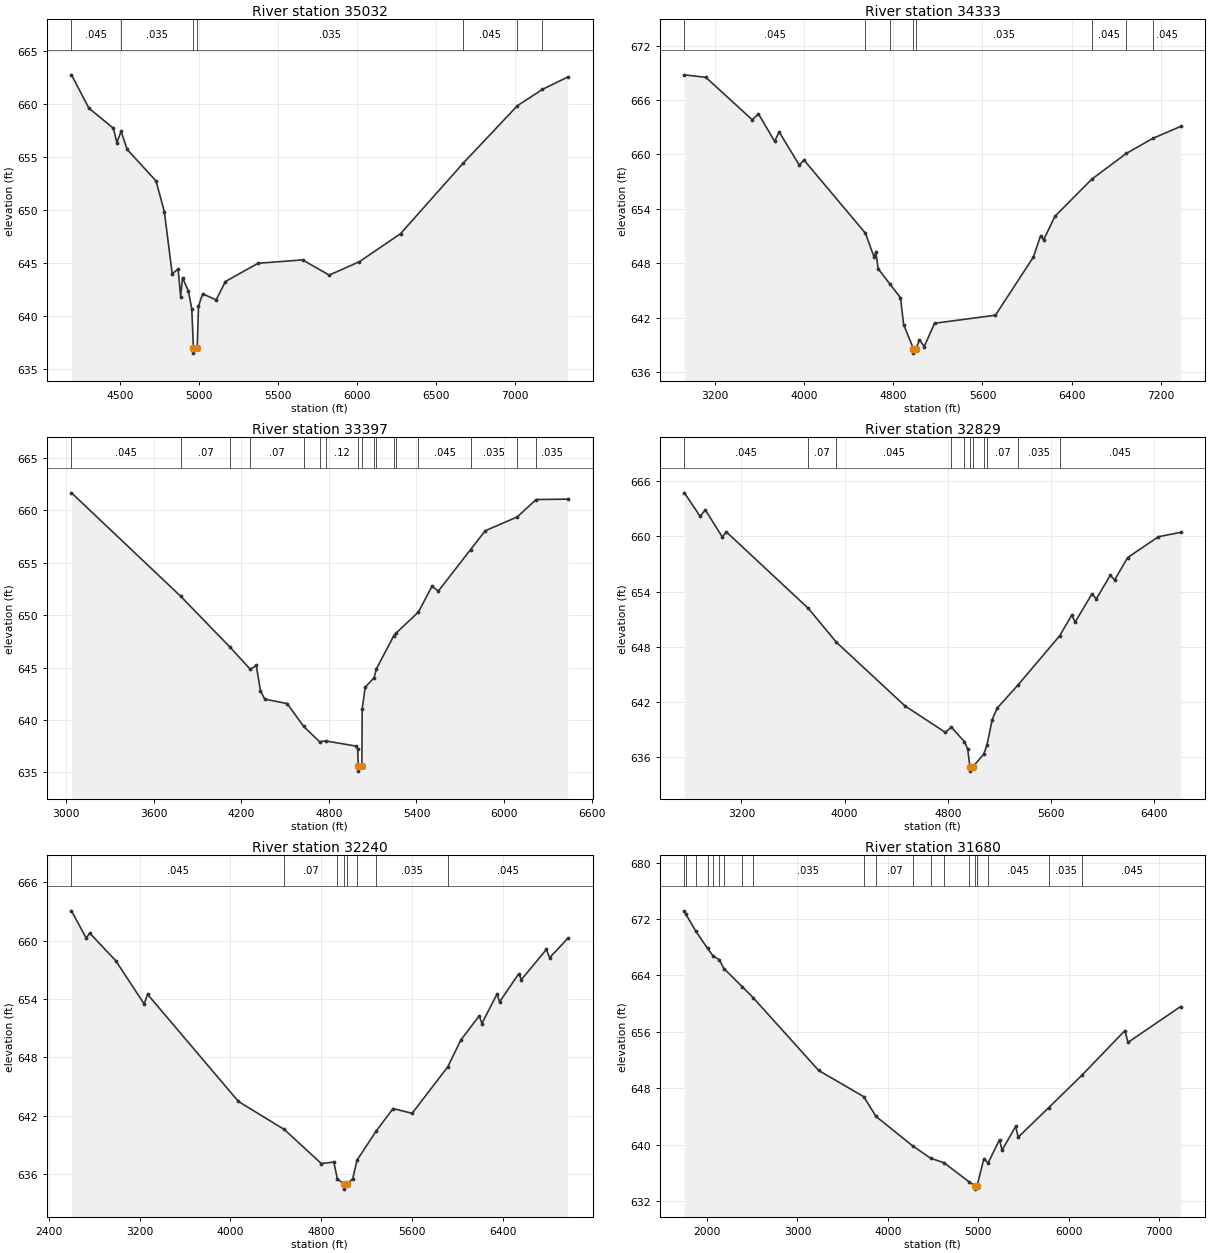
Type RM Length L Ch R = 1 ,35032   ,699,699,699
BEGIN DESCRIPTION:
ALLIGATOR CREEK 129.0
END DESCRIPTION:
XS GIS Cut Line= 3
      2269474.99     13812874.98        2269075.       13812175.
      2267874.99     13810174.99
#Sta/Elev= 30
  4193.9  662.74    4304   659.6  4458.8  657.71  4481.1  656.36  4507.6  657.42
  4545.9  655.72  4728.7  652.74  4781.3  649.85  4830.9  644.01  4868.4  644.44
  4884.2  641.85  4896.4  643.64  4933.2  642.37  4954.8   640.7  4964.9  637.03
  4965.4  636.53  4989.3  637.03  4997.2  640.94  5023.4  642.12  5108.9  641.54
  5167.3  643.27  5373.3  644.99  5655.1  645.31  5824.2  643.88  6014.7  645.14
  6275.1  647.78  6671.3  654.42  7014.1  659.83  7172.4  661.37  7332.5  662.53
#Mann= 7 ,-1 , 0
  4193.9    .045       0  4507.6    .035       0  4964.9    .035       0
  4989.3    .035       0  6671.3    .045       0  7014.1    .035       0
  7172.4    .045       0
Bank Sta=4964.9,4989.3
XS Rating Curve= 0 ,0
Exp/Cntr=0.3,0.1

Type RM Length L Ch R = 1 ,34333   ,936,936,936
BEGIN DESCRIPTION:
ALLIGATOR CREEK 128.0
END DESCRIPTION:
XS GIS Cut Line= 3
      2270724.97     13813374.96      2269575.49       13811830.
      2267925.01     13809925.01
#Sta/Elev= 30
  2928.9  668.77  3121.8  668.49  3536.8  663.82  3593.1  664.46  3737.1  661.45
  3778.8  662.47  3958.1  658.83  4000.8  659.37  4551.4  651.31  4629.7  648.64
  4644.3  649.27  4665.2  647.39  4771.5  645.69  4865.4   644.2  4893.9  641.21
  4981.2  638.59  4981.7  638.09  5005.7  638.59  5035.4  639.56  5078.1  638.81
  5170.3  641.38  5716.4  642.27  6056.4  648.69    6120  651.01  6148.5  650.58
  6248.3  653.16  6577.8  657.25  6888.1   660.1  7125.6  661.76  7375.1  663.08
#Mann= 8 ,-1 , 0
  2928.9    .045       0  4551.4     .07       0  4771.5    .035       0
  4981.2    .035       0  5005.7    .035       0  6577.8    .045       0
  6888.1    .035       0  7125.6    .045       0
Bank Sta=4981.2,5005.7
XS Rating Curve= 0 ,0
Exp/Cntr=0.3,0.1

Type RM Length L Ch R = 1 ,33397   ,568,568,568
BEGIN DESCRIPTION:
ALLIGATOR CREEK 127.0
END DESCRIPTION:
XS GIS Cut Line= 3
      2270374.99     13812674.97        2269575.       13810875.
      2268424.98     13810024.98
#Sta/Elev= 30
  3036.6  661.65    3785  651.79  4123.1  646.94  4261.9  644.83  4302.6   645.2
  4331.3  642.79  4360.7  641.99  4513.9  641.57  4627.4  639.39  4736.6  637.93
  4777.4  638.01  4984.4  637.52  4997.4  637.27  5001.3  635.63  5001.8  635.13
    5026  635.63  5028.3  641.07  5049.1  643.13  5109.2  644.02  5125.3  644.87
  5245.2  648.04    5258  648.25  5413.9   650.3  5506.3  652.74  5550.2  652.29
  5770.5  656.24  5871.7  658.04  6090.4  659.35  6219.6  661.01  6436.4  661.05
#Mann= 17 ,-1 , 0
  3036.6    .045       0    3785     .07       0  4123.1    .045       0
  4261.9     .07       0  4627.4     .12       0  4736.6      .1       0
  4777.4     .12       0  5001.3     .05       0    5026     .12       0
  5109.2     .07       0  5125.3    .035       0  5245.2     .07       0
    5258    .035       0  5413.9    .045       0  5770.5    .035       0
  6090.4    .045       0  6219.6    .035       0
Bank Sta=5001.3,5026
XS Rating Curve= 0 ,0
Exp/Cntr=0.3,0.1

Type RM Length L Ch R = 1 ,32829   ,589,589,589
BEGIN DESCRIPTION:
ALLIGATOR CREEK 126.0
END DESCRIPTION:
XS GIS Cut Line= 3
        2270475.       13812875.        2270075.       13810675.
        2268625.       13809975.
#Sta/Elev= 30
  2757.8  664.72  2879.8  662.18  2920.4  662.86  3052.6  659.91    3083  660.48
  3717.9  652.18  3936.1  648.49  4466.6  641.59  4780.4   638.7  4827.4  639.26
    4928   637.7  4953.2  636.92  4971.3  634.99  4971.8  634.49  4996.1  634.99
    5077  636.32  5102.6  637.28  5143.6  640.08  5182.6  641.34  5343.8  643.85
  5665.6  649.17  5759.5  651.41  5787.6   650.7  5915.5  653.71  5951.4  653.22
  6058.9  655.76  6093.2  655.27  6193.1  657.68  6431.7  659.95    6604  660.43
#Mann= 11 ,-1 , 0
  2757.8    .045       0  3717.9     .07       0  3936.1    .045       0
  4827.4     .07       0    4928    .045       0  4971.3    .045       0
  4996.1    .045       0    5077     .12       0  5102.6     .07       0
  5343.8    .035       0  5665.6    .045       0
Bank Sta=4971.3,4996.1
XS Rating Curve= 0 ,0
Exp/Cntr=0.3,0.1

Type RM Length L Ch R = 1 ,32240   ,560,560,560
BEGIN DESCRIPTION:
ALLIGATOR CREEK 125.0
END DESCRIPTION:
XS GIS Cut Line= 3
        2270525.     13812725.02        2270525.       13810325.
      2268724.99       13809525.
#Sta/Elev= 30
    2600  663.07    2730  660.26    2760  660.79    2990  657.94    3240   653.5
    3270  654.49    4070  643.48  4473.8   640.6    4800   637.1    4910  637.25
  4941.5  635.53  5001.9  634.97  5002.4  634.47  5026.8  634.97  5076.6  635.55
  5114.6  637.45  5283.1  640.44  5431.6  642.75  5599.8  642.26  5913.5  647.04
  6028.7   649.8  6190.8  652.28    6214  651.49  6346.7  654.51    6370  653.72
  6538.2   656.6  6561.5     656  6781.7   659.1  6810.4  658.25  6969.8  660.23
#Mann= 8 ,-1 , 0
    2600    .045       0  4473.8     .07       0  4941.5     .12       0
  5001.9     .05       0  5026.8     .12       0  5114.6    .045       0
  5283.1    .035       0  5913.5    .045       0
Bank Sta=5001.9,5026.8
XS Rating Curve= 0 ,0
Exp/Cntr=0.3,0.1

Type RM Length L Ch R = 1 ,31680   ,1047,1047,1047
BEGIN DESCRIPTION:
ALLIGATOR CREEK 124.0
END DESCRIPTION:
XS GIS Cut Line= 3
      2273375.01     13812225.01        2270975.       13810025.
      2268974.96     13809024.98
#Sta/Elev= 30
  1748.6  673.17  1763.7  672.73  1875.7  670.28  2005.8  667.83  2064.7  666.81
  2135.9  666.22  2186.3  664.98  2388.9  662.41  2508.2  660.87    3235  650.52
  3733.8   646.8  3869.5     644  4275.1  639.82  4472.8  638.08  4623.3  637.41
  4899.9  634.71  4963.8  634.18  4964.3  633.68  4988.9  634.18  5063.1  637.98
  5110.5   637.4  5236.4   640.7  5264.3   639.2  5415.3  642.59  5443.2  641.05
  5779.9  645.23  6152.3  649.89  6622.7  656.16  6659.1  654.51  7240.5  659.59
#Mann= 20 ,-1 , 0
  1748.6    .045       0  1763.7    .035       0  1875.7     .07       0
  2005.8    .035       0  2064.7     .07       0  2135.9    .045       0
  2186.3    .035       0  2388.9    .045       0  2508.2    .035       0
  3733.8    .045       0  3869.5     .07       0  4275.1     .07       0
  4472.8    .045       0  4623.3    .045       0  4899.9     .07       0
  4963.8     .05       0  4988.9     .07       0  5110.5    .045       0
  5779.9    .035       0  6152.3    .045       0
Bank Sta=4963.8,4988.9
XS Rating Curve= 0 ,0
Exp/Cntr=0.3,0.1

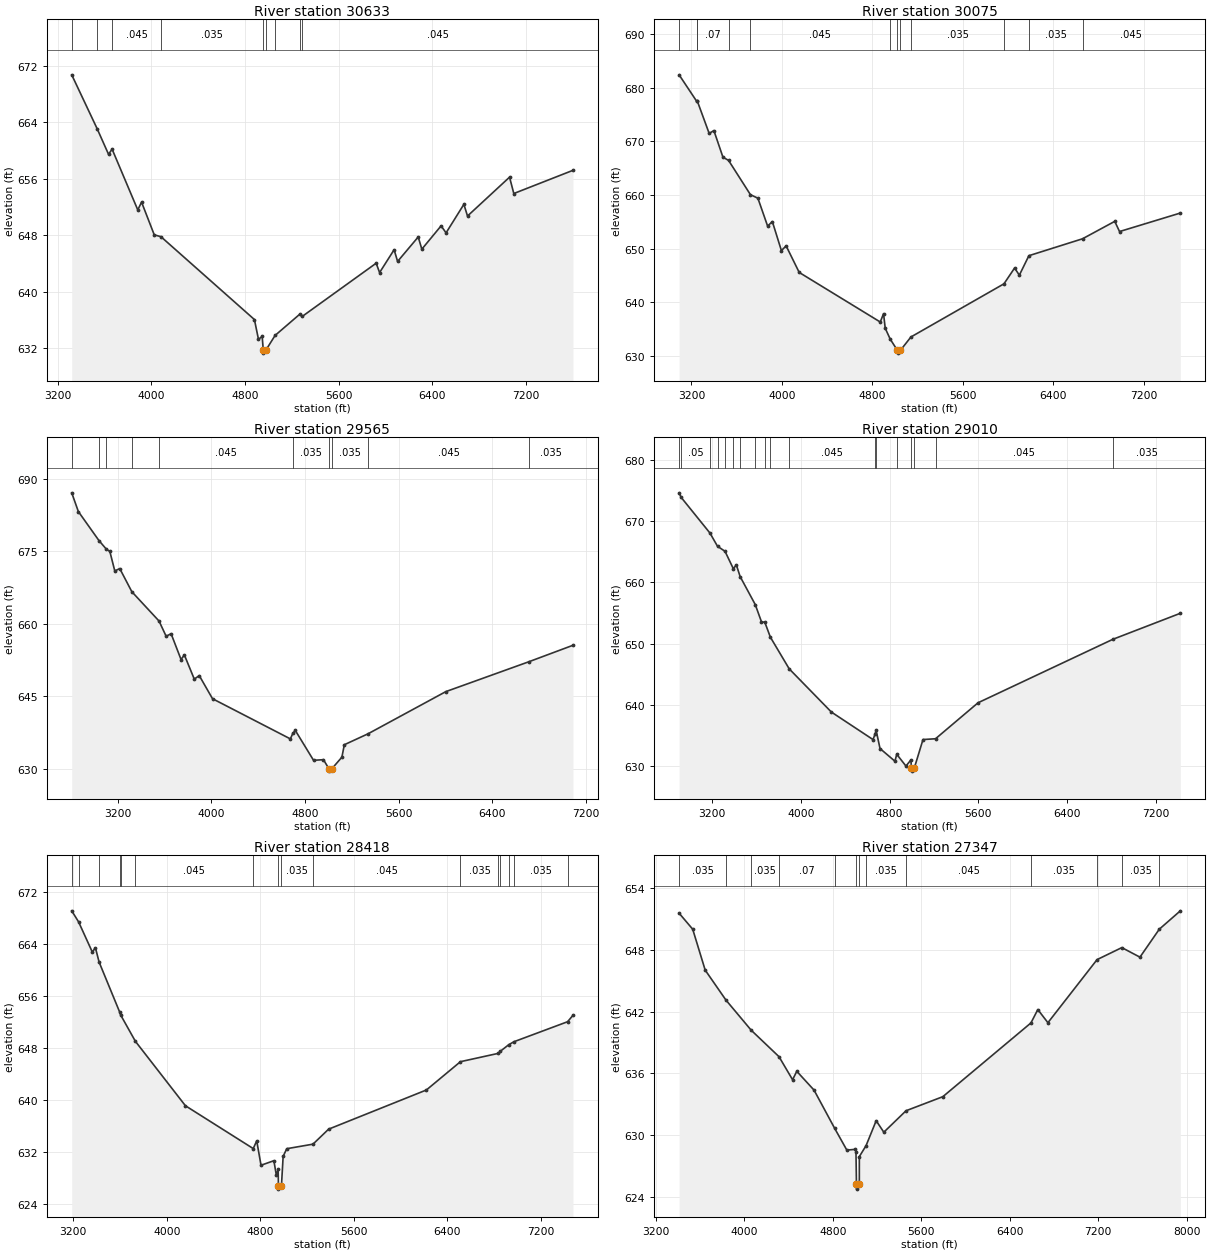
Type RM Length L Ch R = 1 ,30633   ,558,558,558
BEGIN DESCRIPTION:
ALLIGATOR CREEK 123.0
END DESCRIPTION:
XS GIS Cut Line= 3
      2273474.98     13810474.99        2271925.       13809825.
      2269524.96     13808824.98
#Sta/Elev= 30
  3319.5  670.74  3536.8  663.09  3633.9  659.47  3664.3   660.2  3883.4  651.59
  3915.9  652.69  4024.3  648.05  4081.3  647.79  4879.7  636.04  4914.3  633.24
    4946  633.65    4955  631.78  4955.5  631.28  4980.4  631.78  5056.4  633.79
  5267.2   636.8  5288.6  636.49  5919.5  644.03  5948.7   642.7  6072.8  645.94
  6102.5  644.28  6278.6  647.75  6309.5  646.02  6474.1  649.33  6516.4  648.33
  6668.6  652.38  6699.5  650.72  7058.6  656.23  7094.9  653.91  7600.3   657.2
#Mann= 9 ,-1 , 0
  3319.5     .07       0  3536.8    .035       0  3664.3    .045       0
  4081.3    .035       0    4955    .035       0  4980.4    .035       0
  5056.4    .045       0  5267.2     .07       0  5288.6    .045       0
Bank Sta=4955,4980.4
XS Rating Curve= 0 ,0
Exp/Cntr=0.3,0.1

Type RM Length L Ch R = 1 ,30075   ,510,510,510
BEGIN DESCRIPTION:
ALLIGATOR CREEK 122.0
END DESCRIPTION:
XS GIS Cut Line= 3
      2273774.98     13810474.99        2272225.       13809375.
      2269824.96     13808574.99
#Sta/Elev= 30
  3090.9  682.38  3245.3  677.48  3250.5  677.57  3356.6  671.46  3398.4  671.99
  3478.4  667.03  3528.1  666.43  3721.5  660.04  3787.2  659.39  3873.3  654.19
  3915.1  655.03  3995.1  649.62  4036.9   650.5  4152.5  645.55  4868.9  636.31
    4898  637.87  4912.8  635.15  4957.1  633.11  5020.9  631.01  5021.4  630.51
  5046.4  631.01  5139.9  633.52  5962.4  643.43  6056.2  646.37  6098.3  645.04
  6182.6  648.67  6656.5  651.82  6941.6  655.07  6983.8  653.17  7521.4  656.62
#Mann= 12 ,-1 , 0
  3090.9     .07       0  3245.3     .05       0  3250.5     .07       0
  3528.1    .035       0  3721.5    .045       0  4957.1    .035       0
  5020.9    .035       0  5046.4    .035       0  5139.9    .035       0
  5962.4    .045       0  6182.6    .035       0  6656.5    .045       0
Bank Sta=5020.9,5046.4
XS Rating Curve= 0 ,0
Exp/Cntr=0.3,0.1

Type RM Length L Ch R = 1 ,29565   ,555,555,555
BEGIN DESCRIPTION:
ALLIGATOR CREEK 121.0
END DESCRIPTION:
XS GIS Cut Line= 3
      2273875.01     13810475.01        2272325.       13808925.
      2270325.01       13808325.
#Sta/Elev= 30
  2807.5  687.14  2864.1  683.26    3040  677.25  3103.5  675.46  3132.8  675.01
  3175.2  670.96  3217.6  671.45  3320.9  666.65  3553.1  660.58  3613.6  657.43
    3656  657.96  3740.9  652.61  3769.2  653.56    3854  648.55  3896.5  649.28
  4009.6  644.49  4674.3  636.17    4696  637.34  4716.7  637.92  4872.3  631.73
  4957.1  631.86  5003.3  629.99  5003.8  629.49  5028.9  629.99  5114.4  632.38
  5135.3  634.96  5337.4  637.22  6001.8  645.96  6711.1  652.15  7087.6  655.56
#Mann= 10 ,-1 , 0
  2807.5     .07       0    3040     .05       0  3103.5     .07       0
  3320.9    .035       0  3553.1    .045       0    4696    .035       0
  5003.3    .035       0  5028.9    .035       0  5337.4    .045       0
  6711.1    .035       0
Bank Sta=5003.3,5028.9
XS Rating Curve= 0 ,0
Exp/Cntr=0.3,0.1

Type RM Length L Ch R = 1 ,29010   ,592,592,592
BEGIN DESCRIPTION:
ALLIGATOR CREEK 120.0
END DESCRIPTION:
XS GIS Cut Line= 3
      2274074.97     13810074.96        2272675.       13808525.
      2270275.01       13808125.
#Sta/Elev= 30
  2901.2  674.62  2918.7   673.9  3179.4  668.05  3247.6  665.89  3315.6  665.06
  3389.9  662.24  3417.9  662.83  3451.9  660.93  3588.2  656.36  3644.3  653.54
  3674.4  653.48  3724.4  651.04  3894.5  645.86    4275   638.8  4650.2  634.31
  4668.2  635.15  4678.3  635.83  4713.7  632.84  4848.2  630.77  4864.5   631.9
  4947.6  629.98  4992.3  630.98  4997.2  629.65  4997.7  629.15  5022.9  629.65
  5101.3  634.31  5214.5  634.44  5598.1  640.32  6814.4  650.69  7422.9  654.94
#Mann= 18 ,-1 , 0
  2901.2     .07       0  2918.7     .05       0  3179.4     .07       0
  3247.6    .035       0  3315.6     .07       0  3389.9    .035       0
  3451.9     .07       0  3588.2    .035       0  3674.4     .07       0
  3724.4    .035       0  3894.5    .045       0  4668.2    .035       0
  4678.3    .045       0  4864.5    .035       0  4997.2    .035       0
  5022.9    .035       0  5214.5    .045       0  6814.4    .035       0
Bank Sta=4997.2,5022.9
XS Rating Curve= 0 ,0
Exp/Cntr=0.3,0.1

Type RM Length L Ch R = 1 ,28418   ,1071,1071,1071
BEGIN DESCRIPTION:
ALLIGATOR CREEK 119.0
END DESCRIPTION:
XS GIS Cut Line= 3
        2274075.     13809724.99        2273125.       13808175.
      2270725.02       13807575.
#Sta/Elev= 30
  3186.2  669.13  3245.4  667.41  3362.1  662.79  3389.3  663.43  3420.4  661.24
  3595.9  653.56    3605  653.08  3731.3  649.02  4159.7  639.09  4740.3  632.49
  4770.2  633.68  4806.9  629.92  4917.1  630.62  4938.4  628.36  4953.8  629.31
  4956.1  626.74  4956.6  626.24  4981.8  626.74  4996.4  631.29  5027.3  632.47
  5251.8  633.17  5385.5  635.48    6223  641.52  6514.4  645.88  6840.2  647.17
  6855.6  647.48  6927.5  648.49  6973.1  648.96  7431.9  652.04    7478  653.03
#Mann= 16 ,-1 , 0
  3186.2     .05       0  3245.4    .035       0  3420.4     .07       0
  3595.9    .045       0    3605    .035       0  3731.3    .045       0
  4740.3    .035       0  4956.1    .035       0  4981.8    .035       0
  5251.8    .045       0  6514.4    .035       0  6840.2    .094       0
  6855.6    .035       0  6927.5    .094       0  6973.1    .035       0
  7431.9    .045       0
Bank Sta=4956.1,4981.8
XS Rating Curve= 0 ,0
Exp/Cntr=0.3,0.1

Type RM Length L Ch R = 1 ,27347   ,540,540,540
BEGIN DESCRIPTION:
ALLIGATOR CREEK 118.0
END DESCRIPTION:
XS GIS Cut Line= 3
      2274224.99     13809174.97        2273875.       13807625.
      2270974.98       13807125.
#Sta/Elev= 30
    3411  651.59    3534  650.03  3646.8  646.05  3834.7  643.13  4062.7   640.2
  4314.4  637.62  4436.9  635.38    4475   636.2  4630.9  634.37  4817.8  630.64
  4927.5  628.53  5002.5   628.6  5010.1  628.38  5014.4  625.23  5014.9  624.73
  5040.4  625.23  5040.6   627.9  5101.2  628.96  5192.8  631.39  5261.8  630.27
  5462.7  632.36  5795.6  633.73  6592.2  640.91    6654  642.21  6745.4  640.93
  7189.7  647.07  7413.7  648.24  7577.5  647.31  7752.3  650.03  7942.8  651.82
#Mann= 13 ,-1 , 0
    3411    .035       0  3834.7     .07       0  4062.7    .035       0
  4314.4     .07       0  4817.8      .1       0  5014.4     .05       0
  5040.4      .1       0  5101.2    .035       0  5462.7    .045       0
  6592.2    .035       0  7189.7    .094       0  7413.7    .035       0
  7752.3    .045       0
Bank Sta=5014.4,5040.4
XS Rating Curve= 0 ,0
Exp/Cntr=0.3,0.1

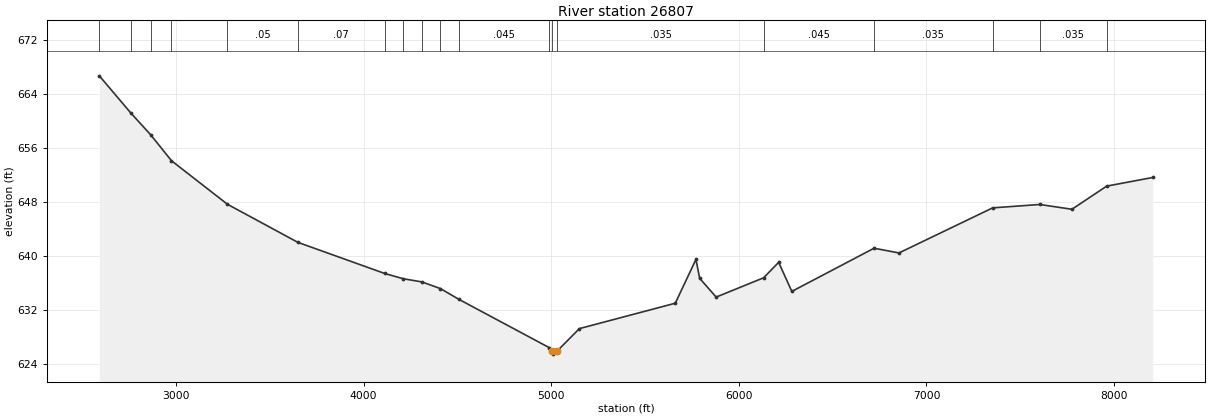
Type RM Length L Ch R = 1 ,26807   ,543,543,543
BEGIN DESCRIPTION:
ALLIGATOR CREEK 117.0
END DESCRIPTION:
XS GIS Cut Line= 3
        2274425.     13809624.97        2274225.       13807225.
      2271025.03       13807025.
#Sta/Elev= 30
  2591.7  666.62  2759.3  661.12  2864.9   657.9  2976.3  654.04  3274.6  647.59
  3649.8  641.95  4112.6  637.34  4211.5  636.56  4310.6  636.09  4409.6   635.1
  4508.6   633.5  4988.3  626.37  5006.9  625.89  5007.4  625.39  5033.2  625.89
  5150.3  629.17  5661.3  632.93  5771.5  639.42  5791.5  636.62  5879.2  633.84
  6132.3   636.7  6212.4  638.99  6282.5  634.68  6720.9  641.08  6853.6  640.38
  7353.2  647.06  7604.1  647.56  7775.4  646.85  7960.7  650.28  8206.2  651.56
#Mann= 19 ,-1 , 0
  2591.7     .05       0  2759.3    .035       0  2864.9     .07       0
  2976.3    .035       0  3274.6     .05       0  3649.8     .07       0
  4112.6     .12       0  4211.5     .07       0  4310.6     .12       0
  4409.6     .07       0  4508.6    .045       0  4988.3    .035       0
  5006.9    .035       0  5033.2    .035       0  6132.3    .045       0
  6720.9    .035       0  7353.2    .094       0  7604.1    .035       0
  7960.7    .045       0
Bank Sta=5006.9,5033.2
XS Rating Curve= 0 ,0
Exp/Cntr=0.3,0.1