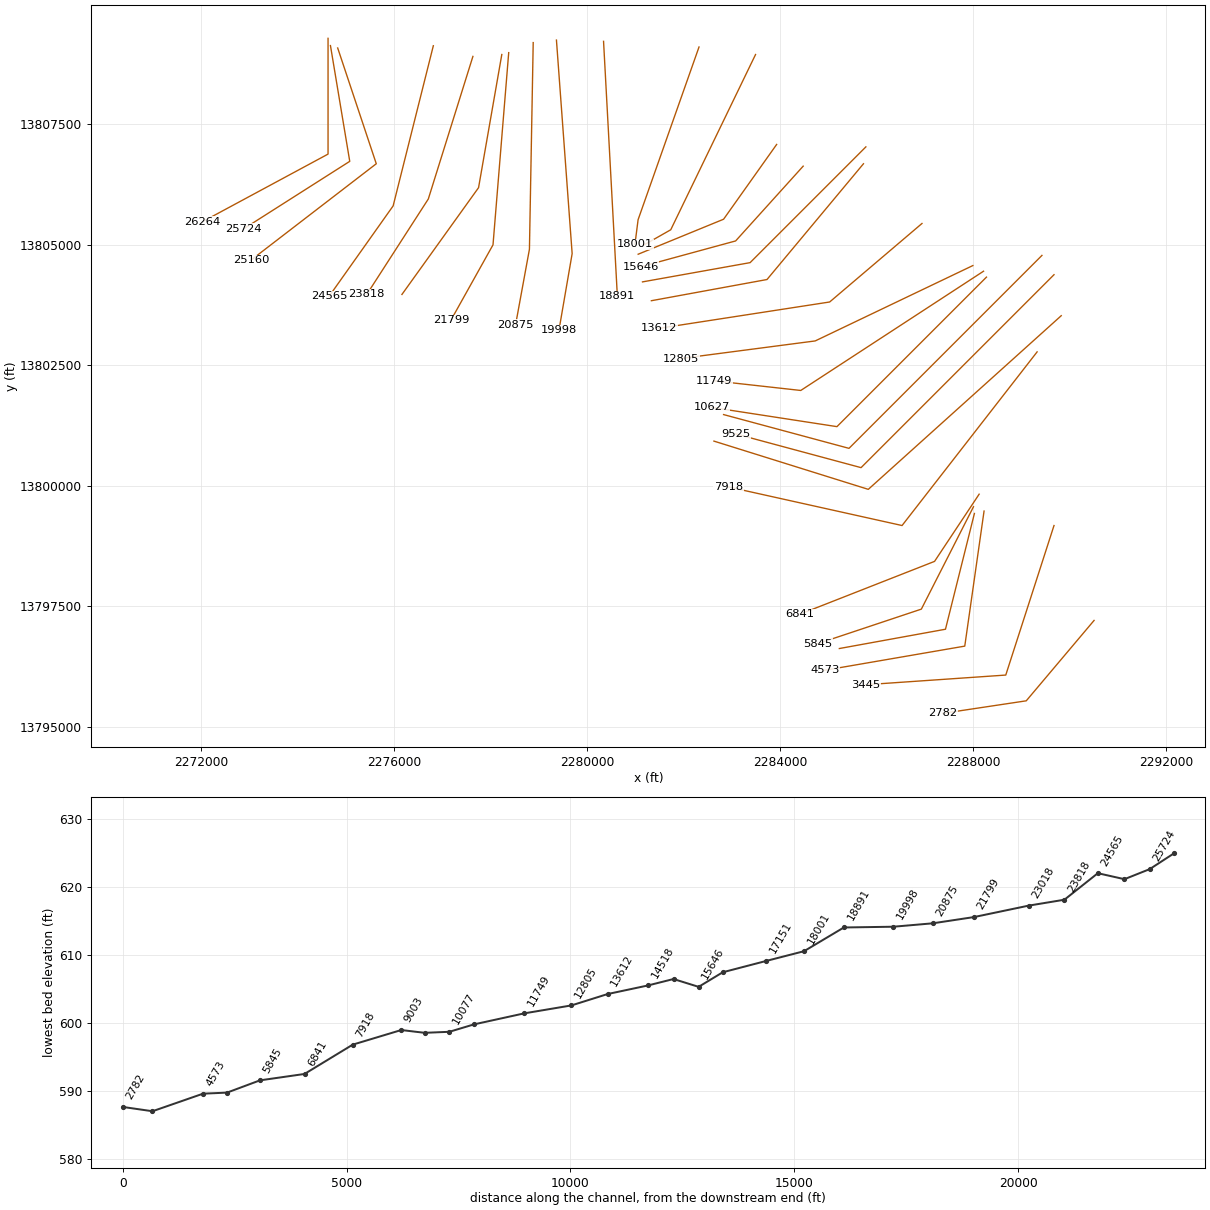
HEC-RAS study ALLIGATOR CREEK.prj: ALLIGATOR CREEK Base Level Engineering

--- ALLIGATOR CREEK.g01 (geometry) --- (continued)

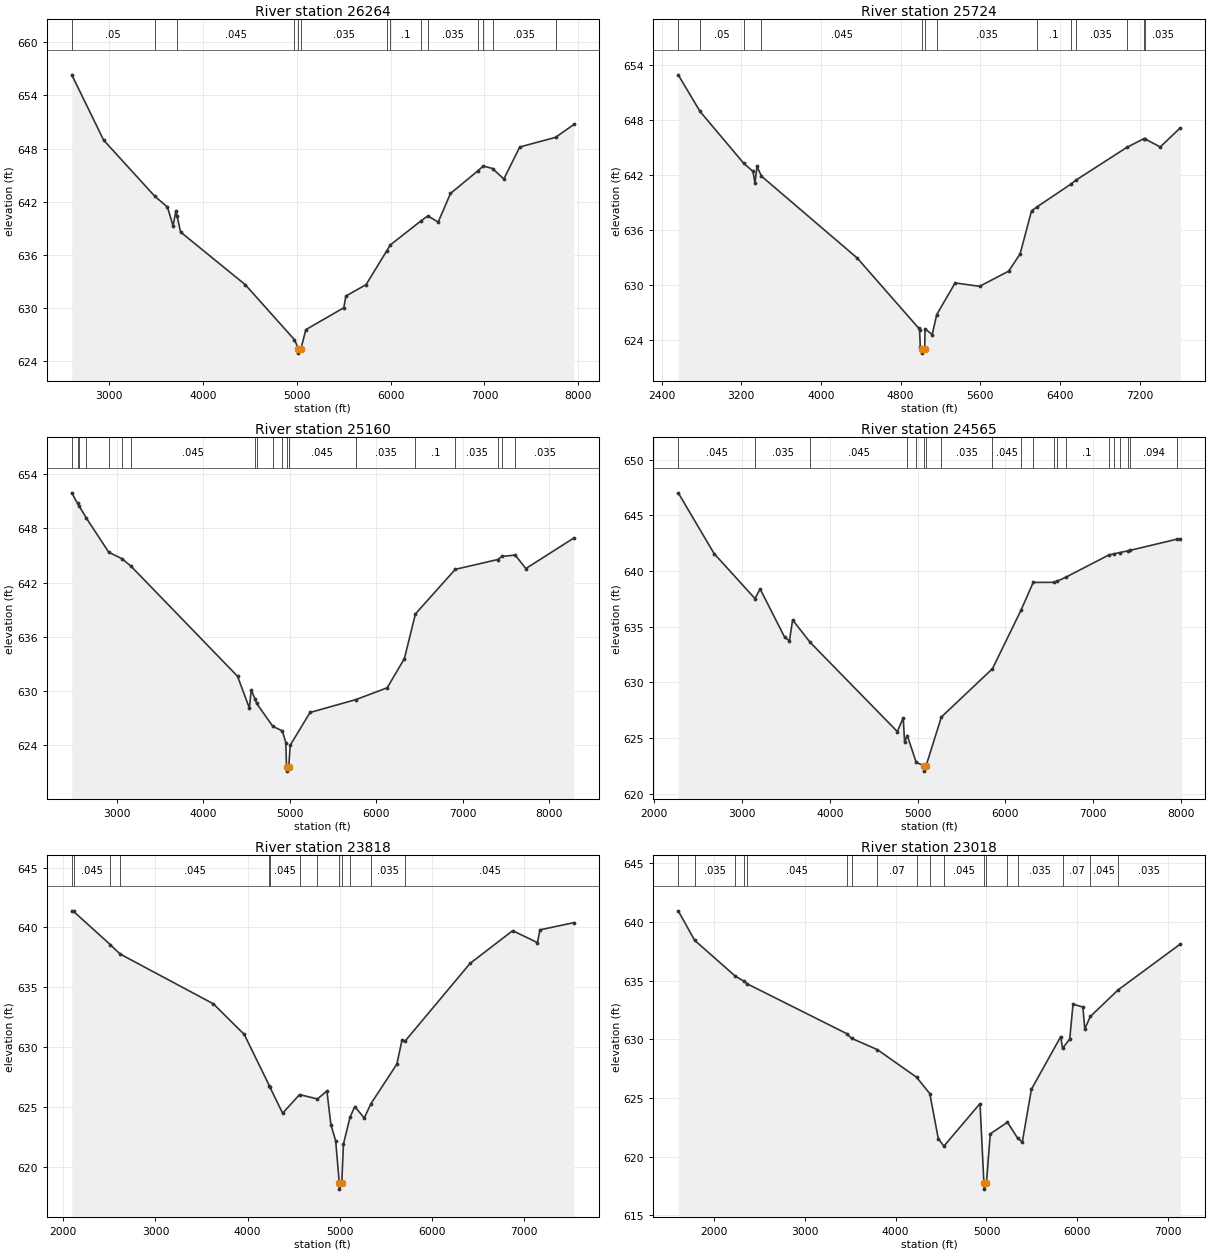
Type RM Length L Ch R = 1 ,26264   ,540,540,540
BEGIN DESCRIPTION:
ALLIGATOR CREEK 116.0
END DESCRIPTION:
XS GIS Cut Line= 3
        2274625.     13809274.99        2274625.       13806875.
      2272024.96     13805474.98
#Sta/Elev= 30
    2600  656.31    2940  648.94  3484.7  642.62    3620   641.4    3680  639.27
    3710  640.98  3723.7  640.34    3760  638.58    4450  632.64  4973.8  626.44
  5016.8  625.42  5017.3  624.92  5043.2  625.42  5095.7  627.57  5500.5  630.04
  5522.4  631.36  5738.2  632.65  5957.7  636.45  5996.9  637.13  6327.3  639.87
    6397   640.4  6506.5   639.7  6637.9  642.93  6928.3  645.47  6987.9  646.03
    7086  645.74  7206.6  644.56  7376.1  648.17  7758.7  649.26    7953  650.71
#Mann= 14 ,-1 , 0
    2600     .05       0  3484.7     .07       0  3723.7    .045       0
  4973.8    .035       0  5016.8    .035       0  5043.2    .035       0
  5957.7    .094       0  5996.9      .1       0  6327.3    .094       0
    6397    .035       0  6928.3    .094       0  6987.9    .063       0
    7086    .035       0  7758.7    .094       0
Bank Sta=5016.8,5043.2
XS Rating Curve= 0 ,0
Exp/Cntr=0.3,0.1

Type RM Length L Ch R = 1 ,25724   ,564,564,564
BEGIN DESCRIPTION:
ALLIGATOR CREEK 115.0
END DESCRIPTION:
XS GIS Cut Line= 3
        2274675.     13809124.99        2275075.       13806725.
      2272874.98     13805324.99
#Sta/Elev= 30
  2567.3   652.9  2786.5  648.91  3226.4  643.25  3317.5   642.4  3337.8  641.13
    3358  642.93    3403  641.87  4364.2  632.96  4980.1  625.34  4990.3   625.1
  4997.9  623.25  5015.9  623.11  5016.4  622.61  5042.4  623.11  5044.4  625.26
  5117.2  624.63  5162.6  626.81  5347.5  630.25    5593  629.88  5884.3  631.53
  5999.4   633.4  6114.6   638.1  6165.7   638.5  6515.4  641.05  6556.2  641.41
  7070.8     645  7243.7  645.96  7249.8  645.95  7406.6  645.05  7608.1  647.13
#Mann= 13 ,-1 , 0
  2567.3     .07       0  2786.5     .05       0  3226.4     .07       0
    3403    .045       0  5015.9    .045       0  5042.4    .045       0
  5162.6    .035       0  6165.7      .1       0  6515.4    .094       0
  6556.2    .035       0  7070.8    .094       0  7243.7    .063       0
  7249.8    .035       0
Bank Sta=5015.9,5042.4
XS Rating Curve= 0 ,0
Exp/Cntr=0.3,0.1

Type RM Length L Ch R = 1 ,25160   ,595,595,595
BEGIN DESCRIPTION:
ALLIGATOR CREEK 114.0
END DESCRIPTION:
XS GIS Cut Line= 3
      2274825.01     13809074.97        2275625.       13806675.
      2273025.03     13804675.02
#Sta/Elev= 30
    2476  651.93  2543.2  650.76  2562.4  650.45  2645.9  649.12  2904.4  645.35
  3056.8  644.64  3159.5  643.83  4394.4  631.63  4531.4   628.1  4552.5   630.1
  4599.8  629.06  4614.1  628.64    4803  626.08  4912.3  625.59  4953.1  624.29
  4960.9  621.63  4961.4  621.13  4987.5  621.63  5003.2  623.99  5233.2  627.62
  5764.6  629.05  6125.8  630.35  6325.1  633.58  6452.8  638.53  6913.9  643.46
  7405.8  644.55  7453.4  644.89  7607.1  645.04  7730.6  643.55    8286  646.93
#Mann= 19 ,-1 , 0
    2476     .07       0  2543.2     .05       0  2562.4    .045       0
  2645.9     .05       0  2904.4     .07       0  3056.8     .05       0
  3159.5    .045       0  4599.8    .035       0  4614.1    .045       0
    4803     .07       0  4912.3    .045       0  4960.9    .045       0
  4987.5    .045       0  5764.6    .035       0  6452.8      .1       0
  6913.9    .035       0  7405.8    .094       0  7453.4    .063       0
  7607.1    .035       0
Bank Sta=4960.9,4987.5
XS Rating Curve= 0 ,0
Exp/Cntr=0.3,0.1

Type RM Length L Ch R = 1 ,24565   ,747,747,747
BEGIN DESCRIPTION:
X18010
END DESCRIPTION:
XS GIS Cut Line= 3
      2276807.91     13809121.63      2275974.58     13805801.35
      2274646.45     13803926.33
#Sta/Elev= 30
  2271.2  647.01  2680.1  641.55  3145.8  637.51  3204.1  638.38  3484.3  634.03
  3538.5  633.72  3574.6  635.59  3775.3  633.57  4768.2  625.56  4834.9   626.8
  4850.5  624.61  4881.1  625.21  4983.3  622.79  5068.8  622.51  5069.3  622.01
  5095.9  622.51  5269.6  626.87  5851.7  631.21  6175.9  636.45  6315.7  638.96
  6549.7  638.97  6582.8  639.05  6685.3  639.42    7178  641.43    7237  641.53
  7301.2  641.64  7400.5  641.81  7424.4  641.85  7950.2  642.84  7992.2  642.82
#Mann= 20 ,-1 , 0
  2271.2    .045       0  3145.8    .035       0  3775.3    .045       0
  4881.1    .035       0  4983.3    .045       0  5068.8    .045       0
  5095.9    .045       0  5269.6    .035       0  5851.7    .045       0
  6175.9    .035       0  6315.7    .094       0  6549.7      .1       0
  6582.8    .094       0  6685.3      .1       0    7178    .094       0
    7237      .1       0  7301.2    .094       0  7400.5      .1       0
  7424.4    .094       0  7950.2    .035       0
Bank Sta=5068.8,5095.9
XS Rating Curve= 0 ,0
Exp/Cntr=0.3,0.1

Type RM Length L Ch R = 1 ,23818   ,800,800,800
BEGIN DESCRIPTION:
X18009
END DESCRIPTION:
XS GIS Cut Line= 3
      2277628.22     13808900.27      2276703.75     13805944.58
      2275427.69     13803965.38
#Sta/Elev= 30
  2091.4  641.39    2111  641.34  2511.3  638.55  2615.4  637.78  3629.2  633.61
  3964.3  631.05  4237.6  626.75  4243.8  626.63  4381.1  624.46  4564.8  626.02
    4759  625.65  4861.8  626.32    4905  623.51  4957.3  622.14  4996.2  618.61
  4996.7  618.11  5023.3  618.61  5041.2  621.88  5113.2  624.13  5164.5  625.02
  5267.1  624.06    5341  625.27  5620.9  628.56  5678.3  630.61  5710.4  630.49
  6416.2  636.99  6878.9  639.73  7148.2  638.73  7175.3   639.8  7543.2   640.4
#Mann= 13 ,-1 , 0
  2091.4    .035       0    2111    .045       0  2511.3    .035       0
  2615.4    .045       0  4237.6     .07       0  4243.8    .045       0
  4564.8    .035       0    4759    .045       0  4996.2    .045       0
  5023.3    .045       0  5113.2    .045       0    5341    .035       0
  5710.4    .045       0
Bank Sta=4996.2,5023.3
XS Rating Curve= 0 ,0
Exp/Cntr=0.3,0.1

Type RM Length L Ch R = 1 ,23018   ,1219,1219,1219
BEGIN DESCRIPTION:
X18008
END DESCRIPTION:
XS GIS Cut Line= 3
      2278227.19     13808939.36      2277745.42     13806178.96
      2276156.87     13803965.41
#Sta/Elev= 30
  1607.2  640.95  1787.5  638.44  2234.9  635.39  2335.4  634.93    2369  634.72
  3461.2  630.49  3514.9  630.09  3800.1  629.12  4231.1  626.77  4376.3  625.38
  4469.8  621.54  4531.4   620.9  4929.1  624.53    4972  617.74  4972.5  617.24
  4999.1  617.74  5042.1  621.95  5231.3  622.94  5344.1  621.57  5394.5  621.26
  5495.2  625.75  5817.4  630.23  5837.1  629.24  5916.4  630.01  5952.8  632.99
  6061.3  632.76  6082.2  630.89  6143.5  631.95    6449  634.21  7133.9  638.12
#Mann= 18 ,-1 , 0
  1607.2    .045       0  1787.5    .035       0  2234.9     .07       0
  2335.4    .035       0    2369    .045       0  3461.2     .07       0
  3514.9    .045       0  3800.1     .07       0  4231.1    .045       0
  4376.3    .035       0  4531.4    .045       0    4972     .05       0
  4999.1    .045       0  5231.3    .045       0  5344.1    .035       0
  5837.1     .07       0  6143.5    .045       0    6449    .035       0
Bank Sta=4972,4999.1
XS Rating Curve= 0 ,0
Exp/Cntr=0.3,0.1

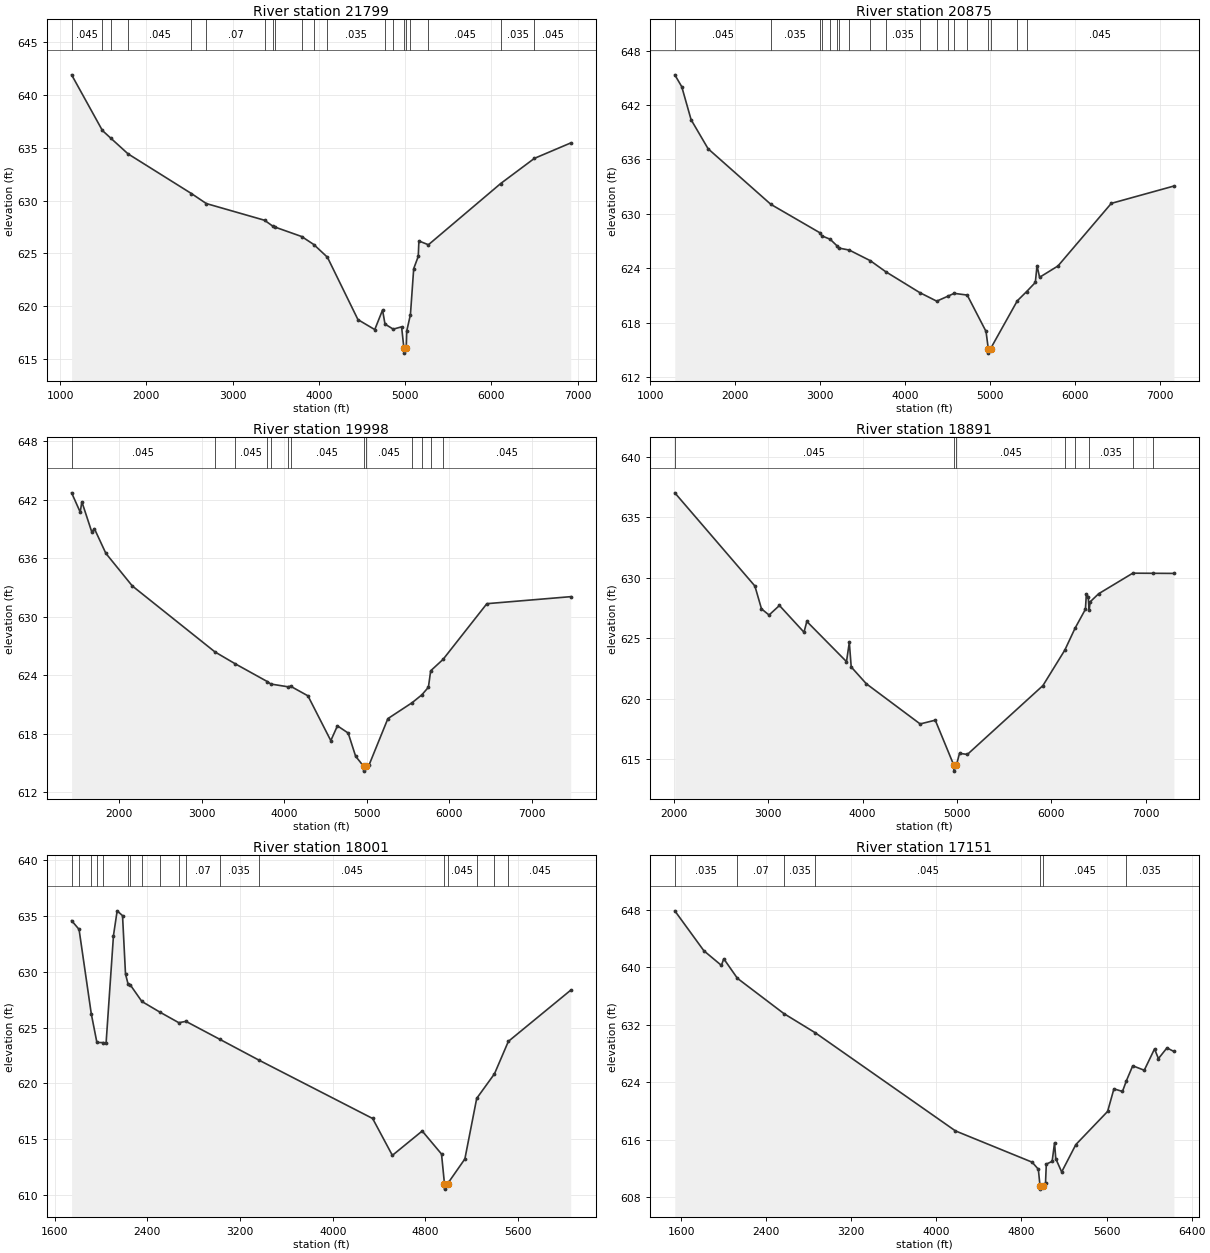
Type RM Length L Ch R = 1 ,21799   ,924,924,924
BEGIN DESCRIPTION:
ALLIGATOR CREEK 113.0
END DESCRIPTION:
XS GIS Cut Line= 3
      2278370.42     13808978.44       2278044.9     13804994.06
       2277172.5     13803431.57
#Sta/Elev= 30
  1133.9  641.91  1490.7  636.64  1589.7   635.9  1787.7  634.43  2522.9  630.67
  2696.2  629.72  3371.3  628.14  3470.3  627.56  3496.6  627.48  3801.4   626.6
  3942.5  625.84  4099.9  624.64  4454.1  618.73    4649  617.79  4739.3  619.64
  4767.7  618.31    4863  617.83    4960  618.05  4986.5  616.06    4987  615.56
  5013.8  616.06  5020.2  617.67  5062.6  619.21  5100.5  623.56  5153.4  624.72
  5160.6  626.18    5271  625.82  6109.4  631.62  6499.9     634  6921.1  635.46
#Mann= 20 ,-1 , 0
  1133.9    .045       0  1490.7    .035       0  1589.7     .07       0
  1787.7    .045       0  2522.9    .035       0  2696.2     .07       0
  3371.3    .045       0  3470.3     .07       0  3496.6    .045       0
  3801.4     .07       0  3942.5    .045       0  4099.9    .035       0
  4767.7    .045       0    4863    .035       0  4986.5    .035       0
  5013.8    .035       0  5062.6     .07       0    5271    .045       0
  6109.4    .035       0  6499.9    .045       0
Bank Sta=4986.5,5013.8
XS Rating Curve= 0 ,0
Exp/Cntr=0.3,0.1

Type RM Length L Ch R = 1 ,20875   ,877,877,877
BEGIN DESCRIPTION:
X18007
END DESCRIPTION:
XS GIS Cut Line= 3
      2278878.23     13809186.73      2278800.11     13804902.92
      2278513.64     13803340.39
#Sta/Elev= 30
  1287.7  645.32  1369.4  644.01  1479.5  640.37  1679.5  637.17  2418.2  631.04
  2992.7  627.92  3017.9  627.57  3116.4  627.19  3198.4  626.45  3214.9  626.23
  3340.9     626  3588.3  624.83  3768.9  623.62  4170.4  621.31  4369.8  620.37
  4502.3  620.92  4575.1  621.23  4728.5  621.04    4950  617.03  4976.2  615.14
  4976.7  614.64  5003.8  615.14  5318.1  620.41  5428.2  621.43  5530.1  622.43
  5550.1  624.28  5580.3     623  5796.7  624.25  6424.1  631.15  7160.8  633.06
#Mann= 19 ,-1 , 0
  1287.7    .045       0  2418.2    .035       0  2992.7    .045       0
  3017.9    .035       0  3116.4    .045       0  3198.4    .035       0
  3214.9    .045       0  3340.9    .035       0  3588.3    .045       0
  3768.9    .035       0  4170.4    .045       0  4369.8    .035       0
  4502.3    .045       0  4575.1    .035       0  4728.5    .045       0
  4976.2    .045       0  5003.8    .045       0  5318.1    .035       0
  5428.2    .045       0
Bank Sta=4976.2,5003.8
XS Rating Curve= 0 ,0
Exp/Cntr=0.3,0.1

Type RM Length L Ch R = 1 ,19998   ,1107,1107,1107
BEGIN DESCRIPTION:
X18006
END DESCRIPTION:
XS GIS Cut Line= 3
        2279360.     13809238.86      2279685.52     13804811.77
      2279412.09     13803223.27
#Sta/Elev= 30
  1423.7  642.71  1527.8  640.73  1547.9  641.79  1668.2  638.69  1699.9  639.03
  1838.7   636.5  2159.5  633.15  3161.2  626.38  3402.6  625.18    3795  623.34
  3839.1  623.08  4045.4   622.8  4077.4  622.86  4288.8  621.87    4566  617.27
  4646.2  618.79  4776.6  618.05  4866.8  615.67  4963.3  614.64  4963.8  614.14
    4991  614.64  5027.3  614.72  5257.9  619.53  5552.6  621.17  5669.5  621.97
  5749.2  622.75  5776.9  624.44  5926.8  625.61  6458.1  631.33  7474.6  632.05
#Mann= 13 ,-1 , 0
  1423.7    .045       0  3161.2    .035       0  3402.6    .045       0
    3795    .035       0  3839.1    .045       0  4045.4    .035       0
  4077.4    .045       0  4963.3    .045       0    4991    .045       0
  5552.6    .035       0  5669.5    .045       0  5776.9    .035       0
  5926.8    .045       0
Bank Sta=4963.3,4991
XS Rating Curve= 0 ,0
Exp/Cntr=0.3,0.1

Type RM Length L Ch R = 1 ,18891   ,890,890,890
BEGIN DESCRIPTION:
X18005
END DESCRIPTION:
XS GIS Cut Line= 2
      2280336.56     13809212.83      2280622.92     13803928.18
#Sta/Elev= 30
  2007.8  637.03  2856.9  629.33    2927  627.44  3007.1  626.93  3117.3  627.72
  3377.6  625.51  3407.7   626.4  3828.3  623.08  3858.3  624.67  3878.4  622.64
  4038.6  621.25  4609.4  617.93  4769.7  618.24  4965.9  614.53  4966.4  614.03
    4994  614.53  5026.7   615.5  5110.2  615.41  5911.3   621.1  6143.3  624.03
  6251.9  625.84    6362  627.41    6372  628.68  6392.1  628.41  6401.5  627.32
  6412.1  628.02  6502.1  628.69  6864.1  630.39  7083.8  630.38  7300.2  630.37
#Mann= 8 ,-1 , 0
  2007.8    .045       0  4965.9    .045       0    4994    .045       0
  6143.3    .035       0  6251.9    .045       0  6401.5    .035       0
  6864.1    .045       0  7083.8    .035       0
Bank Sta=4965.9,4994
XS Rating Curve= 0 ,0
Exp/Cntr=0.3,0.1

Type RM Length L Ch R = 1 ,18001   ,850,850,850
BEGIN DESCRIPTION:
X18004
END DESCRIPTION:
XS GIS Cut Line= 3
      2282315.72     13809095.61      2281052.71     13805514.89
       2280987.8     13805008.57
#Sta/Elev= 30
  1746.5  634.56  1810.7  633.78  1916.1  626.23  1964.7  623.66  2021.6  623.65
    2044  623.61  2107.7  633.23  2139.5  635.44  2185.9  635.01  2211.5  629.79
    2233  628.92  2252.3  628.82  2352.8  627.33  2511.1  626.36  2671.7  625.43
  2733.2  625.55  3026.1  623.94  3363.5  622.08  4344.4  616.86  4514.7  613.56
  4772.2  615.74  4938.9  613.68  4964.1  611.04  4964.6  610.54  4992.4  611.04
  5140.4  613.24  5242.6  618.66  5396.1  620.86  5515.8  623.76  6053.9  628.34
#Mann= 18 ,-1 , 0
  1746.5     .07       0  1810.7    .035       0  1916.1     .07       0
  1964.7    .035       0  2021.6     .05       0    2233    .035       0
  2252.3     .05       0  2352.8    .035       0  2511.1     .07       0
  2671.7    .035       0  2733.2     .07       0  3026.1    .035       0
  3363.5    .045       0  4964.1    .035       0  4992.4    .045       0
  5242.6    .045       0  5396.1    .035       0  5515.8    .045       0
Bank Sta=4964.1,4992.4
XS Rating Curve= 0 ,0
Exp/Cntr=0.3,0.1

Type RM Length L Ch R = 1 ,17151   ,967,967,967
BEGIN DESCRIPTION:
ALLIGATOR CREEK 112.0
END DESCRIPTION:
XS GIS Cut Line= 3
      2283487.61     13808939.38      2281729.79     13805306.56
      2281158.43     13804981.92
#Sta/Elev= 30
  1540.2  647.82  1813.7  642.26  1978.3  640.23  2000.5  641.15  2128.8  638.43
  2565.3  633.53  2862.4  630.84  4179.2   617.2    4900  612.85  4958.4  611.87
  4973.9   609.6  4974.4   609.1  5003.8   609.6  5026.1  610.02  5033.3  612.58
  5088.3  612.96  5110.9  615.56  5122.2  613.34  5177.8  611.49  5311.1   615.3
  5609.8  619.91    5669  623.05  5749.7  622.69  5787.2  624.21    5846  626.26
  5954.4  625.64    6051  628.61  6087.5  627.26    6168  628.75  6233.1  628.25
#Mann= 7 ,-1 , 0
  1540.2    .035       0  2128.8     .07       0  2565.3    .035       0
  2862.4    .045       0  4973.9    .045       0  5003.8    .045       0
  5787.2    .035       0
Bank Sta=4973.9,5003.8
XS Rating Curve= 0 ,0
Exp/Cntr=0.3,0.1

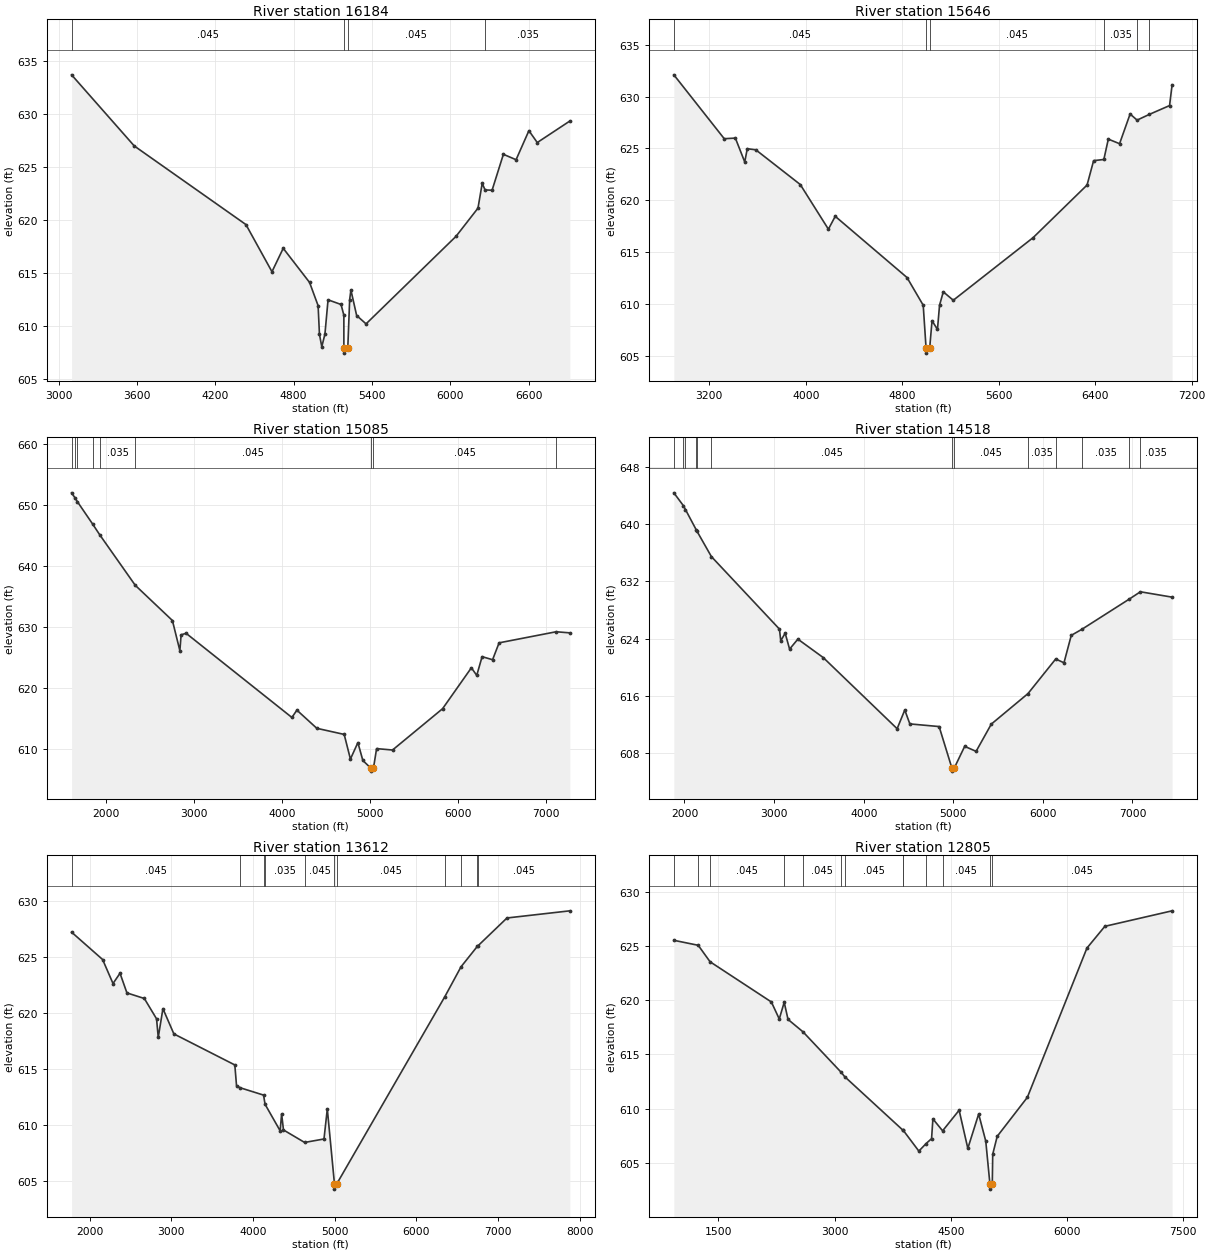
Type RM Length L Ch R = 1 ,16184   ,538,538,538
BEGIN DESCRIPTION:
ALLIGATOR CREEK 111.0
END DESCRIPTION:
XS GIS Cut Line= 3
      2283925.01     13807075.01        2282825.       13805525.
      2281054.27     13804799.39
#Sta/Elev= 30
  3099.8   633.7  3579.6  626.99  4434.6  619.57  4633.9  615.12    4720  617.33
  4921.7  614.11    4987  611.92  4997.4  609.21  5015.2  608.04  5039.2  609.23
  5063.2  612.47  5162.6  612.03  5184.2  611.02  5184.3  607.94  5184.8  607.44
  5214.3  607.94  5228.7   612.5  5238.2  613.39  5282.1  610.99  5354.1   610.2
  6042.8  618.46  6210.9  621.12  6243.3  623.46  6265.1  622.84  6318.9  622.81
  6405.4   626.2  6502.6  625.69  6600.7  628.43  6664.8  627.31  6914.1  629.34
#Mann= 4 ,-1 , 0
  3099.8    .045       0  5184.3    .045       0  5214.3    .045       0
  6265.1    .035       0
Bank Sta=5184.3,5214.3
XS Rating Curve= 0 ,0
Exp/Cntr=0.3,0.1

Type RM Length L Ch R = 1 ,15646   ,561,561,561
BEGIN DESCRIPTION:
ALLIGATOR CREEK 110.0
END DESCRIPTION:
XS GIS Cut Line= 3
      2284475.02     13806625.02        2283075.       13805075.
      2281104.78     13804538.33
#Sta/Elev= 30
  2906.7  632.09  3324.5  625.94  3416.7     626  3494.5   623.7  3515.4  624.98
  3586.4  624.87  3954.8  621.53    4188  617.23  4244.7  618.47  4839.6  612.58
  4974.1  609.91  4997.6   605.8  4998.1   605.3  5027.8   605.8  5047.2  608.42
  5092.2  607.58  5109.4  609.91  5140.5   611.2  5223.4  610.39  5885.5  616.42
  6332.4  621.48  6386.8  623.83  6471.5  623.94  6508.6   625.9  6601.9  625.46
  6689.3  628.32  6747.1  627.73  6848.4  628.28  7016.4  629.13  7037.4  631.13
#Mann= 6 ,-1 , 0
  2906.7    .045       0  4997.6    .045       0  5027.8    .045       0
  6471.5    .035       0  6747.1    .045       0  6848.4    .035       0
Bank Sta=4997.6,5027.8
XS Rating Curve= 0 ,0
Exp/Cntr=0.3,0.1

Type RM Length L Ch R = 1 ,15085   ,567,567,567
BEGIN DESCRIPTION:
ALLIGATOR CREEK 109.0
END DESCRIPTION:
XS GIS Cut Line= 3
      2285774.97     13807024.97        2283375.       13804625.
       2281143.9     13804225.84
#Sta/Elev= 30
  1605.9  651.94  1645.7   651.1  1671.1  650.51  1844.6  646.85  1926.2  645.07
  2329.1  636.83  2751.4  631.07  2836.2  626.14  2850.4  628.73  2906.9  628.98
    4109  615.22  4165.6  616.42  4391.9  613.45    4703  612.45  4773.7  608.42
  4858.6  611.11  4915.1  608.19  5004.9  606.95  5005.4  606.45  5035.7  606.95
  5071.1  610.13  5252.2   609.9  5820.5  616.65  6147.9  623.34  6208.9   622.1
  6269.8  625.16  6388.9  624.66  6462.8  627.42  7110.9  629.23  7266.5  629.05
#Mann= 9 ,-1 , 0
  1605.9    .035       0  1645.7    .045       0  1671.1    .035       0
  1844.6    .045       0  1926.2    .035       0  2329.1    .045       0
  5004.9    .045       0  5035.7    .045       0  7110.9    .035       0
Bank Sta=5004.9,5035.7
XS Rating Curve= 0 ,0
Exp/Cntr=0.3,0.1

Type RM Length L Ch R = 1 ,14518   ,906,906,906
BEGIN DESCRIPTION:
ALLIGATOR CREEK 108.0
END DESCRIPTION:
XS GIS Cut Line= 3
      2285724.98     13806674.98        2283725.       13804275.
      2281328.12     13803835.57
#Sta/Elev= 30
  1881.2  644.35  1986.9  642.57  2010.7  642.02    2131  639.19  2138.5  639.01
  2300.4  635.45  3059.9  625.33  3074.2   623.7  3123.7  624.76  3173.1  622.54
  3265.5  623.93  3549.3  621.35  4373.3  611.43  4458.6  614.04  4515.2   612.1
  4841.9  611.73  4982.7  606.01  4983.2  605.51  5013.5  606.01  5127.3  608.97
  5254.6  608.27  5424.2  612.07  5833.6  616.33  6143.1  621.16  6235.4  620.63
  6316.8  624.46  6437.4  625.32    6963  629.51  7088.3  630.54  7442.1  629.79
#Mann= 13 ,-1 , 0
  1881.2    .035       0  1986.9    .045       0  2010.7    .035       0
    2131    .045       0  2138.5    .035       0  2300.4    .045       0
  4982.7    .045       0  5013.5    .045       0  5833.6    .035       0
  6143.1    .045       0  6437.4    .035       0    6963    .045       0
  7088.3    .035       0
Bank Sta=4982.7,5013.5
XS Rating Curve= 0 ,0
Exp/Cntr=0.3,0.1

Type RM Length L Ch R = 1 ,13612   ,807,807,807
BEGIN DESCRIPTION:
X18003
END DESCRIPTION:
XS GIS Cut Line= 3
      2286938.13     13805436.77      2285024.06     13803809.17
      2281482.35     13803262.28
#Sta/Elev= 30
  1780.4  627.25    2160   624.8  2287.4  622.65    2373  623.57  2457.6  621.81
  2670.7  621.31    2820  619.49  2840.9  617.83    2898   620.4  3031.9  618.14
  3777.7  615.36  3798.5  613.51  3841.7  613.32  4129.4  612.66  4147.5  611.84
  4332.4  609.46  4350.3  610.98  4372.9  609.54  4631.7  608.42  4868.7  608.73
  4909.2  611.42  4996.4  604.74  4996.9  604.24  5027.4  604.74    6347  621.47
  6545.4  624.15    6744  625.97  6747.4  625.99  7107.6  628.52  7876.6  629.16
#Mann= 11 ,-1 , 0
  1780.4    .045       0  3841.7    .035       0  4129.4     .07       0
  4147.5    .035       0  4631.7    .045       0  4996.4    .045       0
  5027.4    .045       0    6347    .035       0  6545.4     .07       0
    6744    .035       0  6747.4    .045       0
Bank Sta=4996.4,5027.4
XS Rating Curve= 0 ,0
Exp/Cntr=0.3,0.1

Type RM Length L Ch R = 1 ,12805   ,1056,1056,1056
BEGIN DESCRIPTION:
ALLIGATOR CREEK 107.0
END DESCRIPTION:
XS GIS Cut Line= 3
      2287992.83     13804564.38      2284724.58     13803001.87
      2281939.08     13802637.42
#Sta/Elev= 30
   924.1  625.53  1238.6  625.07  1391.7  623.55    2183  619.84    2285  618.27
  2348.8  619.81  2398.1  618.23    2592  617.08  3084.1  613.35  3127.7  612.96
  3885.6  607.98  3887.1  607.98  4086.8  606.08  4181.3  606.78    4251  607.23
  4268.2  609.05  4393.6  607.95  4606.7  609.85    4719  606.33  4858.9   609.5
  4950.6     607  5003.9  603.07  5004.4  602.57  5034.9  603.07  5040.4  605.79
  5098.3  607.44  5487.6  611.04  6256.3  624.81  6487.9  626.82  7355.9  628.25
#Mann= 13 ,-1 , 0
   924.1    .045       0  1238.6    .035       0  1391.7    .045       0
  2348.8    .035       0    2592    .045       0  3084.1    .035       0
  3127.7    .045       0  3885.6    .035       0  3887.1    .045       0
  4181.3    .035       0  4393.6    .045       0  5003.9    .045       0
  5034.9    .045       0
Bank Sta=5003.9,5034.9
XS Rating Curve= 0 ,0
Exp/Cntr=0.3,0.1

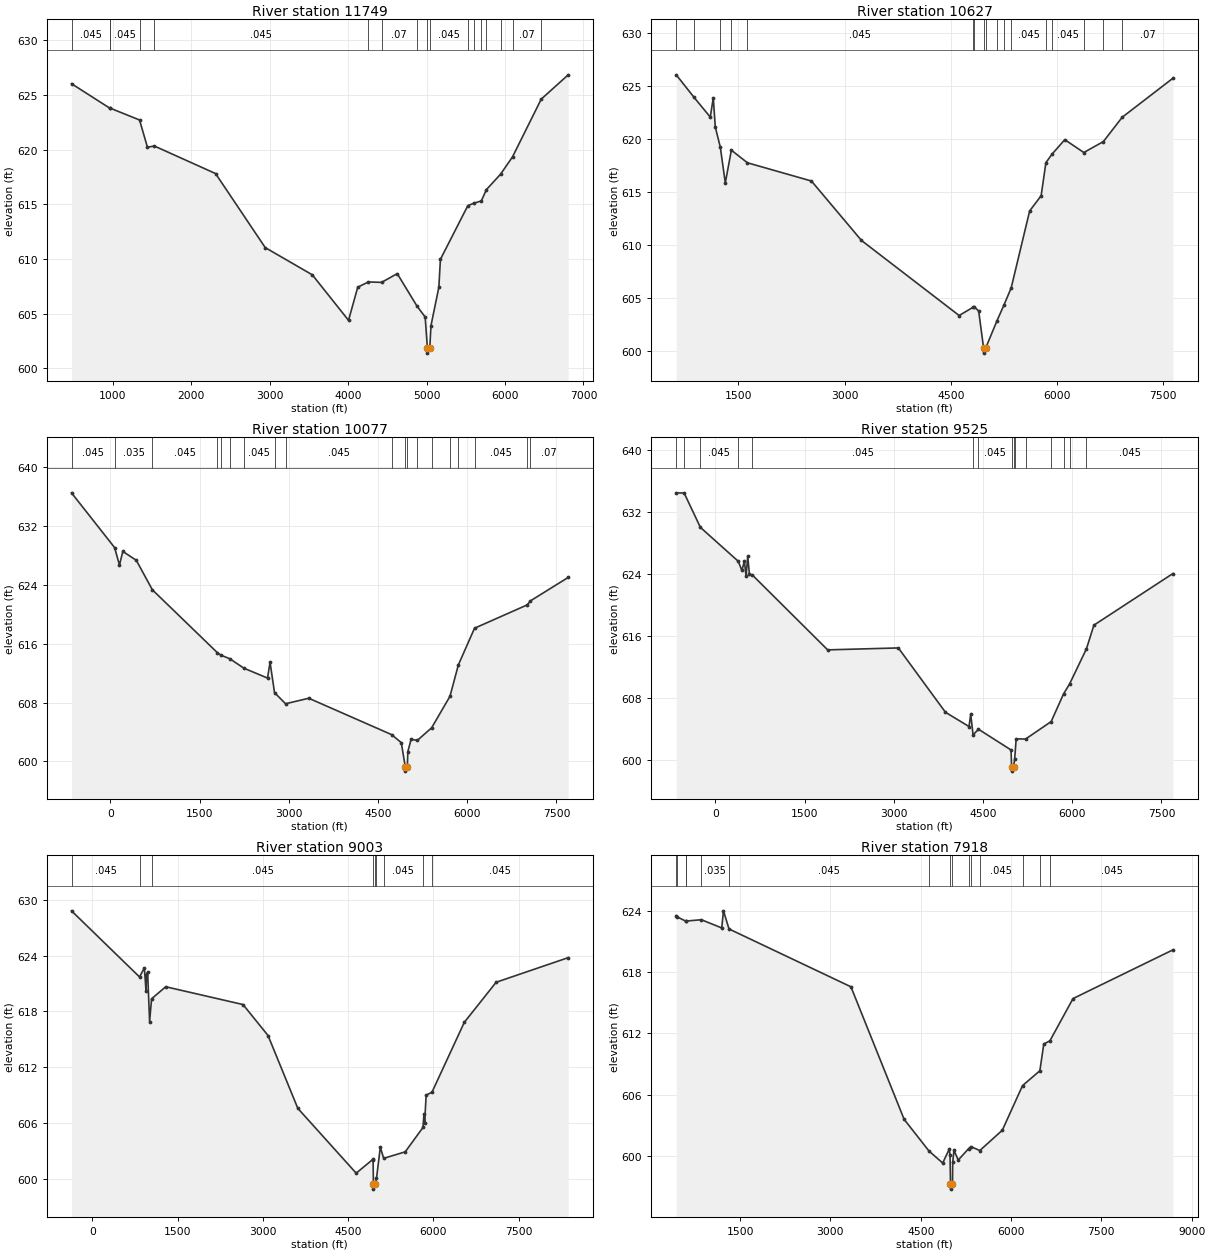
Type RM Length L Ch R = 1 ,11749   ,1122,1122,1122
BEGIN DESCRIPTION:
ALLIGATOR CREEK 106.0
END DESCRIPTION:
XS GIS Cut Line= 3
      2288214.16     13804447.18        2284425.       13801975.
      2282624.99       13802175.
#Sta/Elev= 30
   470.6  626.04   961.2  623.79   964.7   623.8  1338.5  622.72  1439.1  620.23
  1527.2  620.34  2308.1  617.82  2941.6  611.05  3542.1  608.56  4003.9   604.4
  4121.5  607.43  4257.5  607.91  4426.1  607.87  4625.2  608.67  4875.5  605.72
  4981.4   604.7  5009.5   601.9    5010   601.4  5040.7   601.9  5055.3  603.91
  5155.9  607.42    5176  609.98  5525.2  614.88  5598.5   615.1  5697.9  615.32
  5762.3  616.35  5942.8  617.76  6095.6  619.35    6462  624.63    6806  626.85
#Mann= 17 ,-1 , 0
   470.6    .045       0   961.2    .035       0   964.7    .045       0
  1338.5    .035       0  1527.2    .045       0  4257.5    .035       0
  4426.1     .07       0  4875.5    .045       0  5009.5    .045       0
  5040.7    .045       0  5525.2    .035       0  5598.5    .045       0
  5697.9    .035       0  5762.3    .045       0  5942.8    .035       0
  6095.6     .07       0    6462    .035       0
Bank Sta=5009.5,5040.7
XS Rating Curve= 0 ,0
Exp/Cntr=0.3,0.1

Type RM Length L Ch R = 1 ,10627   ,550,550,550
BEGIN DESCRIPTION:
ALLIGATOR CREEK 105.0
END DESCRIPTION:
XS GIS Cut Line= 3
      2288274.99     13804324.99        2285175.       13801225.
      2282575.04     13801624.99
#Sta/Elev= 30
     621  626.04   873.1  623.91  1101.8  622.05  1144.2  623.87  1172.5  621.12
  1243.5  619.21    1314  615.84  1399.5  618.93  1626.6  617.74  2530.2  616.02
  3237.3  610.41  4616.1  603.33  4808.9  604.09  4830.4  604.14  4891.9  603.76
  4961.2  600.28  4961.7  599.78  4992.4  600.28  5151.1  602.84  5251.2  604.35
  5351.3  605.94  5612.1   613.2    5774  614.63  5841.4  617.75  5928.3  618.56
  6107.9  619.92    6377  618.71  6652.8  619.74  6919.5  622.04  7635.6  625.72
#Mann= 17 ,-1 , 0
     621    .045       0   873.1    .035       0  1243.5    .045       0
  1399.5     .07       0  1626.6    .045       0  4808.9    .035       0
  4830.4    .045       0  4961.2    .045       0  4992.4    .045       0
  5151.1    .035       0  5251.2     .07       0  5351.3    .045       0
  5841.4    .035       0  5928.3    .045       0    6377     .07       0
  6652.8    .035       0  6919.5     .07       0
Bank Sta=4961.2,4992.4
XS Rating Curve= 0 ,0
Exp/Cntr=0.3,0.1

Type RM Length L Ch R = 1 ,10077   ,552,552,552
BEGIN DESCRIPTION:
ALLIGATOR CREEK 104.0
END DESCRIPTION:
XS GIS Cut Line= 3
      2289424.97     13804774.97        2285425.       13800775.
      2282824.99       13801475.
#Sta/Elev= 30
    -652  636.49    72.8  629.05   154.1  626.68   210.6  628.53   436.9  627.33
   707.1  623.32  1798.5  614.79  1854.4  614.46  2010.1  613.95  2245.8  612.67
  2643.1  611.33  2685.5  613.49  2760.4  609.36  2946.3  607.84    3336  608.59
  4728.2  603.65  4891.7  602.56  4960.1  599.19  4960.7  598.69  4992.9  599.19
  5001.3  601.33  5056.6  603.02    5161  602.86  5401.9  604.58  5709.4  608.85
  5850.8  613.12  6122.5   618.1  7008.5  621.27  7061.3  621.81  7697.4     625
#Mann= 19 ,-1 , 0
    -652    .045       0    72.8    .035       0   707.1    .045       0
  1798.5     .07       0  1854.4    .045       0  2010.1     .07       0
  2245.8    .045       0  2760.4    .035       0  2946.3    .045       0
  4728.2    .035       0  4960.1    .035       0  4992.9    .035       0
    5161    .045       0  5401.9    .035       0  5709.4    .045       0
  5850.8    .035       0  6122.5    .045       0  7008.5    .035       0
  7061.3     .07       0
Bank Sta=4960.1,4992.9
XS Rating Curve= 0 ,0
Exp/Cntr=0.3,0.1

Type RM Length L Ch R = 1 ,9525    ,522,522,522
BEGIN DESCRIPTION:
ALLIGATOR CREEK 103.0
END DESCRIPTION:
XS GIS Cut Line= 3
      2289675.03     13804375.03        2285675.       13800375.
      2283074.98       13801075.
#Sta/Elev= 30
  -656.9  634.48  -523.4  634.45  -250.9  630.02   385.9  625.64   446.2  624.45
   488.7  625.64   516.9  623.73   545.2   626.3   573.5  623.94   619.3  623.89
  1888.7   614.2  3076.7  614.45  3868.6  606.14  4264.6   604.3  4292.9  605.88
    4333  603.22  4423.8  603.95  4971.7  601.27  4980.1  599.04  4980.6  598.54
  5012.9  599.04  5032.2  600.13  5057.3  602.71  5214.6  602.68  5645.7  604.94
  5854.1  608.52  5956.1  609.81  6239.2  614.35  6363.7  617.39  7692.6  624.06
#Mann= 15 ,-1 , 0
  -656.9    .045       0  -523.4    .035       0  -250.9    .045       0
   385.9    .035       0   619.3    .045       0    4333    .035       0
  4423.8    .045       0  4980.1    .045       0  5012.9    .045       0
  5032.2      .1       0  5214.6    .045       0  5645.7    .035       0
  5854.1    .045       0  5956.1    .035       0  6239.2    .045       0
Bank Sta=4980.1,5012.9
XS Rating Curve= 0 ,0
Exp/Cntr=0.3,0.1

Type RM Length L Ch R = 1 ,9003    ,1085,1085,1085
BEGIN DESCRIPTION:
ALLIGATOR CREEK 102.0
END DESCRIPTION:
XS GIS Cut Line= 3
      2289825.02     13803525.02        2285825.       13799925.
      2282624.99       13800925.
#Sta/Elev= 30
  -365.1  628.79   831.2   621.7   916.4  622.68   944.8  620.24   952.3   621.9
   973.2  622.22  1008.3  616.92    1043  619.36  1291.6  620.65  2651.2  618.74
  3090.6  615.42  3614.6  607.61  4640.8  600.66  4931.5  602.13  4938.3  602.04
  4943.5  599.45  4944.1  598.95  4976.3  599.45  4997.6  600.11  5065.1  603.44
    5124  602.25    5503  602.95    5815  605.56  5833.1  607.04  5844.1  606.07
  5870.8  609.02  5973.9  609.35  6541.3  616.83  7101.3  621.13    8369  623.77
#Mann= 9 ,-1 , 0
  -365.1    .045       0   831.2    .035       0    1043    .045       0
  4943.5     .05       0  4976.3    .045       0  4997.6      .1       0
    5124    .045       0    5815    .035       0  5973.9    .045       0
Bank Sta=4943.5,4976.3
XS Rating Curve= 0 ,0
Exp/Cntr=0.3,0.1

Type RM Length L Ch R = 1 ,7918    ,1077,1077,1077
BEGIN DESCRIPTION:
ALLIGATOR CREEK 101.0
END DESCRIPTION:
XS GIS Cut Line= 3
      2289324.97     13802774.96        2286525.       13799175.
      2282924.97     13799975.01
#Sta/Elev= 30
     440  623.51   448.8  623.41   602.7  622.96   603.4  622.98   857.9  623.11
  1195.5  622.31  1224.5  623.98  1316.3  622.21  3341.1  616.56  4224.2  603.62
  4637.7  600.52  4864.9  599.35  4972.6  600.69  4987.1  600.14  4994.4   597.3
    4995   596.8  5027.4   597.3  5031.4  599.44  5051.9  600.59  5123.6  599.64
  5294.4  600.75  5333.8  600.95  5481.1  600.57  5854.7  602.55  6190.7  606.91
  6478.3  608.36  6543.6  610.97  6645.7  611.29    7029  615.41  8688.5  620.17
#Mann= 15 ,-1 , 0
     440     .07       0   448.8    .045       0   602.7    .035       0
   603.4    .045       0   857.9    .035       0  1316.3    .045       0
  4637.7     .05       0  4994.4     .05       0  5027.4     .05       0
  5294.4    .045       0  5333.8     .05       0  5481.1    .045       0
  6190.7     .07       0  6478.3    .035       0  6645.7    .045       0
Bank Sta=4994.4,5027.4
XS Rating Curve= 0 ,0
Exp/Cntr=0.3,0.1

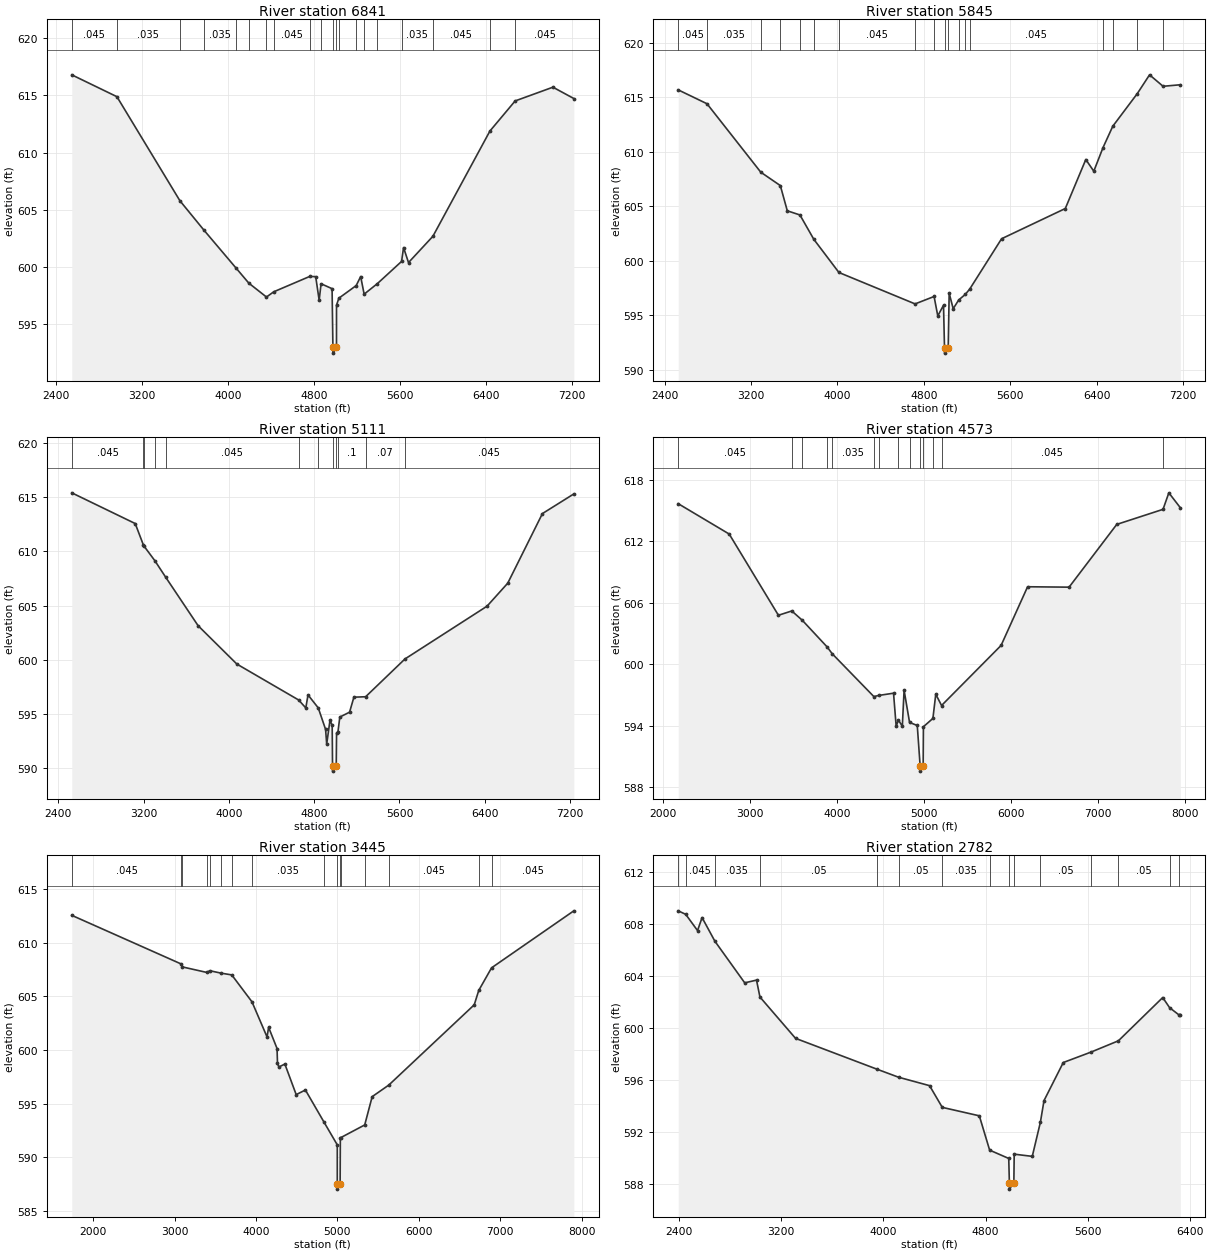
Type RM Length L Ch R = 1 ,6841    ,996,996,996
BEGIN DESCRIPTION:
ALLIGATOR CREEK 100.0
END DESCRIPTION:
XS GIS Cut Line= 3
      2288123.01     13799824.78      2287198.54     13798431.56
      2284412.05      13797337.8
#Sta/Elev= 30
  2550.4   616.8  2969.9  614.89  3555.3   605.8  3776.2  603.26  4079.7  599.89
    4196   598.6  4359.6  597.39  4427.8  597.85  4761.8  599.19  4817.1  599.17
  4849.3  597.11    4867  598.55  4969.3  598.12  4977.1  592.99  4977.7  592.49
  5010.3  592.99  5010.5  596.68  5032.4  597.29  5193.3  598.39    5235  599.18
  5267.3  597.64    5390  598.56    5615   600.5  5633.5  601.71  5679.6   600.4
  5906.4   602.7    6436  611.89  6670.5  614.52  7021.5  615.72  7215.9  614.73
#Mann= 20 ,-1 , 0
  2550.4    .045       0  2969.9    .035       0  3555.3     .07       0
  3776.2    .035       0  4079.7    .035       0    4196    .045       0
  4359.6    .035       0  4427.8    .045       0  4761.8    .035       0
    4867    .045       0  4977.1    .045       0  5010.3    .045       0
  5032.4    .035       0  5193.3    .045       0  5267.3    .035       0
    5390    .045       0    5615    .035       0  5906.4    .045       0
    6436    .035       0  6670.5    .045       0
Bank Sta=4977.1,5010.3
XS Rating Curve= 0 ,0
Exp/Cntr=0.3,0.1

Type RM Length L Ch R = 1 ,5845    ,734,734,734
BEGIN DESCRIPTION:
ALLIGATOR CREEK 99.0
END DESCRIPTION:
XS GIS Cut Line= 3
      2288005.81     13799564.33      2286925.11     13797441.98
      2284774.96     13796724.99
#Sta/Elev= 30
  2525.9  615.67  2792.2   614.4  3289.9  608.13  3471.2   606.9  3535.6  604.59
  3652.6  604.21    3781  601.98  4013.4  598.94  4718.7  596.06  4894.6  596.74
  4928.8  594.96  4981.9  595.94    4991  592.05  4991.7  591.55  5025.4  592.05
  5034.2  597.04  5071.5  595.62  5122.4  596.42  5183.3  596.93  5225.2  597.43
  5519.4  602.03  6109.4   604.8  6299.1  609.29  6373.1  608.22  6458.9  610.39
  6548.9  612.34  6775.9  615.33  6889.4  617.05  7014.5     616  7174.1  616.14
#Mann= 18 ,-1 , 0
  2525.9    .045       0  2792.2    .035       0  3289.9     .07       0
  3471.2    .035       0  3652.6    .045       0    3781    .035       0
  4013.4    .045       0  4718.7     .05       0  4894.6      .1       0
    4991     .05       0  5025.4      .1       0  5122.4     .07       0
  5183.3    .035       0  5225.2    .045       0  6458.9    .035       0
  6548.9    .045       0  6775.9    .035       0  7014.5    .045       0
Bank Sta=4991,5025.4
XS Rating Curve= 0 ,0
Exp/Cntr=0.3,0.1

Type RM Length L Ch R = 1 ,5111    ,538,538,538
BEGIN DESCRIPTION:
ALLIGATOR CREEK 98.0
END DESCRIPTION:
XS GIS Cut Line= 3
        2288025.     13799424.98        2287425.       13797025.
      2285225.01       13796625.
#Sta/Elev= 30
  2526.2  615.38  3121.5  612.55  3197.1   610.6  3203.4  610.48  3305.6  609.13
  3407.8   607.6  3711.6  603.14  4074.9  599.61  4654.7   596.3  4721.7  595.57
  4742.4  596.77  4838.6  595.57  4907.3  593.59  4917.6  592.24  4948.5  594.43
  4969.1  593.96  4972.4  590.25  4973.1  589.75  5007.1  590.25  5010.2  593.26
  5023.3  593.37  5040.7  594.73  5132.2  595.18  5172.8  596.56  5282.7   596.6
  5651.9  600.08  6421.7  604.94  6616.1  607.06  6941.4  613.47  7236.1  615.28
#Mann= 12 ,-1 , 0
  2526.2    .045       0  3197.1    .035       0  3203.4    .045       0
  3305.6    .035       0  3407.8    .045       0  4654.7    .035       0
  4838.6     .05       0  4972.4     .05       0  5007.1     .05       0
  5023.3      .1       0  5282.7     .07       0  5651.9    .045       0
Bank Sta=4972.4,5007.1
XS Rating Curve= 0 ,0
Exp/Cntr=0.3,0.1

Type RM Length L Ch R = 1 ,4573    ,1128,1128,1128
BEGIN DESCRIPTION:
ALLIGATOR CREEK 97.0
END DESCRIPTION:
XS GIS Cut Line= 3
        2288225.     13799474.97        2287825.       13796675.
      2284924.99       13796175.
#Sta/Elev= 30
  2175.7  615.67  2761.6  612.71  3327.2  604.79    3481  605.21  3601.9   604.3
  3886.2  601.71  3946.4  601.03  4424.3  596.86  4479.4  596.97  4650.5  597.19
  4680.9  593.95  4705.7  594.58  4751.6  593.97  4771.8  597.48  4834.7  594.34
  4923.3  594.04  4956.4  590.09  4957.2  589.59  4991.1  590.09    4994  593.92
    5103  594.73    5136  597.09  5202.5  595.99  5886.9  601.85  6191.4  607.57
  6668.3  607.53  7216.3  613.65  7748.3  615.12    7815  616.73  7946.9  615.28
#Mann= 14 ,-1 , 0
  2175.7    .045       0    3481     .07       0  3601.9    .035       0
  3886.2     .07       0  3946.4    .035       0  4424.3    .045       0
  4479.4     .05       0  4705.7     .07       0  4834.7     .05       0
  4956.4     .05       0  4991.1     .05       0    5103     .07       0
  5202.5    .045       0  7748.3    .035       0
Bank Sta=4956.4,4991.1
XS Rating Curve= 0 ,0
Exp/Cntr=0.3,0.1

Type RM Length L Ch R = 1 ,3445    ,663,663,663
BEGIN DESCRIPTION:
ALLIGATOR CREEK 96.0
END DESCRIPTION:
XS GIS Cut Line= 3
      2289674.99     13799174.98        2288675.       13796075.
      2285774.97       13795875.
#Sta/Elev= 30
  1738.3  612.56  3081.5  608.02    3094  607.75  3396.6  607.23    3433  607.39
  3574.8  607.16  3702.5     607  3950.7  604.49  4135.8  601.21    4155  602.11
  4258.7  600.13    4264  598.74  4281.1  598.41  4354.6  598.68  4493.6  595.83
  4606.8  596.26  4832.3   593.3  4998.1  591.14  4998.2  587.51    4999  587.01
    5033  587.51  5035.7  591.74  5039.4  591.81  5334.9     593  5426.6  595.64
  5630.5  596.72  6679.6  604.21  6734.8  605.55  6892.2  607.66  7902.5  612.98
#Mann= 16 ,-1 , 0
  1738.3    .045       0  3081.5    .035       0    3094    .045       0
  3396.6     .07       0    3433    .045       0  3574.8    .035       0
  3702.5     .05       0  3950.7    .035       0  4832.3     .07       0
  4998.2     .05       0    5033     .07       0  5039.4      .1       0
  5334.9     .12       0  5630.5    .045       0  6734.8     .07       0
  6892.2    .045       0
Bank Sta=4998.2,5033
XS Rating Curve= 0 ,0
Exp/Cntr=0.3,0.1

Type RM Length L Ch R = 1 ,2782    ,1007,1007,1007
BEGIN DESCRIPTION:
X18002
END DESCRIPTION:
XS GIS Cut Line= 3
      2290505.84     13797207.61      2289099.58     13795540.94
      2287368.92     13795280.69
#Sta/Elev= 30
  2393.9  609.05  2452.4  608.78  2545.1  607.53  2580.5  608.53    2681  606.71
  2914.4  603.51  3006.7  603.72  3033.6  602.42  3312.3  599.24  3951.7  596.86
  4118.5  596.25  4361.6   595.6  4461.1  593.93  4751.1  593.28  4831.9  590.64
  4981.5     590  4986.4  588.14  4987.1  587.64  5021.5  588.14  5024.2  590.33
  5165.7  590.16  5229.1  592.78  5257.6  594.45  5408.4  597.38  5625.1  598.18
  5839.9  599.05  6187.1  602.38  6240.8   601.6  6310.6  601.07  6324.7  601.07
#Mann= 15 ,-1 , 0
  2393.9    .035       0  2452.4    .045       0    2681    .035       0
  3033.6     .05       0  3951.7    .035       0  4118.5     .05       0
  4461.1    .035       0  4831.9     .07       0  4986.4     .05       0
  5021.5     .07       0  5229.1     .05       0  5625.1    .035       0
  5839.9     .05       0  6240.8    .035       0  6310.6     .05       0
Bank Sta=4986.4,5021.5
XS Rating Curve= 0 ,0
Exp/Cntr=0.3,0.1