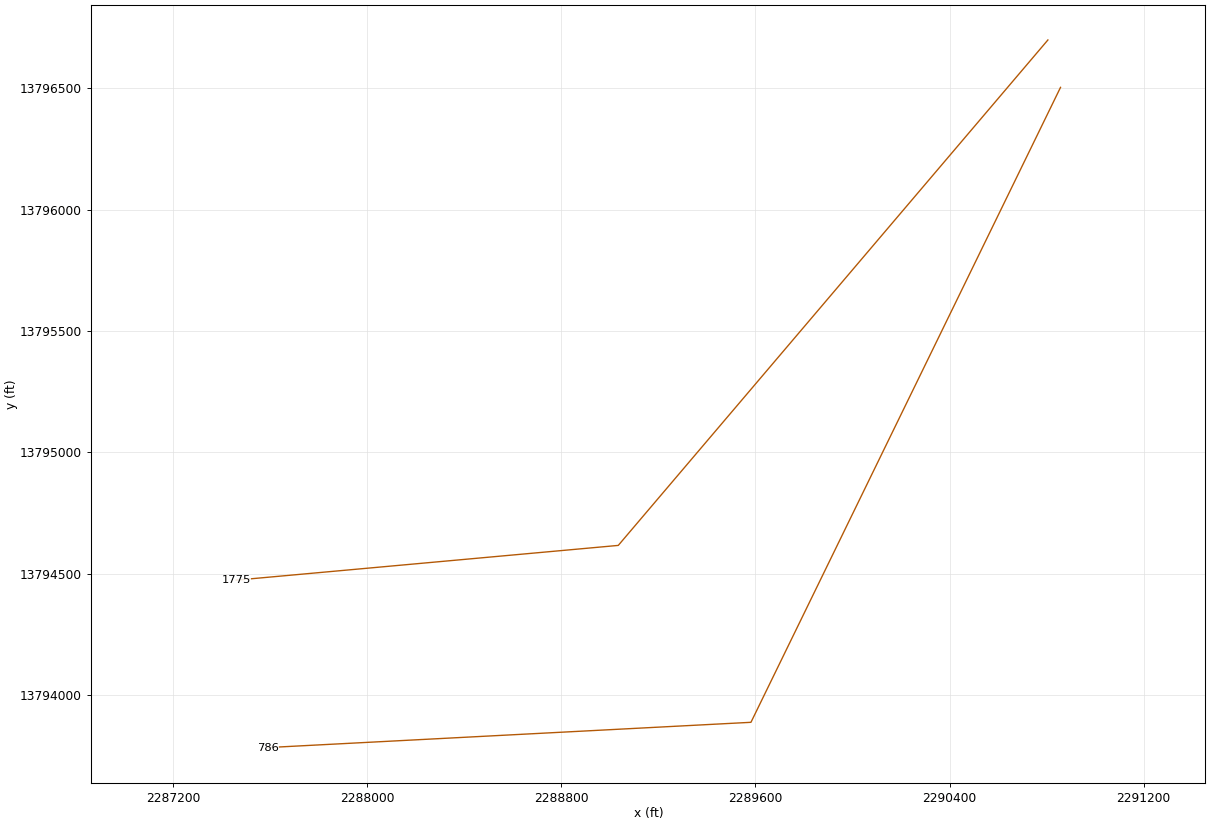
HEC-RAS study ALLIGATOR CREEK.prj: ALLIGATOR CREEK Base Level Engineering

--- ALLIGATOR CREEK.g01 (geometry) --- (continued)

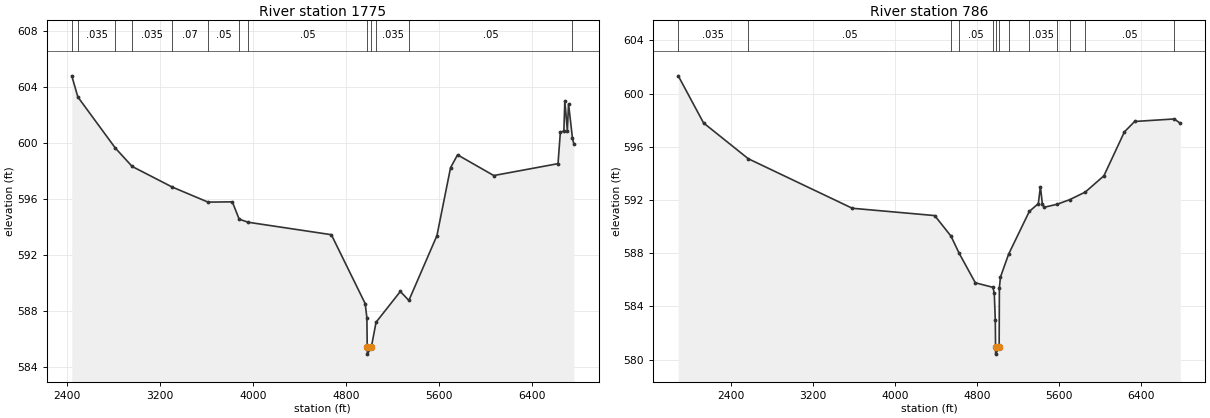
Type RM Length L Ch R = 1 ,1775    ,989,989,989
BEGIN DESCRIPTION:
X18001
END DESCRIPTION:
XS GIS Cut Line= 3
      2290805.31     13796699.78      2289034.48     13794616.46
      2287459.52     13794473.28
#Sta/Elev= 30
  2442.8  604.81    2495   603.3  2816.8  599.65  2961.8  598.33  3305.5  596.86
  3614.1  595.78  3822.9   595.8  3881.6  594.56  3959.2  594.34    4674  593.45
  4965.1  588.52  4979.4  587.51  4982.6  585.41  4983.4  584.91  5017.8  585.41
  5058.4  587.19  5266.9  589.39  5340.4  588.75  5581.5  593.38  5698.7  598.24
  5758.9  599.16  6070.2  597.68  6622.5  598.53  6642.5  600.78  6672.7  600.86
    6681  603.03  6702.8   600.9  6712.8  602.81  6746.4  600.37  6758.5  599.93
#Mann= 13 ,-1 , 0
  2442.8     .07       0    2495    .035       0  2816.8     .07       0
  2961.8    .035       0  3305.5     .07       0  3614.1     .05       0
  3881.6    .035       0  3959.2     .05       0  4982.6     .05       0
  5017.8     .05       0  5058.4    .035       0  5340.4     .05       0
  6746.4    .035       0
Bank Sta=4982.6,5017.8
XS Rating Curve= 0 ,0
Exp/Cntr=0.3,0.1

Type RM Length L Ch R = 1 ,786     ,0,0,0
BEGIN DESCRIPTION:
ALLIGATOR CREEK 95.0
END DESCRIPTION:
XS GIS Cut Line= 3
      2290857.38     13796504.45      2289581.36     13793887.29
      2287589.54     13793783.14
#Sta/Elev= 30
  1881.6  601.33    2129  597.79  2566.3   595.1  3582.3  591.38  4387.7  590.83
  4546.7  589.29  4627.2  587.99  4784.7  585.78  4956.6  585.44  4969.9     585
  4979.9  582.97  4982.3  580.92    4983  580.42  5017.5  580.92  5019.9   585.4
  5029.9   586.2    5110  587.93    5312  591.14  5400.4  591.73  5420.5     593
  5440.5  591.67  5460.5  591.46  5584.6  591.68  5708.2  592.03  5859.9   592.6
  6041.3  593.82  6241.6  597.12  6341.7   597.9  6729.5  598.09  6787.8  597.76
#Mann= 13 ,-1 , 0
  1881.6    .035       0  2566.3     .05       0  4546.7    .035       0
  4627.2     .05       0  4956.6    .035       0  4982.3    .035       0
  5017.5    .035       0    5110     .05       0    5312    .035       0
  5584.6     .05       0  5708.2    .035       0  5859.9     .05       0
  6729.5    .045       0
Bank Sta=4982.3,5017.5
XS Rating Curve= 0 ,0
Exp/Cntr=0.3,0.1

Chan Stop Cuts=-1
Use User Specified Reach Order=0
Composite Channel Slope=5