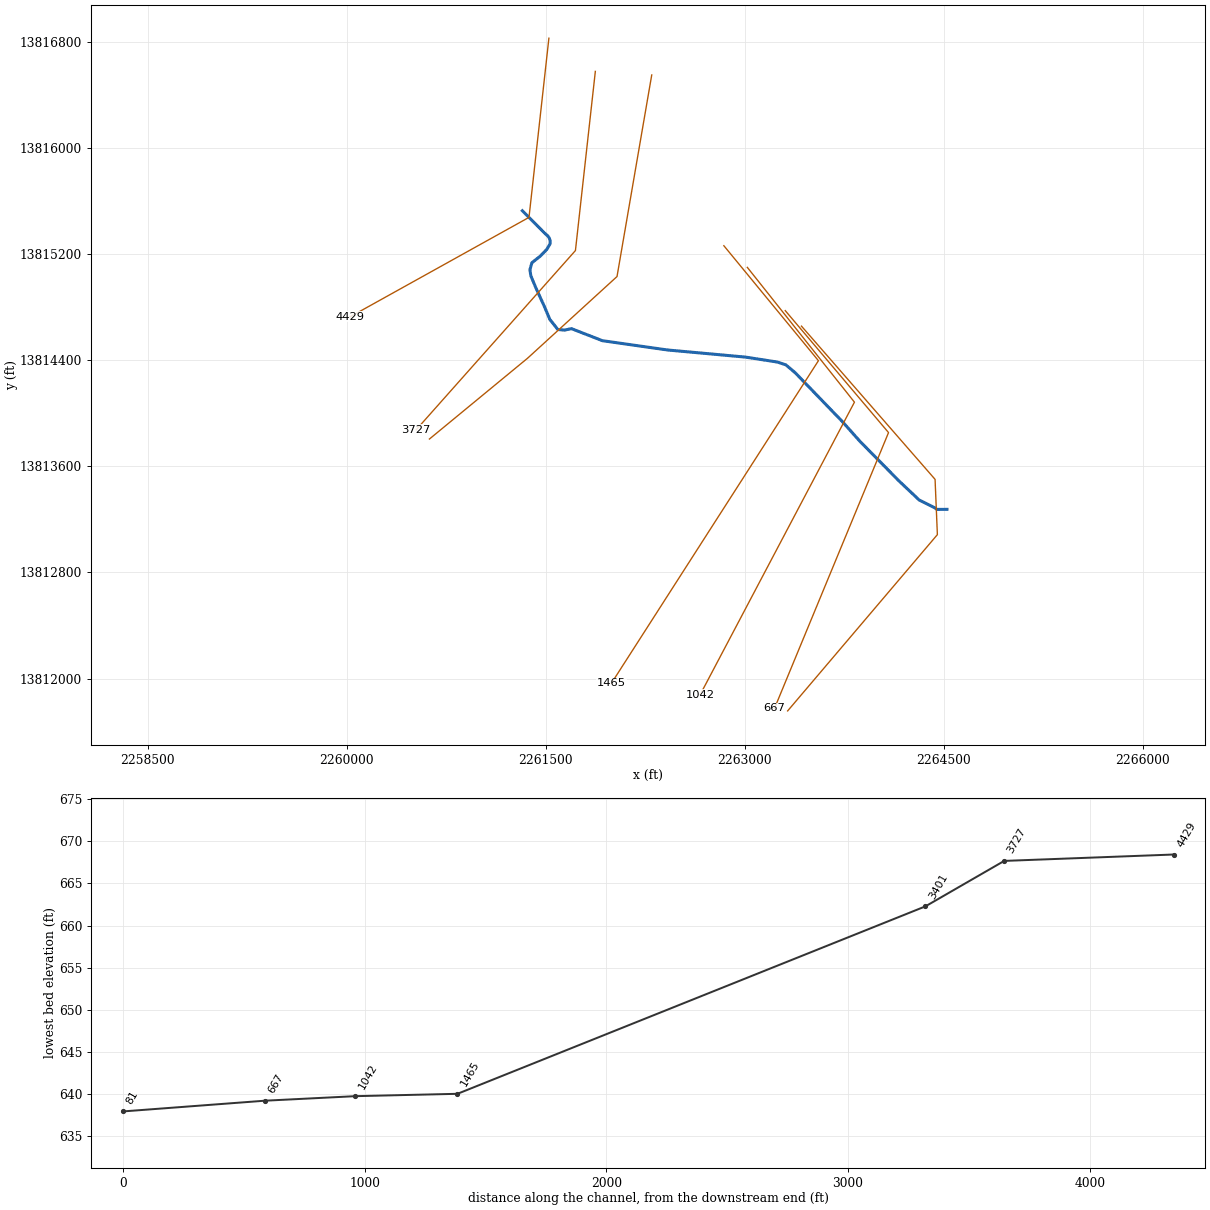
--- Alligator Creek Tributary 3.prj (project) ---

Proj Title=Alligator Creek Tributary 3 Base Level Engineering
Current Plan=p01
Default Exp/Contr=0.3,0.1
English Units
Geom File=g01
Flow File=f01
Plan File=p01
BEGIN DESCRIPTION:
Alligator Creek Tributary 3
END DESCRIPTION:

--- Alligator Creek Tributary 3.p01 (plan) ---

Plan Title=Multiple Run
Short Identifier=Multiple
Geom File=g01
Flow File=f01
Subcritical Flow
K Sum by GR= 0
Std Step Tol= 0.01
Critical Tol= 0.01
Num of Std Step Trials= 20
Max Error Tol= 0.3
Flow Tol Ratio= 0.001
Split Flow NTrial= 30
Split Flow Tol= 0.02
Split Flow Ratio= 0.02
Log Output Level= 0
Friction Slope Method= 1
Unsteady Friction Slope Method= 2
Unsteady Bridges Friction Slope Method= 1
Parabolic Critical Depth
Global Vel Dist=  1 , 1 , 1
Global Log Level= 0
CheckData=True
Encroach Param= -1, 0, 0, 0
BEGIN DESCRIPTION:
Multiple Run
END DESCRIPTION:

--- Alligator Creek Tributary 3.f01 (steady flow) ---

Flow Title=Multiple
Number of Profiles=7
Profile Names=10-year,25-year,50-year,1pct_min,100-year,1pct_plu,500-year
River Rch & RM= Alligator Creek ,Reach-1,4429
     455     706     922     583    1163    2321    1830
River Rch & RM= Alligator Creek ,Reach-1,3727
     630     996    1318     843    1681    3354    2708
Boundary for River Rch & Prof#=Alligator Creek ,Reach-1,1
Up Type=0
Dn Type=3
Dn Slope=0.005
Boundary for River Rch & Prof#=Alligator Creek ,Reach-1,2
Up Type=0
Dn Type=3
Dn Slope=0.005
Boundary for River Rch & Prof#=Alligator Creek ,Reach-1,3
Up Type=0
Dn Type=3
Dn Slope=0.005
Boundary for River Rch & Prof#=Alligator Creek ,Reach-1,4
Up Type=0
Dn Type=3
Dn Slope=0.005
Boundary for River Rch & Prof#=Alligator Creek ,Reach-1,5
Up Type=0
Dn Type=3
Dn Slope=0.005
Boundary for River Rch & Prof#=Alligator Creek ,Reach-1,6
Up Type=0
Dn Type=3
Dn Slope=0.005
Boundary for River Rch & Prof#=Alligator Creek ,Reach-1,7
Up Type=0
Dn Type=3
Dn Slope=0.005

--- Alligator Creek Tributary 3.g01 (geometry) ---

Geom Title=Existing Conditions

River Reach=Alligator Creek ,Reach-1
Reach XY= 30
      2261325.00     13815525.00      2261498.33     13815350.77
      2261515.84     13815335.75      2261528.48     13815318.37
      2261534.99     13815297.23      2261533.36     13815274.46
      2261508.97     13815233.80      2261460.17     13815183.38
      2261396.74     13815132.96      2261382.10     13815080.91
      2261388.61     13815035.37      2261426.02     13814945.91
      2261492.70     13814799.53      2261531.74     13814706.83
      2261591.92     13814630.38      2261642.34     13814625.50
      2261694.38     13814636.89      2261928.59     13814545.81
      2262419.78     13814475.87      2263006.93     13814422.20
      2263247.64     13814384.79      2263311.08     13814363.64
      2263381.53     13814304.21      2263732.71     13813940.64
      2263869.05     13813787.77      2264162.39     13813490.31
      2264315.25     13813345.70      2264430.93     13813287.86
      2264449.82     13813274.53      2264525.00     13813275.00

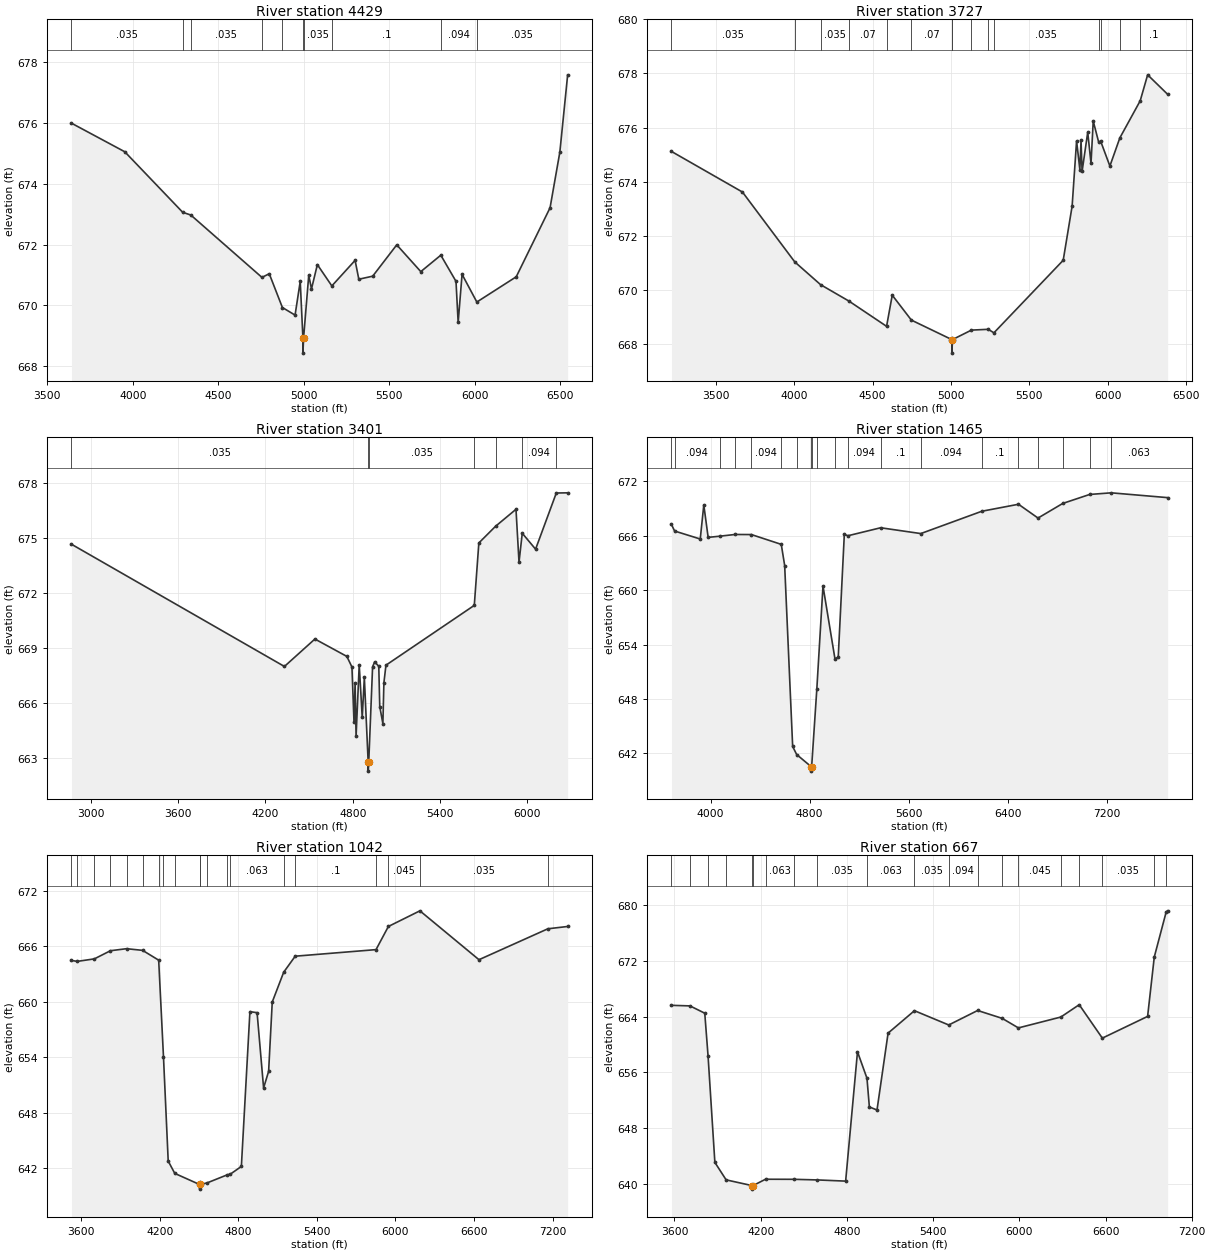
Type RM Length L Ch R = 1,4429,702,702,702
BEGIN DESCRIPTION:
Alligator Creek Tributary 3 4.0
END DESCRIPTION:
XS GIS Cut Line= 3
      2261525.00     13816824.97      2261375.00     13815475.00
      2260025.02     13814725.01
#Sta/Elev= 30
  3641.7  675.99  3953.6  675.05  4292.4  673.06  4339.9  672.97  4755.9  670.92
  4798.7  671.04  4875.5  669.93  4949.7  669.68  4979.9  670.79  4995.5  668.93
  4995.7  668.43  4999.5  668.93  5029.7  670.99  5045.7  670.54  5080.1  671.34
  5164.8  670.64  5300.8  671.48  5322.6  670.86  5403.8  670.96  5544.5  671.99
  5685.2  671.11  5802.3  671.65  5891.1  670.79  5903.7  669.44  5926.6  671.02
  6013.0  670.11  6243.5  670.94  6441.4  673.21  6498.6  675.04  6544.3  677.58
#Mann=10,-1,0
  3641.7   0.035       0  4292.4    0.07       0  4339.9   0.035       0
  4755.9    0.07       0  4875.5   0.035       0  4995.5   0.035       0
  4999.5   0.035       0  5164.8     0.1       0  5802.3   0.094       0
  6013.0   0.035       0
Bank Sta=4995.5,4999.5
Exp/Cntr=0.3,0.1

Type RM Length L Ch R = 1,3727,326,326,326
BEGIN DESCRIPTION:
Alligator Creek Tributary 3 3.0
END DESCRIPTION:
XS GIS Cut Line= 3
      2261875.00     13816575.03      2261725.00     13815225.00
      2260524.98     13813874.98
#Sta/Elev= 30
  3217.6  675.12  3670.4  673.62  4003.9  671.04  4168.4  670.20  4350.2  669.59
  4589.6  668.66  4625.7  669.81  4747.7  668.89  5005.8  668.17  5006.1  667.67
  5009.8  668.17  5130.6  668.52  5238.2  668.55  5274.1  668.42  5716.1  671.10
  5773.0  673.10  5801.4  675.51  5822.3  674.45  5829.8  675.53  5836.5  674.38
  5872.5  675.83  5893.4  674.68  5907.6  676.24  5942.0  675.47  5955.5  675.49
  6013.8  674.58  6077.3  675.62  6207.1  676.99  6254.6  677.95  6382.2  677.23
#Mann=15,-1,0
  3217.6   0.035       0  4003.9    0.07       0  4168.4   0.035       0
  4350.2    0.07       0  4589.6   0.035       0  4747.7    0.07       0
  5005.8    0.05       0  5009.8    0.07       0  5130.6   0.035       0
  5238.2    0.07       0  5274.1   0.035       0  5942.0   0.094       0
  5955.5   0.035       0  6077.3   0.094       0  6207.1     0.1       0
Bank Sta=5005.8,5009.8
Exp/Cntr=0.3,0.1

Type RM Length L Ch R = 1,3401,1936,1936,1936
BEGIN DESCRIPTION:
X18035
END DESCRIPTION:
XS GIS Cut Line= 4
      2262300.01     13816548.05      2262038.38     13815029.32
      2261363.81     13814413.41      2260624.67     13813804.98
#Sta/Elev= 30
  2866.0  674.68  4330.3  668.00  4539.9  669.50  4759.5  668.55  4794.6  667.97
  4808.8  664.95  4816.3  667.11  4823.0  664.18  4844.6  668.09  4865.3  665.22
  4879.8  667.40  4906.1  662.78  4906.4  662.28  4910.1  662.78  4936.5  667.98
  4950.7  668.25  4979.1  668.01  4985.8  665.81  5007.4  664.87  5014.2  667.10
  5028.4  668.07  5635.9  671.34  5667.2  674.75  5781.8  675.66  5922.6  676.59
  5943.4  673.70  5965.7  675.28  6057.3  674.41  6199.8  677.48  6277.9  677.49
#Mann=7,-1,0
  2866.0   0.035       0  4906.1   0.035       0  4910.1   0.035       0
  5635.9   0.094       0  5781.8     0.1       0  5965.7   0.094       0
  6199.8     0.1       0
Bank Sta=4906.1,4910.1
Exp/Cntr=0.3,0.1

Type RM Length L Ch R = 1,1465,423,423,423
BEGIN DESCRIPTION:
X18031
END DESCRIPTION:
XS GIS Cut Line= 3
      2262843.68     13815261.46      2263556.40     13814395.24
      2261996.17     13811964.66
#Sta/Elev= 30
  3683.8  667.23  3709.3  666.51  3916.4  665.63  3945.1  669.38  3980.3  665.81
  4073.6  665.94  4198.0  666.13  4329.9  666.12  4571.2  665.04  4598.7  662.71
  4663.3  642.77  4695.6  641.88  4812.3  640.55  4812.6  640.05  4816.8  640.55
  4858.4  649.06  4908.4  660.45  5005.1  652.43  5031.6  652.61  5080.8  666.14
  5110.0  665.99  5374.4  666.87  5698.9  666.23  6192.2  668.69  6488.4  669.46
  6646.2  667.94  6846.0  669.55  7063.5  670.54  7237.8  670.72  7693.8  670.19
#Mann=20,-1,0
  3683.8   0.094       0  3709.3   0.094       0  4073.6   0.094       0
  4198.0   0.063       0  4329.9   0.094       0  4571.2   0.035       0
  4695.6   0.063       0  4812.3    0.05       0  4816.8   0.063       0
  4858.4   0.094       0  5005.1   0.063       0  5110.0   0.094       0
  5374.4     0.1       0  5698.9   0.094       0  6192.2     0.1       0
  6488.4   0.035       0  6646.2   0.063       0  6846.0   0.094       0
  7063.5   0.063       0  7237.8   0.063       0
Bank Sta=4812.3,4816.8
Exp/Cntr=0.3,0.1

Type RM Length L Ch R = 1,1042,375,375,375
BEGIN DESCRIPTION:
X18030
END DESCRIPTION:
XS GIS Cut Line= 3
      2263020.46     13815098.39      2263827.78     13814082.74
      2262665.15     13811878.94
#Sta/Elev= 30
  3525.9  664.47  3570.5  664.37  3700.7  664.64  3823.5  665.52  3946.3  665.74
  4069.1  665.56  4191.9  664.50  4228.4  654.09  4264.6  642.80  4314.7  641.47
  4504.2  640.27  4504.5  639.77  4508.7  640.27  4561.1  640.44  4716.5  641.32
  4739.2  641.39  4823.3  642.22  4888.6  658.94  4943.3  658.83  4993.0  650.70
  5031.4  652.49  5059.1  659.98  5146.5  663.20  5234.4  664.93  5851.6  665.64
  5945.9  668.14  6186.7  669.83  6637.8  664.55  7163.8  667.89  7315.0  668.14
#Mann=20,-1,0
  3525.9   0.094       0  3570.5   0.063       0  3700.7   0.094       0
  3823.5   0.063       0  3946.3   0.094       0  4069.1   0.094       0
  4191.9   0.035       0  4228.4    0.05       0  4314.7   0.063       0
  4504.2    0.05       0  4508.7   0.063       0  4561.1   0.063       0
  4716.5   0.094       0  4739.2   0.063       0  5146.5   0.094       0
  5234.4     0.1       0  5851.6   0.094       0  5945.9   0.045       0
  6186.7   0.035       0  7163.8    0.07       0
Bank Sta=4504.2,4508.7
Exp/Cntr=0.3,0.1

Type RM Length L Ch R = 1,667,586,586,586
BEGIN DESCRIPTION:
Alligator Creek Tributary 3 1.0
END DESCRIPTION:
XS GIS Cut Line= 3
      2263306.40     13814772.43      2264084.72     13813853.57
      2263225.02     13811775.04
#Sta/Elev= 30
  3578.9  665.62  3707.8  665.54  3810.7  664.49  3833.6  658.36  3881.0  643.07
  3959.4  640.56  4141.2  639.73  4141.6  639.23  4145.8  639.73  4233.5  640.65
  4430.8  640.64  4594.8  640.55  4791.2  640.38  4873.7  658.95  4939.7  655.15
  4956.3  651.03  5009.5  650.59  5086.6  661.63  5270.1  664.85  5508.8  662.80
  5709.9  664.88  5880.7  663.75  5993.6  662.38  6289.0  663.94  6416.9  665.71
  6577.8  660.91  6892.9  664.03  6939.4  672.56  7022.2  679.03  7032.4  679.19
#Mann=20,-1,0
  3578.9   0.063       0  3707.8   0.094       0  3833.6    0.05       0
  3959.4   0.063       0  4141.2    0.05       0  4145.8    0.05       0
  4233.5   0.063       0  4430.8    0.05       0  4594.8   0.035       0
  4939.7   0.063       0  5270.1   0.035       0  5508.8   0.094       0
  5709.9   0.094       0  5880.7   0.035       0  5993.6   0.045       0
  6289.0   0.035       0  6416.9   0.045       0  6577.8   0.035       0
  6939.4    0.07       0  7022.2   0.035       0
Bank Sta=4141.2,4145.8
Exp/Cntr=0.3,0.1

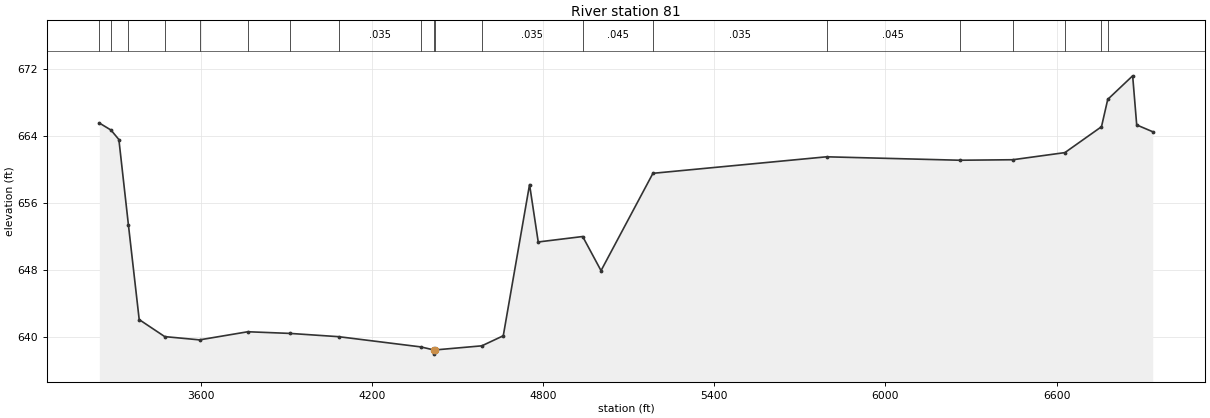
Type RM Length L Ch R = 1,81,0,0,0
BEGIN DESCRIPTION:
X18029
END DESCRIPTION:
XS GIS Cut Line= 4
      2263428.49     13814655.63      2264435.42     13813501.14
      2264452.78     13813084.47      2263324.33     13811756.38
#Sta/Elev= 30
  3244.9  665.53  3285.7  664.69  3313.4  663.56  3346.8  653.38  3384.6  642.08
  3474.1  640.05  3596.0  639.66  3765.3  640.63  3913.6  640.43  4083.9  640.04
  4371.8  638.82  4417.0  638.46  4417.3  637.96  4421.6  638.46  4585.4  638.95
  4660.5  640.15  4752.6  658.19  4783.0  651.34  4938.8  651.99  5003.1  647.92
  5185.0  659.53  5793.4  661.50  6260.3  661.09  6446.0  661.15  6628.7  662.00
  6757.0  665.09  6778.9  668.35  6866.2  671.16  6880.4  665.30  6936.6  664.49
#Mann=20,-1,0
  3244.9   0.094       0  3285.7   0.035       0  3346.8    0.05       0
  3474.1   0.063       0  3596.0    0.05       0  3765.3   0.063       0
  3913.6    0.05       0  4083.9   0.035       0  4371.8    0.05       0
  4417.0   0.045       0  4421.6    0.05       0  4585.4   0.035       0
  4938.8   0.045       0  5185.0   0.035       0  5793.4   0.045       0
  6260.3   0.035       0  6446.0   0.045       0  6628.7   0.035       0
  6757.0   0.045       0  6778.9   0.035       0
Bank Sta=4417,4421.6
Exp/Cntr=0.3,0.1

Chan Stop Cuts=-1