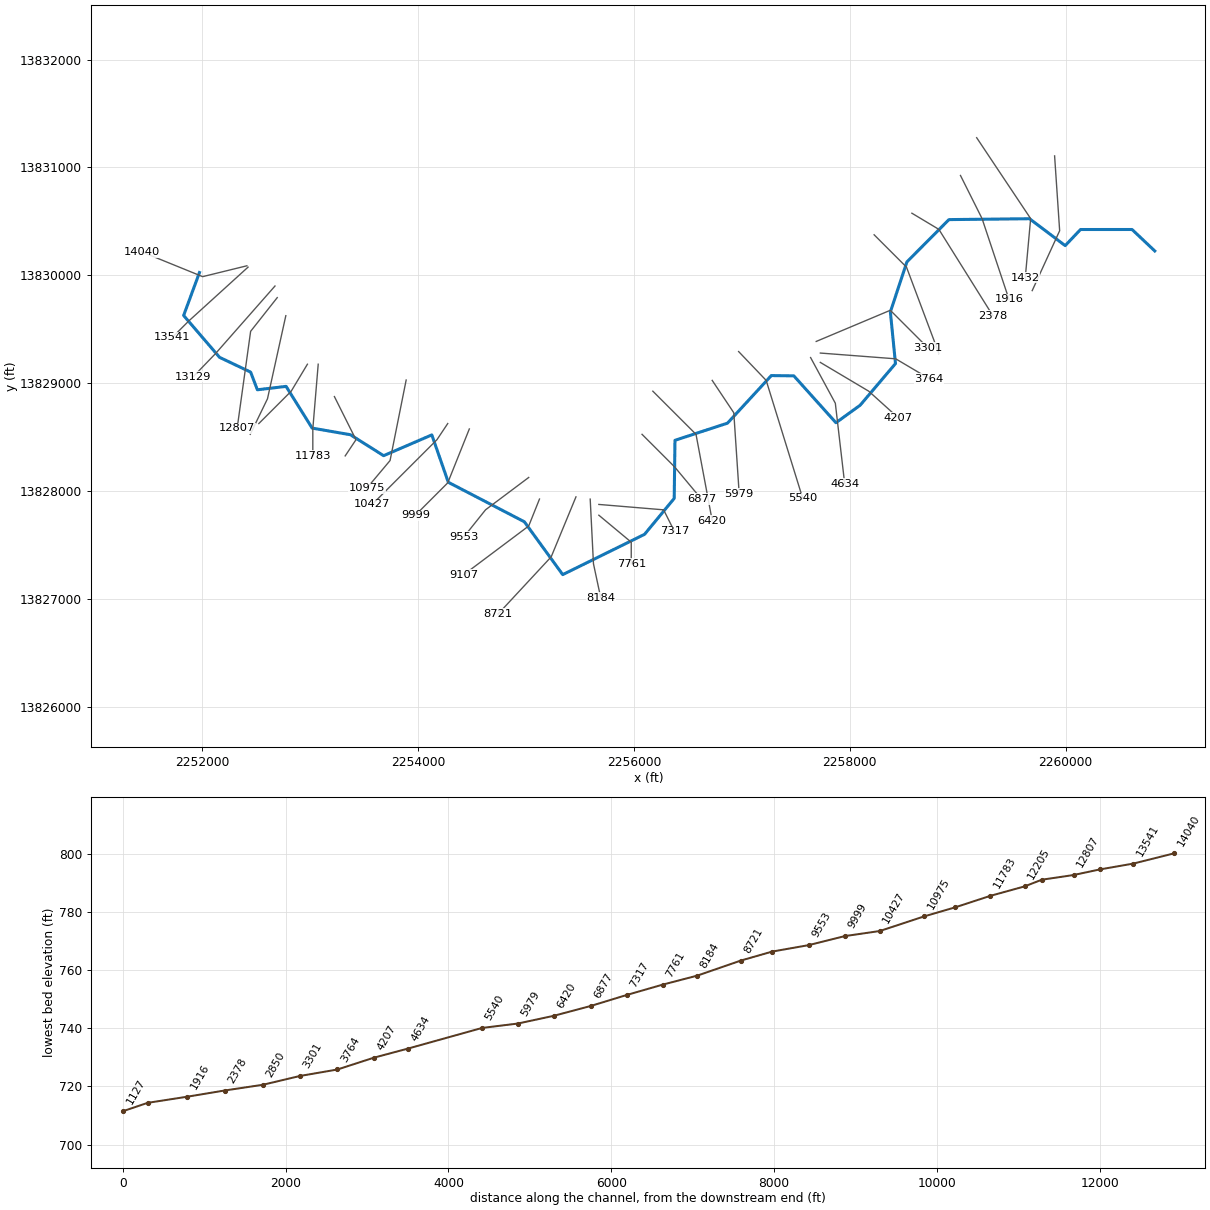
--- Alligator Creek Tributary 6.prj (project) ---

Proj Title=Alligator Creek Tributary 6 Base Level Engineering
Current Plan=p01
Default Exp/Contr=0.3,0.1
English Units
Geom File=g01
Flow File=f01
Plan File=p01
BEGIN DESCRIPTION:
Alligator Creek Tributary 6
END DESCRIPTION:

--- Alligator Creek Tributary 6.p01 (plan) ---

Plan Title=Multiple Run
Short Identifier=Multiple
Geom File=g01
Flow File=f01
Subcritical Flow
K Sum by GR= 0
Std Step Tol= 0.01
Critical Tol= 0.01
Num of Std Step Trials= 20
Max Error Tol= 0.3
Flow Tol Ratio= 0.001
Split Flow NTrial= 30
Split Flow Tol= 0.02
Split Flow Ratio= 0.02
Log Output Level= 0
Friction Slope Method= 1
Unsteady Friction Slope Method= 2
Unsteady Bridges Friction Slope Method= 1
Parabolic Critical Depth
Global Vel Dist=  1 , 1 , 1
Global Log Level= 0
CheckData=True
Encroach Param= -1, 0, 0, 0
BEGIN DESCRIPTION:
Multiple Run
END DESCRIPTION:

--- Alligator Creek Tributary 6.f01 (steady flow) ---

Flow Title=Multiple
Number of Profiles=7
Profile Names=10-year,25-year,50-year,1pct_min,100-year,1pct_plu,500-year
River Rch & RM= Alligator Creek ,Reach-1,14040
     651    1058    1428     936    1868    3727    3154
River Rch & RM= Alligator Creek ,Reach-1,11783
     901    1486    2027    1338    2670    5327    4582
River Rch & RM= Alligator Creek ,Reach-1,2850
    1331    2241    3098    2069    4129    8238    7261
Boundary for River Rch & Prof#=Alligator Creek ,Reach-1,1
Up Type=0
Dn Type=3
Dn Slope=0.005
Boundary for River Rch & Prof#=Alligator Creek ,Reach-1,2
Up Type=0
Dn Type=3
Dn Slope=0.005
Boundary for River Rch & Prof#=Alligator Creek ,Reach-1,3
Up Type=0
Dn Type=3
Dn Slope=0.005
Boundary for River Rch & Prof#=Alligator Creek ,Reach-1,4
Up Type=0
Dn Type=3
Dn Slope=0.005
Boundary for River Rch & Prof#=Alligator Creek ,Reach-1,5
Up Type=0
Dn Type=3
Dn Slope=0.005
Boundary for River Rch & Prof#=Alligator Creek ,Reach-1,6
Up Type=0
Dn Type=3
Dn Slope=0.005
Boundary for River Rch & Prof#=Alligator Creek ,Reach-1,7
Up Type=0
Dn Type=3
Dn Slope=0.005

--- Alligator Creek Tributary 6.g01 (geometry) ---

Geom Title=Existing Conditions

River Reach=Alligator Creek ,Reach-1
Reach XY= 30
      2251975.00     13830025.00      2251828.33     13829626.69
      2252161.43     13829238.47      2252448.85     13829101.93
      2252511.37     13828937.95      2252777.46     13828969.55
      2253018.79     13828582.81      2253373.44     13828521.24
      2253680.86     13828327.05      2254127.46     13828519.55
      2254280.19     13828080.44      2254984.71     13827714.25
      2255340.04     13827224.27      2256098.47     13827598.01
      2256372.94     13827930.85      2256380.17     13828469.59
      2256866.52     13828628.51      2257272.55     13829069.54
      2257481.21     13829067.20      2257871.42     13828632.49
      2258095.47     13828794.63      2258422.94     13829180.86
      2258375.52     13829659.78      2258528.61     13830123.50
      2258918.33     13830515.70      2259664.50     13830523.80
      2259995.16     13830274.52      2260137.03     13830423.78
      2260614.57     13830423.95      2260825.00     13830225.00

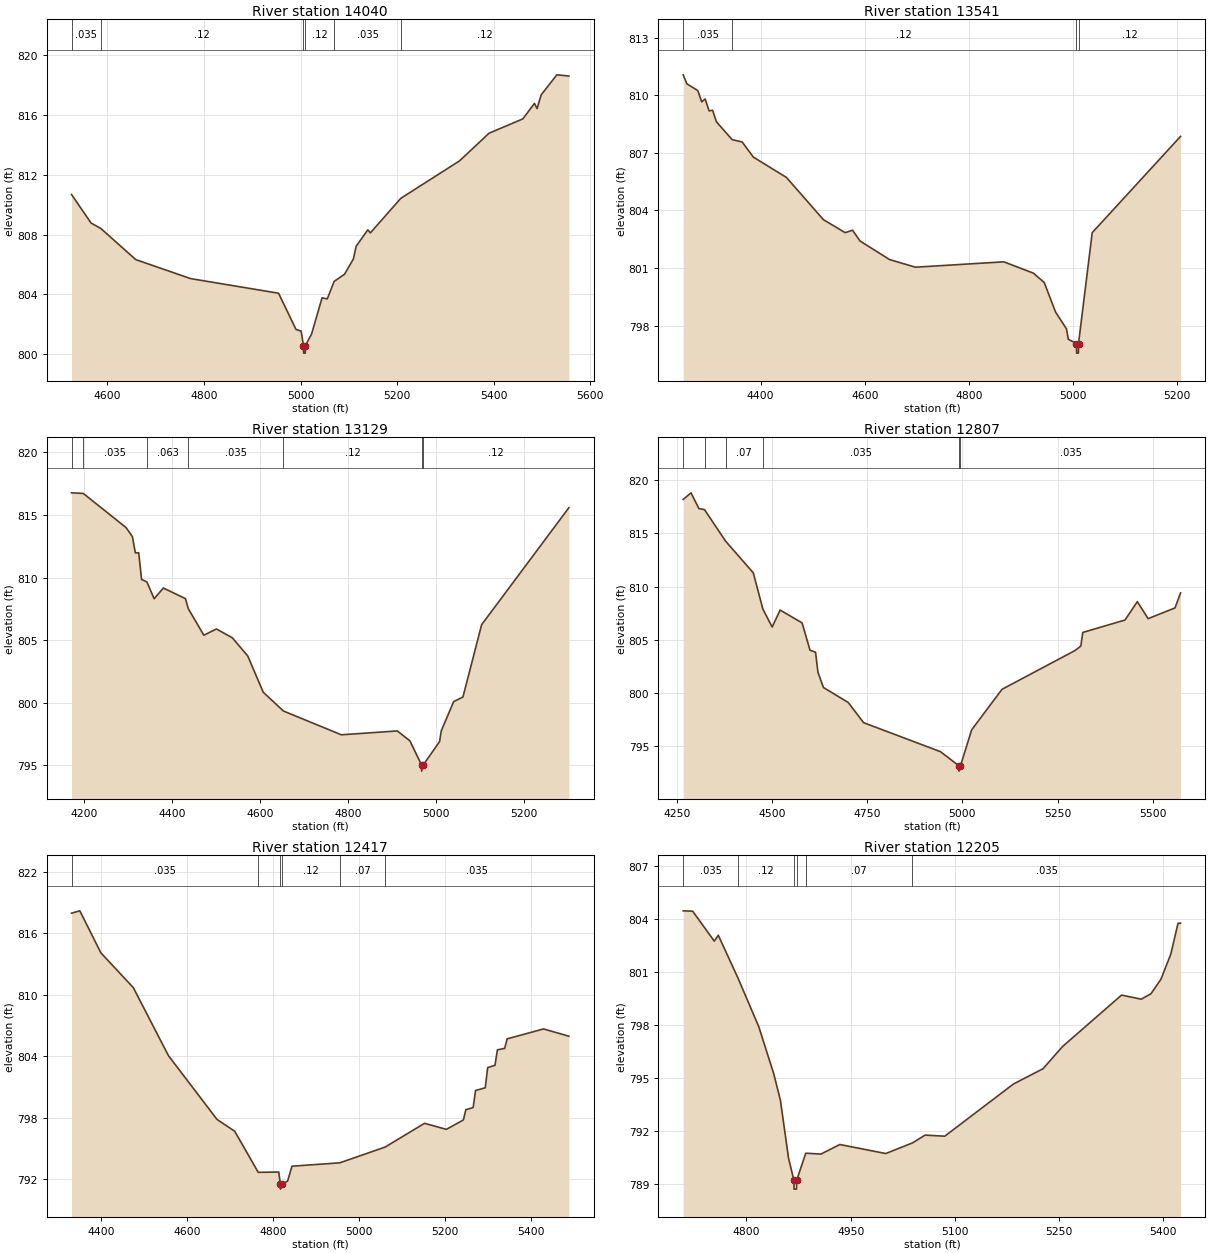
Type RM Length L Ch R = 1,14040,499,499,499
BEGIN DESCRIPTION:
Alligator Creek Tributary 613033
END DESCRIPTION:
XS GIS Cut Line= 3
      2252414.20     13830087.52      2252004.51     13829986.84
      2251441.98     13830216.01
#Sta/Elev= 30
  4526.1  810.68  4566.5  808.77  4586.9  808.40  4659.1  806.32  4772.4  805.05
  4954.6  804.07  4990.6  801.65  5001.4  801.53  5006.1  800.56  5006.4  800.06
  5009.9  800.06  5010.1  800.56  5023.0  801.35  5044.6  803.76  5055.4  803.69
  5069.6  804.86  5091.1  805.34  5109.4  806.36  5115.1  807.21  5139.2  808.31
  5144.6  808.11  5207.5  810.42  5329.1  812.93  5390.2  814.78  5460.2  815.74
  5484.2  816.78  5489.6  816.43  5498.1  817.35  5530.5  818.69  5555.4  818.61
#Mann=6,-1,0
  4526.1   0.035       0  4586.9    0.12       0  5006.1    0.05       0
  5010.1    0.12       0  5069.6   0.035       0  5207.5    0.12       0
Bank Sta=5006.1,5010.1
Exp/Cntr=0.3,0.1

Type RM Length L Ch R = 1,13541,412,412,412
BEGIN DESCRIPTION:
Alligator Creek Tributary 68736
END DESCRIPTION:
XS GIS Cut Line= 3
      2252424.99     13830074.99      2251875.00     13829575.00
      2251725.02     13829425.02
#Sta/Elev= 30
  4251.3  811.07  4258.4  810.60  4279.3  810.25  4286.8  809.66  4293.5  809.81
  4301.0  809.19  4307.7  809.22  4315.1  808.62  4345.4  807.69  4364.5  807.57
  4386.1  806.78  4449.6  805.72  4520.6  803.52  4562.5  802.84  4576.7  802.97
  4590.8  802.41  4647.6  801.44  4697.3  801.04  4867.2  801.32  4924.0  800.73
  4944.9  800.24  4966.6  798.70  4987.5  797.83  4991.2  797.28  5006.7  797.06
  5007.0  796.56  5010.5  796.56  5010.7  797.06  5037.0  802.84  5206.7  807.86
#Mann=4,-1,0
  4251.3   0.035       0  4345.4    0.12       0  5006.7    0.05       0
  5010.7    0.12       0
Bank Sta=5006.7,5010.7
Exp/Cntr=0.3,0.1

Type RM Length L Ch R = 1,13129,322,322,322
BEGIN DESCRIPTION:
Alligator Creek Tributary 68735
END DESCRIPTION:
XS GIS Cut Line= 3
      2252674.64     13829900.02      2252125.00     13829275.00
      2251918.99     13829061.09
#Sta/Elev= 30
  4172.5  816.77  4199.3  816.72  4296.5  813.99  4310.8  813.27  4317.4  811.97
  4325.0  811.99  4331.6  809.85  4343.6  809.66  4360.1  808.31  4381.0  809.17
  4431.3  808.32  4437.5  807.53  4473.0  805.40  4501.5  805.90  4537.5  805.20
  4572.6  803.75  4607.8  800.85  4653.6  799.35  4785.2  797.45  4912.3  797.76
  4940.8  796.97  4967.2  795.05  4967.5  794.55  4971.2  795.05  5008.3  796.91
  5011.9  797.75  5040.2  800.10  5061.3  800.47  5103.7  806.24  5301.8  815.58
#Mann=7,-1,0
  4172.5    0.07       0  4199.3   0.035       0  4343.6   0.063       0
  4437.5   0.035       0  4653.6    0.12       0  4967.2    0.05       0
  4971.2    0.12       0
Bank Sta=4967.2,4971.2
Exp/Cntr=0.3,0.1

Type RM Length L Ch R = 1,12807,390,390,390
BEGIN DESCRIPTION:
Alligator Creek Tributary 613032
END DESCRIPTION:
XS GIS Cut Line= 3
      2252695.51     13829792.43      2252448.95     13829479.89
      2252323.96     13828580.62
#Sta/Elev= 30
  4266.8  818.20  4287.2  818.82  4308.0  817.34  4322.7  817.24  4378.4  814.26
  4450.8  811.29  4476.0  807.88  4500.4  806.19  4521.3  807.79  4579.0  806.58
  4599.8  804.01  4614.3  803.82  4620.6  801.93  4635.1  800.50  4700.1  799.09
  4740.5  797.19  4942.4  794.46  4990.9  793.13  4991.1  792.63  4994.9  793.13
  5024.3  796.52  5104.0  800.33  5295.8  803.98  5311.0  804.40  5316.0  805.68
  5427.0  806.85  5459.3  808.58  5487.6  806.98  5558.3  807.99  5572.8  809.40
#Mann=6,-1,0
  4266.8    0.07       0  4322.7   0.035       0  4378.4    0.07       0
  4476.0   0.035       0  4990.9   0.035       0  4994.9   0.035       0
Bank Sta=4990.9,4994.9
Exp/Cntr=0.3,0.1

Type RM Length L Ch R = 1,12417,212,212,212
BEGIN DESCRIPTION:
Alligator Creek Tributary 68734
END DESCRIPTION:
XS GIS Cut Line= 3
      2252775.00     13829625.02      2252605.20     13828854.89
      2252445.49     13828525.05
#Sta/Elev= 30
  4332.1  817.98  4351.4  818.21  4400.2  814.11  4475.5  810.71  4557.4  804.05
  4670.0  797.83  4711.0  796.68  4765.8  792.66  4813.4  792.69  4817.1  791.52
  4817.4  791.02  4821.1  791.52  4833.9  791.80  4844.1  793.26  4955.3  793.59
  5060.5  795.13  5152.0  797.45  5202.7  796.86  5242.3  797.78  5247.9  798.78
  5264.9  798.99  5270.5  800.66  5293.0  800.92  5298.6  802.89  5315.6  803.12
  5321.2  804.63  5338.2  804.77  5343.8  805.70  5428.5  806.67  5487.2  805.96
#Mann=6,-1,0
  4332.1   0.035       0  4765.8    0.12       0  4817.1    0.05       0
  4821.1    0.12       0  4955.3    0.07       0  5060.5   0.035       0
Bank Sta=4817.1,4821.1
Exp/Cntr=0.3,0.1

Type RM Length L Ch R = 1,12205,422,422,422
BEGIN DESCRIPTION:
Alligator Creek Tributary 68733
END DESCRIPTION:
XS GIS Cut Line= 3
      2252974.98     13829174.96      2252825.00     13828925.00
      2252524.98     13828624.98
#Sta/Elev= 30
  4709.0  804.44  4722.6  804.42  4753.7  802.73  4759.5  803.06  4788.3  800.60
  4817.8  797.89  4839.2  795.25  4848.9  793.74  4860.6  790.47  4868.3  789.22
  4868.5  788.72  4872.0  788.72  4872.3  789.22  4885.4  790.75  4907.2  790.70
  4934.4  791.24  5000.5  790.73  5038.9  791.33  5057.1  791.77  5085.4  791.71
  5184.4  794.66  5226.8  795.52  5255.1  796.78  5339.9  799.68  5368.2  799.45
  5382.3  799.76  5396.5  800.57  5410.6  801.97  5421.2  803.74  5424.8  803.74
#Mann=6,-1,0
  4709.0   0.035       0  4788.3    0.12       0  4868.3    0.05       0
  4872.3    0.12       0  4885.4    0.07       0  5038.9   0.035       0
Bank Sta=4868.3,4872.3
Exp/Cntr=0.3,0.1

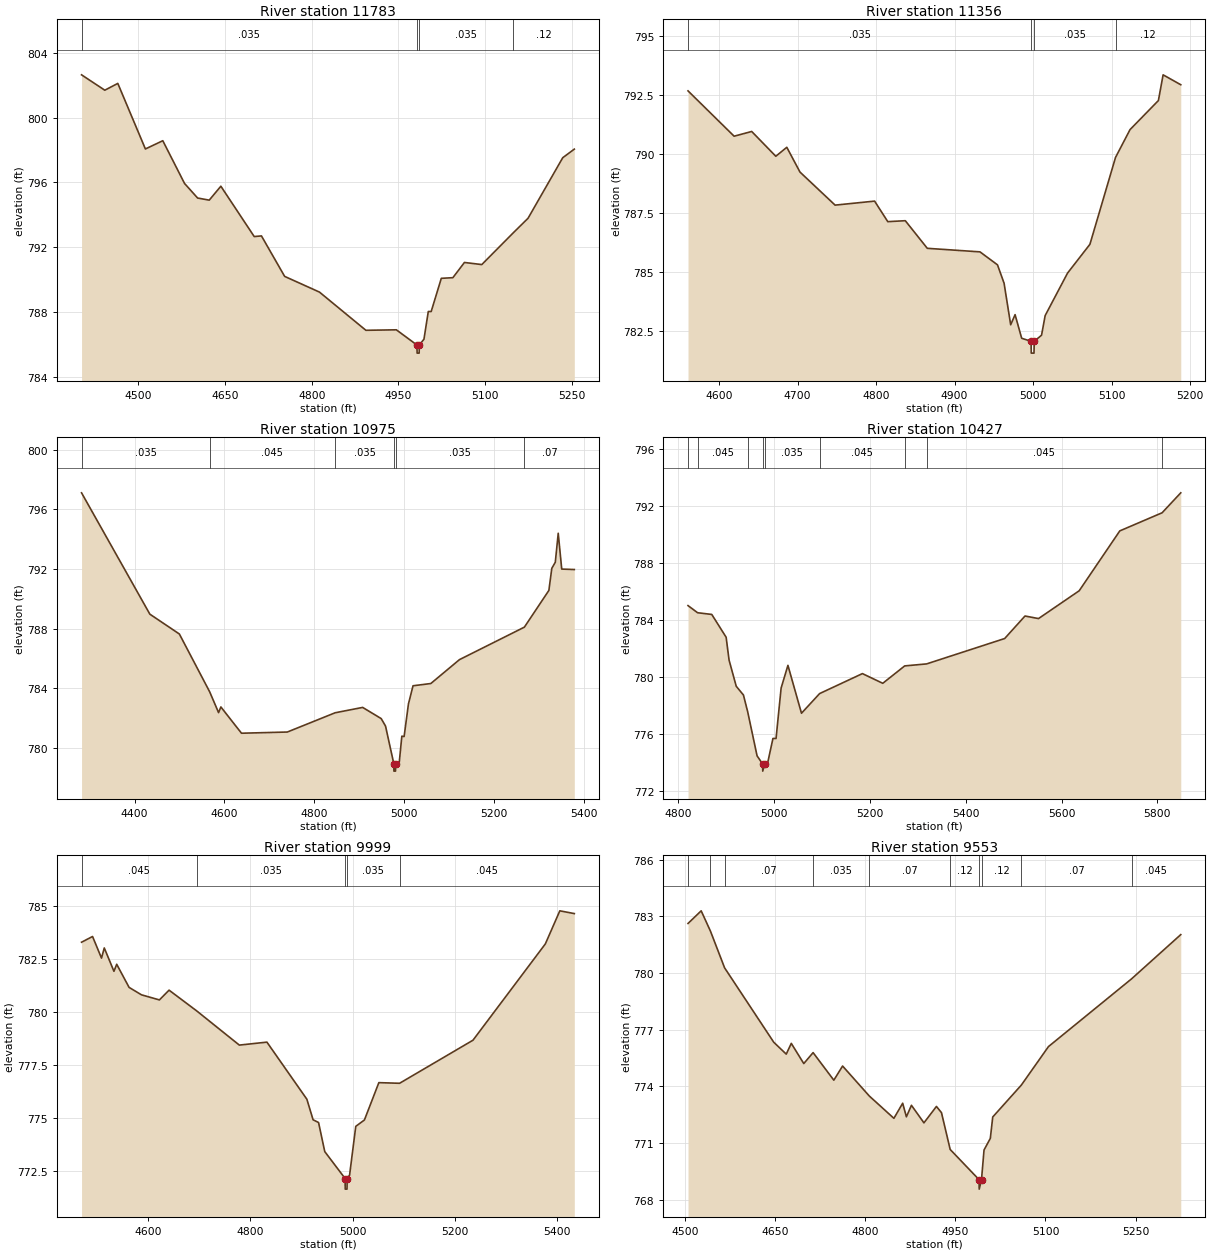
Type RM Length L Ch R = 1,11783,427,427,427
BEGIN DESCRIPTION:
Alligator Creek Tributary 68732
END DESCRIPTION:
XS GIS Cut Line= 3
      2253075.00     13829175.02      2253025.00     13828575.00
      2253025.00     13828325.00
#Sta/Elev= 30
  4402.0  802.65  4442.2  801.70  4464.7  802.12  4512.4  798.07  4542.5  798.58
  4580.1  795.94  4602.7  795.04  4622.8  794.91  4642.9  795.77  4700.6  792.66
  4713.1  792.70  4753.2  790.20  4813.4  789.23  4893.7  786.87  4946.4  786.90
  4982.0  785.96  4982.3  785.46  4985.8  785.46  4986.0  785.96  4994.1  786.32
  5001.6  788.03  5006.6  788.03  5024.1  790.08  5044.1  790.12  5064.1  791.06
  5094.1  790.93  5148.8  792.90  5174.1  793.79  5234.1  797.53  5254.1  798.06
#Mann=4,-1,0
  4402.0   0.035       0  4982.0   0.035       0  4986.0   0.035       0
  5148.8    0.12       0
Bank Sta=4982,4986
Exp/Cntr=0.3,0.1

Type RM Length L Ch R = 1,11356,381,381,381
BEGIN DESCRIPTION:
Alligator Creek Tributary 68731
END DESCRIPTION:
XS GIS Cut Line= 3
      2253224.99     13828875.03      2253425.00     13828475.00
      2253325.01     13828325.02
#Sta/Elev= 30
  4560.5  792.67  4619.2  790.75  4641.6  790.95  4672.3  789.90  4686.3  790.28
  4703.1  789.23  4747.8  787.83  4798.1  788.00  4814.9  787.13  4837.2  787.17
  4865.2  786.00  4932.3  785.85  4954.6  785.30  4963.0  784.52  4971.4  782.76
  4977.0  783.19  4985.4  782.19  4997.4  782.06  4997.6  781.56  5001.1  781.56
  5001.4  782.06  5010.7  782.32  5015.3  783.15  5043.8  784.95  5072.3  786.17
  5104.9  789.85  5123.4  791.03  5159.5  792.26  5165.5  793.35  5188.0  792.93
#Mann=4,-1,0
  4560.5   0.035       0  4997.4   0.035       0  5001.4   0.035       0
  5104.9    0.12       0
Bank Sta=4997.4,5001.4
Exp/Cntr=0.3,0.1

Type RM Length L Ch R = 1,10975,548,548,548
BEGIN DESCRIPTION:
Alligator Creek Tributary 68730
END DESCRIPTION:
XS GIS Cut Line= 3
      2253889.92     13829028.51      2253740.62     13828281.97
      2253524.98     13828024.98
#Sta/Elev= 30
  4282.1  797.10  4434.1  788.97  4499.8  787.64  4567.2  783.77  4587.1  782.37
  4592.2  782.75  4638.1  780.99  4740.1  781.07  4846.5  782.36  4907.8  782.72
  4949.1  781.97  4958.7  781.47  4977.1  778.95  4977.4  778.45  4980.9  778.45
  4981.1  778.95  4989.3  779.05  4995.0  780.79  5000.1  780.77  5009.7  782.95
  5019.9  784.17  5059.5  784.32  5123.2  785.92  5267.8  788.10  5322.3  790.56
  5328.8  792.04  5336.6  792.45  5343.1  794.39  5350.9  791.99  5378.9  791.96
#Mann=6,-1,0
  4282.1   0.035       0  4567.2   0.045       0  4846.5   0.035       0
  4977.1   0.035       0  4981.1   0.035       0  5267.8    0.07       0
Bank Sta=4977.1,4981.1
Exp/Cntr=0.3,0.1

Type RM Length L Ch R = 1,10427,428,428,428
BEGIN DESCRIPTION:
Alligator Creek Tributary 68729
END DESCRIPTION:
XS GIS Cut Line= 3
      2254275.01     13828625.02      2254175.00     13828475.00
      2253575.02     13827875.02
#Sta/Elev= 30
  4820.2  785.01  4840.2  784.51  4869.8  784.39  4899.8  782.79  4905.9  781.19
  4920.9  779.35  4935.9  778.74  4944.8  777.56  4964.4  774.47  4976.0  773.90
  4976.2  773.40  4980.0  773.90  4987.0  774.06  4997.5  775.69  5004.0  775.69
  5014.6  779.23  5028.8  780.82  5057.1  777.46  5095.0  778.84  5184.3  780.24
  5226.8  779.56  5272.6  780.78  5318.3  780.92  5481.3  782.70  5523.8  784.28
  5552.0  784.10  5636.9  786.05  5721.7  790.25  5810.0  791.52  5849.0  792.92
#Mann=9,-1,0
  4820.2   0.035       0  4840.2   0.045       0  4944.8   0.035       0
  4976.0   0.035       0  4980.0   0.035       0  5095.0   0.045       0
  5272.6   0.035       0  5318.3   0.045       0  5810.0    0.07       0
Bank Sta=4976,4980
Exp/Cntr=0.3,0.1

Type RM Length L Ch R = 1,9999,446,446,446
BEGIN DESCRIPTION:
Alligator Creek Tributary 68728
END DESCRIPTION:
XS GIS Cut Line= 3
      2254475.00     13828575.00      2254275.00     13828075.00
      2253974.99     13827774.99
#Sta/Elev= 30
  4470.2  783.30  4491.7  783.57  4509.2  782.55  4514.6  783.03  4533.5  781.93
  4538.9  782.26  4563.1  781.17  4587.3  780.82  4622.3  780.58  4641.2  781.04
  4695.3  780.06  4778.5  778.45  4832.4  778.59  4910.4  775.90  4922.6  774.93
  4933.3  774.80  4945.4  773.43  4985.2  772.16  4985.4  771.66  4988.9  771.66
  4989.2  772.16  4993.9  772.32  5006.0  774.62  5022.9  774.92  5051.1  776.68
  5091.6  776.65  5235.0  778.68  5376.4  783.22  5404.7  784.78  5433.0  784.65
#Mann=5,-1,0
  4470.2   0.045       0  4695.3   0.035       0  4985.2   0.035       0
  4989.2   0.035       0  5091.6   0.045       0
Bank Sta=4985.2,4989.2
Exp/Cntr=0.3,0.1

Type RM Length L Ch R = 1,9553,446,446,446
BEGIN DESCRIPTION:
Alligator Creek Tributary 68727
END DESCRIPTION:
XS GIS Cut Line= 3
      2255025.00     13828125.00      2254625.00     13827825.00
      2254424.97     13827574.97
#Sta/Elev= 30
  4505.0  782.62  4526.9  783.29  4542.4  782.21  4565.9  780.27  4647.7  776.33
  4668.5  775.70  4676.9  776.27  4697.7  775.20  4713.2  775.78  4747.7  774.32
  4762.3  775.07  4806.8  773.48  4847.7  772.30  4862.3  773.10  4868.5  772.38
  4876.9  772.99  4897.7  772.06  4918.5  772.93  4926.9  772.60  4941.4  770.65
  4989.5  769.05  4989.7  768.55  4993.5  769.05  4997.7  770.62  5008.2  771.24
  5012.2  772.37  5059.8  774.06  5105.0  776.10  5243.4  779.69  5325.2  782.03
#Mann=10,-1,0
  4505.0    0.07       0  4542.4   0.035       0  4565.9    0.07       0
  4713.2   0.035       0  4806.8    0.07       0  4941.4    0.12       0
  4989.5    0.05       0  4993.5    0.12       0  5059.8    0.07       0
  5243.4   0.045       0
Bank Sta=4989.5,4993.5
Exp/Cntr=0.3,0.1

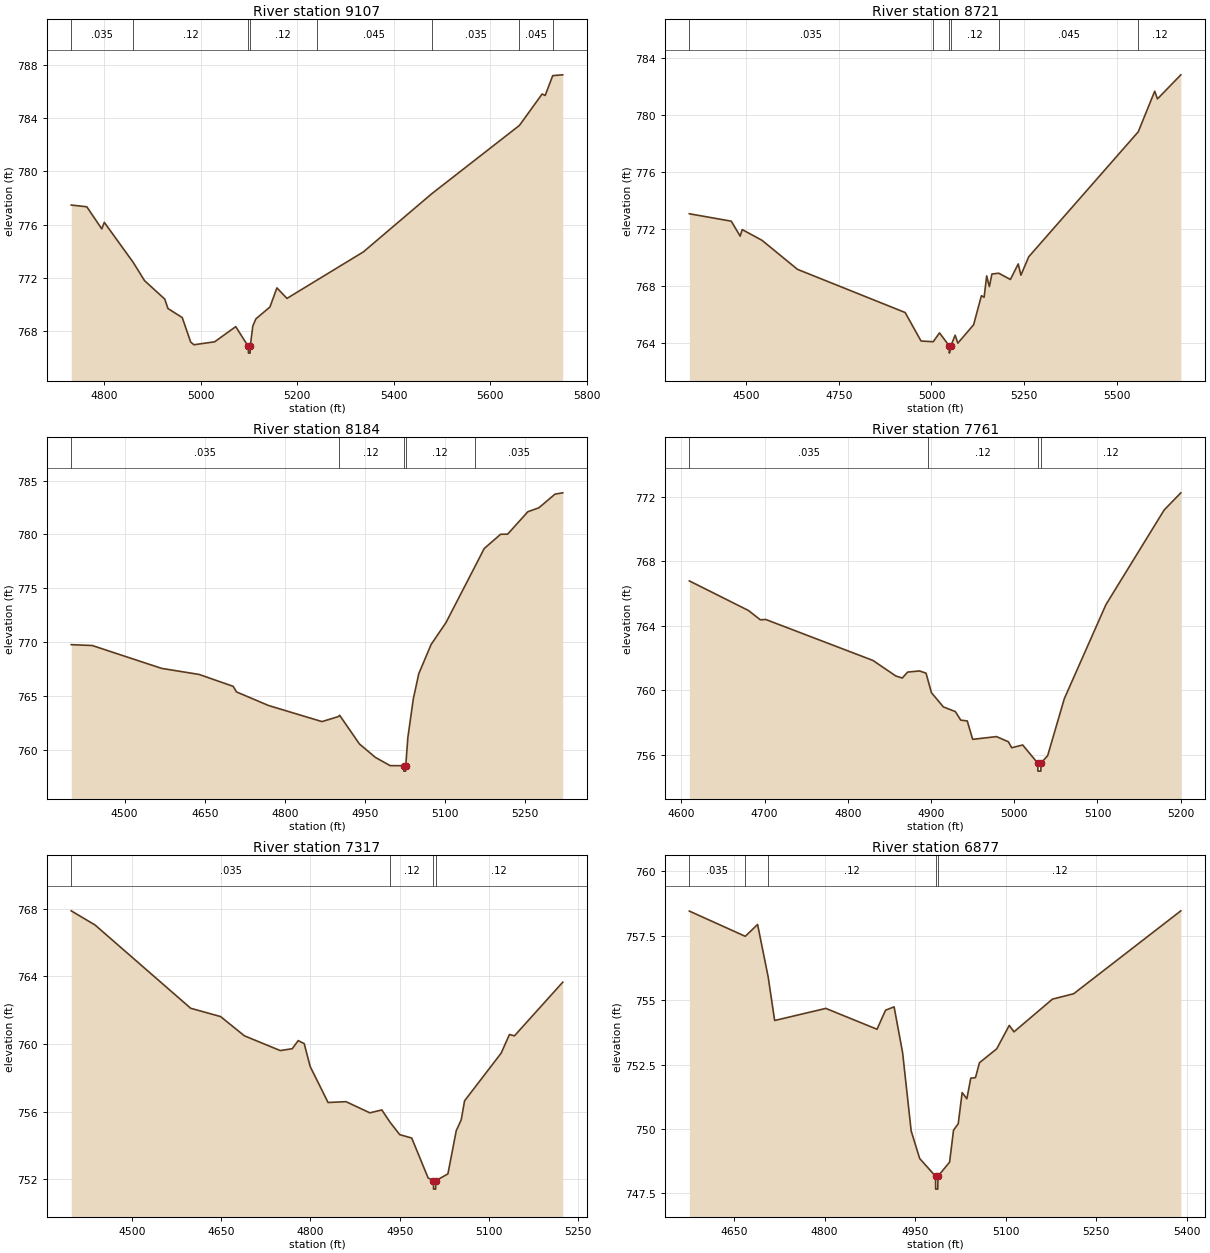
Type RM Length L Ch R = 1,9107,386,386,386
BEGIN DESCRIPTION:
Alligator Creek Tributary 68726
END DESCRIPTION:
XS GIS Cut Line= 3
      2255125.00     13827924.99      2255025.00     13827675.00
      2254425.04     13827225.03
#Sta/Elev= 30
  4731.3  777.47  4763.6  777.34  4794.6  775.68  4799.9  776.17  4859.7  773.17
  4883.4  771.79  4925.2  770.41  4931.9  769.70  4961.5  769.02  4979.0  767.18
  4985.7  766.98  5028.7  767.20  5072.4  768.34  5098.5  766.85  5098.8  766.35
  5102.3  766.35  5102.5  766.85  5107.8  768.38  5114.1  768.92  5143.3  769.81
  5157.8  771.25  5178.7  770.46  5239.9  771.81  5337.0  773.95  5478.9  778.32
  5660.7  783.45  5707.8  785.81  5714.1  785.70  5729.8  787.19  5750.5  787.25
#Mann=8,-1,0
  4731.3   0.035       0  4859.7    0.12       0  5098.5    0.05       0
  5102.5    0.12       0  5239.9   0.045       0  5478.9   0.035       0
  5660.7   0.045       0  5729.8   0.035       0
Bank Sta=5098.5,5102.5
Exp/Cntr=0.3,0.1

Type RM Length L Ch R = 1,8721,537,537,537
BEGIN DESCRIPTION:
Alligator Creek Tributary 613031
END DESCRIPTION:
XS GIS Cut Line= 3
      2255462.83     13827945.15      2255233.67     13827389.61
      2254741.40     13826859.20
#Sta/Elev= 30
  4347.5  773.04  4460.5  772.52  4484.5  771.47  4489.9  771.93  4543.1  771.18
  4638.9  769.14  4929.1  766.11  4971.9  764.11  5004.8  764.06  5021.7  764.68
  5048.1  763.76  5048.3  763.26  5052.1  763.76  5063.9  764.52  5071.1  763.96
  5113.6  765.25  5134.6  767.29  5141.9  767.18  5148.8  768.68  5156.1  767.93
  5162.9  768.81  5181.2  768.87  5212.8  768.43  5233.8  769.52  5241.1  768.73
  5262.1  770.02  5557.3  778.79  5601.7  781.64  5609.1  781.10  5672.1  782.79
#Mann=6,-1,0
  4347.5   0.035       0  5004.8    0.12       0  5048.1   0.035       0
  5052.1    0.12       0  5181.2   0.045       0  5557.3    0.12       0
Bank Sta=5048.1,5052.1
Exp/Cntr=0.3,0.1

Type RM Length L Ch R = 1,8184,423,423,423
BEGIN DESCRIPTION:
Alligator Creek Tributary 68725
END DESCRIPTION:
XS GIS Cut Line= 3
      2255594.78     13827924.32      2255625.00     13827325.00
      2255692.00     13827011.15
#Sta/Elev= 30
  4399.9  769.79  4439.3  769.71  4569.4  767.59  4639.5  767.03  4703.3  765.93
  4709.6  765.41  4769.7  764.15  4869.8  762.66  4900.8  763.13  4902.8  763.25
  4939.9  760.59  4969.9  759.34  4997.5  758.58  5022.7  758.57  5023.0  758.07
  5026.5  758.07  5026.7  758.57  5030.7  761.19  5040.9  764.76  5051.1  767.09
  5074.2  769.80  5102.2  771.84  5155.8  776.97  5173.8  778.70  5204.5  780.02
  5217.7  780.03  5255.6  782.11  5276.1  782.47  5306.5  783.74  5320.9  783.86
#Mann=5,-1,0
  4399.9   0.035       0  4900.8    0.12       0  5022.7    0.05       0
  5026.7    0.12       0  5155.8   0.035       0
Bank Sta=5022.7,5026.7
Exp/Cntr=0.3,0.1

Type RM Length L Ch R = 1,7761,444,444,444
BEGIN DESCRIPTION:
Alligator Creek Tributary 68724
END DESCRIPTION:
XS GIS Cut Line= 3
      2255675.00     13827775.00      2255975.00     13827525.00
      2255975.00     13827325.01
#Sta/Elev= 30
  4609.7  766.78  4680.6  764.95  4695.0  764.37  4701.5  764.39  4830.3  761.85
  4857.7  760.89  4865.5  760.76  4872.0  761.13  4886.3  761.20  4894.1  761.06
  4896.5  760.61  4900.6  759.85  4914.9  758.97  4929.3  758.68  4935.8  758.15
  4943.6  758.10  4950.1  756.96  4978.7  757.13  4993.0  756.81  4997.0  756.44
  5010.2  756.61  5028.2  755.49  5028.5  754.99  5032.0  754.99  5032.2  755.49
  5040.2  755.95  5060.2  759.48  5110.2  765.31  5180.2  771.18  5200.2  772.24
#Mann=4,-1,0
  4609.7   0.035       0  4896.5    0.12       0  5028.2    0.05       0
  5032.2    0.12       0
Bank Sta=5028.2,5032.2
Exp/Cntr=0.3,0.1

Type RM Length L Ch R = 1,7317,440,440,440
BEGIN DESCRIPTION:
Alligator Creek Tributary 68723
END DESCRIPTION:
XS GIS Cut Line= 3
      2255675.00     13827875.00      2256275.00     13827825.00
      2256375.01     13827624.99
#Sta/Elev= 30
  4398.2  767.87  4438.3  767.03  4598.9  762.11  4649.1  761.62  4689.2  760.48
  4749.4  759.61  4769.5  759.72  4779.5  760.20  4789.6  760.02  4799.6  758.67
  4829.7  756.54  4859.8  756.59  4899.9  755.93  4920.0  756.10  4933.7  755.38
  4950.1  754.64  4970.2  754.44  4997.8  752.08  5006.7  751.92  5006.9  751.42
  5010.4  751.42  5010.7  751.92  5031.0  752.32  5045.0  754.87  5053.4  755.52
  5059.0  756.64  5120.5  759.46  5134.4  760.56  5142.8  760.48  5223.9  763.65
#Mann=4,-1,0
  4398.2   0.035       0  4933.7    0.12       0  5006.7    0.05       0
  5010.7    0.12       0
Bank Sta=5006.7,5010.7
Exp/Cntr=0.3,0.1

Type RM Length L Ch R = 1,6877,457,457,457
BEGIN DESCRIPTION:
Alligator Creek Tributary 68722
END DESCRIPTION:
XS GIS Cut Line= 3
      2256075.03     13828524.97      2256375.00     13828225.00
      2256624.98     13827925.03
#Sta/Elev= 30
  4575.8  758.46  4668.5  757.48  4688.9  757.94  4706.4  755.91  4717.2  754.21
  4802.0  754.68  4886.9  753.87  4901.0  754.61  4915.2  754.74  4929.3  752.96
  4943.5  749.92  4957.6  748.85  4983.9  748.16  4984.1  747.66  4987.6  747.66
  4987.9  748.16  5007.2  748.71  5013.7  749.95  5021.5  750.20  5028.0  751.41
  5035.8  751.17  5042.3  751.97  5050.1  751.99  5056.7  752.57  5085.3  753.11
  5106.1  754.02  5113.9  753.77  5177.7  755.04  5212.9  755.25  5390.5  758.47
#Mann=5,-1,0
  4575.8   0.035       0  4668.5    0.07       0  4706.4    0.12       0
  4983.9    0.05       0  4987.9    0.12       0
Bank Sta=4983.9,4987.9
Exp/Cntr=0.3,0.1

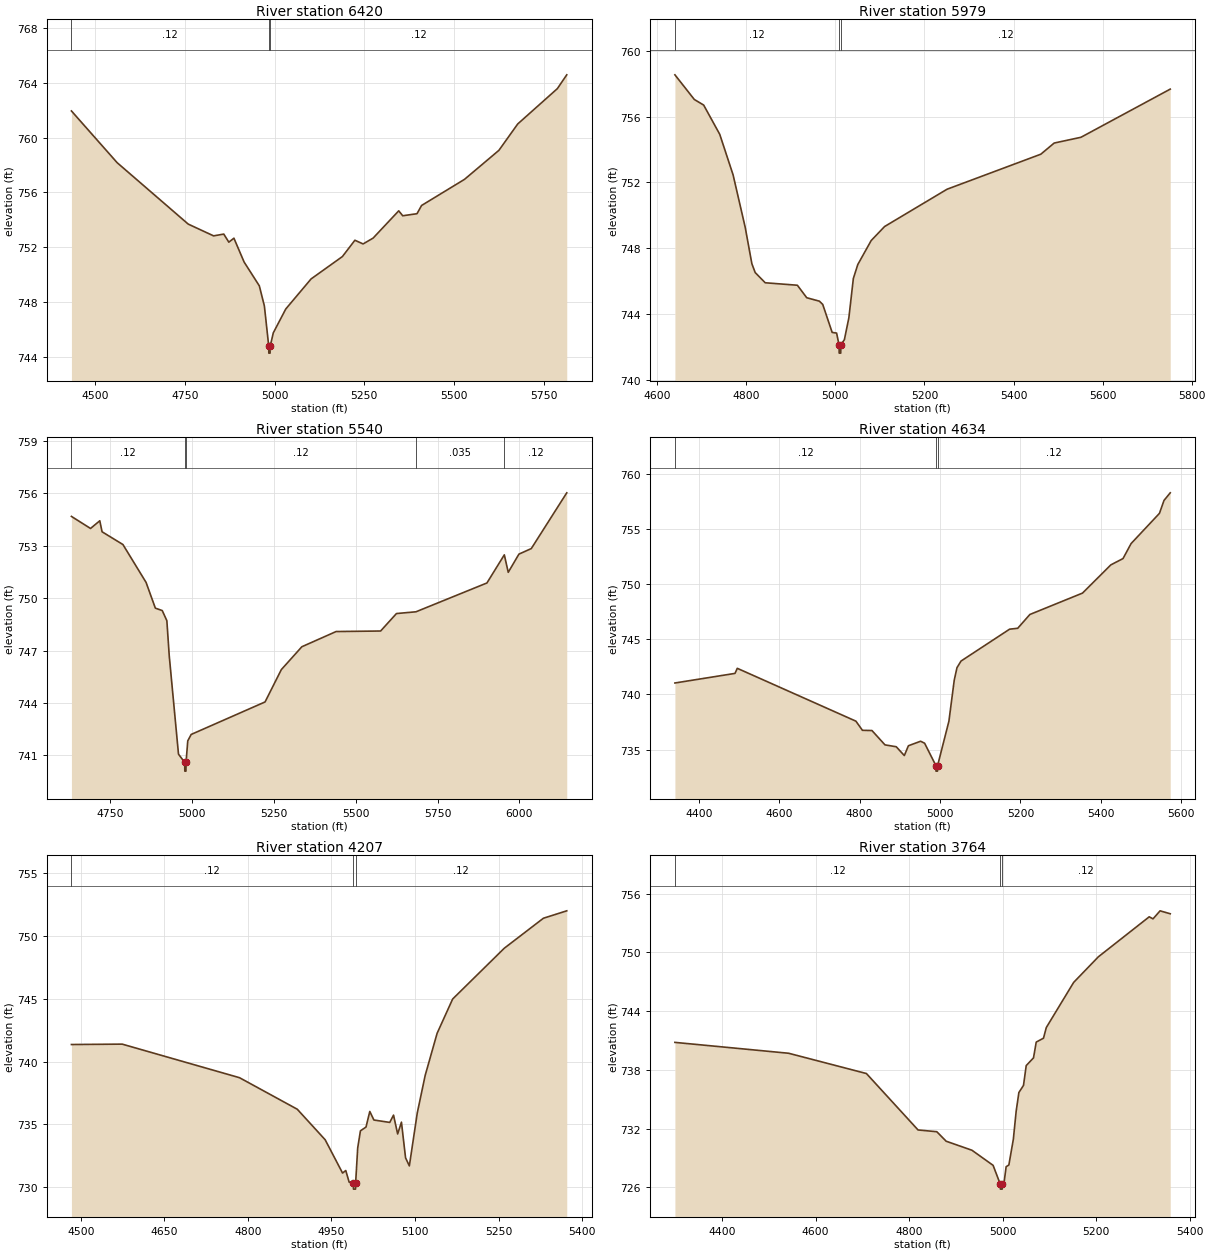
Type RM Length L Ch R = 1,6420,441,441,441
BEGIN DESCRIPTION:
Alligator Creek Tributary 68721
END DESCRIPTION:
XS GIS Cut Line= 3
      2256174.99     13828925.01      2256575.00     13828525.00
      2256724.99     13827725.05
#Sta/Elev= 30
  4434.3  761.96  4561.6  758.18  4759.6  753.69  4830.3  752.83  4858.6  752.96
  4872.7  752.37  4886.9  752.66  4915.2  750.92  4957.6  749.18  4971.7  747.71
  4983.9  744.76  4984.1  744.26  4987.6  744.26  4987.9  744.76  4996.5  745.74
  5031.4  747.49  5101.7  749.68  5189.1  751.32  5223.8  752.51  5246.7  752.24
  5274.7  752.67  5345.9  754.66  5357.0  754.30  5396.8  754.45  5409.5  755.05
  5529.1  756.96  5624.9  759.08  5677.4  761.01  5787.7  763.59  5813.9  764.60
#Mann=3,-1,0
  4434.3    0.12       0  4983.9    0.05       0  4987.9    0.12       0
Bank Sta=4983.9,4987.9
Exp/Cntr=0.3,0.1

Type RM Length L Ch R = 1,5979,439,439,439
BEGIN DESCRIPTION:
Alligator Creek Tributary 68720
END DESCRIPTION:
XS GIS Cut Line= 3
      2256724.98     13829025.03      2256925.00     13828725.00
      2256975.00     13827974.95
#Sta/Elev= 30
  4639.6  758.54  4683.2  757.04  4704.2  756.70  4740.3  754.92  4770.3  752.45
  4797.4  749.27  4812.4  747.05  4819.9  746.51  4842.4  745.89  4914.6  745.74
  4935.6  744.98  4964.1  744.77  4971.6  744.57  4992.7  742.87  5002.7  742.83
  5008.2  742.11  5008.5  741.61  5012.0  741.61  5012.2  742.11  5020.2  742.43
  5030.3  743.77  5040.3  746.15  5050.3  747.00  5080.4  748.46  5110.4  749.31
  5250.7  751.58  5461.2  753.71  5491.3  754.39  5551.4  754.74  5751.9  757.67
#Mann=3,-1,0
  4639.6    0.12       0  5008.2    0.05       0  5012.2    0.12       0
Bank Sta=5008.2,5012.2
Exp/Cntr=0.3,0.1

Type RM Length L Ch R = 1,5540,906,906,906
BEGIN DESCRIPTION:
Alligator Creek Tributary 68719
END DESCRIPTION:
XS GIS Cut Line= 3
      2256969.77     13829292.40      2257225.00     13829025.00
      2257563.54     13827931.25
#Sta/Elev= 30
  4630.6  754.68  4689.0  753.99  4717.3  754.43  4724.3  753.80  4788.1  753.07
  4858.9  750.90  4887.2  749.43  4908.3  749.29  4922.4  748.71  4929.7  746.70
  4958.0  741.07  4977.0  740.60  4977.3  740.10  4980.8  740.10  4981.1  740.60
  4986.3  741.83  4996.8  742.20  5222.7  744.06  5272.4  745.91  5335.2  747.22
  5439.9  748.09  5576.0  748.12  5624.5  749.12  5684.1  749.22  5901.1  750.87
  5954.3  752.48  5966.3  751.48  5998.9  752.52  6036.8  752.84  6145.2  756.03
#Mann=5,-1,0
  4630.6    0.12       0  4977.0    0.05       0  4981.1    0.12       0
  5684.1   0.035       0  5954.3    0.12       0
Bank Sta=4977,4981.1
Exp/Cntr=0.3,0.1

Type RM Length L Ch R = 1,4634,427,427,427
BEGIN DESCRIPTION:
Alligator Creek Tributary 613030
END DESCRIPTION:
XS GIS Cut Line= 3
      2257636.46     13829236.82      2257865.62     13828813.22
      2257952.23     13828068.35
#Sta/Elev= 30
  4340.8  741.03  4490.2  741.90  4495.9  742.36  4790.8  737.57  4807.0  736.74
  4830.7  736.72  4863.1  735.42  4891.1  735.25  4911.2  734.45  4921.3  735.34
  4951.7  735.75  4961.6  735.57  4989.7  733.54  4989.9  733.04  4993.6  733.04
  4993.9  733.54  5022.0  737.56  5035.3  741.29  5042.1  742.42  5052.2  743.02
  5173.0  745.91  5193.1  745.99  5223.3  747.24  5354.2  749.18  5424.7  751.74
  5454.9  752.31  5475.0  753.67  5545.5  756.41  5556.8  757.58  5572.3  758.27
#Mann=3,-1,0
  4340.8    0.12       0  4989.7    0.05       0  4993.9    0.12       0
Bank Sta=4989.7,4993.9
Exp/Cntr=0.3,0.1

Type RM Length L Ch R = 1,4207,443,443,443
BEGIN DESCRIPTION:
Alligator Creek Tributary 68718
END DESCRIPTION:
XS GIS Cut Line= 3
      2257726.70     13829191.71      2258175.00     13828925.00
      2258447.74     13828678.90
#Sta/Elev= 30
  4483.3  741.36  4574.4  741.39  4784.9  738.72  4888.6  736.21  4938.7  733.78
  4969.9  731.13  4975.7  731.33  4981.7  730.41  4989.2  730.35  4989.5  729.85
  4993.2  729.85  4993.4  730.35  4997.1  733.13  5002.0  734.49  5012.0  734.79
  5018.8  736.03  5026.2  735.35  5054.6  735.16  5061.4  735.74  5068.8  734.24
  5075.6  735.18  5083.0  732.34  5089.8  731.70  5104.0  735.91  5118.2  738.90
  5139.6  742.25  5167.5  744.98  5260.1  749.02  5330.4  751.41  5372.3  752.00
#Mann=3,-1,0
  4483.3    0.12       0  4989.2    0.05       0  4993.4    0.12       0
Bank Sta=4989.2,4993.4
Exp/Cntr=0.3,0.1

Type RM Length L Ch R = 1,3764,463,463,463
BEGIN DESCRIPTION:
Alligator Creek Tributary 68717
END DESCRIPTION:
XS GIS Cut Line= 3
      2257726.76     13829278.50      2258425.00     13829225.00
      2258733.65     13829042.40
#Sta/Elev= 30
  4299.2  740.81  4542.3  739.70  4708.6  737.63  4819.0  731.87  4859.1  731.69
  4879.1  730.72  4934.2  729.80  4979.4  728.26  4994.8  726.33  4995.1  725.83
  4998.8  725.83  4999.1  726.33  5002.4  726.33  5007.3  728.12  5013.1  728.29
  5022.7  730.92  5028.7  733.77  5034.5  735.69  5044.4  736.42  5050.2  738.44
  5065.8  739.23  5071.6  740.84  5087.2  741.24  5093.1  742.32  5151.6  746.93
  5204.3  749.54  5313.2  753.63  5321.3  753.42  5336.4  754.24  5358.1  753.94
#Mann=3,-1,0
  4299.2    0.12       0  4994.8    0.05       0  4999.1    0.12       0
Bank Sta=4994.8,4999.1
Exp/Cntr=0.3,0.1

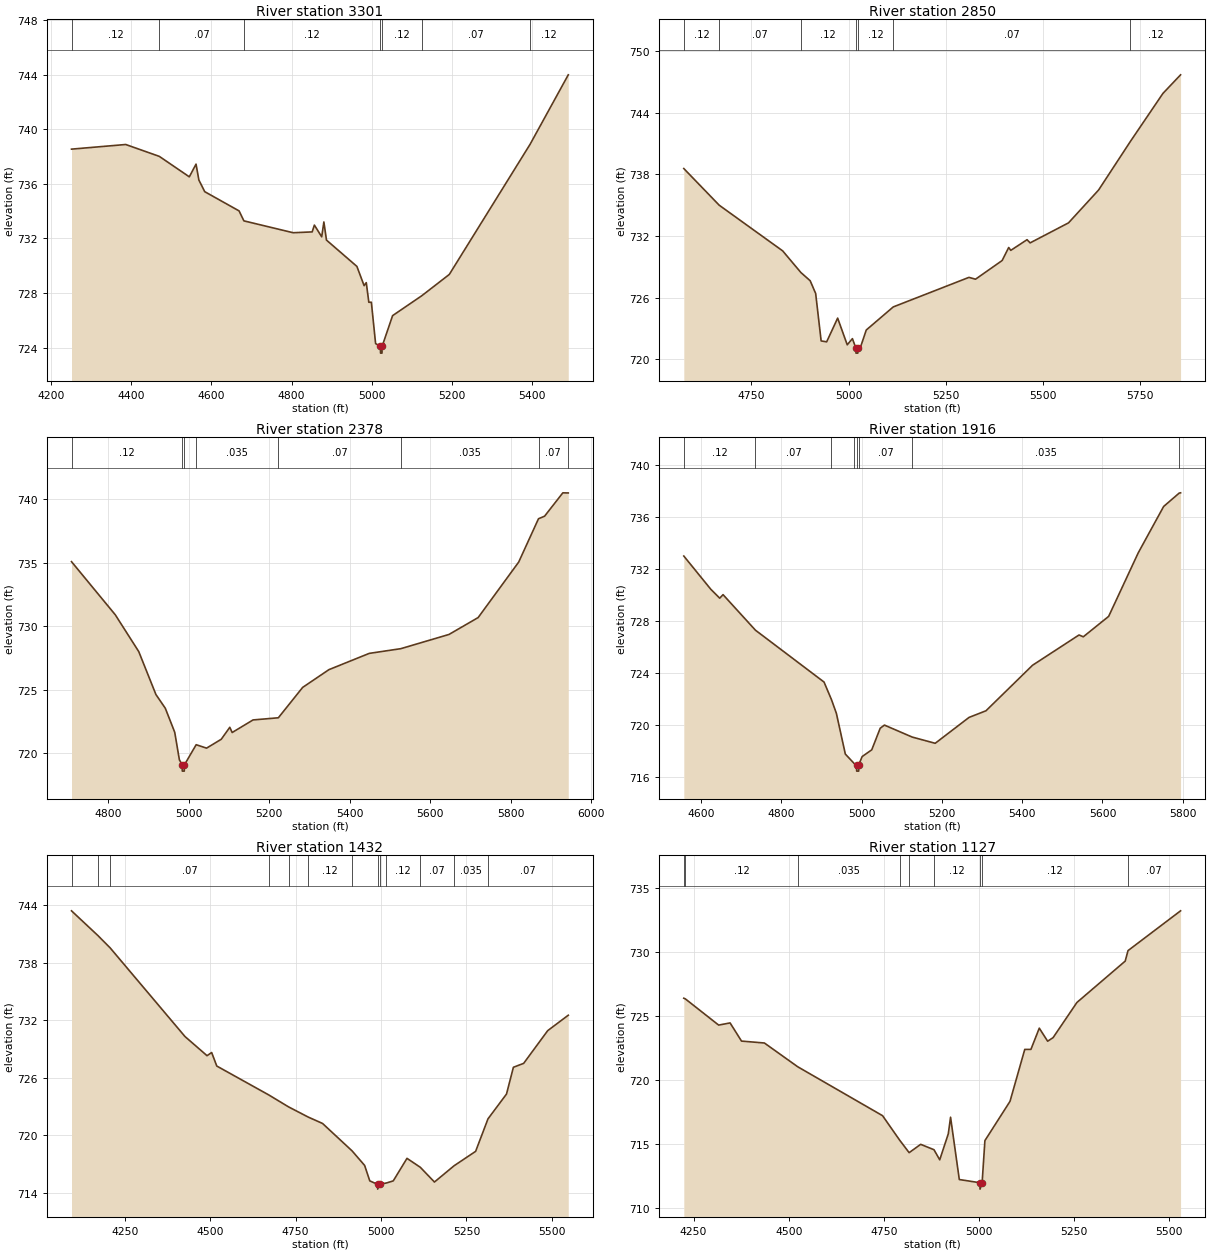
Type RM Length L Ch R = 1,3301,451,451,451
BEGIN DESCRIPTION:
Alligator Creek Tributary 68716
END DESCRIPTION:
XS GIS Cut Line= 3
      2257688.54     13829386.14      2258375.00     13829675.00
      2258724.97     13829325.03
#Sta/Elev= 30
  4250.7  738.55  4386.0  738.89  4469.8  738.02  4544.7  736.52  4561.5  737.45
  4568.5  736.29  4583.2  735.43  4668.9  734.02  4680.9  733.29  4803.8  732.42
  4851.3  732.48  4856.8  732.98  4875.1  732.12  4880.5  733.21  4887.0  731.88
  4962.9  729.95  4980.9  728.54  4986.3  728.76  4992.7  727.32  4999.0  727.32
  5009.6  724.29  5021.6  724.09  5021.9  723.59  5025.6  723.59  5025.9  724.09
  5052.0  726.34  5124.9  727.80  5193.5  729.36  5395.2  738.91  5490.4  744.00
#Mann=7,-1,0
  4250.7    0.12       0  4469.8    0.07       0  4680.9    0.12       0
  5021.6    0.05       0  5025.9    0.12       0  5124.9    0.07       0
  5395.2    0.12       0
Bank Sta=5021.6,5025.9
Exp/Cntr=0.3,0.1

Type RM Length L Ch R = 1,2850,472,472,472
BEGIN DESCRIPTION:
Alligator Creek Tributary 68715
END DESCRIPTION:
XS GIS Cut Line= 3
      2258225.01     13830374.99      2258525.00     13830075.00
      2258825.02     13829274.95
#Sta/Elev= 30
  4575.8  738.57  4666.9  735.00  4830.3  730.55  4877.2  728.44  4901.1  727.64
  4915.2  726.40  4929.3  721.78  4943.5  721.69  4971.8  724.00  4996.5  721.40
  5009.8  722.00  5018.6  721.09  5019.0  720.59  5023.8  720.59  5024.3  721.09
  5032.1  721.34  5045.4  722.84  5114.9  725.09  5309.8  727.97  5326.7  727.79
  5395.2  729.61  5412.1  730.88  5417.5  730.60  5459.3  731.64  5467.3  731.33
  5566.1  733.28  5643.5  736.48  5725.3  741.21  5809.1  745.89  5854.5  747.70
#Mann=7,-1,0
  4575.8    0.12       0  4666.9    0.07       0  4877.2    0.12       0
  5018.6    0.05       0  5024.3    0.12       0  5114.9    0.07       0
  5725.3    0.12       0
Bank Sta=5018.6,5024.3
Exp/Cntr=0.3,0.1

Type RM Length L Ch R = 1,2378,462,462,462
BEGIN DESCRIPTION:
Alligator Creek Tributary 68714
END DESCRIPTION:
XS GIS Cut Line= 3
      2258575.00     13830575.00      2258825.00     13830425.00
      2259324.98     13829625.04
#Sta/Elev= 30
  4708.5  735.10  4817.3  730.92  4875.7  728.02  4918.4  724.64  4941.7  723.56
  4965.1  721.67  4976.7  719.50  4983.5  719.11  4984.0  718.61  4988.8  718.61
  4989.3  719.11  5018.4  720.69  5044.3  720.42  5080.8  721.12  5102.0  722.06
  5107.9  721.65  5159.8  722.64  5222.7  722.81  5283.1  725.20  5348.5  726.60
  5448.7  727.88  5527.1  728.25  5646.9  729.37  5719.4  730.70  5820.2  735.07
  5869.4  738.48  5884.5  738.68  5929.9  740.52  5942.7  740.51  5943.4  740.51
#Mann=8,-1,0
  4708.5    0.12       0  4983.5    0.05       0  4989.3    0.12       0
  5018.4   0.035       0  5222.7    0.07       0  5527.1   0.035       0
  5869.4    0.07       0  5942.7   0.035       0
Bank Sta=4983.5,4989.3
Exp/Cntr=0.3,0.1

Type RM Length L Ch R = 1,1916,484,484,484
BEGIN DESCRIPTION:
Alligator Creek Tributary 68713
END DESCRIPTION:
XS GIS Cut Line= 3
      2259025.00     13830925.01      2259225.00     13830525.00
      2259475.00     13829774.99
#Sta/Elev= 30
  4556.9  733.01  4624.0  730.46  4646.4  729.77  4654.7  730.04  4735.3  727.31
  4906.3  723.32  4924.8  721.97  4937.0  720.92  4959.4  717.78  4982.2  717.03
  4987.2  716.97  4987.7  716.47  4992.6  716.47  4993.0  716.97  5001.3  717.59
  5025.2  718.11  5046.3  719.77  5056.8  720.01  5125.9  719.09  5183.3  718.61
  5267.6  720.60  5309.8  721.11  5425.8  724.61  5541.7  726.94  5552.3  726.80
  5615.5  728.37  5689.3  733.26  5752.5  736.82  5791.3  737.85  5794.7  737.87
#Mann=8,-1,0
  4556.9    0.12       0  4735.3    0.07       0  4924.8    0.12       0
  4982.2    0.07       0  4987.2    0.05       0  4993.0    0.07       0
  5125.9   0.035       0  5791.3    0.07       0
Bank Sta=4987.2,4993
Exp/Cntr=0.3,0.1

Type RM Length L Ch R = 1,1432,305,305,305
BEGIN DESCRIPTION:
Alligator Creek Tributary 68712
END DESCRIPTION:
XS GIS Cut Line= 3
      2259175.02     13831274.97      2259675.00     13830525.00
      2259625.00     13829975.02
#Sta/Elev= 30
  4094.3  743.40  4171.6  740.82  4207.5  739.53  4426.3  730.29  4490.9  728.29
  4504.4  728.62  4519.4  727.21  4671.3  724.20  4729.4  722.95  4787.3  721.88
  4828.9  721.22  4915.3  718.36  4952.1  716.84  4967.1  715.23  4989.7  714.87
  4990.2  714.37  4995.6  714.87  5015.8  715.01  5035.8  715.23  5076.0  717.58
  5114.9  716.65  5156.3  715.11  5213.9  716.81  5276.8  718.31  5313.0  721.70
  5367.2  724.29  5387.3  727.08  5417.4  727.49  5487.7  730.90  5547.9  732.51
#Mann=13,-1,0
  4094.3    0.07       0  4171.6   0.035       0  4207.5    0.07       0
  4671.3    0.12       0  4729.4   0.035       0  4787.3    0.12       0
  4915.3   0.035       0  4989.7   0.035       0  4995.6   0.035       0
  5015.8    0.12       0  5114.9    0.07       0  5213.9   0.035       0
  5313.0    0.07       0
Bank Sta=4989.7,4995.6
Exp/Cntr=0.3,0.1

Type RM Length L Ch R = 1,1127,264,264,264
BEGIN DESCRIPTION:
Alligator Creek Tributary 613029
END DESCRIPTION:
XS GIS Cut Line= 3
      2259897.02     13831106.38      2259943.81     13830412.45
      2259689.53     13829857.21
#Sta/Elev= 30
  4224.2  726.41  4228.6  726.35  4315.8  724.31  4345.9  724.48  4375.9  723.06
  4436.1  722.91  4523.9  721.05  4746.8  717.23  4791.7  715.32  4816.7  714.34
  4847.0  714.99  4882.0  714.57  4897.1  713.78  4919.7  715.82  4925.6  717.11
  4948.6  712.24  5002.7  711.99  5003.1  711.49  5008.6  711.99  5015.9  715.28
  5081.9  718.35  5120.7  722.41  5136.9  722.41  5158.9  724.07  5180.9  723.05
  5195.2  723.33  5257.9  726.08  5384.8  729.31  5392.2  730.13  5530.4  733.24
#Mann=9,-1,0
  4224.2   0.035       0  4228.6    0.12       0  4523.9   0.035       0
  4791.7    0.12       0  4816.7   0.035       0  4882.0    0.12       0
  5002.7    0.05       0  5008.6    0.12       0  5392.2    0.07       0
Bank Sta=5002.7,5008.6
Exp/Cntr=0.3,0.1