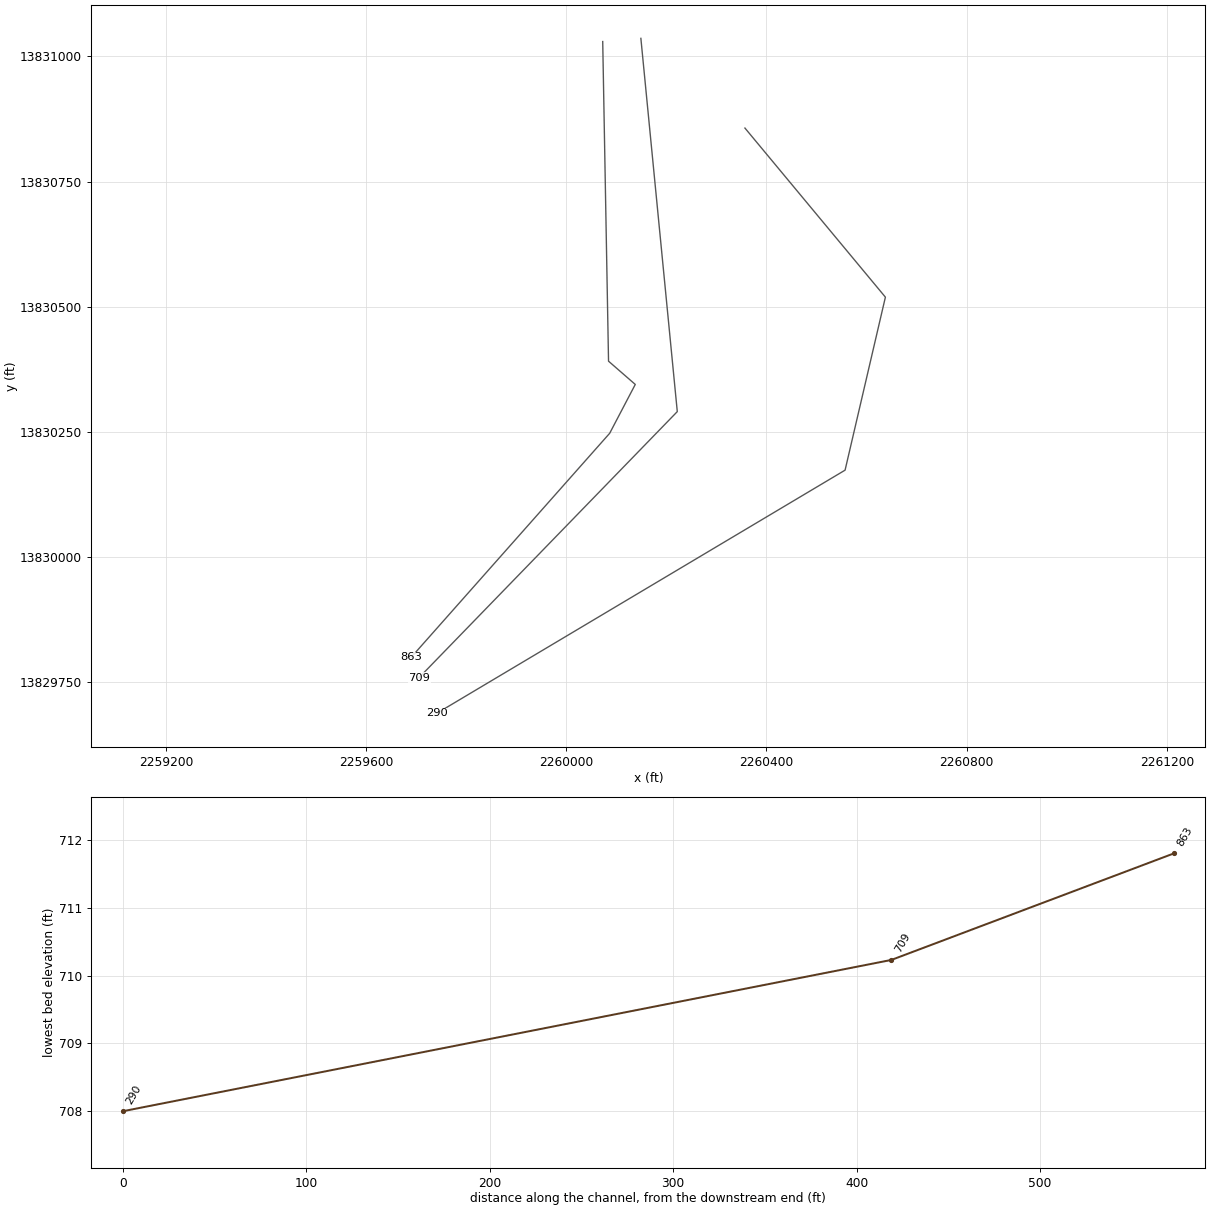
HEC-RAS study Alligator Creek Tributary 6.prj: Alligator Creek Tributary 6 Base Level Engineering

--- Alligator Creek Tributary 6.g01 (geometry) --- (continued)

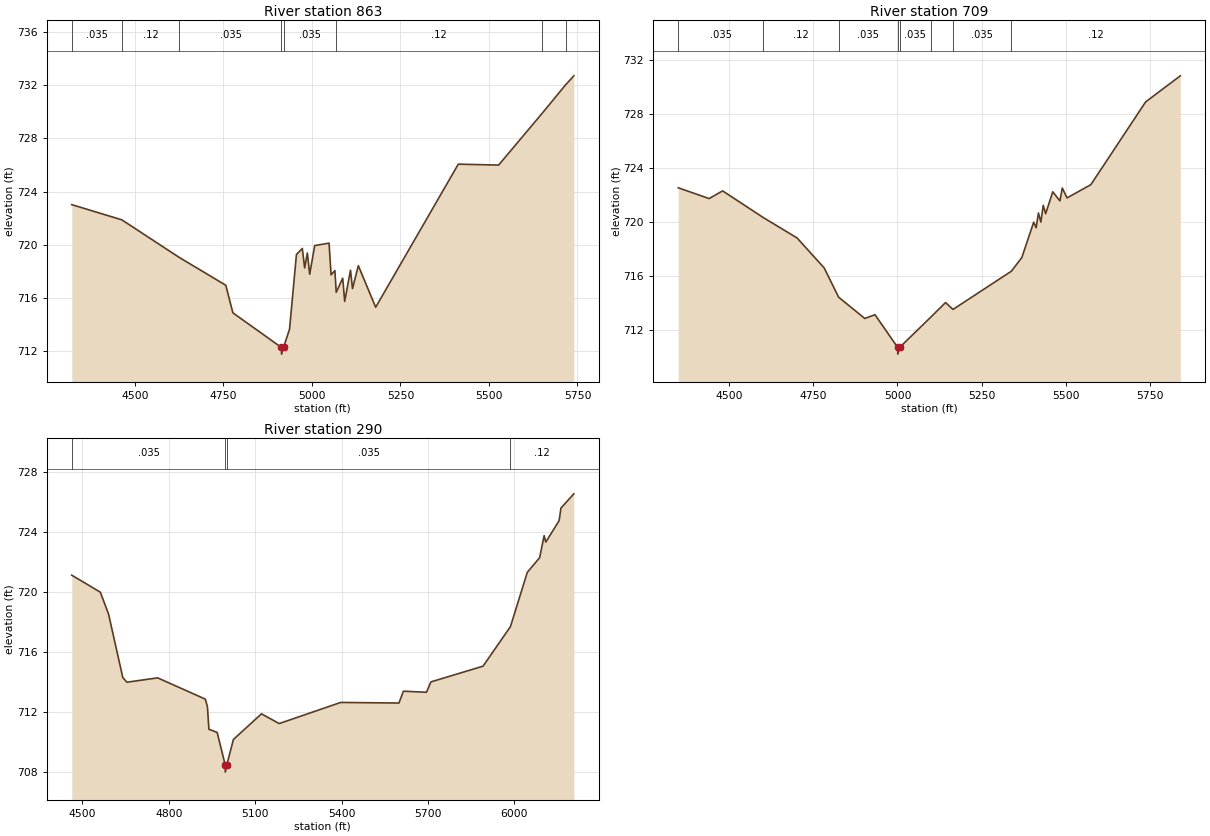
Type RM Length L Ch R = 1,863,154,154,154
BEGIN DESCRIPTION:
Alligator Creek Tributary 6 0.5
END DESCRIPTION:
XS GIS Cut Line= 5
      2260072.90     13831029.82      2260084.52     13830391.06
      2260137.95     13830344.60      2260086.84     13830247.03
      2259690.41     13829799.60
#Sta/Elev= 30
  4322.1  723.02  4463.5  721.88  4626.1  719.05  4757.0  716.97  4777.0  714.90
  4914.1  712.30  4914.5  711.80  4920.0  712.30  4937.0  713.68  4956.5  719.28
  4973.0  719.73  4979.7  718.27  4987.3  719.39  4993.9  717.80  5008.1  719.95
  5048.6  720.13  5054.2  717.75  5065.0  718.07  5068.8  716.44  5087.1  717.50
  5092.7  715.76  5109.1  718.10  5114.8  716.72  5131.2  718.44  5180.2  715.32
  5413.5  726.06  5527.3  725.99  5649.1  729.84  5716.3  732.01  5739.7  732.69
#Mann=8,-1,0
  4322.1   0.035       0  4463.5    0.12       0  4626.1   0.035       0
  4914.1   0.035       0  4920.0   0.035       0  5068.8    0.12       0
  5649.1    0.07       0  5716.3    0.12       0
Bank Sta=4914.1,4920
Exp/Cntr=0.3,0.1

Type RM Length L Ch R = 1,709,419,419,419
BEGIN DESCRIPTION:
Alligator Creek Tributary 613028
END DESCRIPTION:
XS GIS Cut Line= 3
      2260149.14     13831036.20      2260221.91     13830290.30
      2259705.89     13829758.71
#Sta/Elev= 30
  4349.3  722.55  4440.9  721.75  4481.1  722.32  4600.1  720.37  4702.2  718.83
  4782.6  716.61  4825.3  714.45  4903.1  712.87  4933.3  713.15  5000.6  710.73
  5001.1  710.23  5006.6  710.73  5099.4  712.98  5142.8  714.05  5164.9  713.54
  5338.1  716.37  5369.1  717.38  5404.4  720.00  5411.6  719.59  5418.5  720.68
  5425.7  720.01  5432.7  721.25  5439.9  720.63  5461.0  722.25  5482.3  721.58
  5489.3  722.53  5503.4  721.80  5574.1  722.78  5736.7  728.91  5839.6  730.84
#Mann=8,-1,0
  4349.3   0.035       0  4600.1    0.12       0  4825.3   0.035       0
  5000.6   0.035       0  5006.6   0.035       0  5099.4    0.12       0
  5164.9   0.035       0  5338.1    0.12       0
Bank Sta=5000.6,5006.6
Exp/Cntr=0.3,0.1

Type RM Length L Ch R = 1,290,0,0,0
BEGIN DESCRIPTION:
Alligator Creek Tributary 613027
END DESCRIPTION:
XS GIS Cut Line= 4
      2260357.08     13830856.89      2260637.77     13830519.02
      2260557.20     13830173.33      2259741.08     13829687.30
#Sta/Elev= 30
  4462.9  721.14  4562.1  720.01  4590.8  718.54  4640.2  714.31  4654.6  714.00
  4761.3  714.29  4926.8  712.87  4934.2  712.36  4939.3  710.86  4967.9  710.65
  4995.7  708.50  4996.2  708.00  5001.7  708.50  5024.4  710.18  5121.9  711.89
  5183.5  711.24  5397.0  712.65  5599.4  712.61  5615.0  713.40  5694.9  713.33
  5710.5  714.02  5891.5  715.07  5986.8  717.71  6045.3  721.33  6088.2  722.31
  6103.8  723.78  6109.6  723.35  6155.9  724.78  6162.2  725.62  6207.0  726.57
#Mann=4,-1,0
  4462.9   0.035       0  4995.7   0.035       0  5001.7   0.035       0
  5986.8    0.12       0
Bank Sta=4995.7,5001.7
Exp/Cntr=0.3,0.1

Chan Stop Cuts=-1