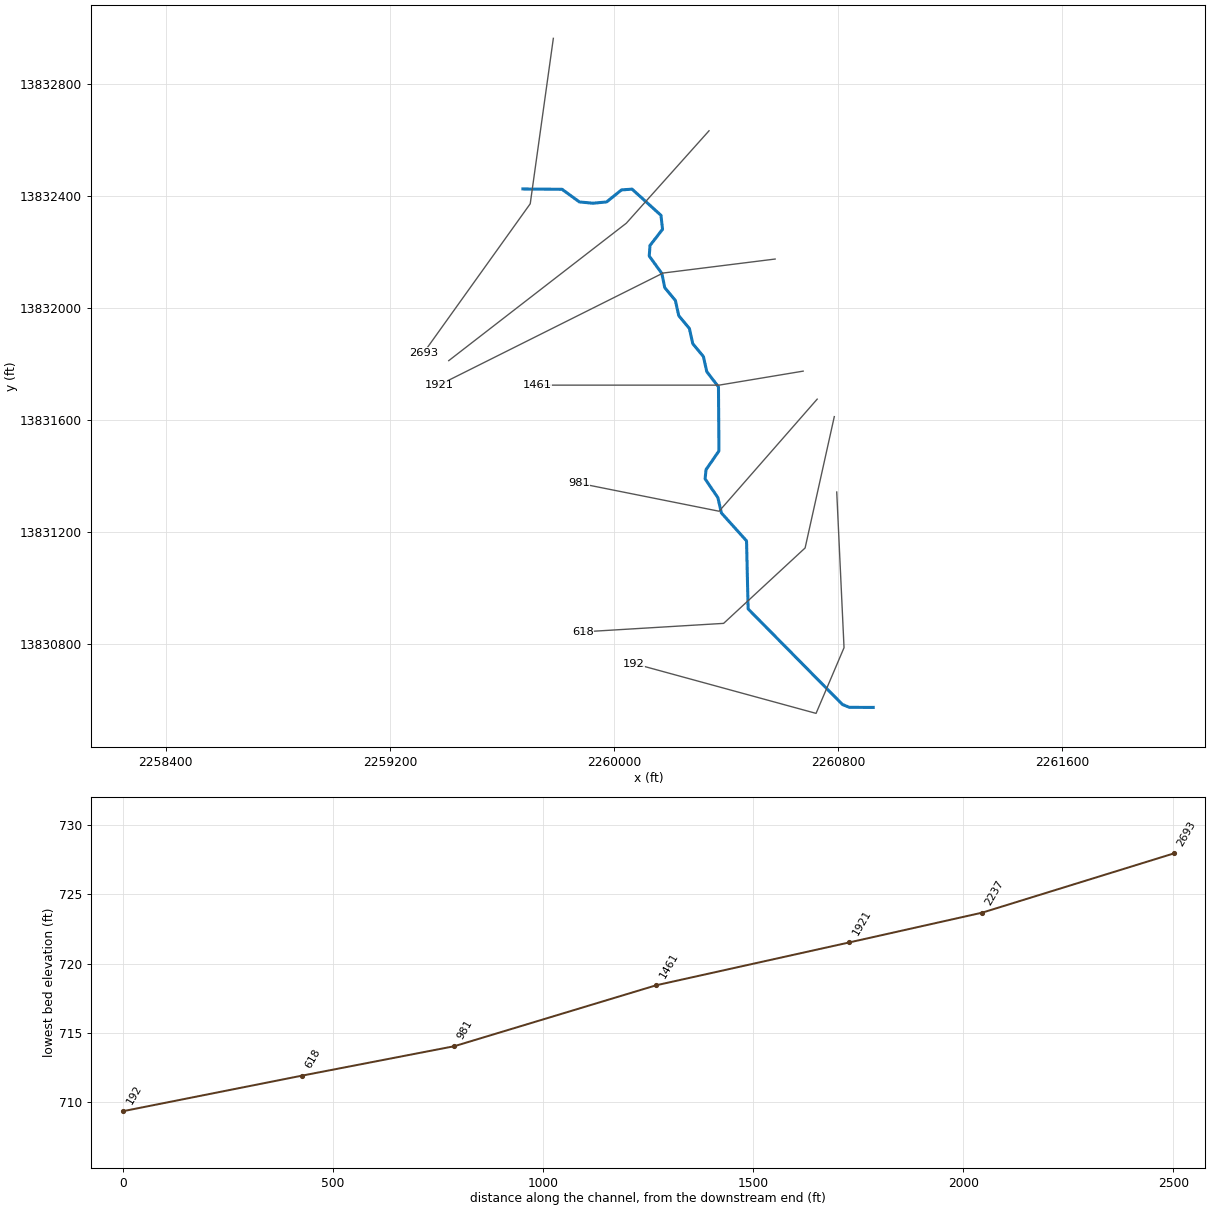
--- Alligator Creek Tributary 8.prj (project) ---

Proj Title=Alligator Creek Tributary 8 Base Level Engineering
Current Plan=p01
Default Exp/Contr=0.3,0.1
English Units
Geom File=g01
Flow File=f01
Plan File=p01
BEGIN DESCRIPTION:
Alligator Creek Tributary 8
END DESCRIPTION:

--- Alligator Creek Tributary 8.p01 (plan) ---

Plan Title=Multiple Run
Short Identifier=Multiple
Geom File=g01
Flow File=f01
Subcritical Flow
K Sum by GR= 0
Std Step Tol= 0.01
Critical Tol= 0.01
Num of Std Step Trials= 20
Max Error Tol= 0.3
Flow Tol Ratio= 0.001
Split Flow NTrial= 30
Split Flow Tol= 0.02
Split Flow Ratio= 0.02
Log Output Level= 0
Friction Slope Method= 1
Unsteady Friction Slope Method= 2
Unsteady Bridges Friction Slope Method= 1
Parabolic Critical Depth
Global Vel Dist=  1 , 1 , 1
Global Log Level= 0
CheckData=True
Encroach Param= -1, 0, 0, 0
BEGIN DESCRIPTION:
Multiple Run
END DESCRIPTION:

--- Alligator Creek Tributary 8.f01 (steady flow) ---

Flow Title=Multiple
Number of Profiles=7
Profile Names=10-year,25-year,50-year,1pct_min,100-year,1pct_plu,500-year
River Rch & RM= Alligator Creek ,Reach-1,2693
    1161    1962    2721    1828    3648    7279    6484
Boundary for River Rch & Prof#=Alligator Creek ,Reach-1,1
Up Type=0
Dn Type=3
Dn Slope=0.005
Boundary for River Rch & Prof#=Alligator Creek ,Reach-1,2
Up Type=0
Dn Type=3
Dn Slope=0.005
Boundary for River Rch & Prof#=Alligator Creek ,Reach-1,3
Up Type=0
Dn Type=3
Dn Slope=0.005
Boundary for River Rch & Prof#=Alligator Creek ,Reach-1,4
Up Type=0
Dn Type=3
Dn Slope=0.005
Boundary for River Rch & Prof#=Alligator Creek ,Reach-1,5
Up Type=0
Dn Type=3
Dn Slope=0.005
Boundary for River Rch & Prof#=Alligator Creek ,Reach-1,6
Up Type=0
Dn Type=3
Dn Slope=0.005
Boundary for River Rch & Prof#=Alligator Creek ,Reach-1,7
Up Type=0
Dn Type=3
Dn Slope=0.005

--- Alligator Creek Tributary 8.g01 (geometry) ---

Geom Title=Existing Conditions

River Reach=Alligator Creek ,Reach-1
Reach XY= 30
      2259675.00     13832425.00      2259814.52     13832423.83
      2259876.60     13832378.70      2259925.00     13832374.19
      2259973.42     13832378.74      2260026.75     13832421.66
      2260064.39     13832424.41      2260167.52     13832331.08
      2260173.19     13832281.13      2260128.40     13832223.28
      2260125.75     13832185.69      2260170.78     13832123.28
      2260181.08     13832072.80      2260218.92     13832027.20
      2260231.08     13831972.80      2260268.92     13831927.20
      2260281.08     13831872.80      2260318.92     13831827.20
      2260331.12     13831772.82      2260372.76     13831719.07
      2260374.46     13831490.21      2260328.37     13831423.26
      2260325.08     13831390.39      2260370.75     13831323.26
      2260383.16     13831268.95      2260472.94     13831169.14
      2260478.54     13830926.46      2260815.18     13830585.43
      2260840.05     13830575.12      2260925.00     13830575.00

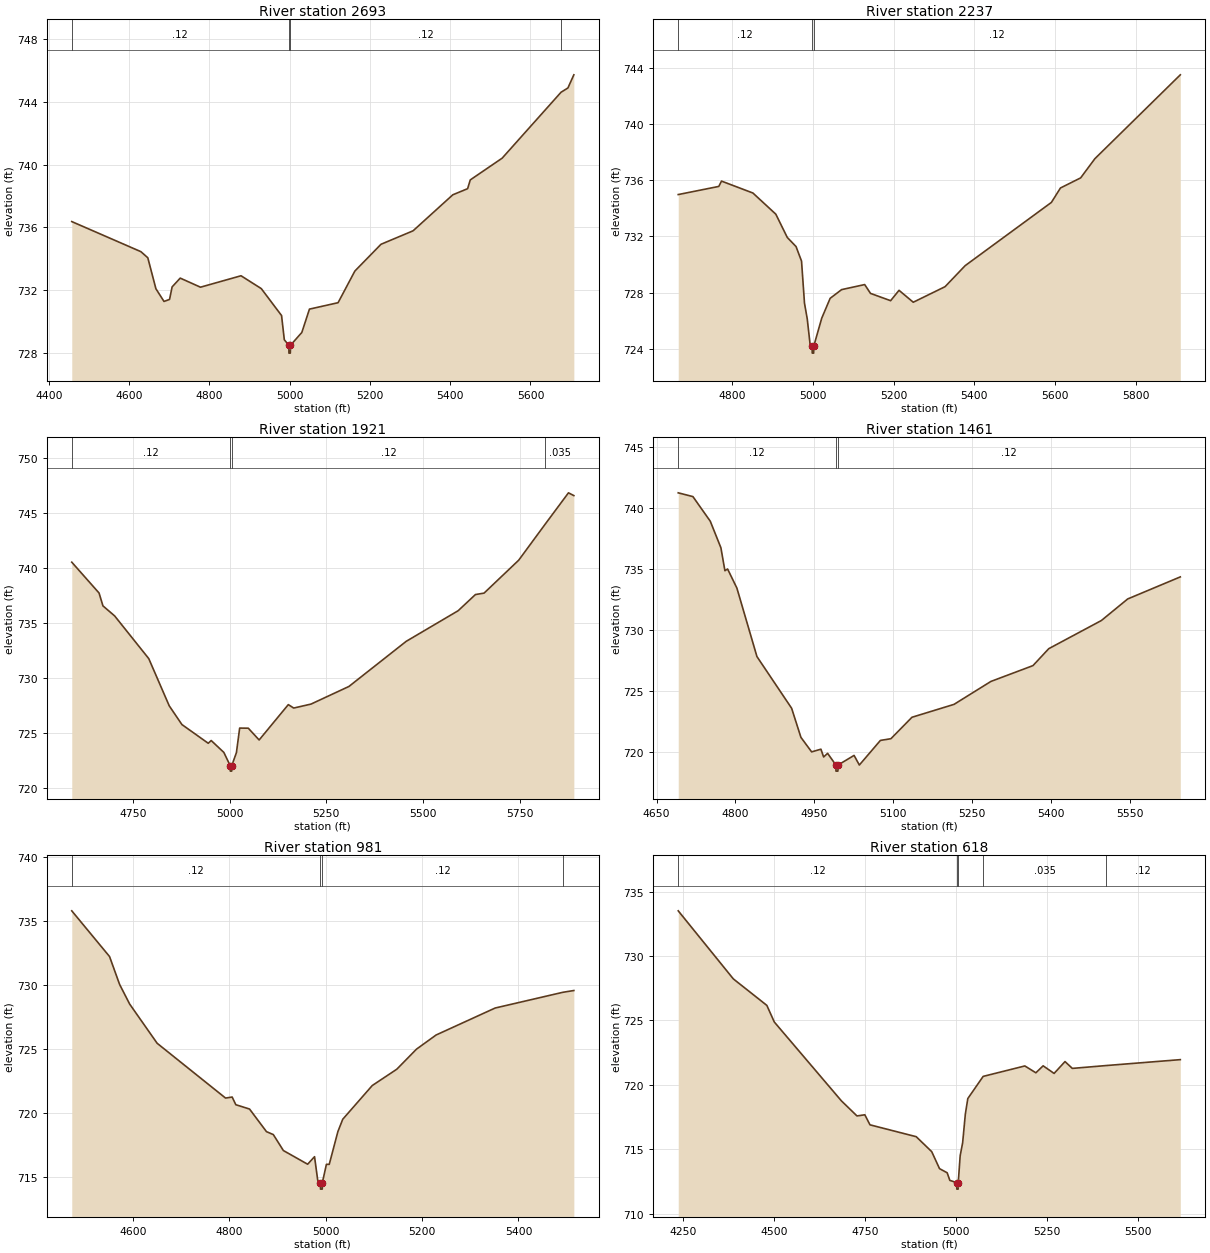
Type RM Length L Ch R = 1,2693,456,456,456
BEGIN DESCRIPTION:
X18039
END DESCRIPTION:
XS GIS Cut Line= 3
      2259783.51     13832962.56      2259701.04     13832372.26
      2259320.11     13831839.82
#Sta/Elev= 30
  4457.3  736.36  4629.4  734.44  4646.7  734.05  4666.9  732.07  4687.1  731.26
  4700.9  731.39  4707.3  732.19  4727.5  732.75  4777.9  732.17  4878.9  732.90
  4929.4  732.08  4979.9  730.36  4986.8  728.81  4998.1  728.46  4998.3  727.96
  5001.8  727.96  5002.1  728.46  5030.4  729.28  5049.4  730.77  5120.7  731.18
  5162.5  733.20  5227.6  734.91  5307.5  735.77  5406.5  738.07  5443.4  738.46
  5450.0  739.02  5529.5  740.41  5676.2  744.62  5693.2  744.89  5708.0  745.73
#Mann=4,-1,0
  4457.3    0.12       0  4998.1    0.05       0  5002.1    0.12       0
  5676.2   0.035       0
Bank Sta=4998.1,5002.1
Exp/Cntr=0.3,0.1

Type RM Length L Ch R = 1,2237,316,316,316
BEGIN DESCRIPTION:
X18038
END DESCRIPTION:
XS GIS Cut Line= 3
      2260339.04     13832632.66      2260043.92     13832302.81
      2259410.25     13831812.37
#Sta/Elev= 30
  4666.5  734.99  4767.0  735.57  4773.7  735.95  4851.5  735.10  4908.3  733.59
  4936.7  731.93  4958.4  731.28  4972.0  730.24  4979.3  727.24  4986.1  726.13
  4993.6  724.20  4998.3  724.18  4998.5  723.68  5002.0  723.68  5002.3  724.18
  5022.0  726.17  5042.9  727.59  5071.3  728.21  5128.4  728.57  5142.9  727.94
  5192.7  727.42  5213.5  728.16  5248.8  727.31  5327.6  728.42  5377.4  729.92
  5591.0  734.43  5613.5  735.46  5663.5  736.18  5698.8  737.55  5910.4  743.53
#Mann=3,-1,0
  4666.5    0.12       0  4998.3    0.05       0  5002.3    0.12       0
Bank Sta=4998.3,5002.3
Exp/Cntr=0.3,0.1

Type RM Length L Ch R = 1,1921,460,460,460
BEGIN DESCRIPTION:
Alligator Creek Tributary 8 3.0
END DESCRIPTION:
XS GIS Cut Line= 3
      2260574.99     13832175.00      2260175.00     13832125.00
      2259375.03     13831725.01
#Sta/Elev= 30
  4592.3  740.51  4662.8  737.71  4672.9  736.54  4703.1  735.63  4791.3  731.75
  4844.2  727.46  4877.0  725.76  4945.0  724.06  4952.6  724.31  4985.3  723.23
  5001.7  722.03  5002.0  721.53  5005.5  721.53  5005.8  722.03  5017.8  723.21
  5026.2  725.44  5048.5  725.43  5076.5  724.36  5151.9  727.57  5165.9  727.26
  5210.6  727.62  5308.5  729.22  5456.6  733.32  5590.8  736.10  5635.5  737.57
  5657.8  737.70  5747.3  740.69  5816.1  743.98  5875.9  746.81  5889.8  746.56
#Mann=4,-1,0
  4592.3    0.12       0  5001.7    0.05       0  5005.8    0.12       0
  5816.1   0.035       0
Bank Sta=5001.7,5005.8
Exp/Cntr=0.3,0.1

Type RM Length L Ch R = 1,1461,480,480,480
BEGIN DESCRIPTION:
Alligator Creek Tributary 8 2.0
END DESCRIPTION:
XS GIS Cut Line= 3
      2260675.03     13831775.01      2260375.00     13831725.00
      2259724.97     13831725.00
#Sta/Elev= 30
  4691.3  741.27  4719.2  740.96  4752.2  738.94  4772.4  736.76  4780.0  734.88
  4785.1  735.02  4802.8  733.45  4840.9  727.83  4906.8  723.59  4924.5  721.20
  4944.8  720.01  4962.5  720.23  4967.6  719.59  4975.2  719.89  4990.9  718.93
  4991.1  718.43  4994.7  718.43  4995.0  718.93  5025.5  719.72  5035.5  718.93
  5075.5  720.95  5095.5  721.09  5135.5  722.85  5215.5  723.91  5285.5  725.79
  5365.5  727.09  5395.5  728.48  5495.5  730.79  5545.5  732.56  5645.5  734.37
#Mann=3,-1,0
  4691.3    0.12       0  4990.9    0.05       0  4995.0    0.12       0
Bank Sta=4990.9,4995
Exp/Cntr=0.3,0.1

Type RM Length L Ch R = 1,981,363,363,363
BEGIN DESCRIPTION:
Alligator Creek Tributary 8 1.0
END DESCRIPTION:
XS GIS Cut Line= 3
      2260725.03     13831675.04      2260375.00     13831275.00
      2259874.96     13831375.01
#Sta/Elev= 30
  4473.4  735.82  4551.8  732.24  4572.6  730.06  4593.5  728.52  4650.5  725.45
  4792.4  721.16  4806.1  721.24  4813.7  720.64  4842.2  720.30  4877.3  718.53
  4891.5  718.30  4912.4  717.05  4962.7  715.98  4977.0  716.57  4983.6  714.73
  4989.1  714.53  4989.4  714.03  4993.0  714.03  4993.2  714.53  5001.6  715.97
  5007.5  715.97  5025.4  718.53  5035.5  719.50  5096.7  722.14  5147.7  723.42
  5188.5  724.99  5229.3  726.10  5351.7  728.21  5492.0  729.44  5514.9  729.58
#Mann=4,-1,0
  4473.4    0.12       0  4989.1    0.05       0  4993.2    0.12       0
  5492.0   0.035       0
Bank Sta=4989.1,4993.2
Exp/Cntr=0.3,0.1

Type RM Length L Ch R = 1,618,426,426,426
BEGIN DESCRIPTION:
X18037
END DESCRIPTION:
XS GIS Cut Line= 4
      2260786.11     13831612.68      2260681.94     13831143.96
      2260391.15     13830874.86      2259888.82     13830844.55
#Sta/Elev= 30
  4237.4  733.50  4388.7  728.22  4480.9  726.16  4501.4  724.87  4685.8  718.75
  4728.6  717.58  4750.1  717.67  4764.3  716.89  4891.3  715.97  4933.9  714.81
  4955.4  713.49  4976.4  713.17  4983.7  712.58  5002.7  712.40  5002.9  711.90
  5006.5  711.90  5006.8  712.40  5012.1  714.49  5018.9  715.50  5026.3  717.72
  5033.1  718.93  5075.3  720.65  5189.8  721.46  5220.1  720.93  5240.1  721.47
  5270.2  720.88  5300.2  721.80  5320.3  721.27  5412.8  721.49  5617.0  721.95
#Mann=5,-1,0
  4237.4    0.12       0  5002.7    0.05       0  5006.8    0.12       0
  5075.3   0.035       0  5412.8    0.12       0
Bank Sta=5002.7,5006.8
Exp/Cntr=0.3,0.1

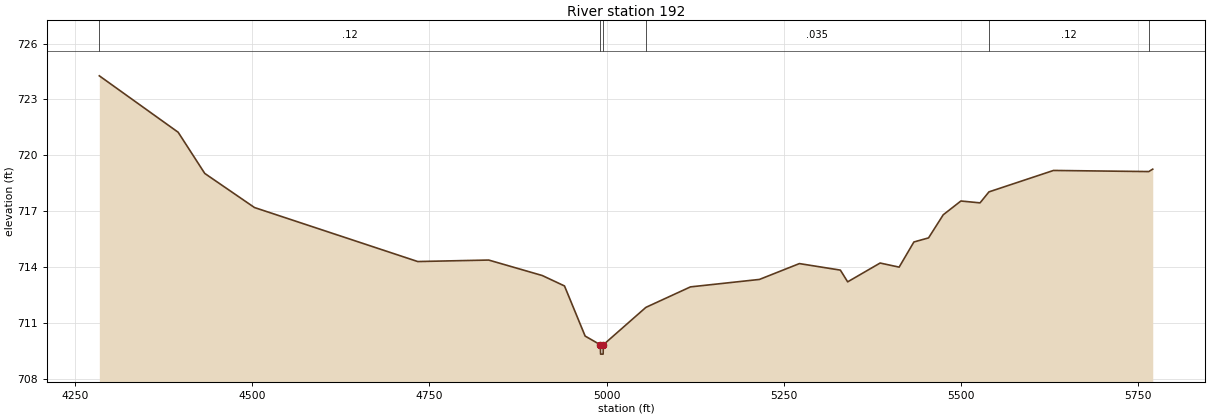
Type RM Length L Ch R = 1,192,0,0,0
BEGIN DESCRIPTION:
X18036
END DESCRIPTION:
XS GIS Cut Line= 4
      2260794.79     13831343.58      2260820.83     13830788.06
      2260721.01     13830553.68      2260069.97     13830731.63
#Sta/Elev= 30
  4284.5  724.27  4395.7  721.24  4433.2  719.03  4503.3  717.20  4733.6  714.30
  4833.7  714.38  4909.2  713.55  4940.6  712.99  4969.7  710.30  4991.2  709.83
  4991.5  709.33  4995.1  709.33  4995.3  709.83  5055.4  711.84  5118.3  712.94
  5215.6  713.34  5271.9  714.19  5329.7  713.84  5340.0  713.21  5385.8  714.22
  5412.6  714.00  5433.4  715.35  5454.1  715.57  5474.8  716.81  5499.7  717.55
  5526.7  717.45  5539.3  718.04  5630.3  719.19  5764.7  719.13  5770.3  719.26
#Mann=6,-1,0
  4284.5    0.12       0  4991.2    0.05       0  4995.3    0.12       0
  5055.4   0.035       0  5539.3    0.12       0  5764.7   0.035       0
Bank Sta=4991.2,4995.3
Exp/Cntr=0.3,0.1

Chan Stop Cuts=-1