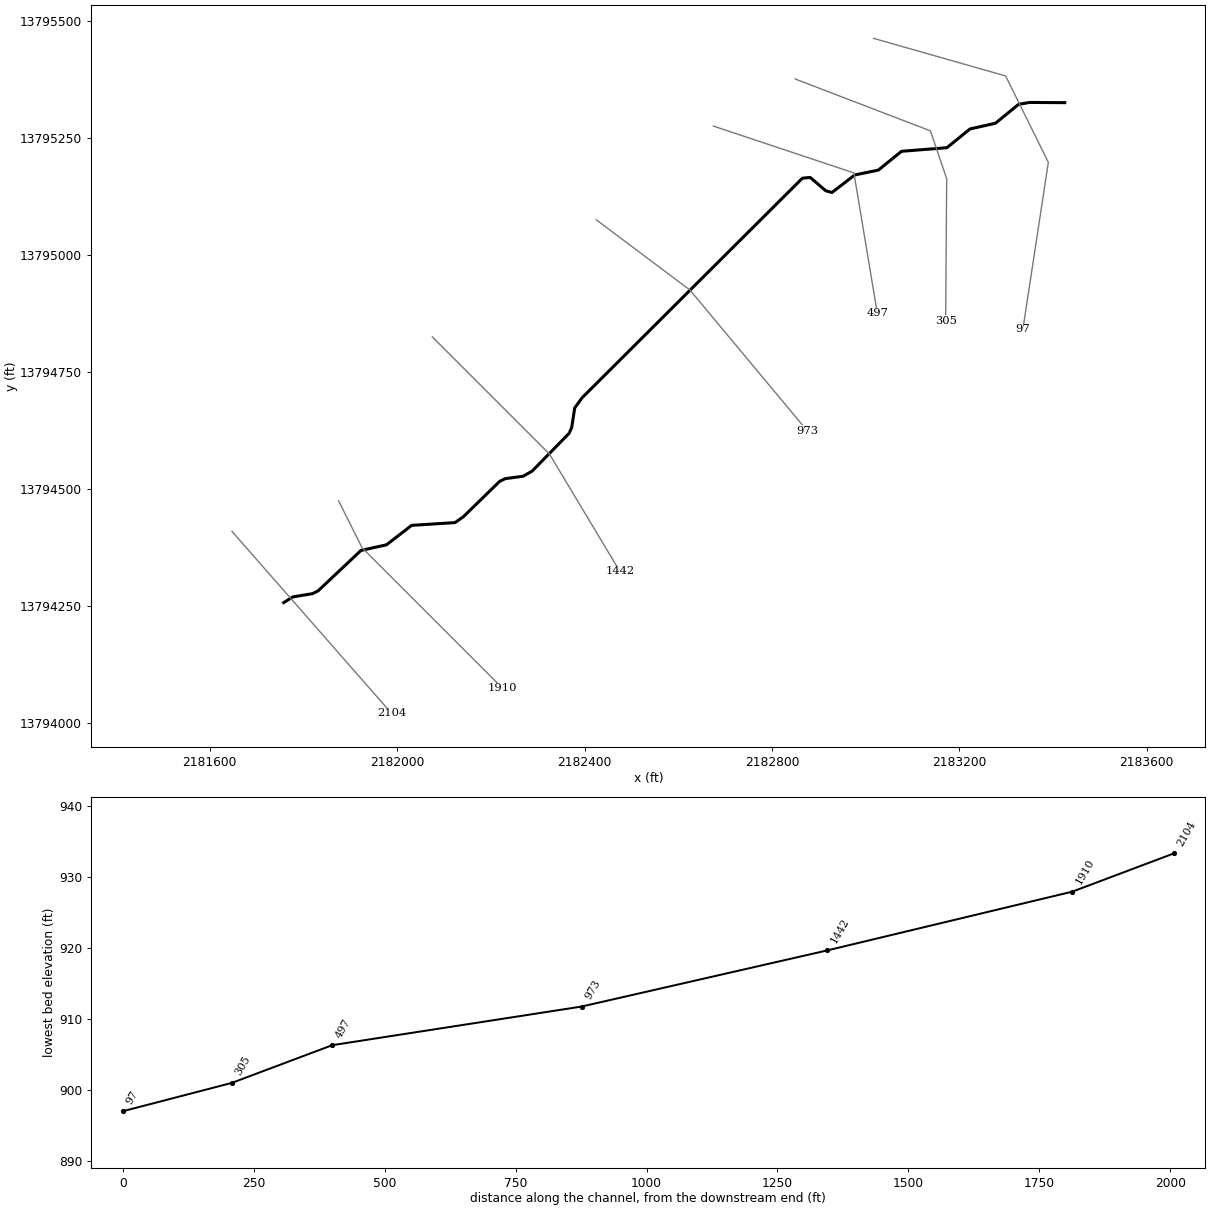
--- Bear Creek Tributary 10.prj (project) ---

Proj Title=Bear Creek Tributary 10 Base Level Engineering
Current Plan=p01
Default Exp/Contr=0.3,0.1
English Units
Geom File=g01
Flow File=f01
Plan File=p01
BEGIN DESCRIPTION:
Bear Creek Tributary 10
END DESCRIPTION:

--- Bear Creek Tributary 10.p01 (plan) ---

Plan Title=Multiple Run
Short Identifier=Multiple
Geom File=g01
Flow File=f01
Subcritical Flow
K Sum by GR= 0
Std Step Tol= 0.01
Critical Tol= 0.01
Num of Std Step Trials= 20
Max Error Tol= 0.3
Flow Tol Ratio= 0.001
Split Flow NTrial= 30
Split Flow Tol= 0.02
Split Flow Ratio= 0.02
Log Output Level= 0
Friction Slope Method= 1
Unsteady Friction Slope Method= 2
Unsteady Bridges Friction Slope Method= 1
Parabolic Critical Depth
Global Vel Dist=  1 , 1 , 1
Global Log Level= 0
CheckData=True
Encroach Param= -1, 0, 0, 0
BEGIN DESCRIPTION:
Multiple Run
END DESCRIPTION:

--- Bear Creek Tributary 10.f01 (steady flow) ---

Flow Title=Multiple
Number of Profiles=7
Profile Names=10-year,25-year,50-year,1pct_min,100-year,1pct_plu,500-year
River Rch & RM= Bear Creek Tribu,Reach-1,2104
     363     574     762     492     982    1959    1609
Boundary for River Rch & Prof#=Bear Creek Tribu,Reach-1,1
Up Type=0
Dn Type=3
Dn Slope=0.005
Boundary for River Rch & Prof#=Bear Creek Tribu,Reach-1,2
Up Type=0
Dn Type=3
Dn Slope=0.005
Boundary for River Rch & Prof#=Bear Creek Tribu,Reach-1,3
Up Type=0
Dn Type=3
Dn Slope=0.005
Boundary for River Rch & Prof#=Bear Creek Tribu,Reach-1,4
Up Type=0
Dn Type=3
Dn Slope=0.005
Boundary for River Rch & Prof#=Bear Creek Tribu,Reach-1,5
Up Type=0
Dn Type=3
Dn Slope=0.005
Boundary for River Rch & Prof#=Bear Creek Tribu,Reach-1,6
Up Type=0
Dn Type=3
Dn Slope=0.005
Boundary for River Rch & Prof#=Bear Creek Tribu,Reach-1,7
Up Type=0
Dn Type=3
Dn Slope=0.005

--- Bear Creek Tributary 10.g01 (geometry) ---

Geom Title=Existing Conditions

River Reach=Bear Creek Tribu,Reach-1
Reach XY= 30
      2181757.78     13794257.78      2181777.10     13794269.91
      2181819.22     13794276.88      2181831.18     13794282.84
      2181922.71     13794369.16      2181977.17     13794381.14
      2182030.97     13794422.67      2182123.50     13794428.62
      2182141.74     13794441.49      2182218.96     13794516.82
      2182231.06     13794522.46      2182268.96     13794527.53
      2182288.24     13794538.62      2182366.85     13794618.93
      2182372.47     13794631.04      2182378.98     13794673.35
      2182394.79     13794695.09      2182865.00     13795163.76
      2182881.66     13795165.40      2182914.95     13795136.84
      2182928.23     13795133.25      2182976.63     13795170.59
      2183027.17     13795181.09      2183076.58     13795221.17
      2183173.42     13795228.83      2183222.82     13795268.89
      2183277.19     13795281.09      2183326.50     13795321.37
      2183349.80     13795325.48      2183425.00     13795325.00

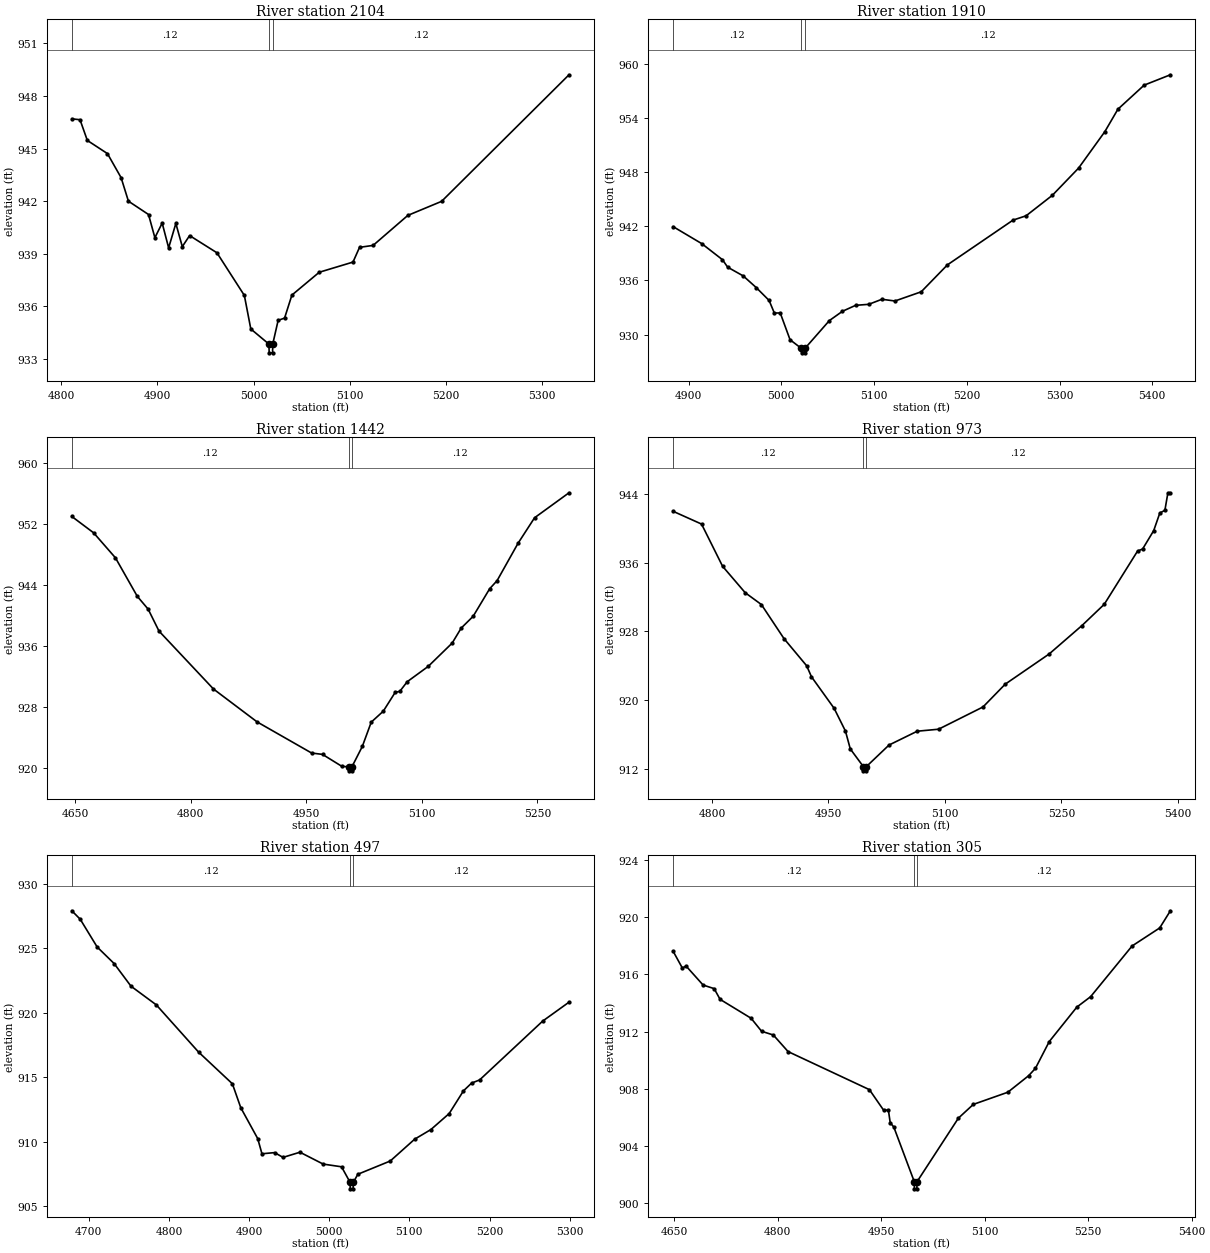
Type RM Length L Ch R = 1,2104,194,194,194
BEGIN DESCRIPTION:
X18117
END DESCRIPTION:
XS GIS Cut Line= 3
      2181647.38     13794409.80      2181771.08     13794268.74
      2181988.09     13794021.35
#Sta/Elev= 30
  4811.2  946.69  4819.7  946.64  4827.3  945.46  4848.2  944.71  4862.4  943.34
  4870.0  942.00  4890.9  941.24  4897.5  939.92  4905.1  940.75  4911.8  939.34
  4919.3  940.73  4926.0  939.41  4933.6  940.04  4962.0  939.06  4990.5  936.63
  4997.2  934.72  5016.0  933.86  5016.3  933.36  5019.8  933.36  5020.0  933.86
  5025.6  935.21  5032.3  935.34  5039.9  936.65  5068.3  937.95  5103.4  938.53
  5110.2  939.37  5124.3  939.48  5160.4  941.19  5195.5  941.99  5327.9  949.20
#Mann=3,-1,0
  4811.2    0.12       0  5016.0    0.05       0  5020.0    0.12       0
Bank Sta=5016,5020
Exp/Cntr=0.3,0.1

Type RM Length L Ch R = 1,1910,468,468,468
BEGIN DESCRIPTION:
Bear Creek Tributary 10 4.0
END DESCRIPTION:
XS GIS Cut Line= 3
      2181874.99     13794475.02      2181925.00     13794375.00
      2182225.01     13794074.99
#Sta/Elev= 30
  4883.4  941.96  4914.2  940.08  4936.5  938.30  4942.1  937.47  4958.9  936.50
  4972.9  935.21  4986.8  933.78  4992.4  932.39  4998.8  932.39  5009.4  929.42
  5021.5  928.47  5021.8  927.97  5025.3  927.97  5025.5  928.47  5051.8  931.55
  5065.9  932.58  5080.1  933.24  5094.2  933.35  5108.4  933.91  5122.5  933.72
  5150.8  934.74  5179.1  937.73  5249.8  942.69  5263.9  943.17  5292.2  945.44
  5320.5  948.46  5348.8  952.50  5362.9  954.99  5391.2  957.66  5419.5  958.81
#Mann=3,-1,0
  4883.4    0.12       0  5021.5    0.05       0  5025.5    0.12       0
Bank Sta=5021.5,5025.5
Exp/Cntr=0.3,0.1

Type RM Length L Ch R = 1,1442,469,469,469
BEGIN DESCRIPTION:
Bear Creek Tributary 10 3.0
END DESCRIPTION:
XS GIS Cut Line= 3
      2182075.00     13794825.00      2182325.00     13794575.00
      2182475.00     13794325.00
#Sta/Elev= 30
  4646.0  952.96  4674.3  950.82  4702.6  947.55  4730.9  942.52  4745.0  940.84
  4759.1  937.97  4829.8  930.39  4886.4  926.09  4957.1  922.02  4971.3  921.84
  4996.0  920.30  5005.3  920.19  5005.6  919.69  5009.1  919.69  5009.3  920.19
  5022.9  922.88  5034.5  926.06  5050.1  927.49  5065.6  929.96  5071.5  930.08
  5081.2  931.35  5108.4  933.35  5139.5  936.40  5151.2  938.36  5166.7  939.90
  5188.1  943.50  5197.8  944.57  5225.0  949.46  5246.4  952.79  5291.1  956.06
#Mann=3,-1,0
  4646.0    0.12       0  5005.3    0.05       0  5009.3    0.12       0
Bank Sta=5005.3,5009.3
Exp/Cntr=0.3,0.1

Type RM Length L Ch R = 1,973,476,476,476
BEGIN DESCRIPTION:
Bear Creek Tributary 10 2.0
END DESCRIPTION:
XS GIS Cut Line= 3
      2182424.99     13795075.01      2182625.00     13794925.00
      2182874.98     13794625.02
#Sta/Elev= 30
  4750.0  941.96  4786.5  940.48  4813.6  935.57  4842.7  932.50  4863.6  931.12
  4892.7  927.16  4921.9  924.00  4928.1  922.72  4957.3  919.05  4971.9  916.40
  4978.1  914.33  4994.9  912.28  4995.1  911.78  4998.6  911.78  4998.9  912.28
  5028.0  914.78  5064.4  916.39  5091.8  916.62  5149.1  919.21  5177.7  921.86
  5234.3  925.37  5276.6  928.68  5305.3  931.15  5348.2  937.34  5354.7  937.58
  5369.0  939.72  5376.9  941.77  5383.4  942.08  5387.3  944.12  5390.5  944.12
#Mann=3,-1,0
  4750.0    0.12       0  4994.9    0.05       0  4998.9    0.12       0
Bank Sta=4994.9,4998.9
Exp/Cntr=0.3,0.1

Type RM Length L Ch R = 1,497,192,192,192
BEGIN DESCRIPTION:
Bear Creek Tributary 10 1.0
END DESCRIPTION:
XS GIS Cut Line= 3
      2182675.02     13795274.99      2182975.00     13795175.00
      2183024.99     13794875.05
#Sta/Elev= 30
  4678.9  927.91  4689.4  927.25  4710.5  925.10  4731.6  923.82  4752.7  922.06
  4784.3  920.61  4837.0  916.95  4879.2  914.49  4889.7  912.63  4910.8  910.24
  4916.1  909.06  4931.9  909.15  4942.4  908.78  4963.5  909.18  4992.5  908.26
  5015.4  908.05  5026.1  906.84  5026.3  906.34  5029.8  906.34  5030.1  906.84
  5035.7  907.47  5076.2  908.50  5106.6  910.19  5126.9  910.94  5149.7  912.18
  5167.5  913.94  5177.6  914.54  5187.7  914.79  5266.3  919.35  5299.2  920.82
#Mann=3,-1,0
  4678.9    0.12       0  5026.1    0.05       0  5030.1    0.12       0
Bank Sta=5026.1,5030.1
Exp/Cntr=0.3,0.1

Type RM Length L Ch R = 1,305,208,208,208
BEGIN DESCRIPTION:
X18116
END DESCRIPTION:
XS GIS Cut Line= 4
      2182849.66     13795375.51      2183138.26     13795264.84
      2183172.99     13795162.84      2183170.82     13794859.49
#Sta/Elev= 30
  4648.9  917.61  4662.1  916.45  4667.5  916.59  4692.2  915.26  4708.2  915.01
  4716.8  914.26  4761.7  912.94  4776.9  912.03  4793.9  911.77  4815.3  910.61
  4933.1  907.95  4953.6  906.52  4960.6  906.52  4963.2  905.65  4968.5  905.33
  4998.1  901.52  4998.3  901.02  5001.8  901.02  5002.1  901.52  5062.0  905.96
  5083.6  906.92  5133.6  907.77  5163.6  908.92  5173.6  909.44  5193.6  911.31
  5233.6  913.72  5253.6  914.45  5313.6  917.99  5353.6  919.25  5369.1  920.45
#Mann=3,-1,0
  4648.9    0.12       0  4998.1    0.05       0  5002.1    0.12       0
Bank Sta=4998.1,5002.1
Exp/Cntr=0.3,0.1

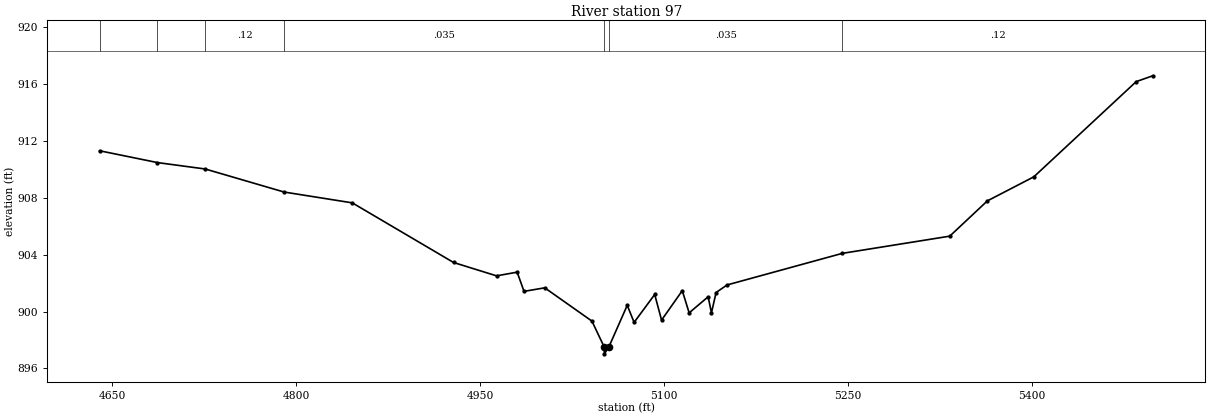
Type RM Length L Ch R = 1,97,0,0,0
BEGIN DESCRIPTION:
X18115
END DESCRIPTION:
XS GIS Cut Line= 4
      2183016.73     13795462.32      2183298.86     13795382.03
      2183390.00     13795197.56      2183335.75     13794841.66
#Sta/Elev= 30
  4639.8  911.30  4687.0  910.47  4725.9  910.02  4790.3  908.40  4845.9  907.64
  4928.5  903.45  4963.6  902.51  4980.4  902.77  4986.0  901.42  5002.9  901.67
  5041.4  899.33  5051.3  897.53  5051.6  897.03  5055.3  897.53  5070.2  900.44
  5075.8  899.24  5092.6  901.20  5098.2  899.40  5115.1  901.47  5120.7  899.91
  5136.2  901.04  5138.9  899.91  5142.7  901.34  5151.6  901.87  5245.6  904.09
  5333.3  905.30  5364.0  907.78  5401.9  909.47  5485.4  916.16  5498.9  916.57
#Mann=7,-1,0
  4639.8    0.12       0  4687.0   0.035       0  4725.9    0.12       0
  4790.3   0.035       0  5051.3   0.035       0  5055.3   0.035       0
  5245.6    0.12       0
Bank Sta=5051.3,5055.3
Exp/Cntr=0.3,0.1

Chan Stop Cuts=-1