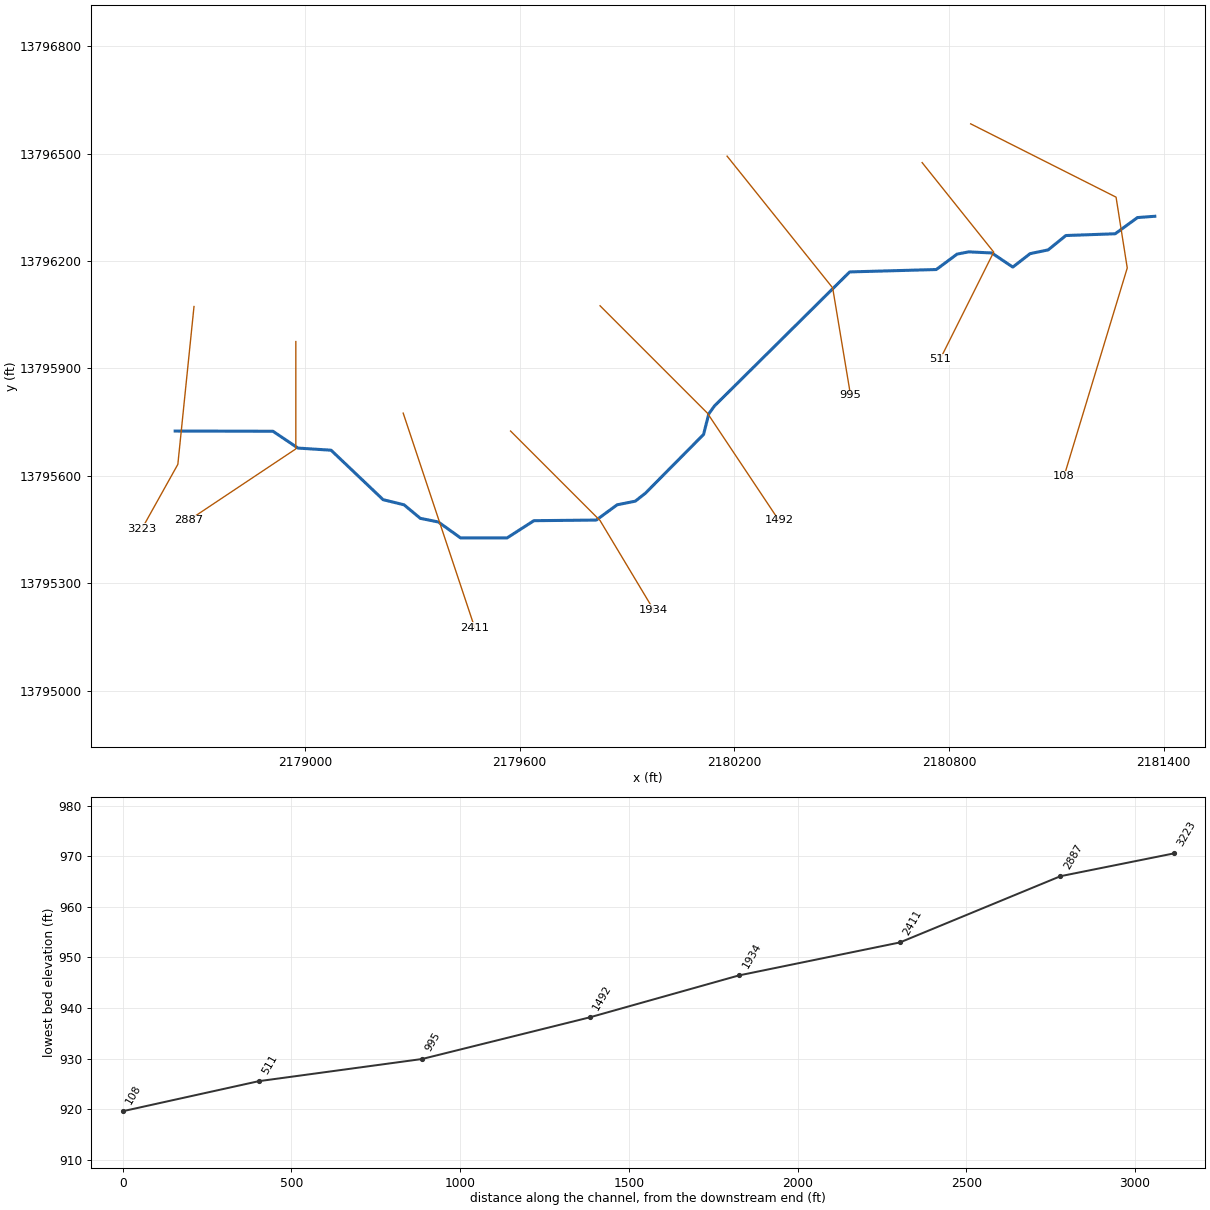
--- Bear Creek Tributary 11.prj (project) ---

Proj Title=Bear Creek Tributary 11 Base Level Engineering
Current Plan=p01
Default Exp/Contr=0.3,0.1
English Units
Geom File=g01
Flow File=f01
Plan File=p01
BEGIN DESCRIPTION:
Bear Creek Tributary 11
END DESCRIPTION:

--- Bear Creek Tributary 11.p01 (plan) ---

Plan Title=Multiple Run
Short Identifier=Multiple
Geom File=g01
Flow File=f01
Subcritical Flow
K Sum by GR= 0
Std Step Tol= 0.01
Critical Tol= 0.01
Num of Std Step Trials= 20
Max Error Tol= 0.3
Flow Tol Ratio= 0.001
Split Flow NTrial= 30
Split Flow Tol= 0.02
Split Flow Ratio= 0.02
Log Output Level= 0
Friction Slope Method= 1
Unsteady Friction Slope Method= 2
Unsteady Bridges Friction Slope Method= 1
Parabolic Critical Depth
Global Vel Dist=  1 , 1 , 1
Global Log Level= 0
CheckData=True
Encroach Param= -1, 0, 0, 0
BEGIN DESCRIPTION:
Multiple Run
END DESCRIPTION:

--- Bear Creek Tributary 11.f01 (steady flow) ---

Flow Title=Multiple
Number of Profiles=7
Profile Names=10-year,25-year,50-year,1pct_min,100-year,1pct_plu,500-year
River Rch & RM= Bear Creek Tribu,Reach-1,3223
     474     763    1024     668    1332    2657    2227
Boundary for River Rch & Prof#=Bear Creek Tribu,Reach-1,1
Up Type=0
Dn Type=3
Dn Slope=0.005
Boundary for River Rch & Prof#=Bear Creek Tribu,Reach-1,2
Up Type=0
Dn Type=3
Dn Slope=0.005
Boundary for River Rch & Prof#=Bear Creek Tribu,Reach-1,3
Up Type=0
Dn Type=3
Dn Slope=0.005
Boundary for River Rch & Prof#=Bear Creek Tribu,Reach-1,4
Up Type=0
Dn Type=3
Dn Slope=0.005
Boundary for River Rch & Prof#=Bear Creek Tribu,Reach-1,5
Up Type=0
Dn Type=3
Dn Slope=0.005
Boundary for River Rch & Prof#=Bear Creek Tribu,Reach-1,6
Up Type=0
Dn Type=3
Dn Slope=0.005
Boundary for River Rch & Prof#=Bear Creek Tribu,Reach-1,7
Up Type=0
Dn Type=3
Dn Slope=0.005

--- Bear Creek Tributary 11.g01 (geometry) ---

Geom Title=Existing Conditions

River Reach=Bear Creek Tribu,Reach-1
Reach XY= 30
      2178637.91     13795725.00      2178911.08     13795724.32
      2178980.98     13795677.36      2179073.50     13795671.39
      2179218.94     13795533.14      2179277.19     13795518.90
      2179322.80     13795481.08      2179373.26     13795470.81
      2179435.50     13795426.19      2179565.33     13795426.37
      2179640.22     13795474.48      2179814.50     13795476.20
      2179872.83     13795518.86      2179923.37     13795528.94
      2179951.82     13795551.29      2180114.22     13795715.32
      2180128.98     13795773.35      2180144.79     13795795.09
      2180522.55     13796169.54      2180764.50     13796176.22
      2180822.69     13796219.31      2180854.96     13796225.58
      2180919.51     13796222.51      2180978.32     13796183.05
      2181026.64     13796220.58      2181077.17     13796231.09
      2181126.56     13796271.24      2181264.53     13796276.13
      2181326.51     13796321.35      2181375.00     13796325.00

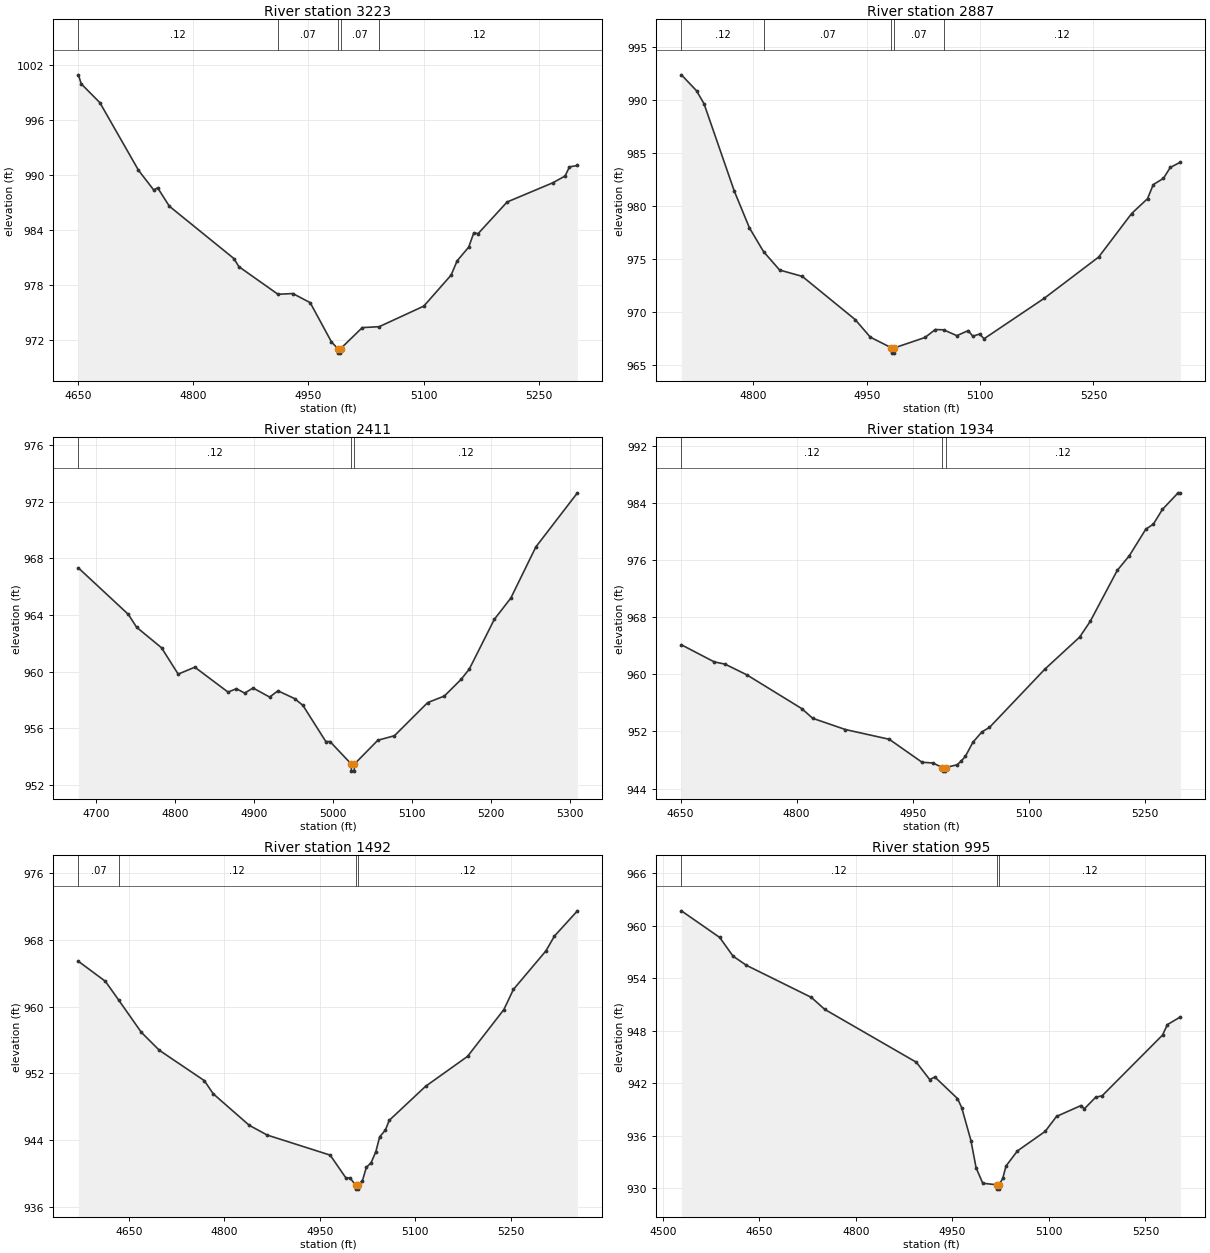
Type RM Length L Ch R = 1,3223,336,336,336
BEGIN DESCRIPTION:
X18119
END DESCRIPTION:
XS GIS Cut Line= 3
      2178690.48     13796072.89      2178645.34     13795631.90
      2178544.66     13795451.37
#Sta/Elev= 30
  4650.3 1000.92  4654.1  999.93  4678.3  997.89  4728.6  990.53  4748.5  988.37
  4753.5  988.62  4768.8  986.61  4852.9  980.91  4859.3  980.03  4910.3  977.02
  4929.6  977.10  4952.2  976.11  4979.9  971.84  4988.0  971.11  4988.2  970.61
  4991.7  970.61  4992.0  971.11  5020.1  973.39  5042.1  973.49  5100.2  975.73
  5135.8  979.11  5143.6  980.66  5158.7  982.16  5165.3  983.71  5171.0  983.63
  5208.7  987.07  5268.2  989.16  5284.2  989.90  5289.9  990.89  5300.3  991.05
#Mann=5,-1,0
  4650.3    0.12       0  4910.3    0.07       0  4988.0    0.05       0
  4992.0    0.07       0  5042.1    0.12       0
Bank Sta=4988,4992
Exp/Cntr=0.3,0.1

Type RM Length L Ch R = 1,2887,476,476,476
BEGIN DESCRIPTION:
Bear Creek Tributary 11 6.0
END DESCRIPTION:
XS GIS Cut Line= 3
      2178975.00     13795974.96      2178975.00     13795675.00
      2178675.01     13795475.01
#Sta/Elev= 30
  4704.7  992.39  4724.7  990.89  4734.7  989.65  4774.7  981.41  4794.7  977.94
  4813.4  975.69  4834.7  973.95  4864.7  973.35  4934.7  969.27  4954.7  967.61
  4982.7  966.60  4982.9  966.10  4986.4  966.10  4986.7  966.60  5027.2  967.58
  5040.7  968.33  5051.8  968.30  5069.3  967.75  5084.3  968.23  5090.3  967.70
  5099.3  967.90  5105.3  967.46  5184.9  971.28  5257.0  975.18  5300.6  979.29
  5321.6  980.69  5329.2  982.02  5342.7  982.61  5351.7  983.64  5365.2  984.14
#Mann=5,-1,0
  4704.7    0.12       0  4813.4    0.07       0  4982.7    0.05       0
  4986.7    0.07       0  5051.8    0.12       0
Bank Sta=4982.7,4986.7
Exp/Cntr=0.3,0.1

Type RM Length L Ch R = 1,2411,477,477,477
BEGIN DESCRIPTION:
Bear Creek Tributary 11 5.0
END DESCRIPTION:
XS GIS Cut Line= 3
      2179275.00     13795775.01      2179375.00     13795475.00
      2179475.01     13795174.97
#Sta/Elev= 30
  4677.4  967.33  4740.7  964.05  4751.2  963.14  4782.8  961.69  4803.9  959.83
  4825.0  960.32  4867.1  958.56  4877.7  958.80  4888.2  958.49  4898.8  958.85
  4919.8  958.21  4930.4  958.65  4951.5  958.10  4962.0  957.62  4991.0  955.07
  4996.3  955.07  5023.3  953.48  5023.5  952.98  5027.0  952.98  5027.3  953.48
  5056.9  955.16  5078.0  955.48  5120.1  957.82  5141.2  958.28  5162.3  959.45
  5172.8  960.18  5204.5  963.69  5225.5  965.20  5257.2  968.81  5309.9  972.63
#Mann=3,-1,0
  4677.4    0.12       0  5023.3    0.05       0  5027.3    0.12       0
Bank Sta=5023.3,5027.3
Exp/Cntr=0.3,0.1

Type RM Length L Ch R = 1,1934,442,442,442
BEGIN DESCRIPTION:
Bear Creek Tributary 11 4.0
END DESCRIPTION:
XS GIS Cut Line= 3
      2179575.03     13795724.97      2179825.00     13795475.00
      2179975.02     13795224.96
#Sta/Elev= 30
  4651.0  964.14  4693.4  961.75  4707.5  961.43  4735.8  959.92  4806.5  955.21
  4820.7  953.85  4863.1  952.27  4919.7  950.91  4962.1  947.69  4976.2  947.59
  4988.4  946.95  4988.6  946.45  4992.1  946.45  4992.4  946.95  5007.4  947.34
  5012.3  947.82  5018.1  948.52  5027.8  950.49  5039.5  951.95  5049.2  952.57
  5121.1  960.76  5165.8  965.22  5179.4  967.41  5214.4  974.56  5230.0  976.61
  5251.3  980.33  5261.1  981.04  5272.7  983.09  5293.1  985.42  5296.1  985.42
#Mann=3,-1,0
  4651.0    0.12       0  4988.4    0.05       0  4992.4    0.12       0
Bank Sta=4988.4,4992.4
Exp/Cntr=0.3,0.1

Type RM Length L Ch R = 1,1492,497,497,497
BEGIN DESCRIPTION:
Bear Creek Tributary 11 3.0
END DESCRIPTION:
XS GIS Cut Line= 3
      2179825.02     13796074.98      2180125.00     13795775.00
      2180325.00     13795475.00
#Sta/Elev= 30
  4570.3  965.42  4612.7  963.03  4633.9  960.76  4669.3  956.92  4697.6  954.77
  4768.3  951.14  4782.4  949.56  4839.0  945.79  4867.3  944.62  4966.3  942.22
  4991.0  939.49  4997.5  939.49  5006.1  938.65  5006.3  938.15  5009.8  938.15
  5010.1  938.65  5017.1  939.18  5023.1  940.75  5030.6  941.31  5038.1  942.63
  5044.1  944.41  5053.1  945.22  5059.1  946.38  5116.2  950.45  5182.3  954.04
  5239.4  959.64  5254.4  962.05  5305.5  966.66  5319.0  968.44  5355.1  971.46
#Mann=4,-1,0
  4570.3    0.07       0  4633.9    0.12       0  5006.1    0.05       0
  5010.1    0.12       0
Bank Sta=5006.1,5010.1
Exp/Cntr=0.3,0.1

Type RM Length L Ch R = 1,995,484,484,484
BEGIN DESCRIPTION:
Bear Creek Tributary 11 2.0
END DESCRIPTION:
XS GIS Cut Line= 3
      2180180.03     13796493.05      2180475.00     13796125.00
      2180525.00     13795825.00
#Sta/Elev= 30
  4528.6  961.70  4588.1  958.66  4608.9  956.52  4629.8  955.47  4730.6  951.81
  4751.4  950.44  4893.8  944.40  4914.6  942.42  4922.6  942.71  4957.8  940.25
  4964.3  939.22  4978.7  935.45  4986.7  932.34  4997.1  930.57  5018.5  930.40
  5018.8  929.90  5022.3  929.90  5022.5  930.40  5028.1  931.12  5033.2  932.54
  5051.0  934.27  5094.0  936.49  5111.8  938.21  5149.8  939.45  5154.9  939.07
  5172.6  940.40  5182.7  940.57  5276.5  947.50  5284.1  948.70  5304.4  949.58
#Mann=3,-1,0
  4528.6    0.12       0  5018.5    0.05       0  5022.5    0.12       0
Bank Sta=5018.5,5022.5
Exp/Cntr=0.3,0.1

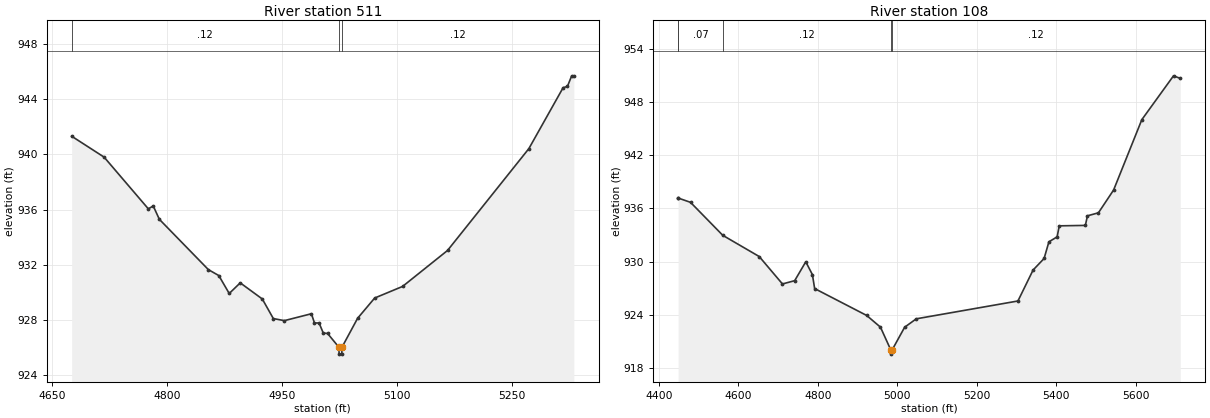
Type RM Length L Ch R = 1,511,403,403,403
BEGIN DESCRIPTION:
Bear Creek Tributary 11 1.0
END DESCRIPTION:
XS GIS Cut Line= 3
      2180725.00     13796475.00      2180925.00     13796225.00
      2180774.99     13795924.97
#Sta/Elev= 30
  4675.6  941.32  4718.0  939.80  4775.7  936.05  4782.1  936.26  4790.1  935.29
  4854.1  931.64  4867.7  931.21  4881.3  929.91  4895.7  930.68  4924.5  929.51
  4938.9  928.09  4953.3  927.94  4988.6  928.44  4992.6  927.77  4998.6  927.77
  5004.1  927.04  5009.7  927.01  5024.5  926.01  5024.8  925.51  5028.3  925.51
  5028.5  926.01  5048.9  928.11  5071.2  929.58  5107.6  930.42  5166.3  933.03
  5272.5  940.42  5317.2  944.84  5322.8  944.93  5328.4  945.70  5331.2  945.70
#Mann=3,-1,0
  4675.6    0.12       0  5024.5    0.05       0  5028.5    0.12       0
Bank Sta=5024.5,5028.5
Exp/Cntr=0.3,0.1

Type RM Length L Ch R = 1,108,0,0,0
BEGIN DESCRIPTION:
X18118
END DESCRIPTION:
XS GIS Cut Line= 4
      2180860.58     13796583.31      2181266.87     13796378.43
      2181298.12     13796180.51      2181121.48     13795598.62
#Sta/Elev= 30
  4448.8  937.15  4449.2  937.15  4480.0  936.67  4561.2  932.95  4652.9  930.56
  4711.3  927.47  4742.1  927.84  4770.0  929.97  4786.7  928.52  4792.3  926.95
  4923.2  923.92  4957.9  922.60  4983.6  920.06  4983.9  919.56  4987.6  920.06
  5018.7  922.59  5048.0  923.54  5303.8  925.55  5341.9  929.04  5369.6  930.34
  5381.7  932.22  5402.4  932.78  5407.7  934.02  5473.4  934.07  5478.7  935.15
  5506.3  935.49  5544.5  938.06  5615.5  945.99  5695.2  950.93  5712.3  950.64
#Mann=5,-1,0
  4448.8    0.12       0  4449.2    0.07       0  4561.2    0.12       0
  4983.6    0.05       0  4987.6    0.12       0
Bank Sta=4983.6,4987.6
Exp/Cntr=0.3,0.1

Chan Stop Cuts=-1