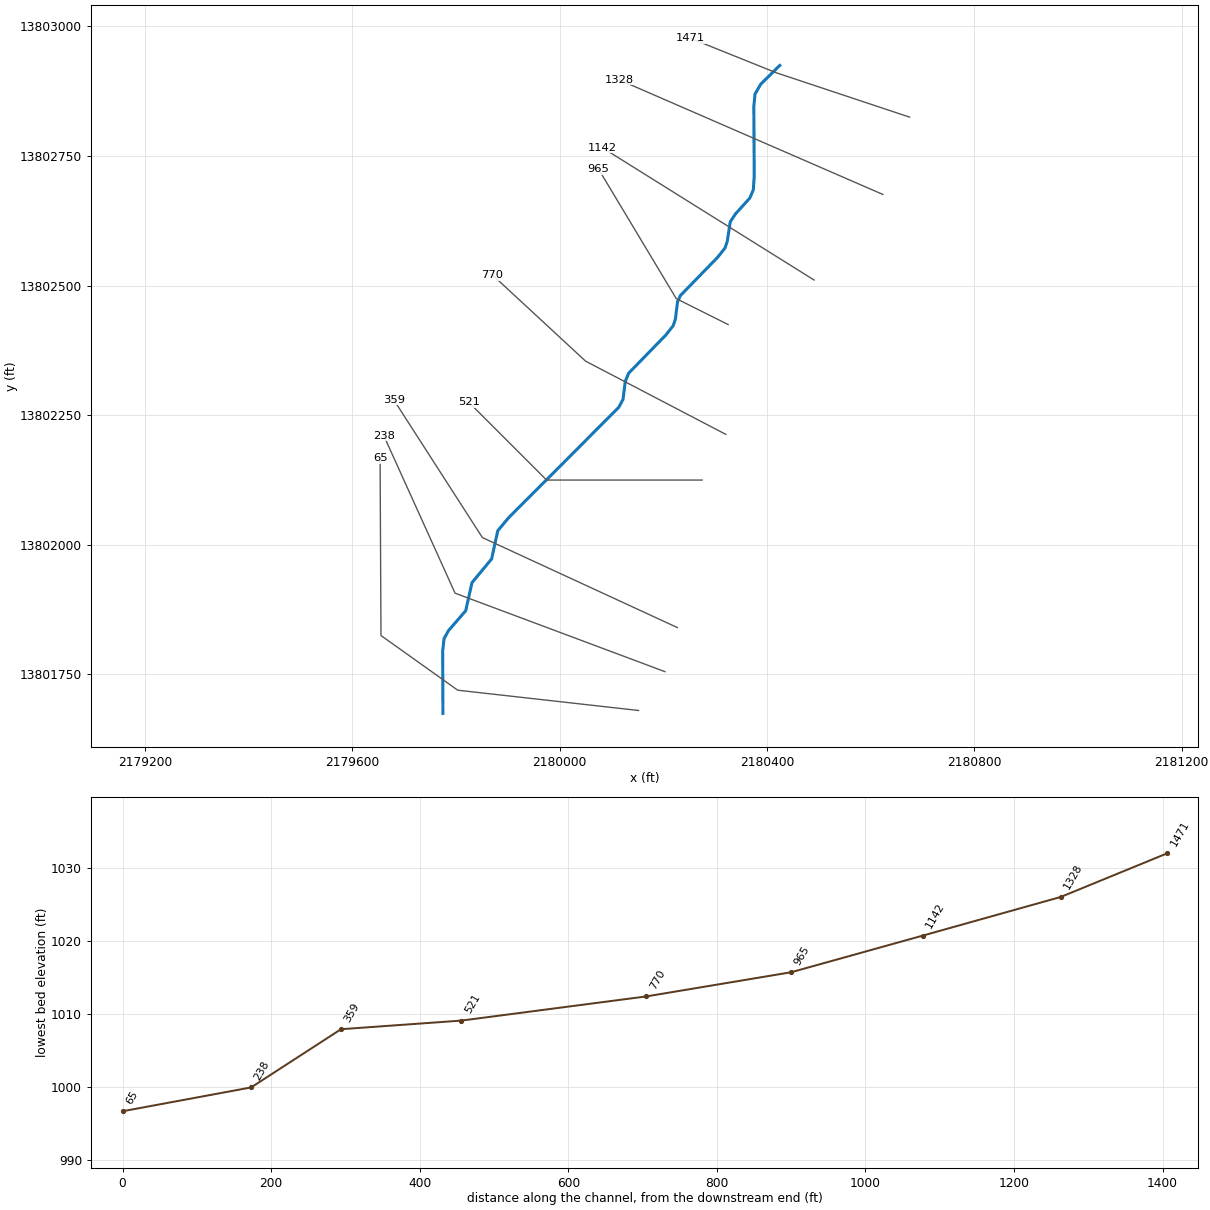
--- Bear Creek Tributary 13.prj (project) ---

Proj Title=Bear Creek Tributary 13 Base Level Engineering
Current Plan=p01
Default Exp/Contr=0.3,0.1
English Units
Geom File=g01
Flow File=f01
Plan File=p01
BEGIN DESCRIPTION:
Bear Creek Tributary 13
END DESCRIPTION:

--- Bear Creek Tributary 13.p01 (plan) ---

Plan Title=Multiple Run
Short Identifier=Multiple
Geom File=g01
Flow File=f01
Subcritical Flow
K Sum by GR= 0
Std Step Tol= 0.01
Critical Tol= 0.01
Num of Std Step Trials= 20
Max Error Tol= 0.3
Flow Tol Ratio= 0.001
Split Flow NTrial= 30
Split Flow Tol= 0.02
Split Flow Ratio= 0.02
Log Output Level= 0
Friction Slope Method= 1
Unsteady Friction Slope Method= 2
Unsteady Bridges Friction Slope Method= 1
Parabolic Critical Depth
Global Vel Dist=  1 , 1 , 1
Global Log Level= 0
CheckData=True
Encroach Param= -1, 0, 0, 0
BEGIN DESCRIPTION:
Multiple Run
END DESCRIPTION:

--- Bear Creek Tributary 13.f01 (steady flow) ---

Flow Title=Multiple
Number of Profiles=7
Profile Names=10-year,25-year,50-year,1pct_min,100-year,1pct_plu,500-year
River Rch & RM= Bear Creek Tribu,Reach-1,1471
     329     519     688     444     886    1769    1451
River Rch & RM= Bear Creek Tribu,Reach-1,65
     901    1509    2080    1389    2771    5529    4868
Boundary for River Rch & Prof#=Bear Creek Tribu,Reach-1,1
Up Type=0
Dn Type=3
Dn Slope=0.005
Boundary for River Rch & Prof#=Bear Creek Tribu,Reach-1,2
Up Type=0
Dn Type=3
Dn Slope=0.005
Boundary for River Rch & Prof#=Bear Creek Tribu,Reach-1,3
Up Type=0
Dn Type=3
Dn Slope=0.005
Boundary for River Rch & Prof#=Bear Creek Tribu,Reach-1,4
Up Type=0
Dn Type=3
Dn Slope=0.005
Boundary for River Rch & Prof#=Bear Creek Tribu,Reach-1,5
Up Type=0
Dn Type=3
Dn Slope=0.005
Boundary for River Rch & Prof#=Bear Creek Tribu,Reach-1,6
Up Type=0
Dn Type=3
Dn Slope=0.005
Boundary for River Rch & Prof#=Bear Creek Tribu,Reach-1,7
Up Type=0
Dn Type=3
Dn Slope=0.005

--- Bear Creek Tributary 13.g01 (geometry) ---

Geom Title=Existing Conditions

River Reach=Bear Creek Tribu,Reach-1
Reach XY= 30
      2180424.68     13802924.68      2180387.84     13802888.42
      2180376.89     13802869.22      2180374.65     13802845.15
      2180375.44     13802711.18      2180373.64     13802684.65
      2180366.91     13802668.92      2180339.05     13802638.03
      2180329.22     13802623.25      2180323.49     13802585.62
      2180319.16     13802572.71      2180305.18     13802554.93
      2180233.18     13802481.04      2180227.54     13802468.95
      2180223.45     13802435.64      2180219.13     13802422.72
      2180205.17     13802404.93      2180133.18     13802331.04
      2180126.71     13802315.20      2180122.36     13802280.64
      2180114.22     13802265.32      2179901.29     13802051.82
      2179880.83     13802027.30      2179868.90     13801972.81
      2179831.08     13801927.20      2179818.88     13801872.82
      2179785.79     13801834.67      2179777.20     13801819.09
      2179774.56     13801795.18      2179775.00     13801675.00

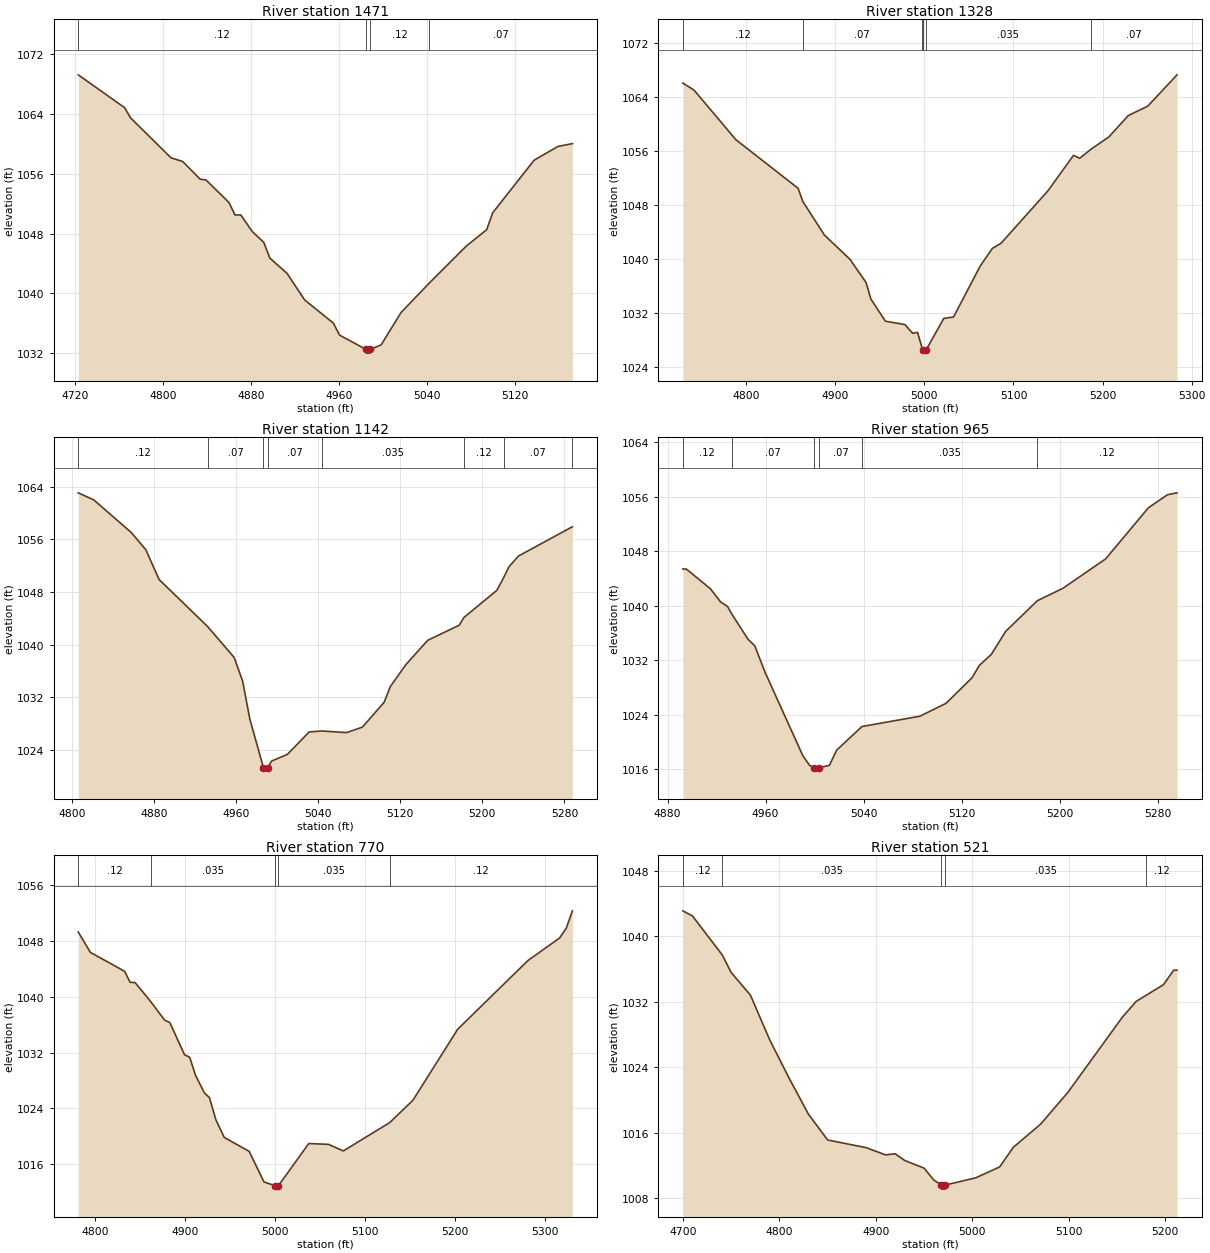
Type RM Length L Ch R = 1,1471,143,143,143
BEGIN DESCRIPTION:
Bear Creek Tributary 13 3.0
END DESCRIPTION:
XS GIS Cut Line= 3
      2180675.00     13802825.00      2180417.72     13802910.60
      2180252.71     13802976.94
#Sta/Elev= 30
  4722.9 1069.24  4765.1 1064.84  4770.4 1063.49  4807.3 1058.13  4817.8 1057.65
  4833.7 1055.28  4838.9 1055.19  4859.9 1052.16  4865.3 1050.50  4870.6 1050.50
  4881.0 1048.29  4891.5 1046.83  4897.0 1044.73  4912.6 1042.69  4928.6 1039.14
  4954.8 1036.02  4960.3 1034.43  4984.4 1032.52  4984.6 1032.02  4988.1 1032.02
  4988.4 1032.52  4998.2 1033.14  5016.2 1037.45  5042.0 1041.41  5075.3 1046.31
  5094.0 1048.53  5099.5 1050.79  5137.1 1057.82  5158.7 1059.66  5171.9 1060.04
#Mann=4,-1,0
  4722.9    0.12       0  4984.4    0.05       0  4988.4    0.12       0
  5042.0    0.07       0
Bank Sta=4984.4,4988.4
Exp/Cntr=0.3,0.1

Type RM Length L Ch R = 1,1328,186,186,186
BEGIN DESCRIPTION:
X18125
END DESCRIPTION:
XS GIS Cut Line= 2
      2180623.58     13802675.82      2180114.88     13802897.00
#Sta/Elev= 30
  4728.9 1066.03  4741.5 1064.98  4788.4 1057.65  4858.2 1050.46  4863.6 1048.49
  4887.7 1043.55  4916.6 1039.93  4934.5 1036.51  4940.0 1034.05  4956.3 1030.78
  4978.1 1030.29  4986.9 1028.99  4992.3 1029.14  4997.0 1027.01  4998.0 1026.56
  4998.2 1026.06  5002.0 1026.56  5021.8 1031.20  5032.7 1031.40  5062.7 1038.96
  5076.3 1041.56  5086.1 1042.33  5138.5 1050.05  5167.4 1055.33  5174.4 1054.90
  5186.6 1056.20  5207.1 1058.06  5228.9 1061.22  5250.8 1062.62  5283.6 1067.25
#Mann=6,-1,0
  4728.9    0.12       0  4863.6    0.07       0  4997.0   0.035       0
  4998.0   0.035       0  5002.0   0.035       0  5186.6    0.07       0
Bank Sta=4998,5002
Exp/Cntr=0.3,0.1

Type RM Length L Ch R = 1,1142,177,177,177
BEGIN DESCRIPTION:
X18124
END DESCRIPTION:
XS GIS Cut Line= 2
      2180490.85     13802510.81      2180082.54     13802766.00
#Sta/Elev= 30
  4806.3 1063.08  4821.4 1062.01  4857.9 1057.06  4872.2 1054.42  4885.0 1049.91
  4932.4 1042.74  4958.2 1038.05  4966.5 1034.43  4973.5 1028.67  4986.8 1021.26
  4987.1 1020.76  4990.8 1021.26  4994.7 1022.29  5010.0 1023.30  5031.3 1026.72
  5043.8 1026.86  5067.8 1026.62  5083.2 1027.45  5104.4 1031.24  5110.3 1033.60
  5125.6 1036.97  5146.8 1040.65  5177.5 1042.95  5182.2 1044.14  5214.1 1048.24
  5220.9 1050.21  5225.9 1051.82  5235.3 1053.47  5287.6 1057.91  5287.8 1057.91
#Mann=8,-1,0
  4806.3    0.12       0  4932.4    0.07       0  4986.8    0.05       0
  4990.8    0.07       0  5043.8   0.035       0  5182.2    0.12       0
  5220.9    0.07       0  5287.6    0.12       0
Bank Sta=4986.8,4990.8
Exp/Cntr=0.3,0.1

Type RM Length L Ch R = 1,965,195,195,195
BEGIN DESCRIPTION:
Bear Creek Tributary 13 2.0
END DESCRIPTION:
XS GIS Cut Line= 3
      2180325.04     13802424.98      2180225.00     13802475.00
      2180075.00     13802725.00
#Sta/Elev= 30
  4892.5 1045.38  4895.3 1045.38  4914.9 1042.50  4923.3 1040.55  4928.9 1039.90
  4932.3 1038.82  4945.7 1035.08  4951.2 1034.12  4959.6 1030.24  4990.4 1018.02
  4996.0 1016.58  4999.6 1016.25  4999.8 1015.75  5003.3 1015.75  5003.6 1016.25
  5012.1 1016.60  5018.0 1018.82  5038.7 1022.29  5086.0 1023.80  5107.4 1025.70
  5128.7 1029.47  5134.6 1031.27  5144.3 1032.86  5156.0 1036.24  5181.9 1040.74
  5202.6 1042.54  5237.6 1046.86  5272.6 1054.37  5288.1 1056.27  5295.9 1056.55
#Mann=6,-1,0
  4892.5    0.12       0  4932.3    0.07       0  4999.6    0.05       0
  5003.6    0.07       0  5038.7   0.035       0  5181.9    0.12       0
Bank Sta=4999.6,5003.6
Exp/Cntr=0.3,0.1

Type RM Length L Ch R = 1,770,249,249,249
BEGIN DESCRIPTION:
X18123
END DESCRIPTION:
XS GIS Cut Line= 3
      2180320.73     13802213.08      2180050.24     13802354.28
      2179870.57     13802520.51
#Sta/Elev= 30
  4781.0 1049.27  4794.5 1046.35  4832.6 1043.64  4838.7 1042.06  4844.3 1042.02
  4861.9 1039.26  4877.2 1036.63  4882.9 1036.30  4899.3 1031.68  4905.0 1031.33
  4911.5 1028.74  4921.4 1026.22  4927.0 1025.55  4934.1 1022.39  4943.5 1019.84
  4971.2 1017.85  4987.7 1013.47  4999.8 1012.94  5000.0 1012.44  5003.8 1012.94
  5037.5 1018.97  5059.6 1018.85  5076.0 1017.91  5127.5 1021.96  5153.4 1025.16
  5203.3 1035.35  5281.6 1045.20  5316.7 1048.41  5324.1 1049.82  5330.9 1052.30
#Mann=5,-1,0
  4781.0    0.12       0  4861.9   0.035       0  4999.8   0.035       0
  5003.8   0.035       0  5127.5    0.12       0
Bank Sta=4999.8,5003.8
Exp/Cntr=0.3,0.1

Type RM Length L Ch R = 1,521,162,162,162
BEGIN DESCRIPTION:
Bear Creek Tributary 13 1.0
END DESCRIPTION:
XS GIS Cut Line= 3
      2180274.98     13802125.00      2179975.00     13802125.00
      2179825.01     13802274.99
#Sta/Elev= 30
  4700.0 1043.10  4710.0 1042.47  4740.9 1037.70  4750.0 1035.58  4770.0 1032.81
  4790.0 1027.35  4810.0 1022.69  4830.0 1018.30  4850.0 1015.13  4890.0 1014.19
  4910.0 1013.31  4920.0 1013.45  4930.0 1012.62  4950.0 1011.69  4960.0 1010.24
  4968.0 1009.63  4968.2 1009.13  4971.7 1009.13  4972.0 1009.63  5003.5 1010.51
  5028.3 1011.84  5042.4 1014.23  5070.7 1017.06  5099.0 1020.94  5155.5 1030.13
  5169.7 1032.04  5180.1 1032.79  5198.0 1034.08  5208.6 1035.85  5212.1 1035.85
#Mann=5,-1,0
  4700.0    0.12       0  4740.9   0.035       0  4968.0   0.035       0
  4972.0   0.035       0  5180.1    0.12       0
Bank Sta=4968,4972
Exp/Cntr=0.3,0.1

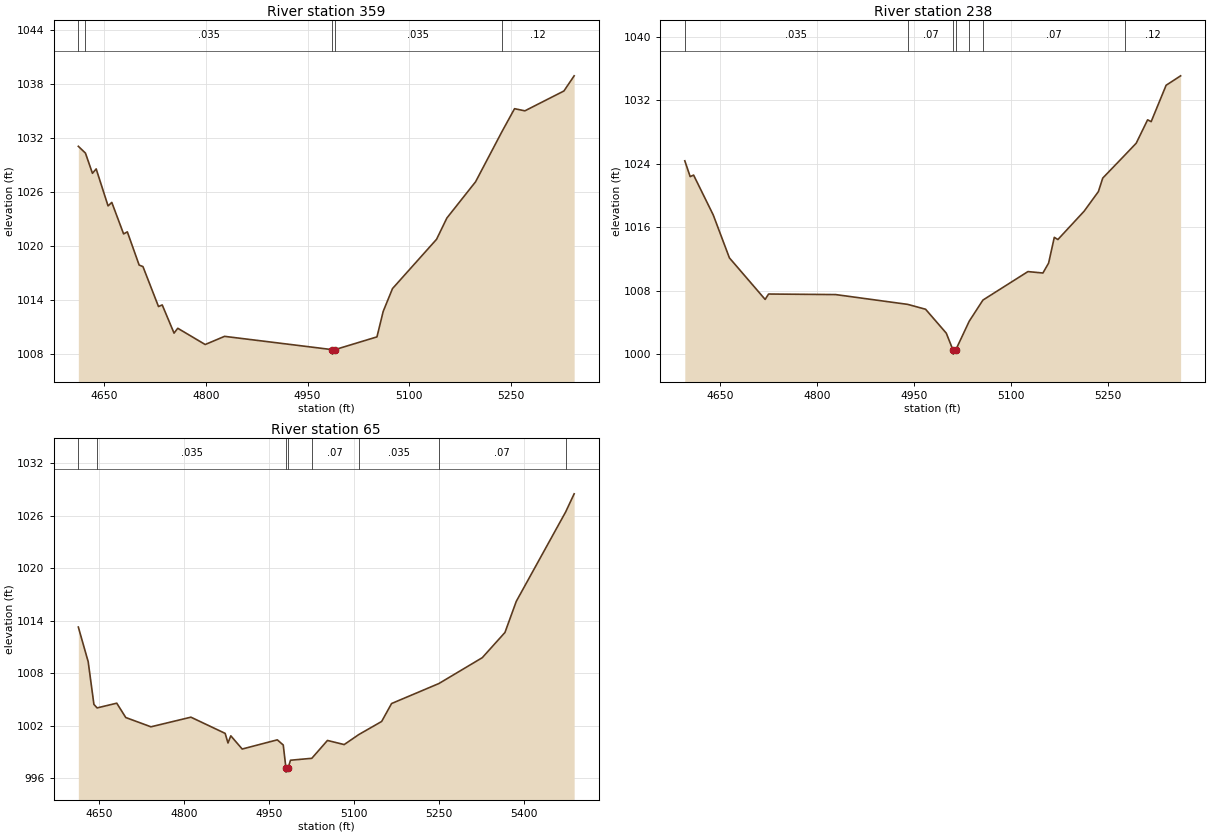
Type RM Length L Ch R = 1,359,121,121,121
BEGIN DESCRIPTION:
X18122
END DESCRIPTION:
XS GIS Cut Line= 3
      2180227.18     13801840.49      2179851.19     13802014.02
      2179680.06     13802280.03
#Sta/Elev= 30
  4612.3 1031.10  4622.8 1030.34  4633.1 1028.09  4638.6 1028.58  4656.1 1024.46
  4661.6 1024.85  4679.0 1021.34  4684.5 1021.57  4701.9 1017.87  4707.5 1017.70
  4730.4 1013.25  4735.9 1013.43  4753.3 1010.29  4758.8 1010.83  4799.2 1009.02
  4827.7 1009.93  4986.3 1008.45  4986.6 1007.95  4990.3 1008.45  5052.2 1009.87
  5061.4 1012.71  5075.1 1015.25  5140.0 1020.74  5155.2 1023.11  5197.5 1027.15
  5236.1 1032.70  5254.9 1035.29  5270.1 1035.05  5327.6 1037.26  5342.7 1038.95
#Mann=5,-1,0
  4612.3    0.12       0  4622.8   0.035       0  4986.3   0.035       0
  4990.3   0.035       0  5236.1    0.12       0
Bank Sta=4986.3,4990.3
Exp/Cntr=0.3,0.1

Type RM Length L Ch R = 1,238,173,173,173
BEGIN DESCRIPTION:
X18121
END DESCRIPTION:
XS GIS Cut Line= 3
      2180203.31     13801755.44      2179798.45     13801906.84
      2179660.93     13802210.73
#Sta/Elev= 30
  4595.8 1024.36  4604.1 1022.37  4609.4 1022.56  4639.7 1017.54  4664.7 1012.12
  4719.9 1006.88  4725.2 1007.56  4828.9 1007.49  4940.4 1006.25  4967.7 1005.64
  4999.7 1002.62  5010.1 1000.48  5010.4  999.98  5014.1 1000.48  5035.1 1004.13
  5056.3 1006.80  5125.8 1010.39  5148.9 1010.21  5157.7 1011.46  5166.5 1014.71
  5172.0 1014.43  5212.6 1018.01  5234.6 1020.48  5241.3 1022.18  5275.7 1025.10
  5293.0 1026.58  5310.6 1029.53  5316.1 1029.30  5339.2 1033.89  5361.6 1035.08
#Mann=7,-1,0
  4595.8   0.035       0  4940.4    0.07       0  5010.1    0.05       0
  5014.1    0.07       0  5035.1   0.035       0  5056.3    0.07       0
  5275.7    0.12       0
Bank Sta=5010.1,5014.1
Exp/Cntr=0.3,0.1

Type RM Length L Ch R = 1,65,0,0,0
BEGIN DESCRIPTION:
X18120
END DESCRIPTION:
XS GIS Cut Line= 4
      2180152.34     13801680.57      2179803.55     13801719.70
      2179655.54     13801825.18      2179653.84     13802167.15
#Sta/Elev= 30
  4613.7 1013.30  4631.1 1009.34  4641.2 1004.46  4646.8 1004.06  4681.5 1004.60
  4697.4 1002.96  4741.8 1001.90  4812.3 1003.00  4872.7 1001.15  4877.7 1000.05
  4882.7 1000.87  4902.8  999.36  4964.7 1000.41  4975.2  999.82  4979.9  997.22
  4980.1  996.72  4983.9  997.22  4988.0  998.08  5025.6  998.30  5053.2 1000.34
  5082.7  999.87  5108.4 1001.01  5148.8 1002.51  5166.3 1004.56  5249.9 1006.85
  5326.3 1009.80  5366.3 1012.68  5386.3 1016.24  5473.4 1026.46  5488.4 1028.53
#Mann=8,-1,0
  4613.7    0.07       0  4646.8   0.035       0  4979.9   0.035       0
  4983.9   0.035       0  5025.6    0.07       0  5108.4   0.035       0
  5249.9    0.07       0  5473.4    0.12       0
Bank Sta=4979.9,4983.9
Exp/Cntr=0.3,0.1

Chan Stop Cuts=-1