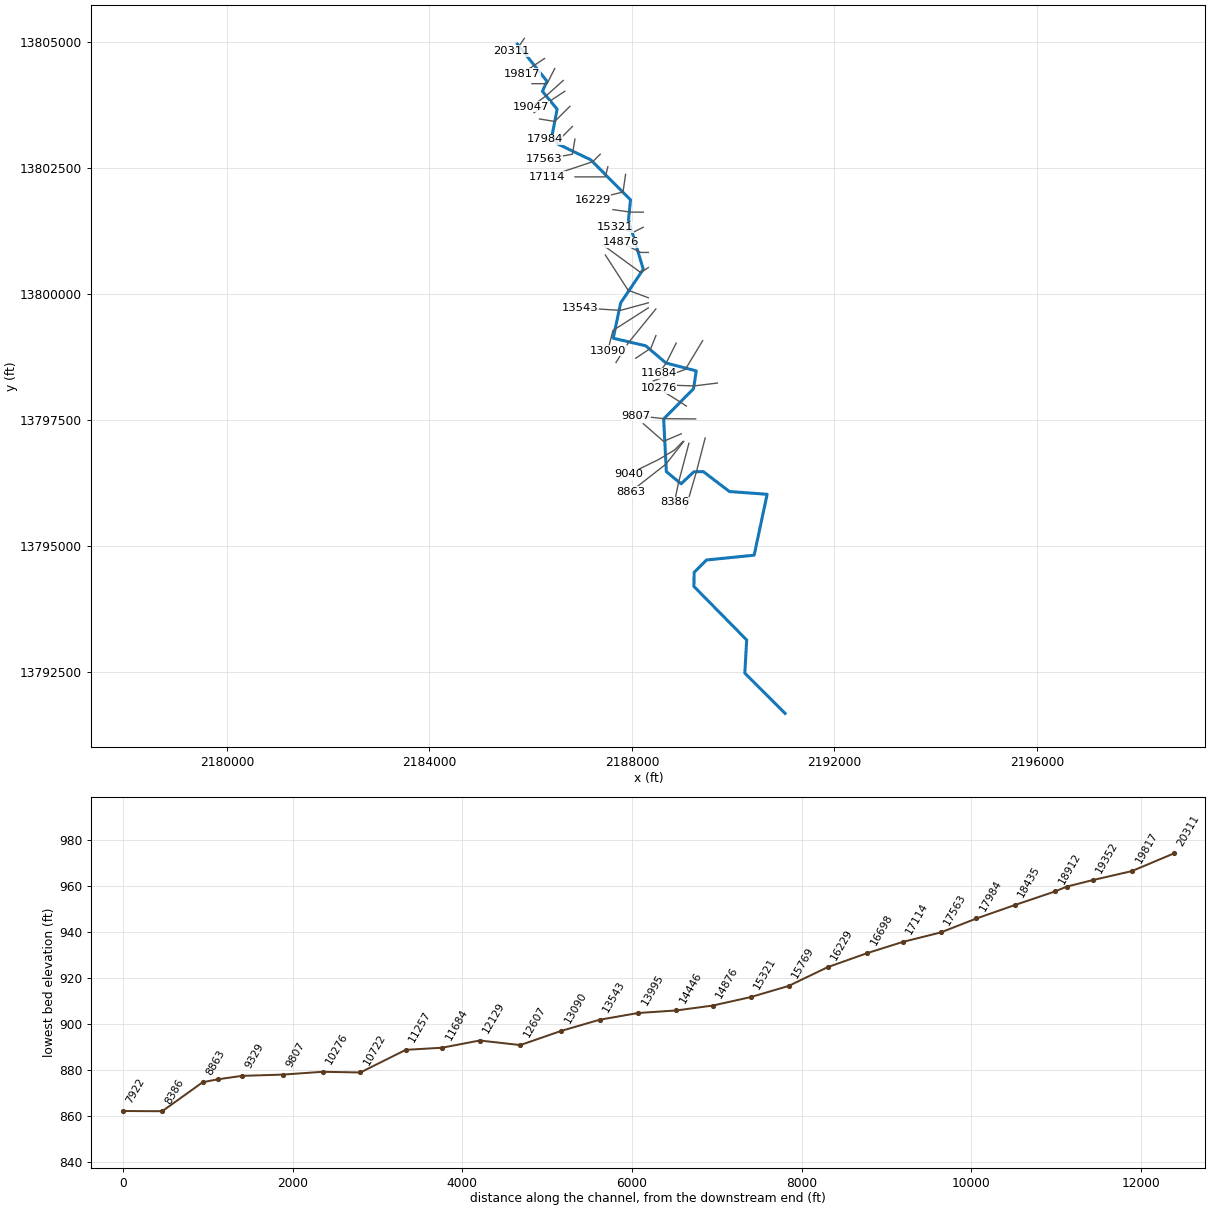
--- Bear Creek Tributary 14.prj (project) ---

Proj Title=Bear Creek Tributary 14 Base Level Engineering
Current Plan=p01
Default Exp/Contr=0.3,0.1
English Units
Geom File=g01
Flow File=f01
Plan File=p01
Y Axis Title=Elevation
X Axis Title(PF)=Main Channel Distance
X Axis Title(XS)=Station
BEGIN DESCRIPTION:
Bear Creek Tributary 14
END DESCRIPTION:
DSS Export Rating Curves= 0
DSS Export Rating Curve Sorted= 0
DSS Export Volume Flow Curves= 0
DXF OffsetX= 0
DXF OffsetY= 0
DXF ScaleX= 1
DXF ScaleY= 10

--- Bear Creek Tributary 14.p01 (plan) ---

Plan Title=Multiple Run
Short Identifier=Multiple
Geom File=g01
Flow File=f01
Subcritical Flow
K Sum by GR= 0
Std Step Tol= 0.01
Critical Tol= 0.01
Num of Std Step Trials= 20
Max Error Tol= 0.3
Flow Tol Ratio= 0.001
Split Flow NTrial= 30
Split Flow Tol= 0.02
Split Flow Ratio= 0.02
Log Output Level= 0
Friction Slope Method= 1
Unsteady Friction Slope Method= 2
Unsteady Bridges Friction Slope Method= 1
Parabolic Critical Depth
Global Vel Dist=  1 , 1 , 1
Global Log Level= 0
CheckData=True
Encroach Param= -1, 0, 0, 0
BEGIN DESCRIPTION:
Multiple Run
END DESCRIPTION:

--- Bear Creek Tributary 14.f01 (steady flow) ---

Flow Title=Multiple
Number of Profiles=7
Profile Names=10-year,25-year,50-year,1pct_min,100-year,1pct_plu,500-year
River Rch & RM= Bear Creek Tribu,Reach-1,20311
     811    1352    1857    1237    2468    4925    4314
River Rch & RM= Bear Creek Tribu,Reach-1,16698
    1205    2052    2860    1929    3850    7681    6905
River Rch & RM= Bear Creek Tribu,Reach-1,13543
    1536    2648    3721    2529    5046   10067    9189
River Rch & RM= Bear Creek Tribu,Reach-1,12607
    1794    3090    4337    2940    5866   11704   10633
River Rch & RM= Bear Creek Tribu,Reach-1,4637
    1918    3309    4648    3152    6288   12547   11406
Boundary for River Rch & Prof#=Bear Creek Tribu,Reach-1,1
Up Type=0
Dn Type=3
Dn Slope=0.005
Boundary for River Rch & Prof#=Bear Creek Tribu,Reach-1,2
Up Type=0
Dn Type=3
Dn Slope=0.005
Boundary for River Rch & Prof#=Bear Creek Tribu,Reach-1,3
Up Type=0
Dn Type=3
Dn Slope=0.005
Boundary for River Rch & Prof#=Bear Creek Tribu,Reach-1,4
Up Type=0
Dn Type=3
Dn Slope=0.005
Boundary for River Rch & Prof#=Bear Creek Tribu,Reach-1,5
Up Type=0
Dn Type=3
Dn Slope=0.005
Boundary for River Rch & Prof#=Bear Creek Tribu,Reach-1,6
Up Type=0
Dn Type=3
Dn Slope=0.005
Boundary for River Rch & Prof#=Bear Creek Tribu,Reach-1,7
Up Type=0
Dn Type=3
Dn Slope=0.005

--- Bear Creek Tributary 14.g01 (geometry) ---

Geom Title=Existing Conditions
Program Version=4.10

River Reach=Bear Creek Tribu,Reach-1
Reach XY= 30
       2185738.4      13804961.6      2186321.33     13804223.41
      2186232.61     13804021.67      2186522.95     13803669.14
      2186424.54     13803154.83      2186530.47     13802980.26
       2187185.1     13802664.61      2187972.94     13801869.15
      2187932.81     13801471.59      2188224.49     13800490.21
       2187778.3     13799823.63      2187630.36      13799122.3
      2188273.45     13798971.25      2188672.56     13798630.48
      2189271.57     13798473.78      2189216.86     13798118.94
      2188627.06     13797519.15      2188680.46     13796472.55
      2188971.67      13796232.6      2189222.55     13796469.54
      2189409.79      13796474.5      2189926.55     13796078.75
      2190671.57     13796023.78      2190414.49     13794815.19
      2189472.55     13794719.53      2189228.75     13794473.45
      2189224.96     13794194.98      2190267.31     13793131.48
      2190230.47     13792472.55        2191025.       13791675.

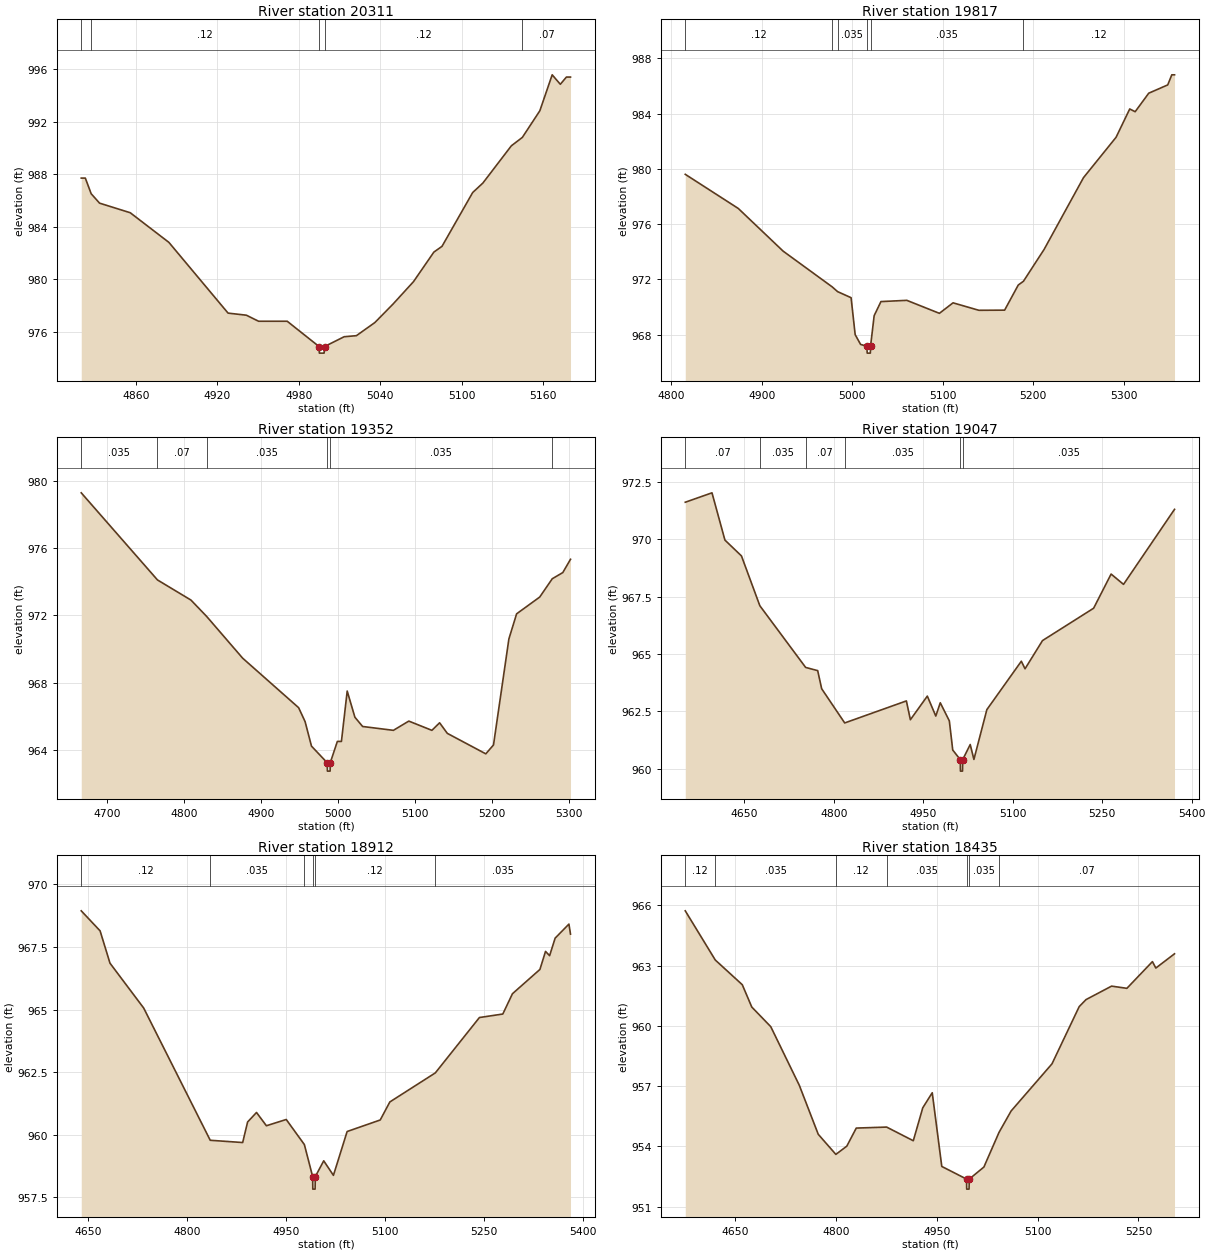
Type RM Length L Ch R = 1 ,20311   ,494,494,494
BEGIN DESCRIPTION:
Bear Creek Tributary 14 44.0
END DESCRIPTION:
XS GIS Cut Line= 3
      2185875.01     13805075.02        2185775.       13804925.
      2185624.98     13804824.99
#Sta/Elev= 30
  4819.7   987.7  4822.7   987.7    4827  986.51  4833.2  985.79  4855.8  985.06
  4884.3   982.8  4927.9  977.41  4941.4  977.25  4950.4  976.79  4971.5  976.79
    4995  974.86  4995.2  974.36  4998.7  974.36    4999  974.86  5013.5  975.61
  5022.5  975.69  5036.1  976.69  5049.6  978.11  5064.6  979.81  5079.6  982.06
  5085.6   982.5  5108.2   986.6  5115.7  987.32  5136.7  990.16  5144.8   990.8
  5157.7  992.83  5166.8  995.57  5172.8  994.85  5177.3   995.4  5180.3   995.4
#Mann= 5 ,-1 , 0
  4819.7     .07       0    4827     .12       0    4995     .05       0
    4999     .12       0  5144.8     .07       0
Bank Sta=4995,4999
XS Rating Curve= 0 ,0
Exp/Cntr=0.3,0.1

Type RM Length L Ch R = 1 ,19817   ,465,465,465
BEGIN DESCRIPTION:
Bear Creek Tributary 14 43.0
END DESCRIPTION:
XS GIS Cut Line= 3
        2186275.       13804675.        2186125.       13804575.
      2185825.03     13804375.02
#Sta/Elev= 30
  4815.3  979.61  4873.9  977.14  4923.5  974.05  4977.6  971.47  4983.7  971.12
  4998.6  970.68  5003.1  968.01  5009.1   967.3  5016.1  967.17  5016.4  966.67
  5019.9  966.67  5020.1  967.17  5024.1  969.38  5031.6   970.4  5060.2  970.49
  5096.2  969.55  5111.3  970.31  5139.8  969.77  5168.3  969.78  5183.4   971.6
  5189.1  971.87  5211.9  974.17  5255.5  979.37  5291.5  982.29  5306.6  984.34
  5312.6  984.14  5327.6  985.48  5348.6  986.08  5353.1  986.81  5356.1  986.81
#Mann= 6 ,-1 , 0
  4815.3     .12       0  4977.6     .07       0  4983.7    .035       0
  5016.1    .035       0  5020.1    .035       0  5189.1     .12       0
Bank Sta=5016.1,5020.1
XS Rating Curve= 0 ,0
Exp/Cntr=0.3,0.1

Type RM Length L Ch R = 1 ,19352   ,305,305,305
BEGIN DESCRIPTION:
Bear Creek Tributary 14 42.0
END DESCRIPTION:
XS GIS Cut Line= 3
      2186474.99     13804474.97        2186325.       13804175.
      2186024.98       13804175.
#Sta/Elev= 30
  4666.5   979.3  4765.5  974.11    4809  972.91  4829.3  971.94  4876.1  969.45
  4948.8   966.5  4957.2  965.67  4965.5  964.21  4985.9  963.22  4986.2  962.72
  4989.7  962.72  4989.9  963.22  4999.1  964.49  5004.4  964.49  5011.9  967.49
  5021.9  965.93  5031.9  965.38  5071.9  965.15  5091.9   965.7  5121.9  965.15
  5131.9   965.6  5141.9  964.97  5191.9  963.75  5201.9  964.28  5221.9   970.6
  5231.9  972.09  5261.9  973.09  5278.2  974.18  5291.9  974.55  5301.9  975.34
#Mann= 6 ,-1 , 0
  4666.5    .035       0  4765.5     .07       0  4829.3    .035       0
  4985.9    .035       0  4989.9    .035       0  5278.2     .07       0
Bank Sta=4985.9,4989.9
XS Rating Curve= 0 ,0
Exp/Cntr=0.3,0.1

Type RM Length L Ch R = 1 ,19047   ,135,135,135
BEGIN DESCRIPTION:
Bear Creek Tributary 14 41.5
END DESCRIPTION:
XS GIS Cut Line= 3
      2186644.61     13804238.86      2186319.26     13803945.16
      2186011.32     13803719.28
#Sta/Elev= 30
  4551.1  971.62  4595.9  972.03  4617.6  969.97  4645.3  969.28  4676.1  967.11
  4752.9  964.42  4773.1  964.28  4779.8  963.49  4818.4     962  4921.8  962.96
  4928.5  962.14  4956.9  963.17  4971.1   962.3  4978.6  962.88  4993.8  962.09
  4999.5  960.82  5012.2   960.4  5012.4   959.9  5015.9   959.9  5016.2   960.4
  5028.8  961.06    5035  960.41  5056.7  962.58  5114.5  964.69  5120.7  964.36
    5150  965.59  5235.7     967    5265  968.49  5285.8  968.04  5371.3  971.31
#Mann= 6 ,-1 , 0
  4551.1     .07       0  4676.1    .035       0  4752.9     .07       0
  4818.4    .035       0  5012.2    .035       0  5016.2    .035       0
Bank Sta=5012.2,5016.2
XS Rating Curve= 0 ,0
Exp/Cntr=0.3,0.1

Type RM Length L Ch R = 1 ,18912   ,477,477,477
BEGIN DESCRIPTION:
Bear Creek Tributary 14 41.0
END DESCRIPTION:
XS GIS Cut Line= 3
      2186675.01     13804025.01        2186375.       13803825.
       2186067.2     13803599.22
#Sta/Elev= 30
  4639.2  968.94  4667.8  968.14  4682.8  966.85  4733.9  965.06  4834.9  959.78
  4884.1  959.69  4891.6  960.51  4905.1  960.89  4920.1  960.36  4950.2  960.61
  4977.7  959.61  4990.3  958.33  4990.5  957.83    4994  957.83  4994.3  958.33
  5007.1  958.96  5021.8  958.38  5042.6  960.13  5092.8  960.59  5107.4  961.31
  5176.4  962.47  5243.3  964.68  5278.8  964.82  5293.4  965.63  5335.1   966.6
  5343.6  967.32  5349.8  967.15  5358.2  967.85  5379.1  968.41  5381.5  968.01
#Mann= 6 ,-1 , 0
  4639.2     .12       0  4834.9    .035       0  4977.7     .12       0
  4990.3     .05       0  4994.3     .12       0  5176.4    .035       0
Bank Sta=4990.3,4994.3
XS Rating Curve= 0 ,0
Exp/Cntr=0.3,0.1

Type RM Length L Ch R = 1 ,18435   ,451,451,451
BEGIN DESCRIPTION:
Bear Creek Tributary 14 40.0
END DESCRIPTION:
XS GIS Cut Line= 3
      2186775.03     13803725.03        2186475.       13803425.
      2186175.05     13803474.99
#Sta/Elev= 30
  4575.4  965.73  4620.1  963.28  4660.3  962.05  4674.4  960.94  4702.7  959.96
  4745.2  957.04  4773.4   954.6  4799.6   953.6  4815.9  954.01    4830  954.91
  4875.2  954.96  4914.9  954.28    4929  955.92  4943.1  956.67  4957.3     953
  4994.2  952.37  4994.4  951.87  4997.9  951.87  4998.2  952.37    5020  952.97
  5042.6   954.7  5060.5  955.76  5121.4  958.11  5161.9  960.96  5172.1  961.31
  5210.1  961.98  5232.9  961.87  5270.9   963.2    5276  962.88  5303.8  963.59
#Mann= 7 ,-1 , 0
  4575.4     .12       0  4620.1    .035       0  4799.6     .12       0
  4875.2    .035       0  4994.2    .035       0  4998.2    .035       0
  5042.6     .07       0
Bank Sta=4994.2,4998.2
XS Rating Curve= 0 ,0
Exp/Cntr=0.3,0.1

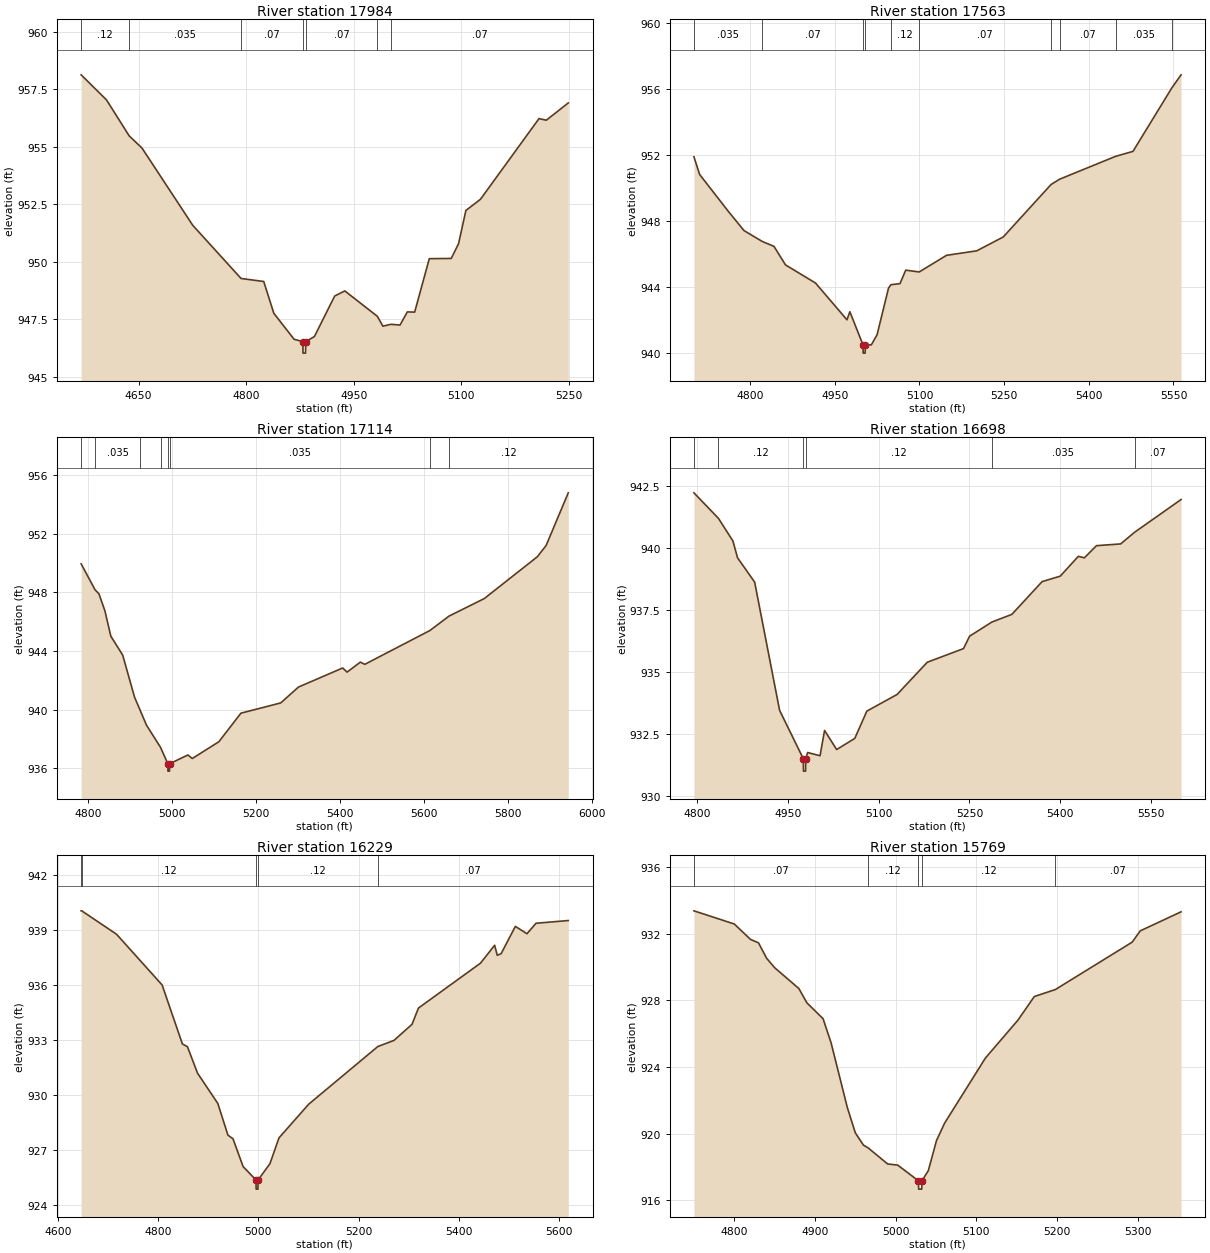
Type RM Length L Ch R = 1 ,17984   ,421,421,421
BEGIN DESCRIPTION:
Bear Creek Tributary 14 39.0
END DESCRIPTION:
XS GIS Cut Line= 3
      2186825.03     13803325.03        2186525.       13803025.
      2186274.96     13803075.01
#Sta/Elev= 30
  4569.9  958.12  4605.3  957.03  4636.9  955.47  4654.8  954.94  4725.5  951.59
  4792.9  949.28  4824.5  949.15  4838.6  947.77  4866.9  946.64  4879.1  946.54
  4879.3  946.04  4882.8  946.04  4883.1  946.54  4895.2  946.76  4923.5  948.52
  4937.6  948.74  4982.9  947.64  4990.7  947.21  5001.7  947.29  5014.6  947.26
  5024.8  947.83    5035  947.82  5055.4  950.14    5086  950.15  5096.2  950.79
  5106.4  952.23  5126.8  952.72  5208.4  956.22  5218.6  956.15  5249.2   956.9
#Mann= 7 ,-1 , 0
  4569.9     .12       0  4636.9    .035       0  4792.9     .07       0
  4879.1     .05       0  4883.1     .07       0  4982.9     .12       0
  5001.7     .07       0
Bank Sta=4879.1,4883.1
XS Rating Curve= 0 ,0
Exp/Cntr=0.3,0.1

Type RM Length L Ch R = 1 ,17563   ,449,449,449
BEGIN DESCRIPTION:
Bear Creek Tributary 14 38.0
END DESCRIPTION:
XS GIS Cut Line= 3
        2186875.       13803075.        2186825.       13802775.
      2186274.96     13802674.99
#Sta/Elev= 30
  4700.3  951.87  4710.4   950.8  4761.1  948.57    4789   947.4  4821.3  946.74
  4842.2  946.44  4862.5  945.32  4915.7  944.22  4971.5  941.99  4976.6  942.48
  4999.9  940.47  5000.2  939.97  5003.7  939.97  5003.9  940.47  5014.6  940.47
  5024.8  941.08  5045.1  943.91  5049.4  944.12  5065.4  944.18  5075.6     945
  5099.5  944.89    5148   945.9  5201.4  946.17  5248.4  947.01  5333.1  950.19
  5348.1  950.51  5447.7   951.9  5478.3   952.2  5547.2  956.05  5563.5  956.84
#Mann= 10 ,-1 , 0
  4700.3    .035       0  4821.3     .07       0  4999.9     .05       0
  5003.9     .07       0  5049.4     .12       0  5099.5     .07       0
  5333.1    .035       0  5348.1     .07       0  5447.7    .035       0
  5547.2     .07       0
Bank Sta=4999.9,5003.9
XS Rating Curve= 0 ,0
Exp/Cntr=0.3,0.1

Type RM Length L Ch R = 1 ,17114   ,416,416,416
BEGIN DESCRIPTION:
Bear Creek Tributary 14 37.0
END DESCRIPTION:
XS GIS Cut Line= 3
      2187375.02     13802775.02        2187225.       13802625.
      2186324.95     13802324.98
#Sta/Elev= 30
  4783.7  949.95  4816.7  948.19  4826.2   947.9  4840.3  946.75  4854.4  945.02
  4882.7  943.73    4911  940.86  4923.7  940.01  4939.3  938.96  4973.1  937.43
  4990.3  936.32  4990.6  935.82  4994.1  935.82  4994.3  936.32    5038  936.92
  5048.6  936.68  5111.8  937.82  5164.5  939.77  5259.4  940.47  5301.6  941.55
    5407  942.85  5417.5  942.57  5449.1  943.25  5459.7   943.1  5614.6   945.4
  5660.6  946.39  5744.3  947.58  5870.8  950.43  5891.8   951.2  5944.6  954.79
#Mann= 8 ,-1 , 0
  4783.7     .12       0  4816.7    .035       0  4923.7     .12       0
  4973.1    .035       0  4990.3    .035       0  4994.3    .035       0
  5614.6     .07       0  5660.6     .12       0
Bank Sta=4990.3,4994.3
XS Rating Curve= 0 ,0
Exp/Cntr=0.3,0.1

Type RM Length L Ch R = 1 ,16698   ,469,469,469
BEGIN DESCRIPTION:
Bear Creek Tributary 14 36.0
END DESCRIPTION:
XS GIS Cut Line= 3
      2187525.01     13802525.04        2187475.       13802325.
        2186875.       13802325.
#Sta/Elev= 30
  4794.1  942.21  4834.7  941.18  4858.6  940.27  4866.3  939.59  4894.6  938.61
  4935.9  933.44  4975.1  931.49  4975.4  930.99  4978.9  930.99  4979.1  931.49
  4982.3  931.74  5002.8  931.61  5010.3  932.63  5030.3  931.86  5060.3  932.31
  5080.3  933.41  5130.3  934.08  5180.3  935.38  5240.3  935.93  5250.3  936.43
  5287.2     937  5320.3  937.31  5370.3  938.63  5400.3  938.85  5430.3  939.65
  5440.3  939.59  5460.3  940.08  5500.3  940.15  5523.4  940.62  5600.3  941.94
#Mann= 6 ,-1 , 0
  4794.1    .035       0  4834.7     .12       0  4975.1     .05       0
  4979.1     .12       0  5287.2    .035       0  5523.4     .07       0
Bank Sta=4975.1,4979.1
XS Rating Curve= 0 ,0
Exp/Cntr=0.3,0.1

Type RM Length L Ch R = 1 ,16229   ,460,460,460
BEGIN DESCRIPTION:
Bear Creek Tributary 14 35.0
END DESCRIPTION:
XS GIS Cut Line= 3
        2187875.       13802375.        2187825.       13802025.
      2187225.02       13801875.
#Sta/Elev= 30
  4646.5  940.04  4647.7  940.04  4717.2  938.76  4808.1  935.99  4848.5  932.77
  4858.6  932.62  4878.8  931.17  4919.2  929.52  4939.4  927.79  4949.5  927.59
  4969.7  926.07  4995.4  925.34  4995.7  924.84  4999.3  924.84  4999.6  925.34
  5023.2  926.23  5041.3  927.64  5100.6  929.48  5238.6  932.63  5270.6  932.96
  5306.7  933.84  5319.6  934.73  5443.3  937.18  5471.6  938.16  5476.8  937.61
  5484.5   937.7  5512.9  939.19  5536.1  938.79  5554.1  939.36  5618.5  939.51
#Mann= 5 ,-1 , 0
  4646.5    .035       0  4647.7     .12       0  4995.4     .05       0
  4999.6     .12       0  5238.6     .07       0
Bank Sta=4995.4,4999.6
XS Rating Curve= 0 ,0
Exp/Cntr=0.3,0.1

Type RM Length L Ch R = 1 ,15769   ,448,448,448
BEGIN DESCRIPTION:
Bear Creek Tributary 14 34.0
END DESCRIPTION:
XS GIS Cut Line= 3
      2188224.99       13801625.        2187975.       13801625.
      2187625.04     13801674.99
#Sta/Elev= 30
  4750.1  933.36  4800.1  932.57  4820.1  931.65  4830.1  931.44  4840.1  930.52
  4850.1  929.95  4880.1   928.7  4890.1  927.84  4910.1  926.89  4920.1  925.43
  4940.1  921.57  4950.1  920.04  4960.1  919.31    4966  919.14  4990.1  918.18
  5002.6  918.11  5028.2  917.17  5028.5  916.67  5032.3  916.67  5032.6  917.17
  5040.5  917.78  5050.6  919.58  5060.7  920.63  5111.2  924.53  5151.6  926.81
  5171.8  928.22  5197.9  928.64    5293  931.48  5303.1  932.16  5353.6   933.3
#Mann= 5 ,-1 , 0
  4750.1     .07       0    4966     .12       0  5028.2     .05       0
  5032.6     .12       0  5197.9     .07       0
Bank Sta=5028.2,5032.6
XS Rating Curve= 0 ,0
Exp/Cntr=0.3,0.1

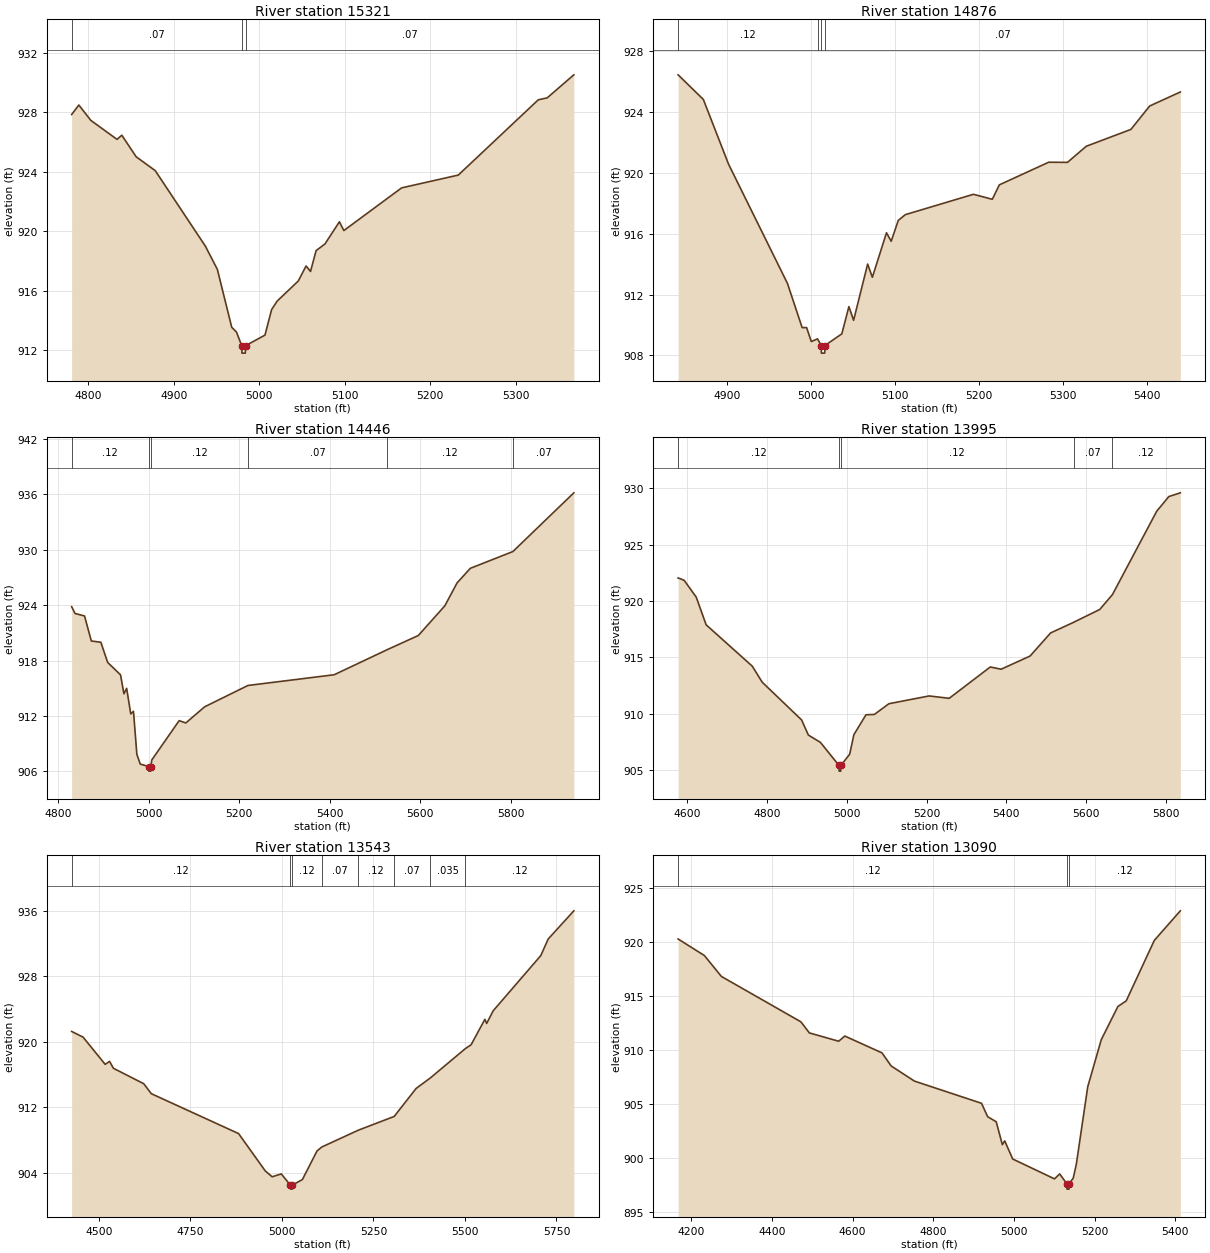
Type RM Length L Ch R = 1 ,15321   ,445,445,445
BEGIN DESCRIPTION:
Bear Creek Tributary 14 33.0
END DESCRIPTION:
XS GIS Cut Line= 3
      2188225.02     13801325.01        2188025.       13801225.
      2187675.03     13801324.99
#Sta/Elev= 30
  4780.5  927.86  4788.9   928.5  4802.9  927.47  4833.6  926.19  4839.2  926.47
    4856  925.02  4878.3  924.09    4937  919.01    4951  917.45  4967.8  913.56
  4973.4  913.23  4979.5  912.32  4979.8  911.82  4983.7  911.82    4984  912.32
  5006.7  913.03  5014.5  914.75    5021  915.32  5045.7  916.67  5054.8  917.68
    5060  917.31  5066.5  918.71  5076.9  919.16  5093.8  920.65    5099  920.06
  5166.6  922.93  5232.9  923.79  5326.5  928.85  5336.9  928.98  5368.1  930.53
#Mann= 3 ,-1 , 0
  4780.5     .07       0  4979.5     .05       0    4984     .07       0
Bank Sta=4979.5,4984
XS Rating Curve= 0 ,0
Exp/Cntr=0.3,0.1

Type RM Length L Ch R = 1 ,14876   ,430,430,430
BEGIN DESCRIPTION:
Bear Creek Tributary 14 32.0
END DESCRIPTION:
XS GIS Cut Line= 3
      2188324.97       13800825.        2188175.       13800825.
      2187774.98     13801025.01
#Sta/Elev= 30
  4842.3  926.46  4872.3  924.84  4902.3  920.58  4972.3  912.74  4989.8  909.83
  4995.1  909.83  5000.7  908.91  5008.1  909.09  5012.4  908.65  5012.7  908.15
  5016.6  908.15  5016.9  908.65    5037  909.42  5045.4  911.21    5051  910.31
  5067.7  914.01  5073.3  913.14  5090.1  916.07  5095.7  915.51  5104.1  916.88
  5112.5  917.26  5193.5   918.6  5215.9  918.27  5224.3  919.22    5283  920.71
  5305.3   920.7  5327.7  921.76  5380.8  922.87  5403.1  924.41  5439.5  925.33
#Mann= 4 ,-1 , 0
  4842.3     .12       0  5008.1     .07       0  5012.4     .05       0
  5016.9     .07       0
Bank Sta=5012.4,5016.9
XS Rating Curve= 0 ,0
Exp/Cntr=0.3,0.1

Type RM Length L Ch R = 1 ,14446   ,451,451,451
BEGIN DESCRIPTION:
Bear Creek Tributary 14 31.0
END DESCRIPTION:
XS GIS Cut Line= 3
      2188324.96     13800524.97        2188175.       13800425.
      2187424.99     13800975.01
#Sta/Elev= 30
  4829.6  923.83  4837.1   923.1  4858.1  922.83  4873.1  920.12  4894.2  919.98
  4909.2   917.8  4937.7  916.45  4945.2   914.4  4951.2  914.99  4960.3  912.22
  4966.3   912.5  4973.8  907.84  4981.3  906.78    5000  906.52  5000.4  906.02
  5004.3  906.02  5004.6  906.52  5006.8  907.23  5067.3  911.49    5082  911.24
  5123.7  912.99  5219.4   915.3    5410  916.46  5527.4  919.18    5596  920.71
  5654.7  923.93  5681.7  926.41    5711  927.99  5805.2  929.81  5939.9  936.17
#Mann= 6 ,-1 , 0
  4829.6     .12       0    5000     .05       0  5004.6     .12       0
  5219.4     .07       0  5527.4     .12       0  5805.2     .07       0
Bank Sta=5000,5004.6
XS Rating Curve= 0 ,0
Exp/Cntr=0.3,0.1

Type RM Length L Ch R = 1 ,13995   ,452,452,452
BEGIN DESCRIPTION:
Bear Creek Tributary 14 30.0
END DESCRIPTION:
XS GIS Cut Line= 3
      2188324.98     13799925.01        2187925.       13800075.
      2187475.03     13800774.96
#Sta/Elev= 30
  4577.1  922.04  4592.2  921.83  4622.5  920.34  4647.4  917.88  4763.1  914.21
    4788  912.79  4886.8  909.44  4903.7   908.1    4934  907.45  4980.6   905.4
  4980.9   904.9  4984.9   904.9  4985.2   905.4  5007.3   906.4  5017.8  908.13
  5048.2   909.9  5069.3  909.93  5105.7  910.88  5206.4  911.57  5256.9  911.36
  5359.9  914.14    5387  913.94  5459.7  915.11  5511.2  917.16  5569.3  918.11
  5634.3  919.24  5666.2  920.56  5777.3  927.96  5807.7  929.26  5836.4  929.59
#Mann= 5 ,-1 , 0
  4577.1     .12       0  4980.6     .05       0  4985.2     .12       0
  5569.3     .07       0  5666.2     .12       0
Bank Sta=4980.6,4985.2
XS Rating Curve= 0 ,0
Exp/Cntr=0.3,0.1

Type RM Length L Ch R = 1 ,13543   ,453,453,453
BEGIN DESCRIPTION:
Bear Creek Tributary 14 29.0
END DESCRIPTION:
XS GIS Cut Line= 3
      2188324.96     13799824.99        2187775.       13799675.
        2186975.       13799725.
#Sta/Elev= 30
  4425.8  921.26  4456.9  920.57  4517.3  917.24  4529.4   917.6  4539.8  916.76
  4622.7  914.87  4643.4  913.65  4881.8  908.77  4954.4  904.22  4973.4  903.49
  4998.3  903.84  5023.1  902.48  5023.5  901.98  5028.3  901.98  5028.8  902.48
    5056  903.15    5096  906.65    5109  907.13  5207.9  909.17  5306.8  910.87
  5366.6  914.29  5405.6  915.58  5500.5  919.14  5516.9  919.64  5554.4  922.74
  5559.4  922.24    5577  923.78  5707.2  930.54  5727.3  932.56  5797.4  936.01
#Mann= 8 ,-1 , 0
  4425.8     .12       0  5023.1     .05       0  5028.8     .12       0
    5109     .07       0  5207.9     .12       0  5306.8     .07       0
  5405.6    .035       0  5500.5     .12       0
Bank Sta=5023.1,5028.8
XS Rating Curve= 0 ,0
Exp/Cntr=0.3,0.1

Type RM Length L Ch R = 1 ,13090   ,483,483,483
BEGIN DESCRIPTION:
Bear Creek Tributary 14 28.0
END DESCRIPTION:
XS GIS Cut Line= 3
      2188325.02     13799725.01        2187625.       13799275.
        2187525.       13798875.
#Sta/Elev= 30
  4167.7   920.3  4232.8  918.77    4275  916.83  4471.9  912.63    4493   911.6
  4565.6  910.83  4580.8  911.31    4673  909.75  4695.7  908.54  4753.2  907.14
  4919.6  905.08  4934.8  903.84    4956  903.37  4971.2  901.25  4977.1   901.6
  4996.9  899.92  5100.4  898.08  5113.3  898.54    5131  897.63  5131.5  897.13
  5136.3  897.13  5136.7  897.63  5146.8  898.14  5154.5  899.43  5182.8  906.61
  5216.3  910.97  5257.6  914.05  5278.2  914.57  5347.8  920.17  5412.2  922.91
#Mann= 3 ,-1 , 0
  4167.7     .12       0    5131     .05       0  5136.7     .12       0
Bank Sta=5131,5136.7
XS Rating Curve= 0 ,0
Exp/Cntr=0.3,0.1

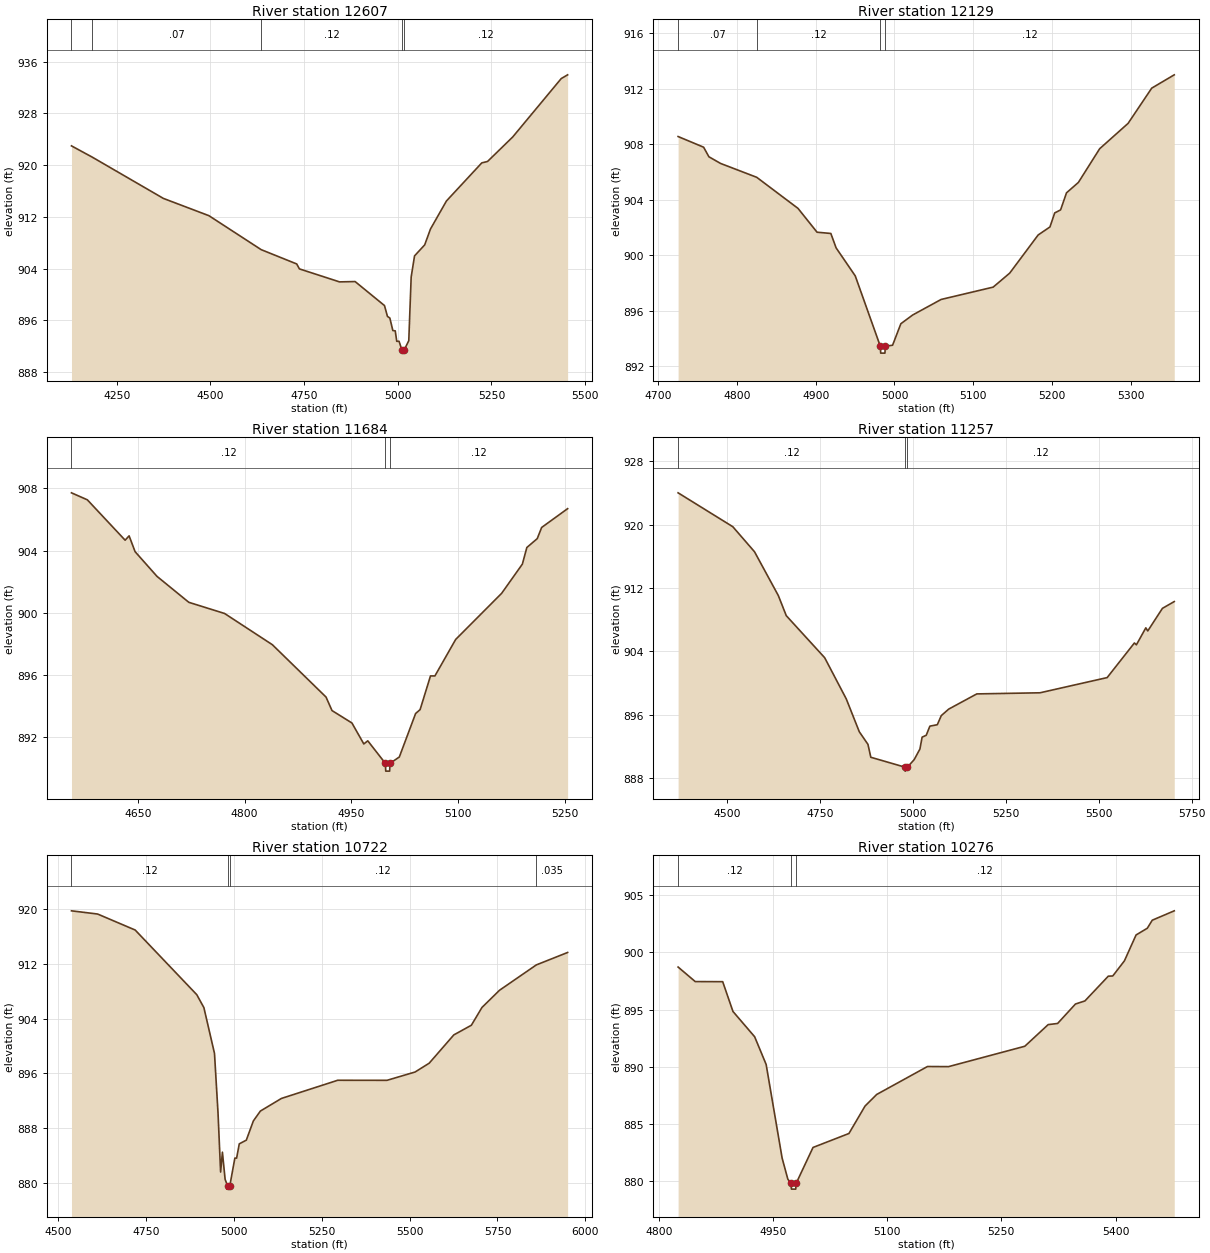
Type RM Length L Ch R = 1 ,12607   ,478,478,478
BEGIN DESCRIPTION:
Bear Creek Tributary 14 27.0
END DESCRIPTION:
XS GIS Cut Line= 3
      2188472.96     13799702.31        2187925.       13799025.
      2187685.94     13798640.47
#Sta/Elev= 30
  4129.3  922.98    4185  921.23  4374.6  914.86  4496.1  912.19  4635.6  906.94
  4730.4  904.73  4737.5  903.97  4844.6  901.96  4886.2  902.01  4964.6   898.3
  4972.5  896.63  4978.9  896.37  4986.9  894.44  4993.3  894.39  4997.3  892.78
  5003.5  892.78  5010.9  891.45  5011.4  890.95  5017.2  891.45  5029.4  892.87
  5035.8  902.71  5044.8  905.98  5071.9  907.68  5087.3  910.13    5130  914.47
  5224.2  920.35  5239.6  920.57  5306.7  924.35  5436.2  933.38  5453.3  933.96
#Mann= 5 ,-1 , 0
  4129.3     .12       0    4185     .07       0  4635.6     .12       0
  5010.9     .05       0  5017.2     .12       0
Bank Sta=5010.9,5017.2
XS Rating Curve= 0 ,0
Exp/Cntr=0.3,0.1

Type RM Length L Ch R = 1 ,12129   ,445,445,445
BEGIN DESCRIPTION:
Bear Creek Tributary 14 26.0
END DESCRIPTION:
XS GIS Cut Line= 3
      2188475.02     13799175.04        2188375.       13798925.
      2188074.96     13798724.98
#Sta/Elev= 30
  4725.3  908.56  4757.7  907.79  4764.4   907.1  4779.2  906.62  4825.1  905.62
  4877.5  903.38  4901.7  901.66  4919.2  901.57  4925.9  900.53  4950.2  898.51
    4982  893.44  4982.5  892.94  4987.9  892.94  4988.4  893.44  4997.6  893.51
  5008.1  895.06  5023.1  895.69  5059.2  896.81  5125.3   897.7  5146.3  898.71
  5182.4  901.46  5197.4  902.04  5203.4  903.05  5210.9  903.27  5218.4   904.5
  5233.5  905.25  5260.5  907.68  5296.6  909.51  5326.6  912.05  5355.2  913.01
#Mann= 4 ,-1 , 0
  4725.3     .07       0  4825.1     .12       0    4982     .05       0
  4988.4     .12       0
Bank Sta=4982,4988.4
XS Rating Curve= 0 ,0
Exp/Cntr=0.3,0.1

Type RM Length L Ch R = 1 ,11684   ,427,427,427
BEGIN DESCRIPTION:
Bear Creek Tributary 14 25.0
END DESCRIPTION:
XS GIS Cut Line= 3
      2188874.98     13799024.97        2188675.       13798625.
      2188524.99     13798424.98
#Sta/Elev= 30
  4556.7  907.72    4579  907.27  4632.1  904.67  4637.7  904.95  4646.1  903.93
  4676.9  902.34  4721.6  900.67  4771.9  899.95    4839  897.94  4914.4  894.57
  4922.8   893.7  4950.8   892.9  4967.5  891.55  4973.1  891.75  4997.8   890.3
  4998.3   889.8  5003.8   889.8  5004.3   890.3  5017.4  890.71  5040.3  893.51
  5046.6  893.76  5061.2  895.93  5067.4  895.93  5096.6  898.28  5161.2  901.25
  5190.3  903.13  5196.6   904.2  5211.2  904.77  5217.4  905.49  5253.9   906.7
#Mann= 3 ,-1 , 0
  4556.7     .12       0  4997.8     .05       0  5004.3     .12       0
Bank Sta=4997.8,5004.3
XS Rating Curve= 0 ,0
Exp/Cntr=0.3,0.1

Type RM Length L Ch R = 1 ,11257   ,535,535,535
BEGIN DESCRIPTION:
Bear Creek Tributary 14 24.0
END DESCRIPTION:
XS GIS Cut Line= 3
      2189397.38     13799073.55      2189055.92     13798503.05
      2188425.04     13798275.02
#Sta/Elev= 30
  4367.5  924.01  4514.8  919.73  4573.2  916.57  4637.3  911.04  4658.7   908.5
  4762.1  903.19  4820.3  897.98  4855.3  893.84  4878.6  892.25  4886.3  890.62
  4978.3  889.37  4978.8  888.87  4984.8  889.37    5003  890.32  5018.5  891.66
  5024.4  893.16  5035.5   893.4  5045.3  894.55  5065.3  894.73    5076  895.88
    5096   896.7  5171.6  898.62  5341.7  898.76  5522.5  900.68  5595.9  905.05
  5601.3  904.82  5626.6  906.96  5631.9  906.57  5671.3  909.42  5703.2  910.28
#Mann= 3 ,-1 , 0
  4367.5     .12       0  4978.3     .05       0  4984.8     .12       0
Bank Sta=4978.3,4984.8
XS Rating Curve= 0 ,0
Exp/Cntr=0.3,0.1

Type RM Length L Ch R = 1 ,10722   ,446,446,446
BEGIN DESCRIPTION:
Bear Creek Tributary 14 23.0
END DESCRIPTION:
XS GIS Cut Line= 3
      2189688.81     13798232.38        2189225.       13798175.
       2188281.4      13798207.4
#Sta/Elev= 30
  4538.1  919.78  4612.5  919.31  4719.3  916.97  4894.6   907.5  4914.8  905.61
    4945   898.9  4955.1   890.1  4962.4  881.53  4967.5  884.44  4975.2  880.46
    4982  879.53  4982.5  879.03  4988.6  879.53  5002.9  883.57  5007.9  883.57
  5015.5  885.66  5035.5   886.2  5055.5  889.01  5075.5  890.46  5135.5  892.31
  5295.6  894.97  5435.7  894.96  5515.7  896.18  5555.8  897.47  5625.8  901.61
  5675.8  903.03  5705.9  905.63  5755.9  908.15  5860.5  911.86  5949.6  913.68
#Mann= 4 ,-1 , 0
  4538.1     .12       0    4982     .05       0  4988.6     .12       0
  5860.5    .035       0
Bank Sta=4982,4988.6
XS Rating Curve= 0 ,0
Exp/Cntr=0.3,0.1

Type RM Length L Ch R = 1 ,10276   ,469,469,469
BEGIN DESCRIPTION:
Bear Creek Tributary 14 22.0
END DESCRIPTION:
XS GIS Cut Line= 3
      2189074.98     13797775.01        2188925.       13797875.
      2188524.96     13798125.02
#Sta/Elev= 30
  4825.2  898.72  4847.7  897.45  4883.8  897.44  4897.3  894.84  4925.8  892.63
  4940.9  890.21  4961.9  882.03  4969.4  880.19  4973.6  879.82  4974.1  879.32
  4979.8  879.32  4980.3  879.82  5002.5  882.96  5049.7  884.18  5070.9  886.58
  5086.2  887.59  5152.9  890.03  5180.6  890.02  5280.8   891.8  5311.5  893.69
  5323.9  893.79  5347.4  895.49  5359.8  895.76  5390.5  897.92  5396.4  897.94
  5411.7  899.26    5427  901.52  5441.8  902.11  5448.3  902.81  5477.2  903.63
#Mann= 3 ,-1 , 0
  4825.2     .12       0  4973.6     .05       0  4980.3     .12       0
Bank Sta=4973.6,4980.3
XS Rating Curve= 0 ,0
Exp/Cntr=0.3,0.1

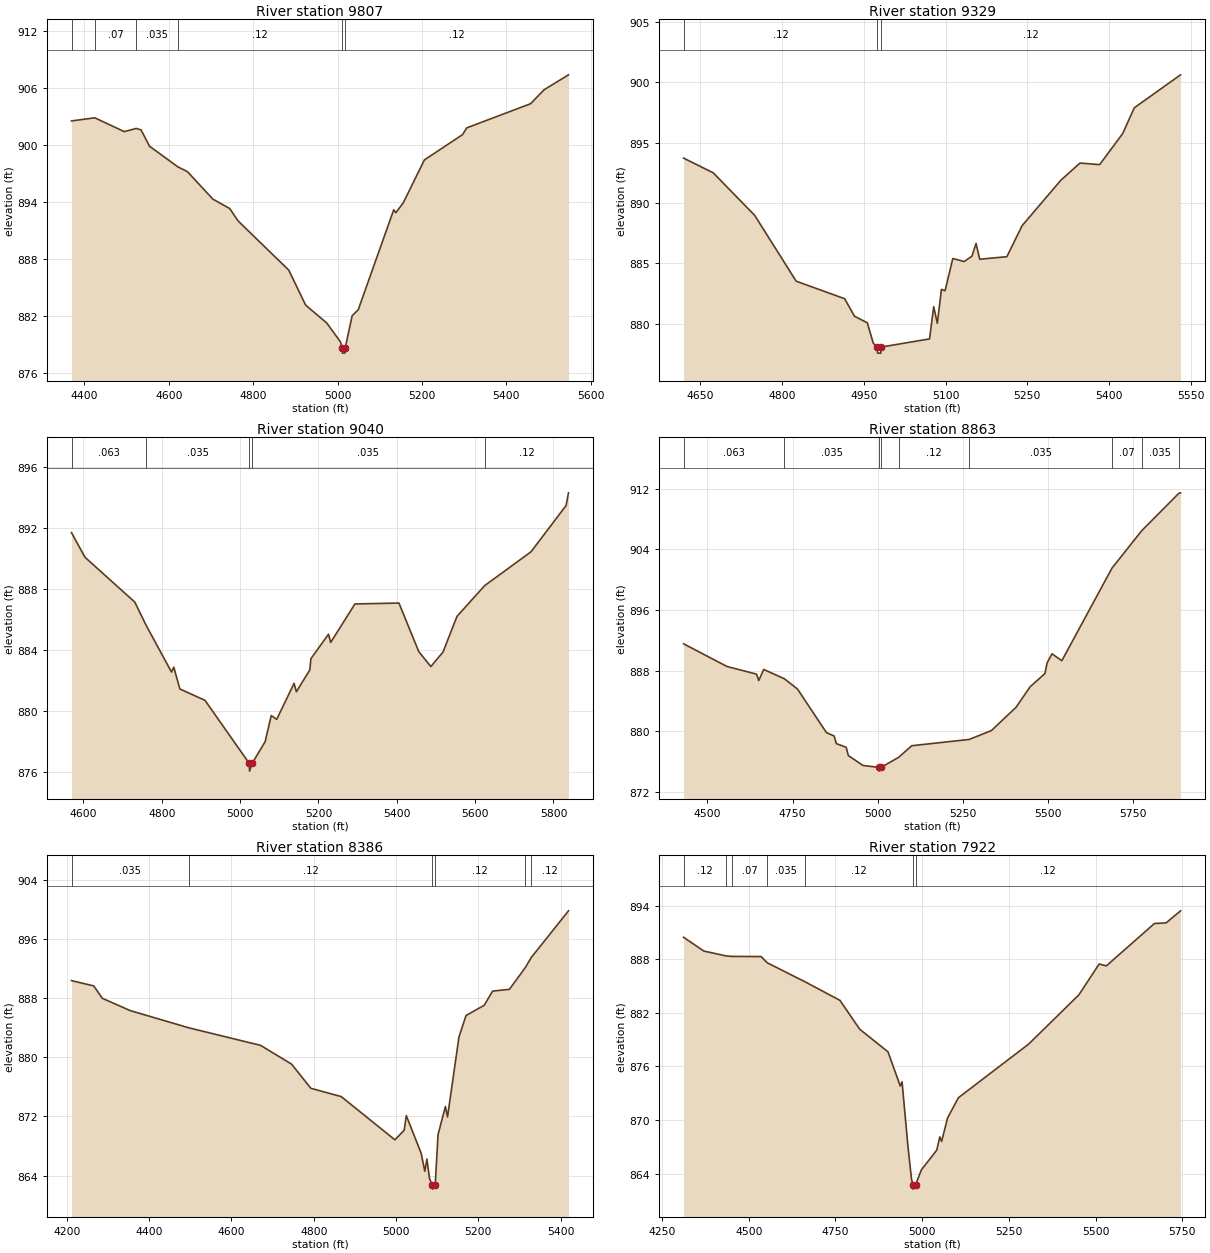
Type RM Length L Ch R = 1 ,9807    ,478,478,478
BEGIN DESCRIPTION:
Bear Creek Tributary 14 21.0
END DESCRIPTION:
XS GIS Cut Line= 3
      2189259.92     13797520.33        2188625.       13797525.
      2188085.69     13797586.96
#Sta/Elev= 30
  4369.3  902.52  4424.4  902.85  4494.2   901.4  4522.9  901.73  4534.2  901.57
  4554.2  899.86  4621.4  897.69  4644.2  897.18  4704.2   894.3  4744.2  893.31
  4764.2     892  4884.2  886.83  4924.2  883.15  4974.2  881.27  5006.8  879.28
  5010.9   878.6  5011.4   878.1  5017.2   878.1  5017.7   878.6  5034.4  882.03
  5048.8  882.66  5132.9  893.17  5137.9  892.87  5155.2  893.88  5205.6  898.42
  5296.1  901.08    5306  901.79  5457.2  904.33  5489.3   905.8  5547.1  907.37
#Mann= 6 ,-1 , 0
  4369.3    .035       0  4424.4     .07       0  4522.9    .035       0
  4621.4     .12       0  5010.9     .05       0  5017.7     .12       0
Bank Sta=5010.9,5017.7
XS Rating Curve= 0 ,0
Exp/Cntr=0.3,0.1

Type RM Length L Ch R = 1 ,9329    ,289,289,289
BEGIN DESCRIPTION:
Bear Creek Tributary 14 20.0
END DESCRIPTION:
XS GIS Cut Line= 3
      2188975.01     13797225.01        2188625.       13797075.
      2188225.01     13797424.99
#Sta/Elev= 30
  4619.1  893.72  4673.5   892.5  4749.7  888.97  4825.8  883.52  4914.7  882.07
  4932.8  880.62  4956.4  880.07  4967.3  878.38  4974.7  878.06  4975.2  877.56
  4981.1  877.56  4981.6  878.06  5070.6  878.74  5078.2  881.41  5084.9  880.03
  5092.4  882.84  5099.1  882.73  5113.3   885.4  5134.2  885.15  5148.4  885.59
    5156  886.65  5162.7  885.34  5212.5  885.55  5240.5  888.12  5311.7  891.89
  5346.8  893.31  5382.9  893.18  5425.1  895.75  5446.5  897.89  5531.4  900.62
#Mann= 3 ,-1 , 0
  4619.1     .12       0  4974.7     .05       0  4981.6     .12       0
Bank Sta=4974.7,4981.6
XS Rating Curve= 0 ,0
Exp/Cntr=0.3,0.1

Type RM Length L Ch R = 1 ,9040    ,177,177,177
BEGIN DESCRIPTION:
Bear Creek Tributary 14 19.5
END DESCRIPTION:
XS GIS Cut Line= 4
      2189007.26     13797071.35      2188837.32     13796899.85
      2188522.41     13796711.22       2187929.5     13796420.21
#Sta/Elev= 30
  4569.4  891.67  4603.8  890.06  4731.1  887.12  4759.8  885.61  4824.7  882.54
  4830.5  882.86  4846.1  881.43  4910.2  880.69  5023.5  876.55    5024  876.05
  5030.4  876.55  5063.8  877.98  5079.4  879.69  5093.3  879.44  5137.7   881.8
  5143.6  881.25  5177.9  882.68  5180.6  883.41  5225.6  885.02  5231.2  884.48
  5293.1     887  5405.5  887.06  5456.1  883.88  5486.9   882.9    5518  883.85
  5553.8  886.19  5624.3   888.2  5742.8  890.42  5832.3  893.45  5838.4  894.28
#Mann= 5 ,-1 , 0
  4569.4    .063       0  4759.8    .035       0  5023.5    .035       0
  5030.4    .035       0  5624.3     .12       0
Bank Sta=5023.5,5030.4
XS Rating Curve= 0 ,0
Exp/Cntr=0.3,0.1

Type RM Length L Ch R = 1 ,8863    ,477,477,477
BEGIN DESCRIPTION:
Bear Creek Tributary 14 19.0
END DESCRIPTION:
XS GIS Cut Line= 3
      2189024.99     13797074.99        2188675.       13796625.
        2187975.       13796075.
#Sta/Elev= 30
  4429.9  891.56  4557.5  888.57  4644.3  887.56  4650.7  886.71  4665.2  888.18
  4726.1  886.95  4764.7  885.59  4849.8  879.84  4872.4   879.4  4878.7   878.4
  4907.7  877.91    4914  876.82  4957.4  875.51  5003.7  875.27  5004.2  874.77
  5010.6  875.27    5062   876.6  5100.3  878.12  5269.3  878.95  5334.4  880.12
  5406.6  883.18  5448.3   885.9  5491.6  887.63    5498  889.04  5512.4  890.24
  5541.3  889.33  5688.8  901.55  5776.4  906.49  5884.9   911.4  5890.2  911.47
#Mann= 9 ,-1 , 0
  4429.9    .063       0  4726.1    .035       0  5003.7    .035       0
  5010.6    .035       0    5062     .12       0  5269.3    .035       0
  5688.8     .07       0  5776.4    .035       0  5884.9     .07       0
Bank Sta=5003.7,5010.6
XS Rating Curve= 0 ,0
Exp/Cntr=0.3,0.1

Type RM Length L Ch R = 1 ,8386    ,464,464,464
BEGIN DESCRIPTION:
Bear Creek Tributary 14 18.0
END DESCRIPTION:
XS GIS Cut Line= 3
      2189126.71      13797037.3        2188925.       13796275.
      2188839.69      13795864.5
#Sta/Elev= 30
  4211.3  890.37  4265.4  889.65  4286.1  887.98  4354.1  886.31  4496.6  883.98
  4670.8  881.61  4746.1  879.07    4793   875.8  4866.8  874.68  4997.2  868.83
  5019.8  870.13  5024.9  872.11  5061.1  867.01  5069.9  864.58    5075  866.23
  5081.5  863.56  5088.3  862.66  5088.8  862.16  5095.2  862.66    5102  869.51
    5120  873.34  5125.1  871.92    5153  882.76  5170.1  885.65  5214.3  887.03
  5234.7  888.95  5275.6  889.19  5313.7   892.1    5329  893.52  5419.1  899.81
#Mann= 6 ,-1 , 0
  4211.3    .035       0  4496.6     .12       0  5088.3     .05       0
  5095.2     .12       0  5313.7     .07       0    5329     .12       0
Bank Sta=5088.3,5095.2
XS Rating Curve= 0 ,0
Exp/Cntr=0.3,0.1

Type RM Length L Ch R = 1 ,7922    ,475,475,475
BEGIN DESCRIPTION:
Bear Creek Tributary 14 17.0
END DESCRIPTION:
XS GIS Cut Line= 3
      2189447.34     13797141.42        2189275.       13796475.
      2189068.55     13795759.43
#Sta/Elev= 30
  4312.1  890.45  4370.4  888.91  4433.7  888.37  4450.6  888.31  4535.6  888.29
  4553.1   887.6  4661.6  885.48  4762.9  883.39  4820.2  880.15  4901.5  877.63
  4936.9   873.8  4942.1  874.27  4959.1  867.04  4969.5  863.33  4973.9  862.76
  4974.4  862.26  4981.2  862.76  4997.9  864.43  5042.1  866.62  5050.9  868.11
  5056.1   867.6  5073.3  870.22  5104.5  872.49  5307.3   878.5  5452.3  884.02
  5510.4  887.46  5531.2  887.25  5669.8  891.99  5703.4  892.06  5745.2  893.41
#Mann= 7 ,-1 , 0
  4312.1     .12       0  4433.7    .035       0  4450.6     .07       0
  4553.1    .035       0  4661.6     .12       0  4973.9     .05       0
  4981.2     .12       0
Bank Sta=4973.9,4981.2
XS Rating Curve= 0 ,0
Exp/Cntr=0.3,0.1