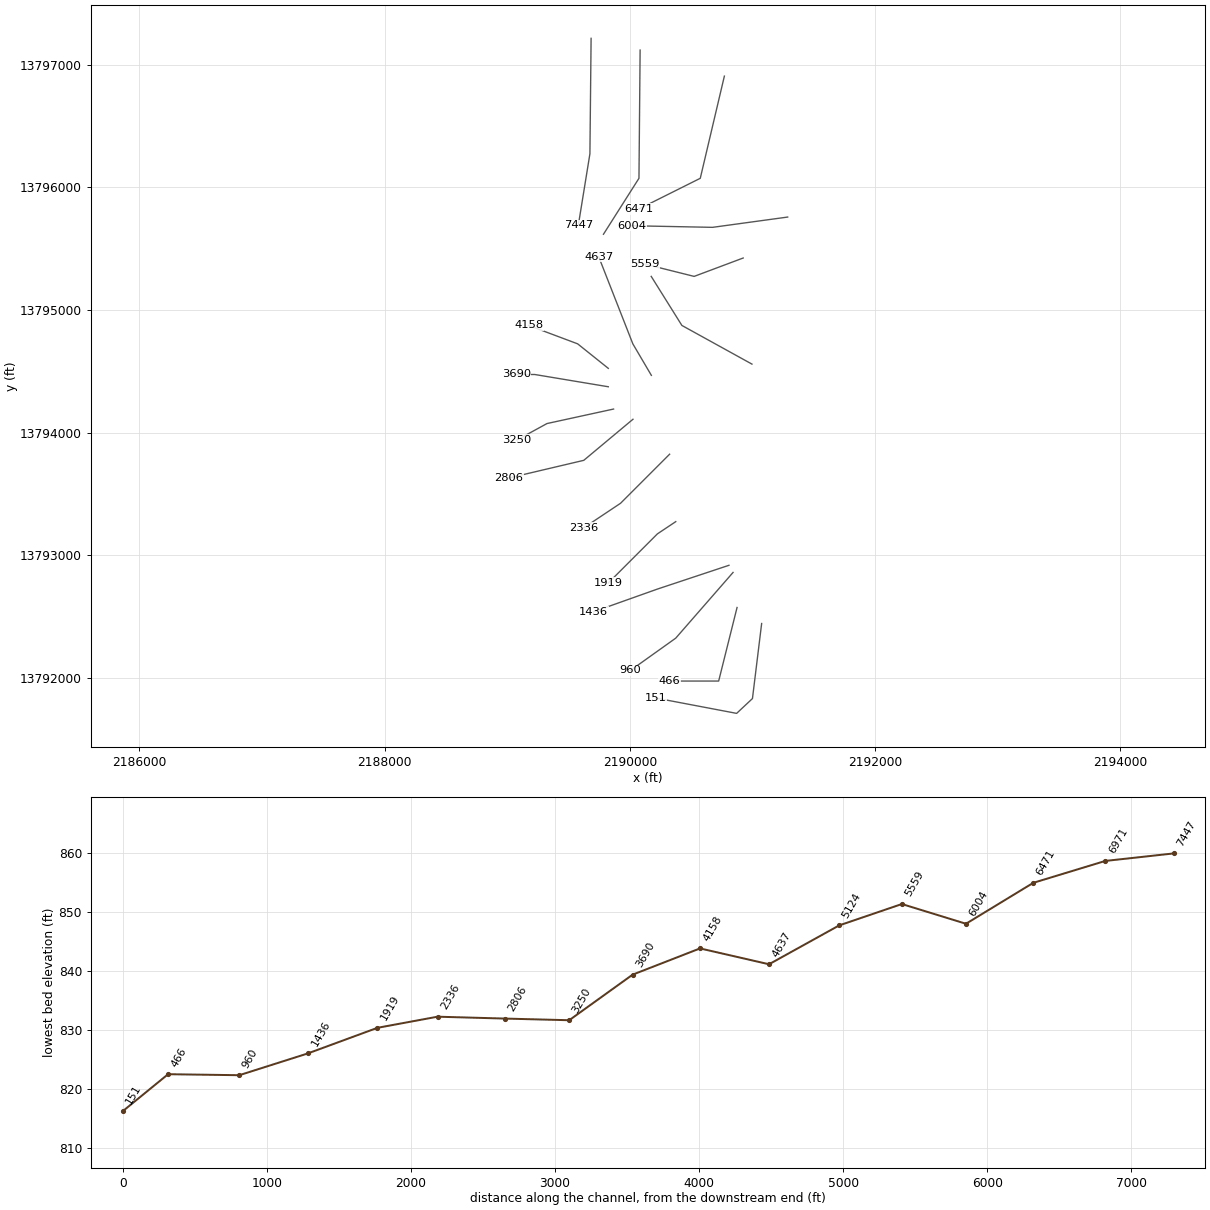
HEC-RAS study Bear Creek Tributary 14.prj: Bear Creek Tributary 14 Base Level Engineering

--- Bear Creek Tributary 14.g01 (geometry) --- (continued)

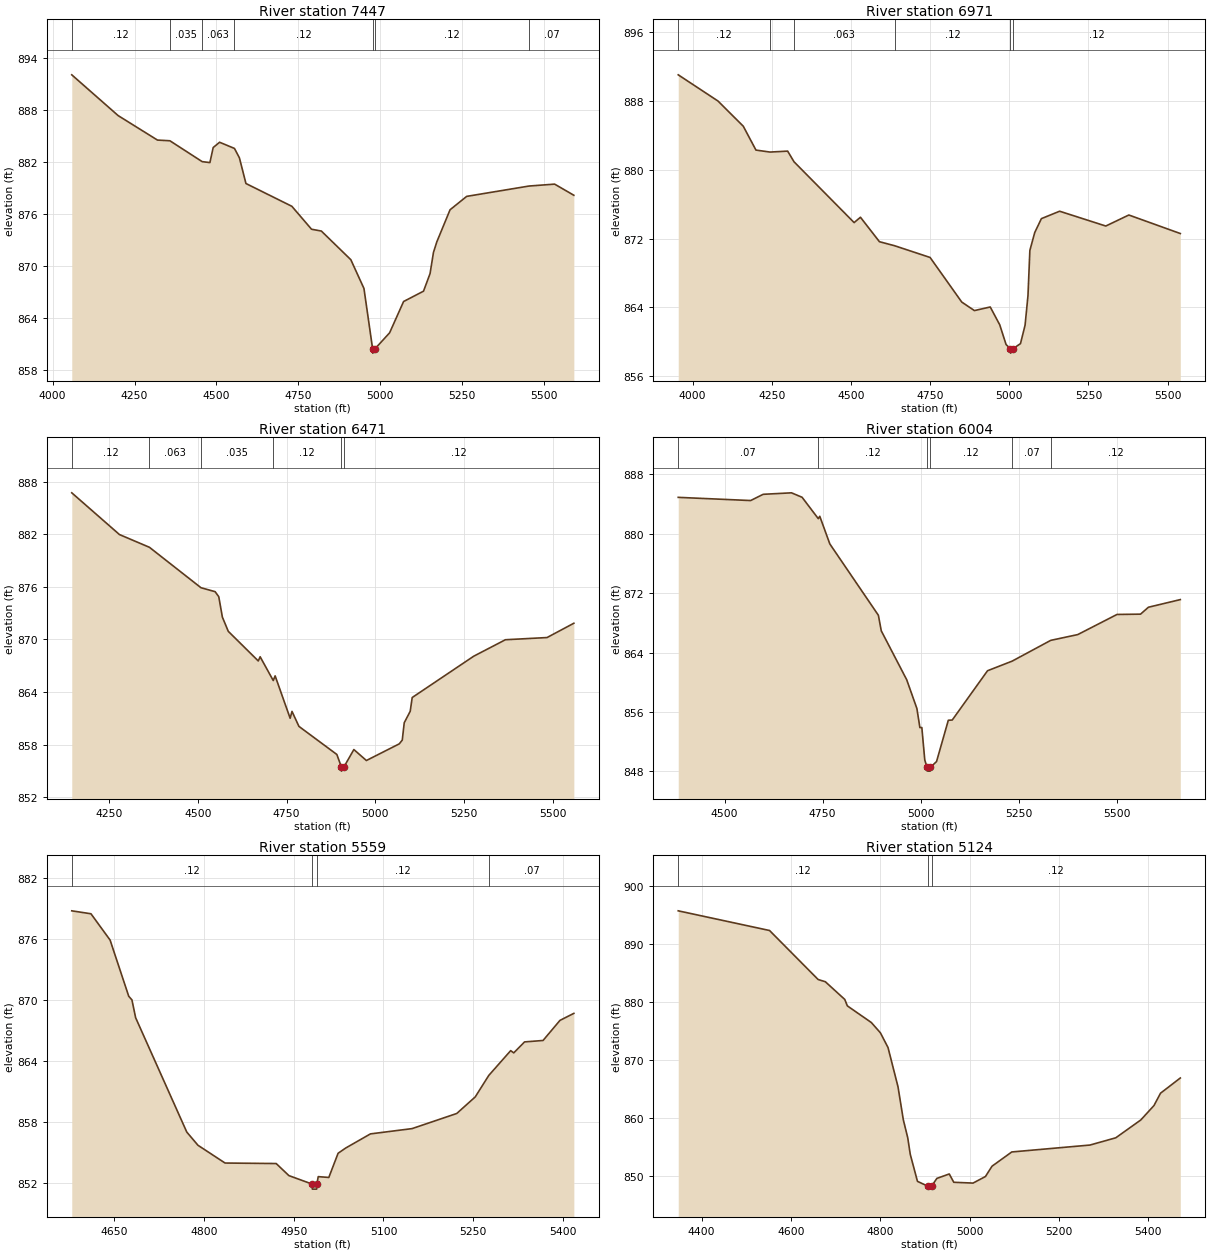
Type RM Length L Ch R = 1 ,7447    ,476,476,476
BEGIN DESCRIPTION:
Bear Creek Tributary 14 16.0
END DESCRIPTION:
XS GIS Cut Line= 3
      2189684.69     13797216.36        2189675.       13796275.
      2189580.59     13795692.31
#Sta/Elev= 30
  4058.6  892.01    4200  887.32    4320   884.5    4358  884.42  4456.4  882.02
    4480  881.91    4490  883.64  4509.6  884.25  4554.9  883.54    4570  882.46
    4590   879.5    4730  876.88    4790  874.24    4820  874.03    4910  870.73
    4950  867.42  4976.4  860.48  4976.9  859.98  4983.7  860.48  5028.3  862.32
  5070.9  865.92  5131.7  867.11  5151.6  869.13  5162.1  871.58  5172.2  872.78
  5212.7  876.48  5263.4  878.02  5453.5  879.21  5531.7  879.43  5590.3  878.15
#Mann= 7 ,-1 , 0
  4058.6     .12       0    4358    .035       0  4456.4    .063       0
  4554.9     .12       0  4976.4     .05       0  4983.7     .12       0
  5453.5     .07       0
Bank Sta=4976.4,4983.7
XS Rating Curve= 0 ,0
Exp/Cntr=0.3,0.1

Type RM Length L Ch R = 1 ,6971    ,500,500,500
BEGIN DESCRIPTION:
Bear Creek Tributary 14 15.0
END DESCRIPTION:
XS GIS Cut Line= 3
      2190084.44     13797120.54        2190075.       13796075.
      2189785.47     13795618.68
#Sta/Elev= 30
  3954.4  891.02  4079.9  887.98  4159.9  885.05  4199.9  882.28  4244.3  882.05
    4300  882.16  4320.2  880.92    4510  873.86    4530  874.48    4590  871.64
  4638.1  871.17    4750  869.81    4850  864.63    4890  863.64    4940  864.06
    4970  861.99    4990   859.7  5003.9   859.2  5004.4   858.7  5011.3   859.2
  5035.5   859.8    5050  861.94  5059.2  865.38  5065.2  870.63  5080.5   872.7
  5101.6  874.32  5159.2  875.18    5305  873.46  5377.8  874.74  5540.4  872.59
#Mann= 6 ,-1 , 0
  3954.4     .12       0  4244.3    .035       0  4320.2    .063       0
  4638.1     .12       0  5003.9     .05       0  5011.3     .12       0
Bank Sta=5003.9,5011.3
XS Rating Curve= 0 ,0
Exp/Cntr=0.3,0.1

Type RM Length L Ch R = 1 ,6471    ,467,467,467
BEGIN DESCRIPTION:
Bear Creek Tributary 14 14.0
END DESCRIPTION:
XS GIS Cut Line= 3
       2190771.5     13796908.19        2190575.       13796075.
      2190074.97     13795824.98
#Sta/Elev= 30
  4144.4  886.71  4278.9  881.95  4363.3   880.5  4508.6  875.89  4548.4  875.44
  4558.7  874.87  4568.9  872.54  4585.5  870.92  4670.1  867.54  4675.3  868.02
  4712.3  865.31  4717.6  865.84  4759.9  861.01  4765.1  861.79  4784.7  860.08
  4891.5  856.88  4904.1  855.48  4904.6  854.98  4911.8  855.48  4939.5  857.44
  4974.8  856.19  5067.5  858.09  5075.9  858.52  5081.5   860.5  5098.3   861.8
  5103.9  863.37  5277.2  868.08  5366.6  869.96    5484  870.21  5559.5  871.84
#Mann= 6 ,-1 , 0
  4144.4     .12       0  4363.3    .063       0  4508.6    .035       0
  4712.3     .12       0  4904.1     .05       0  4911.8     .12       0
Bank Sta=4904.1,4911.8
XS Rating Curve= 0 ,0
Exp/Cntr=0.3,0.1

Type RM Length L Ch R = 1 ,6004    ,445,445,445
BEGIN DESCRIPTION:
Bear Creek Tributary 14 13.0
END DESCRIPTION:
XS GIS Cut Line= 3
      2191287.88     13795758.94        2190675.       13795675.
      2190013.63     13795688.15
#Sta/Elev= 30
  4381.8   884.9  4566.4  884.47  4598.4  885.31  4670.6  885.51  4697.6  884.91
  4738.9  882.03  4742.7  882.35  4768.3  878.63  4892.1  869.02  4899.5  866.92
  4964.3  860.34  4990.3  856.46  4997.9   853.9  5002.9   853.9  5010.4  849.52
  5016.4  848.53  5016.9  848.03  5023.9  848.03  5024.4  848.53  5040.4  849.32
  5070.4  854.88  5080.4  854.91  5170.4  861.55    5233  862.84  5331.5  865.64
  5400.5  866.42  5500.5  869.13  5560.5  869.17  5580.5   870.1  5661.9  871.13
#Mann= 6 ,-1 , 0
  4381.8     .07       0  4738.9     .12       0  5016.4     .05       0
  5024.4     .12       0    5233     .07       0  5331.5     .12       0
Bank Sta=5016.4,5024.4
XS Rating Curve= 0 ,0
Exp/Cntr=0.3,0.1

Type RM Length L Ch R = 1 ,5559    ,435,435,435
BEGIN DESCRIPTION:
Bear Creek Tributary 14 12.0
END DESCRIPTION:
XS GIS Cut Line= 3
      2190925.02     13795425.01        2190525.       13795275.
      2190125.03     13795374.99
#Sta/Elev= 30
  4578.8  878.79  4610.9   878.5  4642.9  875.91  4674.1  870.37  4679.4  870.02
  4685.6  868.26  4771.1     857  4789.8   855.7  4835.1  853.95  4920.6   853.9
  4941.9  852.71  4980.6  851.88  4981.1  851.38  4988.2  851.38  4988.7  851.88
  4990.9  852.61  5008.6  852.53  5024.1  854.91  5036.9  855.43  5078.2  856.82
  5147.8  857.34  5222.5  858.83  5253.4  860.46  5276.1  862.58  5312.7  865.02
  5317.8   864.8  5335.9  865.88  5366.8  866.02  5395.1     868  5418.3  868.69
#Mann= 4 ,-1 , 0
  4578.8     .12       0  4980.6     .05       0  4988.7     .12       0
  5276.1     .07       0
Bank Sta=4980.6,4988.7
XS Rating Curve= 0 ,0
Exp/Cntr=0.3,0.1

Type RM Length L Ch R = 1 ,5124    ,487,487,487
BEGIN DESCRIPTION:
Bear Creek Tributary 14 11.0
END DESCRIPTION:
XS GIS Cut Line= 3
      2190996.34     13794559.71        2190425.       13794875.
      2190174.98     13795275.03
#Sta/Elev= 30
  4347.5  895.68    4552  892.29  4660.8  883.85  4676.9  883.47  4720.4  880.42
  4726.2  879.31    4780  876.44  4800.2  874.67  4817.3  872.13  4839.6  865.39
  4851.6  859.67  4861.4  856.61  4867.1  853.74  4883.2  849.09  4906.6  848.25
  4907.1  847.75  4914.7  848.25  4926.7   849.6  4954.4  850.36  4964.5  848.93
  5007.7  848.79  5035.4  849.92  5050.2   851.7  5094.4  854.15  5269.5  855.34
  5327.3  856.59  5383.3  859.66  5412.8  862.14  5427.5  864.27  5471.8  866.89
#Mann= 3 ,-1 , 0
  4347.5     .12       0  4906.6     .05       0  4914.7     .12       0
Bank Sta=4906.6,4914.7
XS Rating Curve= 0 ,0
Exp/Cntr=0.3,0.1

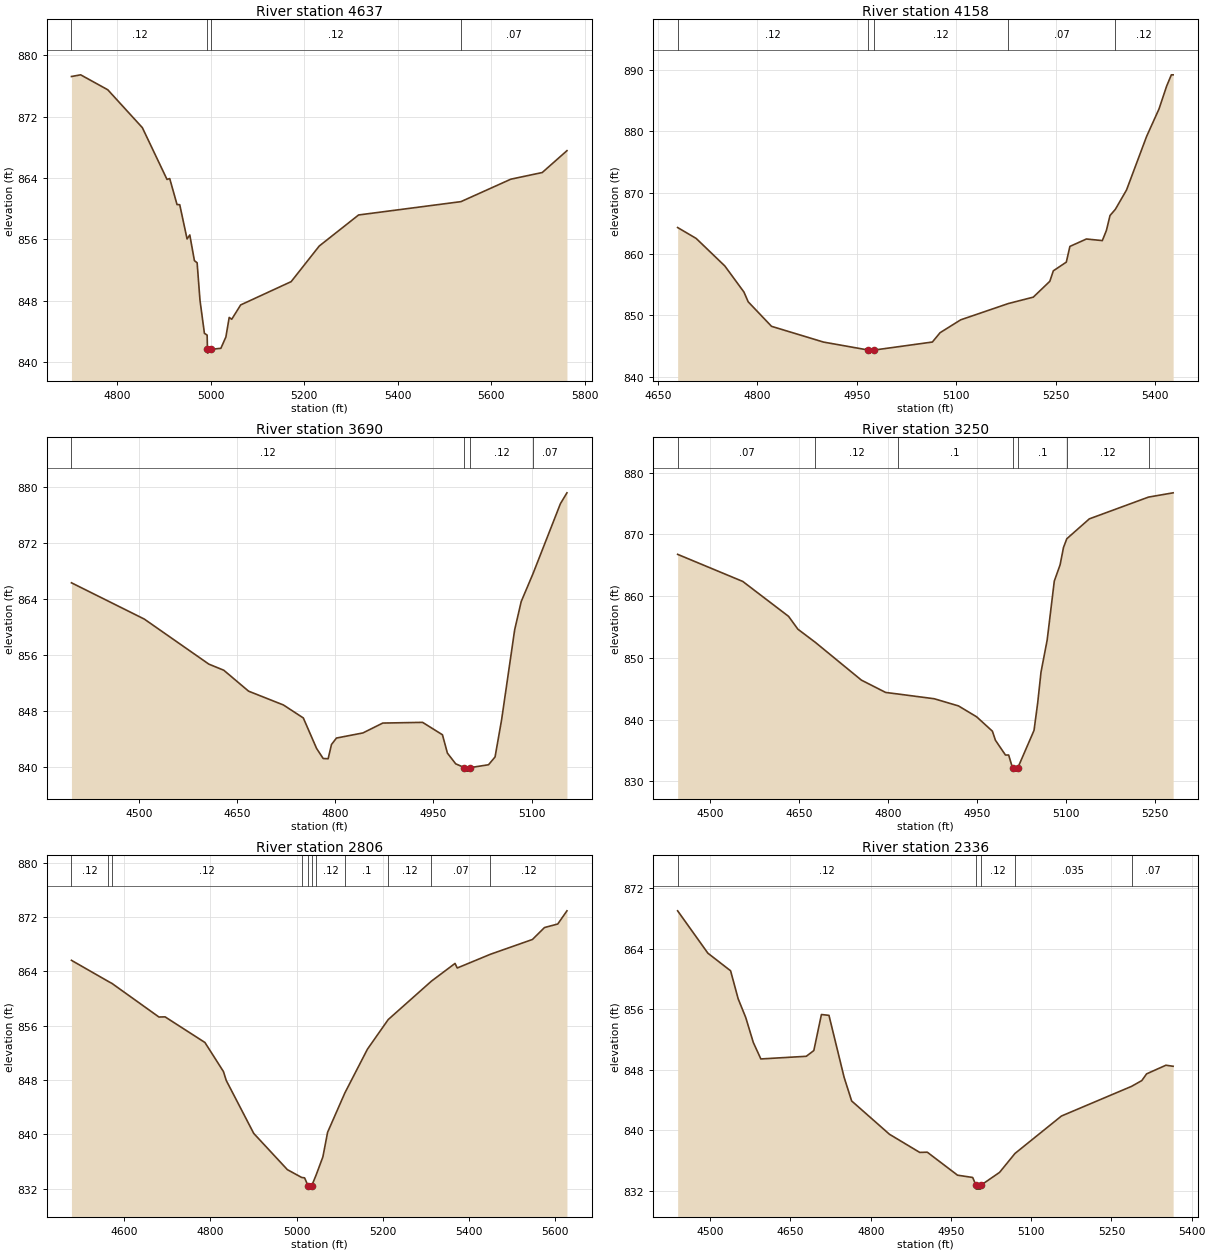
Type RM Length L Ch R = 1 ,4637    ,479,479,479
BEGIN DESCRIPTION:
Bear Creek Tributary 14 10.0
END DESCRIPTION:
XS GIS Cut Line= 3
      2190176.07     13794468.04        2190025.       13794725.
      2189747.15     13795434.14
#Sta/Elev= 30
  4701.9  877.25  4721.6  877.47  4779.6  875.52  4853.5  870.58  4906.3  863.82
  4912.1  863.93  4927.7  860.54  4933.5  860.52  4949.2  856.05    4955  856.57
  4964.9  853.22  4970.7  852.94  4976.8  848.06  4986.3  843.73  4992.1  843.51
  4992.8  841.65  4993.3  841.15  5001.3  841.65  5021.5  841.78  5032.2  843.26
  5039.3  845.81  5044.7  845.57  5063.8  847.44  5171.8  850.48  5231.9  855.13
    5316  859.18  5534.9  860.92  5641.6  863.85  5708.8  864.72  5761.6  867.57
#Mann= 4 ,-1 , 0
  4701.9     .12       0  4992.8     .05       0  5001.3     .12       0
  5534.9     .07       0
Bank Sta=4992.8,5001.3
XS Rating Curve= 0 ,0
Exp/Cntr=0.3,0.1

Type RM Length L Ch R = 1 ,4158    ,468,468,468
BEGIN DESCRIPTION:
Bear Creek Tributary 14 9.0
END DESCRIPTION:
XS GIS Cut Line= 3
      2189824.97     13794525.03        2189575.       13794725.
      2189175.01       13794875.
#Sta/Elev= 30
  4679.6  864.32  4707.6  862.54  4750.8  858.05  4779.6   853.8    4786  852.21
  4821.2  848.21  4899.7  845.64  4967.4  844.34  4967.9  843.84    4976  844.34
  5063.8  845.65  5075.4  847.17  5106.5  849.27  5178.2  851.92    5216  852.97
  5240.9  855.55  5246.2  857.26  5265.8  858.68  5271.2  861.24  5296.1  862.45
  5320.1  862.19  5326.3  863.86  5331.7  866.28  5339.7  867.28  5356.6  870.44
  5386.9  879.18  5405.6  883.66  5417.1  887.38  5424.2  889.22  5426.9  889.22
#Mann= 5 ,-1 , 0
  4679.6     .12       0  4967.4     .05       0    4976     .12       0
  5178.2     .07       0  5339.7     .12       0
Bank Sta=4967.4,4976
XS Rating Curve= 0 ,0
Exp/Cntr=0.3,0.1

Type RM Length L Ch R = 1 ,3690    ,440,440,440
BEGIN DESCRIPTION:
Bear Creek Tributary 14 8.0
END DESCRIPTION:
XS GIS Cut Line= 3
      2189824.96     13794375.01        2189225.       13794475.
      2189075.04       13794475.
#Sta/Elev= 30
    4396  866.26  4507.5  861.08  4606.3  854.65  4629.1  853.78  4667.1  850.79
  4720.4  848.82  4750.8  846.97  4771.1  842.62  4781.2  841.18  4788.8  841.15
  4793.9  843.18  4801.5   844.1    4842  844.83  4872.4  846.24  4933.3  846.34
  4963.7  844.57  4971.3  841.95    4984  840.42  4997.4  839.88  4997.9  839.38
  5005.6  839.38  5006.1  839.88  5034.2  840.29  5044.2   841.4  5054.2   846.7
  5074.2  859.55  5084.2  863.58  5102.3  867.57  5144.2  877.55  5154.2   879.1
#Mann= 4 ,-1 , 0
    4396     .12       0  4997.4     .05       0  5006.1     .12       0
  5102.3     .07       0
Bank Sta=4997.4,5006.1
XS Rating Curve= 0 ,0
Exp/Cntr=0.3,0.1

Type RM Length L Ch R = 1 ,3250    ,444,444,444
BEGIN DESCRIPTION:
Bear Creek Tributary 14 7.0
END DESCRIPTION:
XS GIS Cut Line= 3
      2189867.94     13794193.26        2189325.       13794075.
      2189079.04      13793940.5
#Sta/Elev= 30
  4444.6  866.77  4554.5  862.38  4631.8  856.72  4647.5  854.64  4676.8  852.52
  4754.6  846.39  4795.6  844.39  4816.2  844.14  4877.5  843.37  4918.4  842.21
  4949.1  840.44  4975.7  838.11  4980.8  836.64  4997.7  834.25  5003.1  834.25
  5009.7  832.14  5010.2  831.64  5017.9  831.64  5018.4  832.14  5045.9  838.24
    5052  842.63  5057.7   847.7  5068.1   852.9  5080.1  862.44  5089.9  865.08
  5095.6  867.88  5101.2   869.3  5139.2  872.52  5239.1  876.05  5280.6  876.74
#Mann= 7 ,-1 , 0
  4444.6     .07       0  4676.8     .12       0  4816.2      .1       0
  5009.7     .05       0  5018.4      .1       0  5101.2     .12       0
  5239.1     .07       0
Bank Sta=5009.7,5018.4
XS Rating Curve= 0 ,0
Exp/Cntr=0.3,0.1

Type RM Length L Ch R = 1 ,2806    ,470,470,470
BEGIN DESCRIPTION:
Bear Creek Tributary 14 6.0
END DESCRIPTION:
XS GIS Cut Line= 3
      2190026.17     13794109.99        2189625.       13793775.
      2189014.26      13793631.1
#Sta/Elev= 30
  4477.4  865.62  4563.3   862.5  4571.4  862.22  4680.5  857.27  4694.8  857.29
  4787.2  853.52  4830.2  849.24  4836.7  847.93  4900.5  840.13  4978.6  834.79
  5011.7  833.64  5018.6  833.58  5026.5  832.42    5027  831.92  5034.7  831.92
  5035.2  832.42  5045.7  834.06    5061  836.67    5072   840.3  5112.2  846.11
  5164.4  852.53  5212.6  856.89  5313.1  862.56  5367.7  865.16  5372.9  864.49
  5449.8  866.51  5547.4  868.69  5575.4  870.45  5606.2  870.97  5627.5  872.91
#Mann= 11 ,-1 , 0
  4477.4     .12       0  4563.3     .07       0  4571.4     .12       0
  5011.7      .1       0  5026.5     .05       0  5035.2      .1       0
  5045.7     .12       0  5112.2      .1       0  5212.6     .12       0
  5313.1     .07       0  5449.8     .12       0
Bank Sta=5026.5,5035.2
XS Rating Curve= 0 ,0
Exp/Cntr=0.3,0.1

Type RM Length L Ch R = 1 ,2336    ,417,417,417
BEGIN DESCRIPTION:
Bear Creek Tributary 14 5.0
END DESCRIPTION:
XS GIS Cut Line= 3
      2190325.04     13793825.04        2189925.       13793425.
      2189624.99     13793224.99
#Sta/Elev= 30
  4439.1  869.01  4495.7  863.41  4538.1  861.09  4552.3  857.38  4566.4  854.92
  4580.6  851.61  4594.7  849.44  4679.6  849.79  4693.7  850.55  4707.9  855.31
    4722   855.2  4750.3  847.02  4764.4  843.89  4835.1  839.49  4891.7  837.09
  4905.8  837.12  4962.4  834.08  4990.7  833.78  4996.8  832.74  4997.3  832.24
  5005.2  832.24  5005.7  832.74  5040.9  834.45  5069.7  836.95  5156.6   841.9
  5287.7  845.82  5306.8  846.58  5315.8  847.47  5351.9  848.61  5365.4  848.47
#Mann= 5 ,-1 , 0
  4439.1     .12       0  4996.8     .05       0  5005.7     .12       0
  5069.7    .035       0  5287.7     .07       0
Bank Sta=4996.8,5005.7
XS Rating Curve= 0 ,0
Exp/Cntr=0.3,0.1

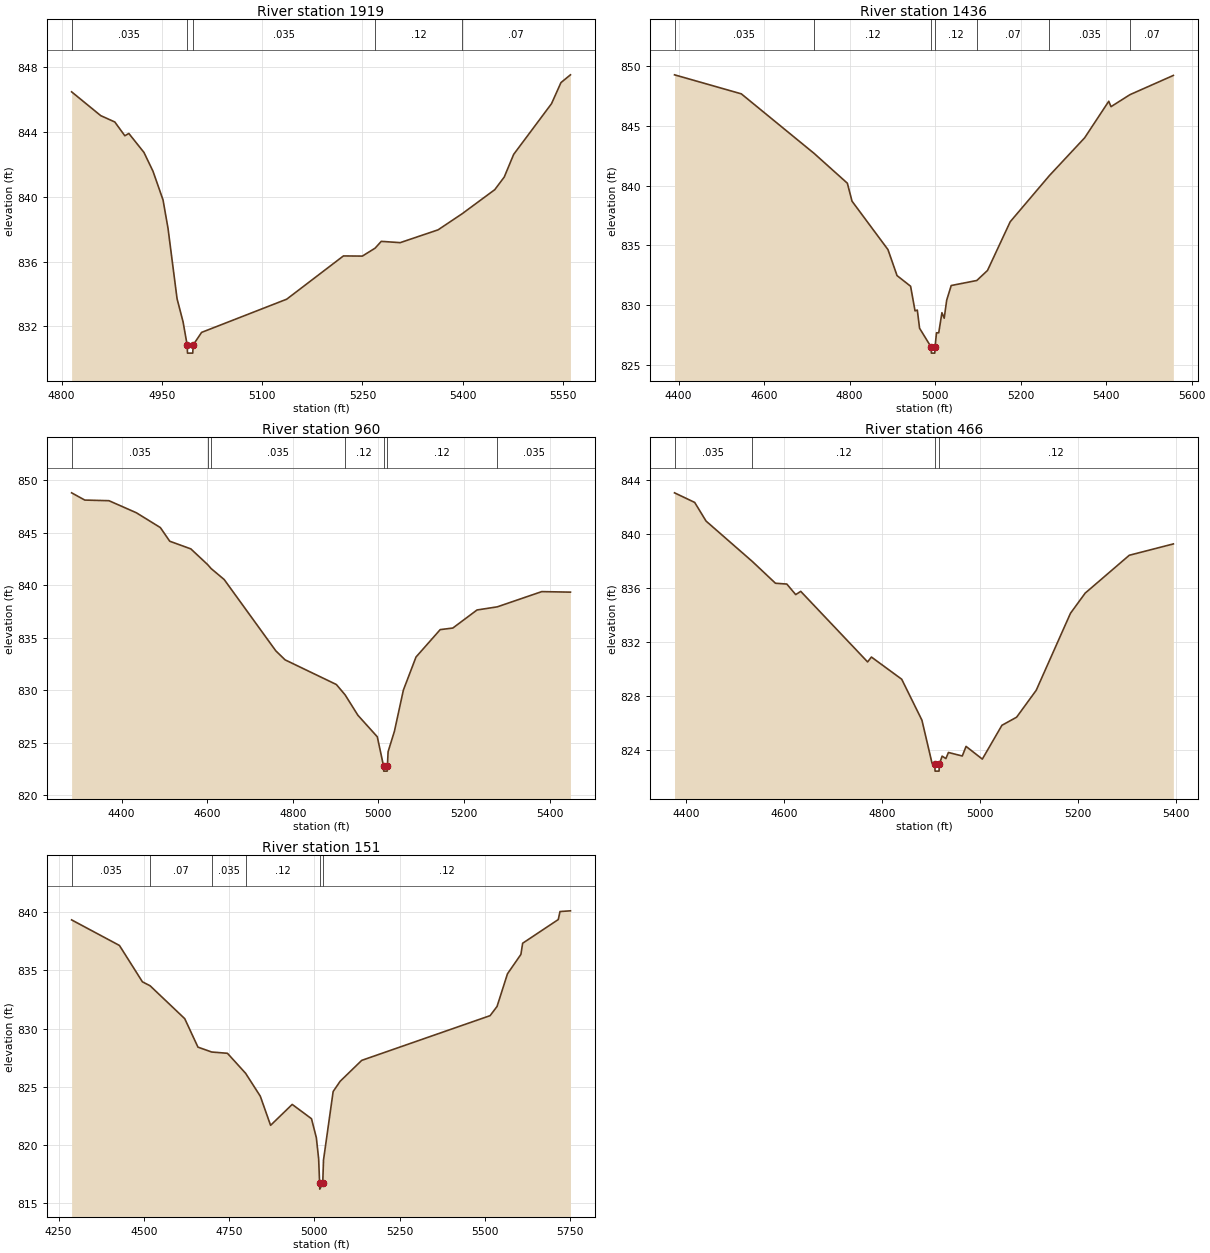
Type RM Length L Ch R = 1 ,1919    ,483,483,483
BEGIN DESCRIPTION:
Bear Creek Tributary 14 4.0
END DESCRIPTION:
XS GIS Cut Line= 3
      2190374.99       13793275.        2190225.       13793175.
      2189824.97     13792774.97
#Sta/Elev= 30
  4815.1  846.48  4858.7  845.01  4879.7  844.62  4894.7  843.77  4900.7  843.91
  4923.3  842.74  4936.8  841.58  4951.8  839.81  4959.3  838.05  4972.8  833.71
  4981.8  832.28  4987.9  830.85  4988.4  830.35  4996.3  830.35  4996.8  830.85
  5009.5  831.63  5136.8  833.68  5221.6  836.35  5249.9  836.34    5269  836.83
  5278.2  837.25  5306.5  837.17  5363.1  837.96    5399  838.95  5447.9  840.44
  5462.1  841.22  5476.2  842.62  5532.8  845.75  5546.9  847.05  5561.1  847.53
#Mann= 5 ,-1 , 0
  4815.1    .035       0  4987.9    .035       0  4996.8    .035       0
    5269     .12       0    5399     .07       0
Bank Sta=4987.9,4996.8
XS Rating Curve= 0 ,0
Exp/Cntr=0.3,0.1

Type RM Length L Ch R = 1 ,1436    ,476,476,476
BEGIN DESCRIPTION:
Bear Creek Tributary 14 3.0
END DESCRIPTION:
XS GIS Cut Line= 3
      2190808.99     13792919.05        2190225.       13792725.
       2189705.5     13792540.12
#Sta/Elev= 30
  4390.4  849.26  4546.7  847.67  4716.7   842.7  4794.7   840.2  4805.6   838.7
  4889.7  834.65  4910.9  832.48  4942.6  831.59    4953  829.53  4958.3   829.6
  4963.6  828.08  4990.7   826.5  4991.2     826  4999.2     826  4999.7   826.5
  5003.2   827.7  5008.4   827.7  5015.9  829.38  5021.2  828.92    5027  830.42
  5037.6  831.65  5097.4  832.07  5122.5  832.91  5175.6  836.98  5267.3  840.84
  5349.8     844  5406.1  847.05  5411.4   846.6  5455.6   847.6  5557.2  849.21
#Mann= 7 ,-1 , 0
  4390.4    .035       0  4716.7     .12       0  4990.7     .05       0
  4999.7     .12       0  5097.4     .07       0  5267.3    .035       0
  5455.6     .07       0
Bank Sta=4990.7,4999.7
XS Rating Curve= 0 ,0
Exp/Cntr=0.3,0.1

Type RM Length L Ch R = 1 ,960     ,494,494,494
BEGIN DESCRIPTION:
Bear Creek Tributary 14 2.0
END DESCRIPTION:
XS GIS Cut Line= 3
      2190842.32     13792860.77        2190375.       13792325.
      2190005.29     13792061.23
#Sta/Elev= 30
  4283.4  848.81  4314.2  848.12  4370.7  848.06  4434.7  846.91  4490.7   845.5
  4512.6   844.2  4561.9  843.47  4601.2  841.97  4609.4  841.59  4639.8  840.55
  4760.3  833.76    4782   832.9  4901.8  830.55  4922.3  829.56  4952.1  827.62
  4997.4  825.57  5011.9   822.8  5012.4   822.3  5020.5   822.3    5021   822.8
  5022.6  824.15  5037.4   826.1  5058.3  830.02  5087.8  833.17  5144.3  835.78
  5173.8  835.93  5230.3  837.65  5277.7  837.95  5381.5   839.4  5448.5  839.35
#Mann= 7 ,-1 , 0
  4283.4    .035       0  4601.2     .12       0  4609.4    .035       0
  4922.3     .12       0  5011.9     .05       0    5021     .12       0
  5277.7    .035       0
Bank Sta=5011.9,5021
XS Rating Curve= 0 ,0
Exp/Cntr=0.3,0.1

Type RM Length L Ch R = 1 ,466     ,315,315,315
BEGIN DESCRIPTION:
Bear Creek Tributary 14 1.0
END DESCRIPTION:
XS GIS Cut Line= 3
      2190874.99     13792574.97        2190725.       13791975.
      2190325.04       13791975.
#Sta/Elev= 30
  4376.8  843.06    4418  842.35  4441.2  840.97  4535.7  837.98  4582.9  836.37
  4606.1  836.31  4624.2  835.53  4634.5  835.77    4771  830.55  4778.8  830.91
  4840.6  829.27  4881.9  826.24  4902.5  823.06  4908.2  822.97  4908.7  822.47
  4916.9  822.47  4917.4  822.97  4923.1  823.58  4930.8   823.4    4936  823.85
  4964.3  823.59    4972   824.3  5005.2  823.36  5045.2  825.86  5075.2  826.46
  5115.2  828.45  5185.2  834.15  5215.2  835.64  5305.2  838.44  5395.2  839.28
#Mann= 4 ,-1 , 0
  4376.8    .035       0  4535.7     .12       0  4908.2     .05       0
  4917.4     .12       0
Bank Sta=4908.2,4917.4
XS Rating Curve= 0 ,0
Exp/Cntr=0.3,0.1

Type RM Length L Ch R = 1 ,151     ,0,0,0
BEGIN DESCRIPTION:
X18126
END DESCRIPTION:
XS GIS Cut Line= 4
      2191075.48      13792444.3      2191000.53     13791832.23
      2190871.45     13791711.47      2190213.51     13791836.39
#Sta/Elev= 30
  4288.1  839.35  4428.4  837.15  4495.8  834.02  4518.3  833.68  4619.9  830.85
  4658.7   828.4  4698.9  827.98  4745.2  827.87  4798.4  826.15  4841.5  824.18
  4871.7  821.67  4935.1  823.47  4991.7  822.24  5005.9  820.61  5012.7  818.78
  5015.5  816.68    5016  816.18  5024.7  816.68  5026.9  818.68  5055.2  824.58
  5075.7  825.46    5139  827.26  5515.6  831.11  5535.9   831.9  5566.5  834.71
  5605.9  836.38    5611  837.34  5715.5  839.38  5720.6  840.07  5751.2  840.13
#Mann= 6 ,-1 , 0
  4288.1    .035       0  4518.3     .07       0  4698.9    .035       0
  4798.4     .12       0  5015.5     .05       0  5024.7     .12       0
Bank Sta=5015.5,5024.7
XS Rating Curve= 0 ,0
Exp/Cntr=0.3,0.1

Chan Stop Cuts=-1
Use User Specified Reach Order=0
Composite Channel Slope=5