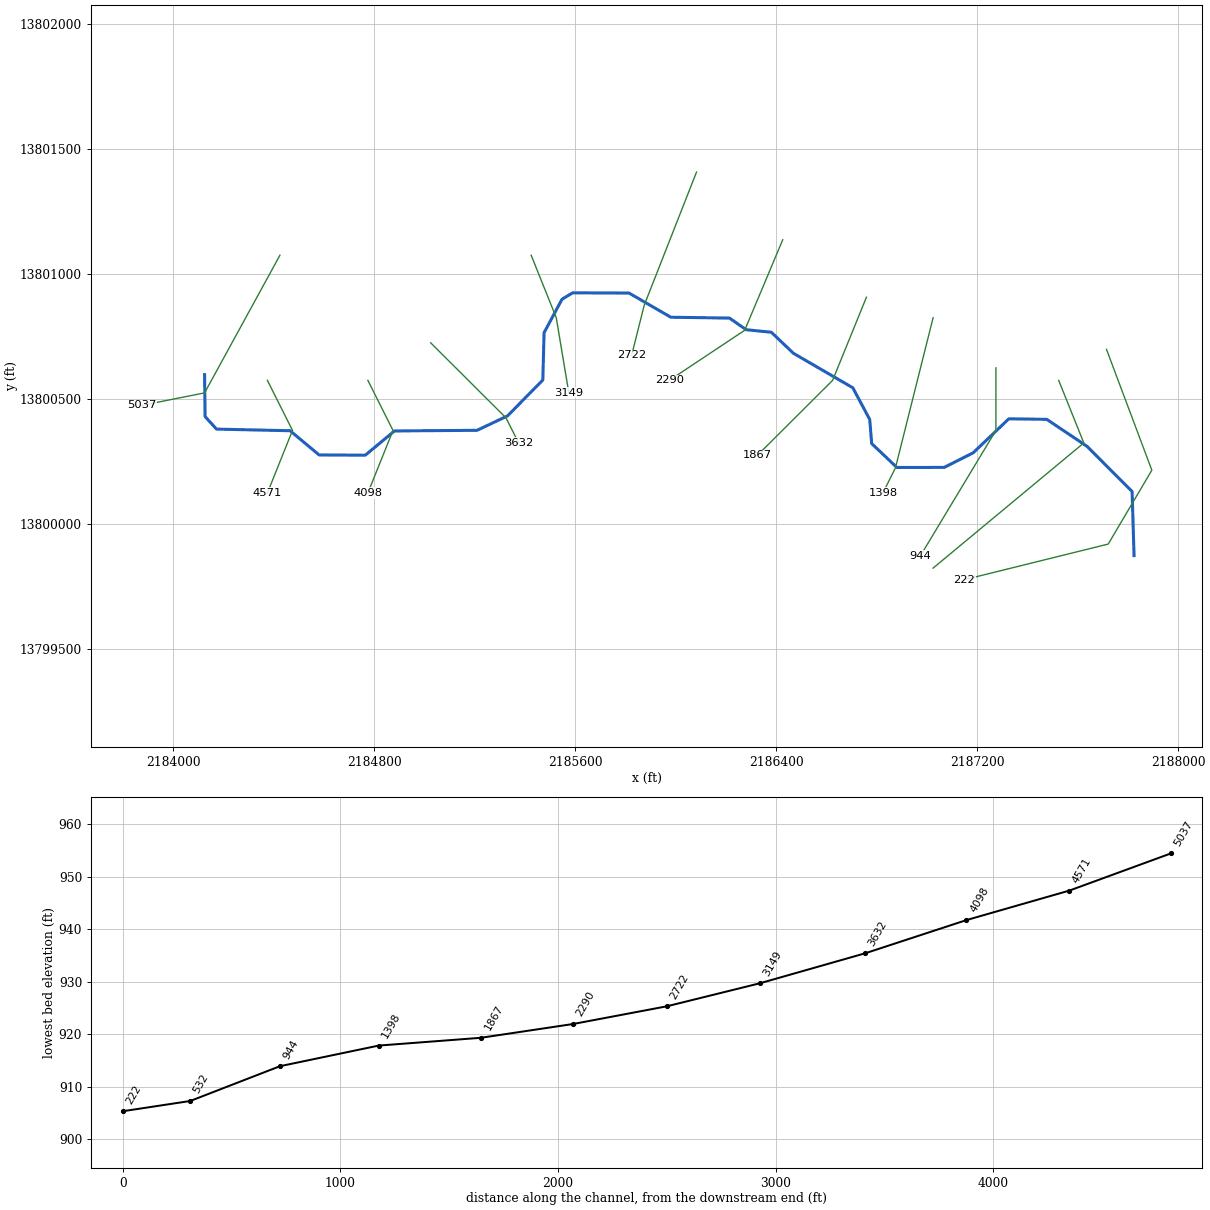
--- Bear Creek Tributary 15.prj (project) ---

Proj Title=Bear Creek Tributary 15 Base Level Engineering
Current Plan=p01
Default Exp/Contr=0.3,0.1
English Units
Geom File=g01
Flow File=f01
Plan File=p01
BEGIN DESCRIPTION:
Bear Creek Tributary 15
END DESCRIPTION:

--- Bear Creek Tributary 15.p01 (plan) ---

Plan Title=Multiple Run
Short Identifier=Multiple
Geom File=g01
Flow File=f01
Subcritical Flow
K Sum by GR= 0
Std Step Tol= 0.01
Critical Tol= 0.01
Num of Std Step Trials= 20
Max Error Tol= 0.3
Flow Tol Ratio= 0.001
Split Flow NTrial= 30
Split Flow Tol= 0.02
Split Flow Ratio= 0.02
Log Output Level= 0
Friction Slope Method= 1
Unsteady Friction Slope Method= 2
Unsteady Bridges Friction Slope Method= 1
Parabolic Critical Depth
Global Vel Dist=  1 , 1 , 1
Global Log Level= 0
CheckData=True
Encroach Param= -1, 0, 0, 0
BEGIN DESCRIPTION:
Multiple Run
END DESCRIPTION:

--- Bear Creek Tributary 15.f01 (steady flow) ---

Flow Title=Multiple
Number of Profiles=7
Profile Names=10-year,25-year,50-year,1pct_min,100-year,1pct_plu,500-year
River Rch & RM= Bear Creek Tribu,Reach-1,5037
     593     967    1309     861    1717    3427    2921
Boundary for River Rch & Prof#=Bear Creek Tribu,Reach-1,1
Up Type=0
Dn Type=3
Dn Slope=0.005
Boundary for River Rch & Prof#=Bear Creek Tribu,Reach-1,2
Up Type=0
Dn Type=3
Dn Slope=0.005
Boundary for River Rch & Prof#=Bear Creek Tribu,Reach-1,3
Up Type=0
Dn Type=3
Dn Slope=0.005
Boundary for River Rch & Prof#=Bear Creek Tribu,Reach-1,4
Up Type=0
Dn Type=3
Dn Slope=0.005
Boundary for River Rch & Prof#=Bear Creek Tribu,Reach-1,5
Up Type=0
Dn Type=3
Dn Slope=0.005
Boundary for River Rch & Prof#=Bear Creek Tribu,Reach-1,6
Up Type=0
Dn Type=3
Dn Slope=0.005
Boundary for River Rch & Prof#=Bear Creek Tribu,Reach-1,7
Up Type=0
Dn Type=3
Dn Slope=0.005

--- Bear Creek Tributary 15.g01 (geometry) ---

Geom Title=Existing Conditions

River Reach=Bear Creek Tribu,Reach-1
Reach XY= 30
      2184125.00     13800597.83      2184126.95     13800430.63
      2184172.26     13800380.34      2184465.41     13800373.79
      2184580.86     13800277.06      2184764.56     13800276.05
      2184880.86     13800372.93      2185209.79     13800375.51
      2185331.06     13800433.14      2185471.46     13800576.46
      2185476.36     13800765.35      2185547.80     13800898.97
      2185590.03     13800924.67      2185814.50     13800923.80
      2185980.93     13800827.24      2186214.50     13800823.78
      2186280.98     13800777.36      2186381.16     13800767.12
      2186468.96     13800683.18      2186705.38     13800545.47
      2186772.67     13800419.03      2186780.52     13800322.56
      2186880.84     13800227.05      2187069.48     13800227.35
      2187184.68     13800285.76      2187326.47     13800421.47
      2187477.38     13800419.31      2187638.00     13800311.31
      2187817.19     13800131.19      2187825.00     13799875.00

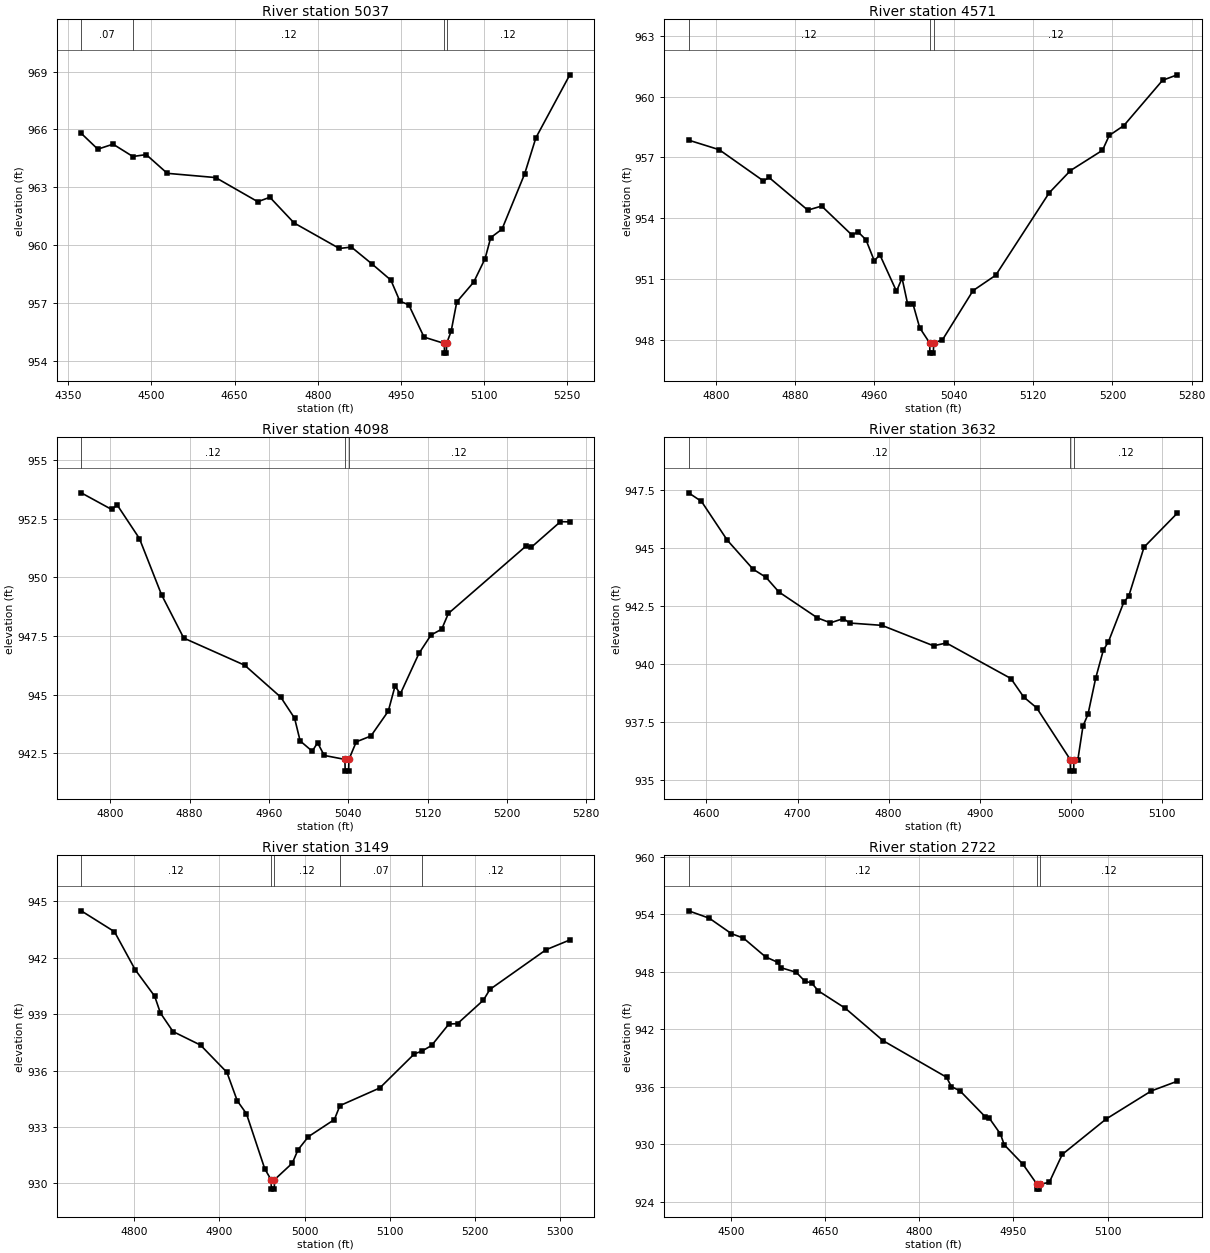
Type RM Length L Ch R = 1,5037,466,466,466
BEGIN DESCRIPTION:
Bear Creek Tributary 15 11.0
END DESCRIPTION:
XS GIS Cut Line= 3
      2184424.99     13801074.99      2184125.00     13800525.00
      2183875.04     13800475.01
#Sta/Elev= 30
  4373.4  965.80  4403.3  964.98  4430.8  965.24  4466.6  964.60  4490.6  964.70
  4528.6  963.73  4615.9  963.51  4691.9  962.26  4713.7  962.49  4757.4  961.16
  4839.0  959.84  4860.8  959.91  4897.4  959.05  4932.0  958.20  4948.2  957.11
  4964.3  956.92  4991.8  955.25  5028.5  954.92  5028.7  954.42  5032.2  954.42
  5032.5  954.92  5040.7  955.55  5050.9  957.07  5081.5  958.10  5101.9  959.31
  5112.1  960.40  5132.5  960.84  5173.3  963.70  5193.6  965.57  5254.8  968.83
#Mann=4,-1,0
  4373.4    0.07       0  4466.6    0.12       0  5028.5    0.05       0
  5032.5    0.12       0
Bank Sta=5028.5,5032.5
Exp/Cntr=0.3,0.1

Type RM Length L Ch R = 1,4571,473,473,473
BEGIN DESCRIPTION:
Bear Creek Tributary 15 10.0
END DESCRIPTION:
XS GIS Cut Line= 3
      2184374.98     13800575.04      2184475.00     13800375.00
      2184375.01     13800125.01
#Sta/Elev= 30
  4772.5  957.85  4803.3  957.38  4848.0  955.84  4853.6  956.01  4892.7  954.40
  4906.7  954.60  4937.5  953.16  4943.1  953.34  4951.4  952.94  4959.8  951.90
  4965.4  952.20  4982.2  950.40  4987.8  951.05  4993.4  949.78  4998.8  949.78
  5005.6  948.60  5015.7  947.85  5015.9  947.35  5019.4  947.35  5019.7  947.85
  5028.5  948.00  5059.4  950.43  5082.3  951.19  5136.2  955.25  5157.7  956.35
  5190.0  957.35  5196.8  958.08  5211.6  958.57  5250.6  960.80  5265.4  961.07
#Mann=3,-1,0
  4772.5    0.12       0  5015.7    0.05       0  5019.7    0.12       0
Bank Sta=5015.7,5019.7
Exp/Cntr=0.3,0.1

Type RM Length L Ch R = 1,4098,466,466,466
BEGIN DESCRIPTION:
Bear Creek Tributary 15 9.0
END DESCRIPTION:
XS GIS Cut Line= 3
      2184775.02     13800574.97      2184875.00     13800375.00
      2184775.01     13800125.03
#Sta/Elev= 30
  4770.7  953.61  4801.4  952.90  4807.0  953.09  4829.4  951.66  4851.7  949.26
  4874.1  947.41  4935.6  946.25  4971.9  944.89  4985.9  943.99  4991.5  943.02
  5003.7  942.58  5009.1  942.94  5015.8  942.40  5036.7  942.23  5036.9  941.73
  5040.4  941.73  5040.7  942.23  5048.1  942.98  5062.9  943.23  5080.4  944.29
  5087.2  945.36  5092.6  945.03  5111.4  946.76  5123.5  947.54  5134.3  947.79
  5141.0  948.46  5219.1  951.33  5224.5  951.28  5254.1  952.38  5263.5  952.37
#Mann=3,-1,0
  4770.7    0.12       0  5036.7    0.05       0  5040.7    0.12       0
Bank Sta=5036.7,5040.7
Exp/Cntr=0.3,0.1

Type RM Length L Ch R = 1,3632,483,483,483
BEGIN DESCRIPTION:
Bear Creek Tributary 15 8.0
END DESCRIPTION:
XS GIS Cut Line= 3
      2185025.00     13800725.00      2185325.00     13800425.00
      2185375.01     13800324.97
#Sta/Elev= 30
  4580.5  947.39  4594.6  947.02  4622.9  945.35  4651.2  944.10  4665.4  943.75
  4679.5  943.12  4721.9  942.00  4736.1  941.79  4750.2  941.97  4757.3  941.78
  4792.6  941.68  4849.2  940.80  4863.3  940.92  4934.1  939.39  4948.2  938.59
  4962.3  938.13  4999.2  935.90  4999.5  935.40  5003.0  935.40  5003.2  935.90
  5007.6  935.90  5013.2  937.34  5018.7  937.85  5027.1  939.40  5035.5  940.61
  5041.1  940.97  5057.9  942.67  5063.5  942.95  5080.2  945.05  5116.6  946.51
#Mann=3,-1,0
  4580.5    0.12       0  4999.2    0.05       0  5003.2    0.12       0
Bank Sta=4999.2,5003.2
Exp/Cntr=0.3,0.1

Type RM Length L Ch R = 1,3149,427,427,427
BEGIN DESCRIPTION:
Bear Creek Tributary 15 7.0
END DESCRIPTION:
XS GIS Cut Line= 3
      2185425.00     13801074.99      2185525.00     13800825.00
      2185575.00     13800524.99
#Sta/Elev= 30
  4737.9  944.50  4776.9  943.39  4801.2  941.37  4824.1  939.96  4830.8  939.07
  4845.6  938.08  4877.9  937.36  4908.9  935.91  4921.0  934.40  4931.8  933.71
  4953.3  930.78  4960.7  930.20  4961.0  929.70  4964.5  929.70  4964.7  930.20
  4985.6  931.08  4992.3  931.79  5004.5  932.49  5035.0  933.40  5041.5  934.14
  5088.3  935.08  5128.8  936.89  5137.8  937.04  5149.1  937.34  5169.4  938.48
  5179.5  938.50  5209.9  939.75  5217.5  940.32  5283.4  942.43  5311.3  942.95
#Mann=5,-1,0
  4737.9    0.12       0  4960.7    0.05       0  4964.7    0.12       0
  5041.5    0.07       0  5137.8    0.12       0
Bank Sta=4960.7,4964.7
Exp/Cntr=0.3,0.1

Type RM Length L Ch R = 1,2722,432,432,432
BEGIN DESCRIPTION:
Bear Creek Tributary 15 6.0
END DESCRIPTION:
XS GIS Cut Line= 3
      2186083.32     13801407.22      2185875.00     13800875.00
      2185825.00     13800675.00
#Sta/Elev= 30
  4433.0  954.34  4465.9  953.57  4501.1  951.96  4520.2  951.50  4555.4  949.54
  4574.5  948.98  4579.8  948.41  4604.3  947.93  4617.9  947.01  4628.7  946.82
  4639.5  945.99  4682.4  944.18  4742.7  940.79  4843.5  936.99  4851.2  936.01
  4864.9  935.57  4905.5  932.84  4910.9  932.78  4929.4  931.06  4935.3  929.95
  4965.2  927.91  4987.6  925.82  4987.9  925.32  4991.4  925.32  4991.6  925.82
  5007.1  926.03  5027.7  928.94  5097.3  932.62  5169.5  935.56  5210.7  936.57
#Mann=3,-1,0
  4433.0    0.12       0  4987.6    0.05       0  4991.6    0.12       0
Bank Sta=4987.6,4991.6
Exp/Cntr=0.3,0.1

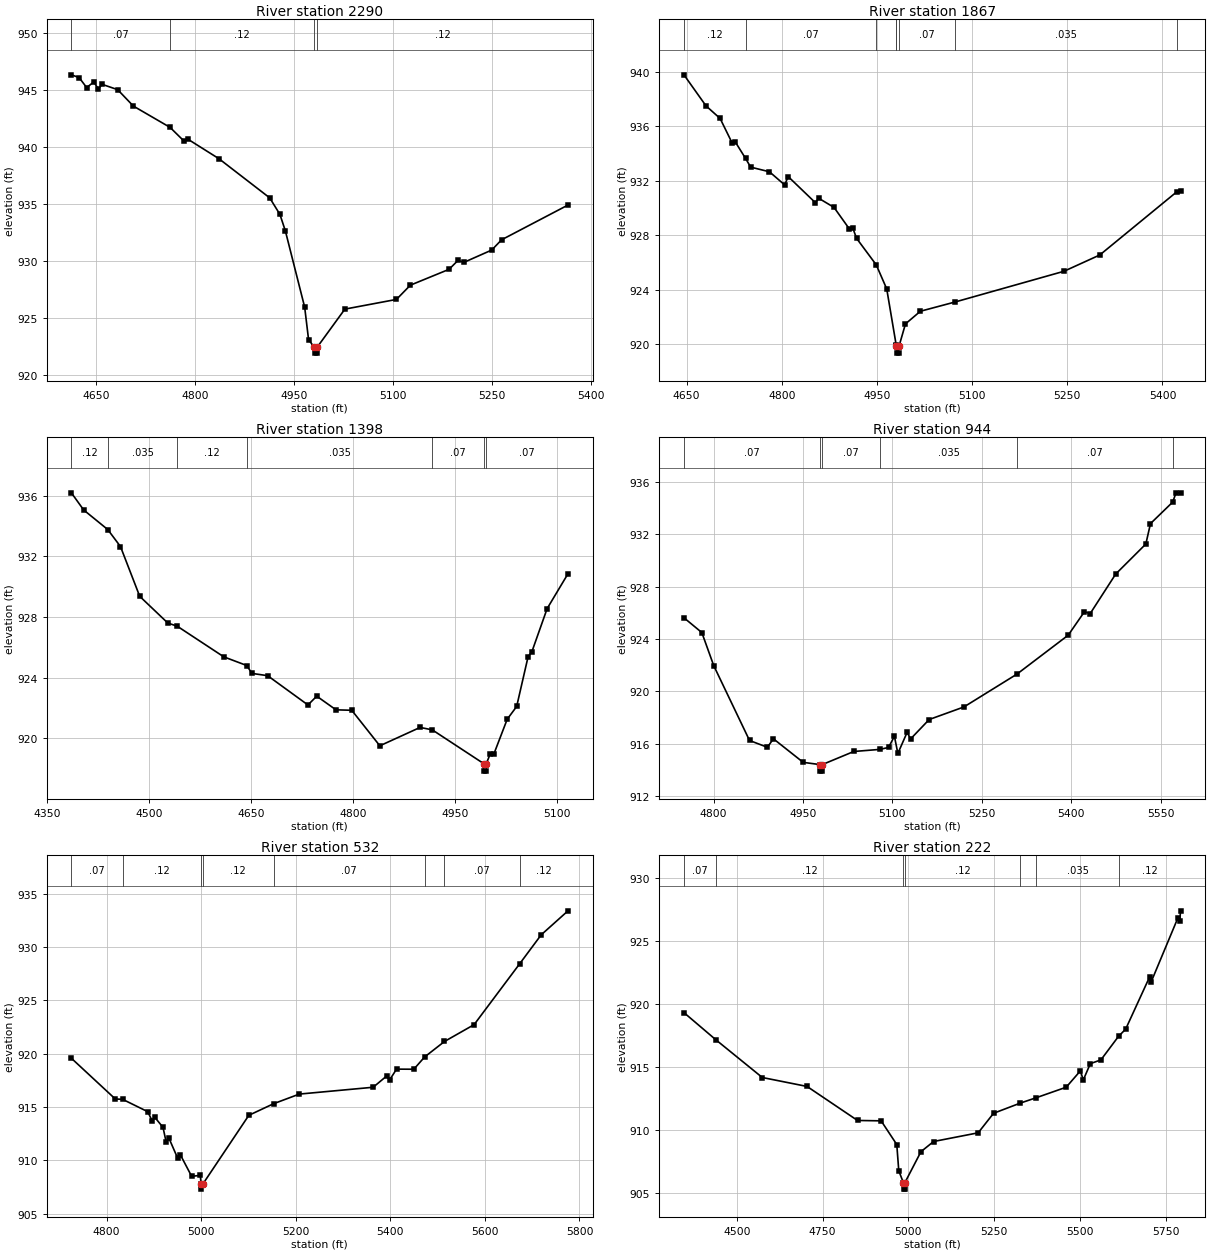
Type RM Length L Ch R = 1,2290,423,423,423
BEGIN DESCRIPTION:
Bear Creek Tributary 15 5.0
END DESCRIPTION:
XS GIS Cut Line= 3
      2186426.37     13801136.36      2186275.00     13800775.00
      2185975.03     13800575.02
#Sta/Elev= 30
  4612.4  946.35  4624.1  946.11  4635.6  945.23  4646.4  945.73  4653.3  945.09
  4658.7  945.52  4682.5  945.05  4706.3  943.61  4761.9  941.74  4783.0  940.54
  4788.5  940.72  4836.0  938.99  4912.8  935.56  4928.3  934.11  4936.6  932.65
  4965.8  925.97  4971.7  923.13  4980.5  922.44  4980.7  921.94  4984.2  921.94
  4984.5  922.44  5026.7  925.80  5104.8  926.65  5125.9  927.90  5184.5  929.29
  5198.0  930.07  5207.0  929.90  5249.1  930.98  5264.1  931.88  5364.7  934.93
#Mann=4,-1,0
  4612.4    0.07       0  4761.9    0.12       0  4980.5    0.05       0
  4984.5    0.12       0
Bank Sta=4980.5,4984.5
Exp/Cntr=0.3,0.1

Type RM Length L Ch R = 1,1867,469,469,469
BEGIN DESCRIPTION:
Bear Creek Tributary 15 4.0
END DESCRIPTION:
XS GIS Cut Line= 3
      2186759.69     13800907.17      2186625.00     13800575.00
      2186325.00     13800275.00
#Sta/Elev= 30
  4645.9  939.79  4680.6  937.51  4702.9  936.58  4721.6  934.80  4727.0  934.84
  4743.0  933.64  4751.1  933.00  4780.6  932.66  4804.7  931.69  4810.1  932.31
  4852.9  930.39  4858.3  930.71  4882.4  930.04  4906.5  928.46  4911.9  928.53
  4918.0  927.76  4949.0  925.81  4965.5  924.04  4980.3  919.94  4980.8  919.82
  4981.0  919.32  4984.5  919.32  4984.8  919.82  4995.0  921.47  5018.5  922.40
  5073.1  923.08  5244.8  925.34  5301.3  926.54  5423.0  931.20  5428.6  931.28
#Mann=8,-1,0
  4645.9    0.12       0  4743.0    0.07       0  4949.0   0.035       0
  4980.3    0.07       0  4980.8    0.05       0  4984.8    0.07       0
  5073.1   0.035       0  5423.0    0.07       0
Bank Sta=4980.8,4984.8
Exp/Cntr=0.3,0.1

Type RM Length L Ch R = 1,1398,454,454,454
BEGIN DESCRIPTION:
Bear Creek Tributary 15 3.0
END DESCRIPTION:
XS GIS Cut Line= 3
      2187025.01     13800825.03      2186875.00     13800225.00
      2186825.00     13800125.00
#Sta/Elev= 30
  4385.4  936.18  4403.5  935.05  4438.9  933.76  4457.6  932.64  4485.9  929.36
  4527.2  927.60  4541.1  927.39  4609.6  925.37  4643.3  924.80  4650.9  924.28
  4674.0  924.13  4733.3  922.20  4746.2  922.78  4774.5  921.88  4797.7  921.85
  4839.0  919.51  4898.2  920.72  4916.1  920.56  4991.6  918.34  4991.8  917.84
  4995.3  917.84  4995.6  918.34  5001.3  918.97  5006.7  918.97  5026.3  921.26
  5040.2  922.10  5057.0  925.38  5062.6  925.71  5085.0  928.55  5115.7  930.85
#Mann=7,-1,0
  4385.4    0.12       0  4438.9   0.035       0  4541.1    0.12       0
  4643.3   0.035       0  4916.1    0.07       0  4991.6    0.05       0
  4995.6    0.07       0
Bank Sta=4991.6,4995.6
Exp/Cntr=0.3,0.1

Type RM Length L Ch R = 1,944,412,412,412
BEGIN DESCRIPTION:
Bear Creek Tributary 15 2.0
END DESCRIPTION:
XS GIS Cut Line= 3
      2187275.00     13800624.95      2187275.00     13800375.00
      2186975.02     13799875.04
#Sta/Elev= 30
  4750.4  925.62  4780.4  924.49  4800.4  921.96  4860.4  916.25  4890.4  915.73
  4900.4  916.38  4950.4  914.58  4978.4  914.41  4978.6  913.91  4982.1  913.91
  4982.4  914.41  5035.3  915.41  5079.2  915.57  5093.6  915.72  5103.4  916.57
  5109.2  915.26  5124.7  916.87  5130.6  916.37  5161.7  917.85  5220.0  918.81
  5309.0  921.32  5394.9  924.29  5422.1  926.08  5431.8  925.94  5474.6  928.96
  5525.1  931.25  5532.9  932.81  5570.1  934.45  5575.7  935.15  5583.4  935.16
#Mann=6,-1,0
  4750.4    0.07       0  4978.4    0.05       0  4982.4    0.07       0
  5079.2   0.035       0  5309.0    0.07       0  5570.1    0.12       0
Bank Sta=4978.4,4982.4
Exp/Cntr=0.3,0.1

Type RM Length L Ch R = 1,532,310,310,310
BEGIN DESCRIPTION:
Bear Creek Tributary 15 1.0
END DESCRIPTION:
XS GIS Cut Line= 3
      2187525.01     13800574.97      2187625.00     13800325.00
      2187024.96     13799824.97
#Sta/Elev= 30
  4725.5  919.56  4818.4  915.74  4833.8  915.71  4887.0  914.55  4896.4  913.68
  4901.8  914.03  4919.3  913.08  4926.1  911.67  4931.5  912.10  4950.3  910.19
  4955.7  910.53  4979.9  908.49  4998.0  908.58  4999.9  907.79  5000.1  907.29
  5003.9  907.79  5100.8  914.21  5153.3  915.30  5207.6  916.20  5363.8  916.84
  5392.4  917.90  5398.9  917.55  5413.2  918.54  5449.7  918.53  5472.6  919.68
  5514.5  921.13  5577.2  922.71  5674.0  928.44  5719.1  931.13  5775.8  933.38
#Mann=8,-1,0
  4725.5    0.07       0  4833.8    0.12       0  4999.9    0.05       0
  5003.9    0.12       0  5153.3    0.07       0  5472.6   0.035       0
  5514.5    0.07       0  5674.0    0.12       0
Bank Sta=4999.9,5003.9
Exp/Cntr=0.3,0.1

Type RM Length L Ch R = 1,222,0,0,0
BEGIN DESCRIPTION:
X18127
END DESCRIPTION:
XS GIS Cut Line= 4
      2187715.26     13800698.88      2187895.81     13800216.23
      2187722.20     13799921.09      2187149.65     13799778.82
#Sta/Elev= 30
  4345.8  919.35  4439.0  917.19  4574.2  914.20  4704.7  913.49  4851.8  910.79
  4920.6  910.76  4966.2  908.88  4972.0  906.80  4985.6  905.84  4985.9  905.34
  4989.4  905.34  4989.6  905.84  5036.6  908.31  5073.5  909.12  5203.5  909.81
  5248.3  911.36  5326.4  912.17  5373.2  912.60  5460.1  913.43  5501.5  914.73
  5509.8  914.00  5530.4  915.30  5561.3  915.60  5612.7  917.47  5633.4  918.04
  5703.0  922.17  5708.2  921.82  5785.7  926.87  5790.9  926.61  5793.5  927.43
#Mann=7,-1,0
  4345.8    0.07       0  4439.0    0.12       0  4985.6    0.05       0
  4989.6    0.12       0  5326.4    0.07       0  5373.2   0.035       0
  5612.7    0.12       0
Bank Sta=4985.6,4989.6
Exp/Cntr=0.3,0.1

Chan Stop Cuts=-1