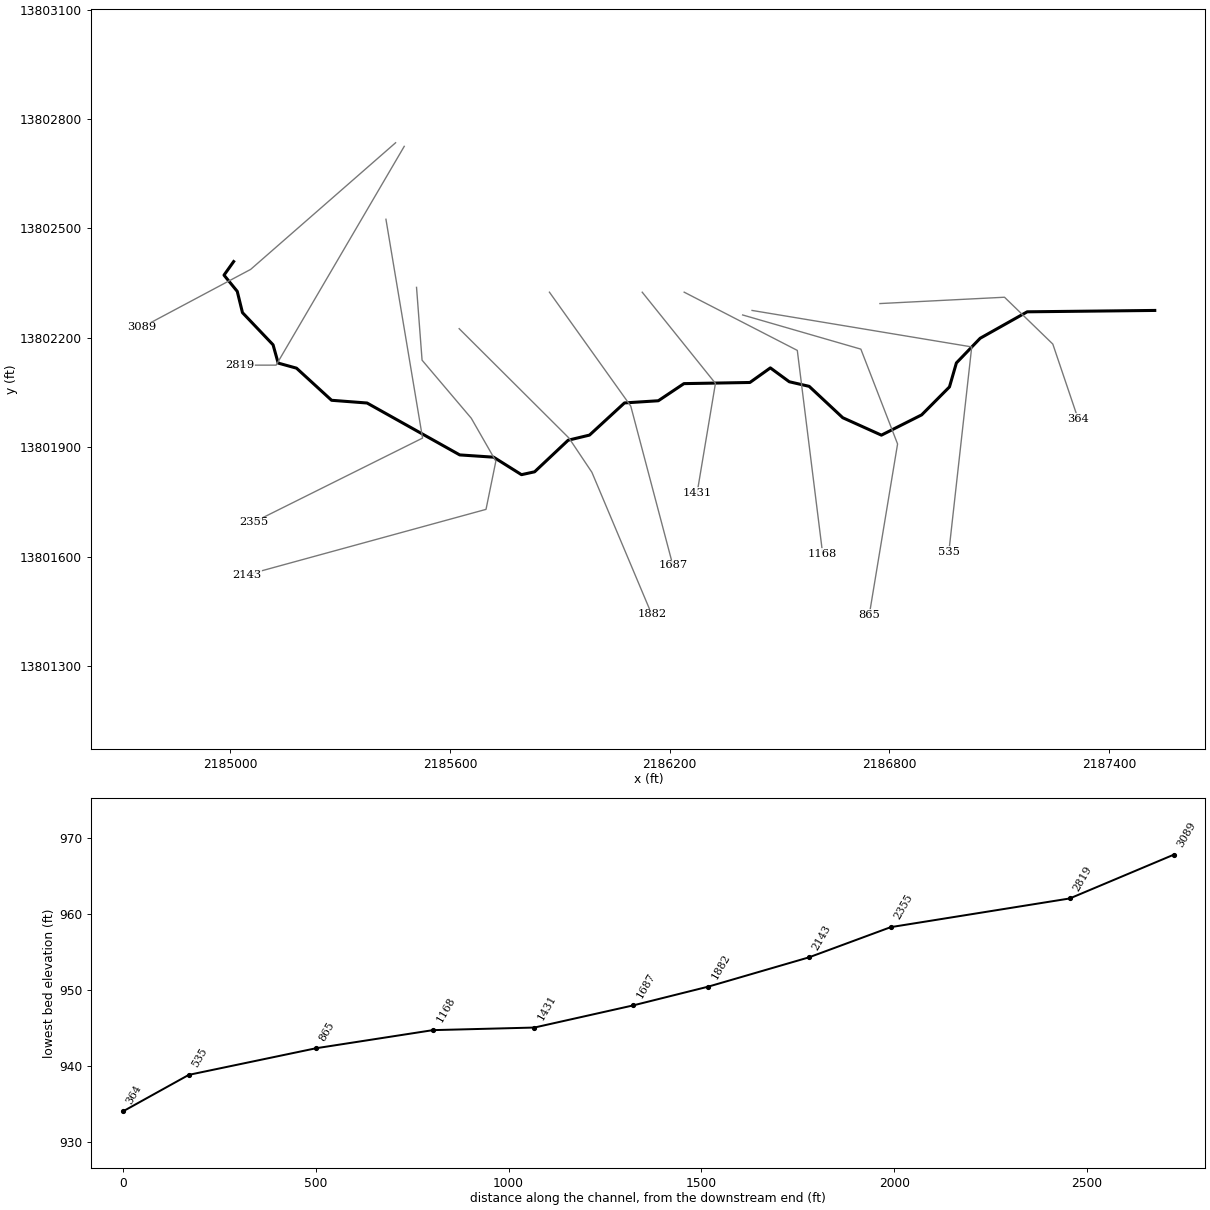
--- Bear Creek Tributary 16.prj (project) ---

Proj Title=Bear Creek Tributary 16 Base Level Engineering
Current Plan=p01
Default Exp/Contr=0.3,0.1
English Units
Geom File=g01
Flow File=f01
Plan File=p01
BEGIN DESCRIPTION:
Bear Creek Tributary 16
END DESCRIPTION:

--- Bear Creek Tributary 16.p01 (plan) ---

Plan Title=Multiple Run
Short Identifier=Multiple
Geom File=g01
Flow File=f01
Subcritical Flow
K Sum by GR= 0
Std Step Tol= 0.01
Critical Tol= 0.01
Num of Std Step Trials= 20
Max Error Tol= 0.3
Flow Tol Ratio= 0.001
Split Flow NTrial= 30
Split Flow Tol= 0.02
Split Flow Ratio= 0.02
Log Output Level= 0
Friction Slope Method= 1
Unsteady Friction Slope Method= 2
Unsteady Bridges Friction Slope Method= 1
Parabolic Critical Depth
Global Vel Dist=  1 , 1 , 1
Global Log Level= 0
CheckData=True
Encroach Param= -1, 0, 0, 0
BEGIN DESCRIPTION:
Multiple Run
END DESCRIPTION:

--- Bear Creek Tributary 16.f01 (steady flow) ---

Flow Title=Multiple
Number of Profiles=7
Profile Names=10-year,25-year,50-year,1pct_min,100-year,1pct_plu,500-year
River Rch & RM= Bear Creek Tribu,Reach-1,3089
     450     722     966     629    1256    2505    2092
Boundary for River Rch & Prof#=Bear Creek Tribu,Reach-1,1
Up Type=0
Dn Type=3
Dn Slope=0.005
Boundary for River Rch & Prof#=Bear Creek Tribu,Reach-1,2
Up Type=0
Dn Type=3
Dn Slope=0.005
Boundary for River Rch & Prof#=Bear Creek Tribu,Reach-1,3
Up Type=0
Dn Type=3
Dn Slope=0.005
Boundary for River Rch & Prof#=Bear Creek Tribu,Reach-1,4
Up Type=0
Dn Type=3
Dn Slope=0.005
Boundary for River Rch & Prof#=Bear Creek Tribu,Reach-1,5
Up Type=0
Dn Type=3
Dn Slope=0.005
Boundary for River Rch & Prof#=Bear Creek Tribu,Reach-1,6
Up Type=0
Dn Type=3
Dn Slope=0.005
Boundary for River Rch & Prof#=Bear Creek Tribu,Reach-1,7
Up Type=0
Dn Type=3
Dn Slope=0.005

--- Bear Creek Tributary 16.g01 (geometry) ---

Geom Title=Existing Conditions

River Reach=Bear Creek Tribu,Reach-1
Reach XY= 30
      2185009.04     13802409.04      2184982.67     13802371.82
      2185018.85     13802327.32      2185033.13     13802268.95
      2185116.70     13802180.74      2185130.62     13802130.62
      2185180.74     13802116.70      2185276.50     13802028.62
      2185373.41     13802021.17      2185626.58     13801878.83
      2185719.03     13801872.62      2185795.21     13801824.64
      2185831.05     13801832.50      2185922.72     13801919.13
      2185981.04     13801933.18      2186076.50     13802021.38
      2186169.02     13802027.36      2186238.92     13802074.32
      2186419.14     13802077.46      2186475.01     13802117.47
      2186526.65     13802079.45      2186581.04     13802066.86
      2186672.72     13801980.82      2186778.31     13801933.02
      2186888.24     13801988.59      2186964.23     13802065.30
      2186983.15     13802131.06      2187048.12     13802198.73
      2187176.55     13802271.25      2187525.00     13802275.00

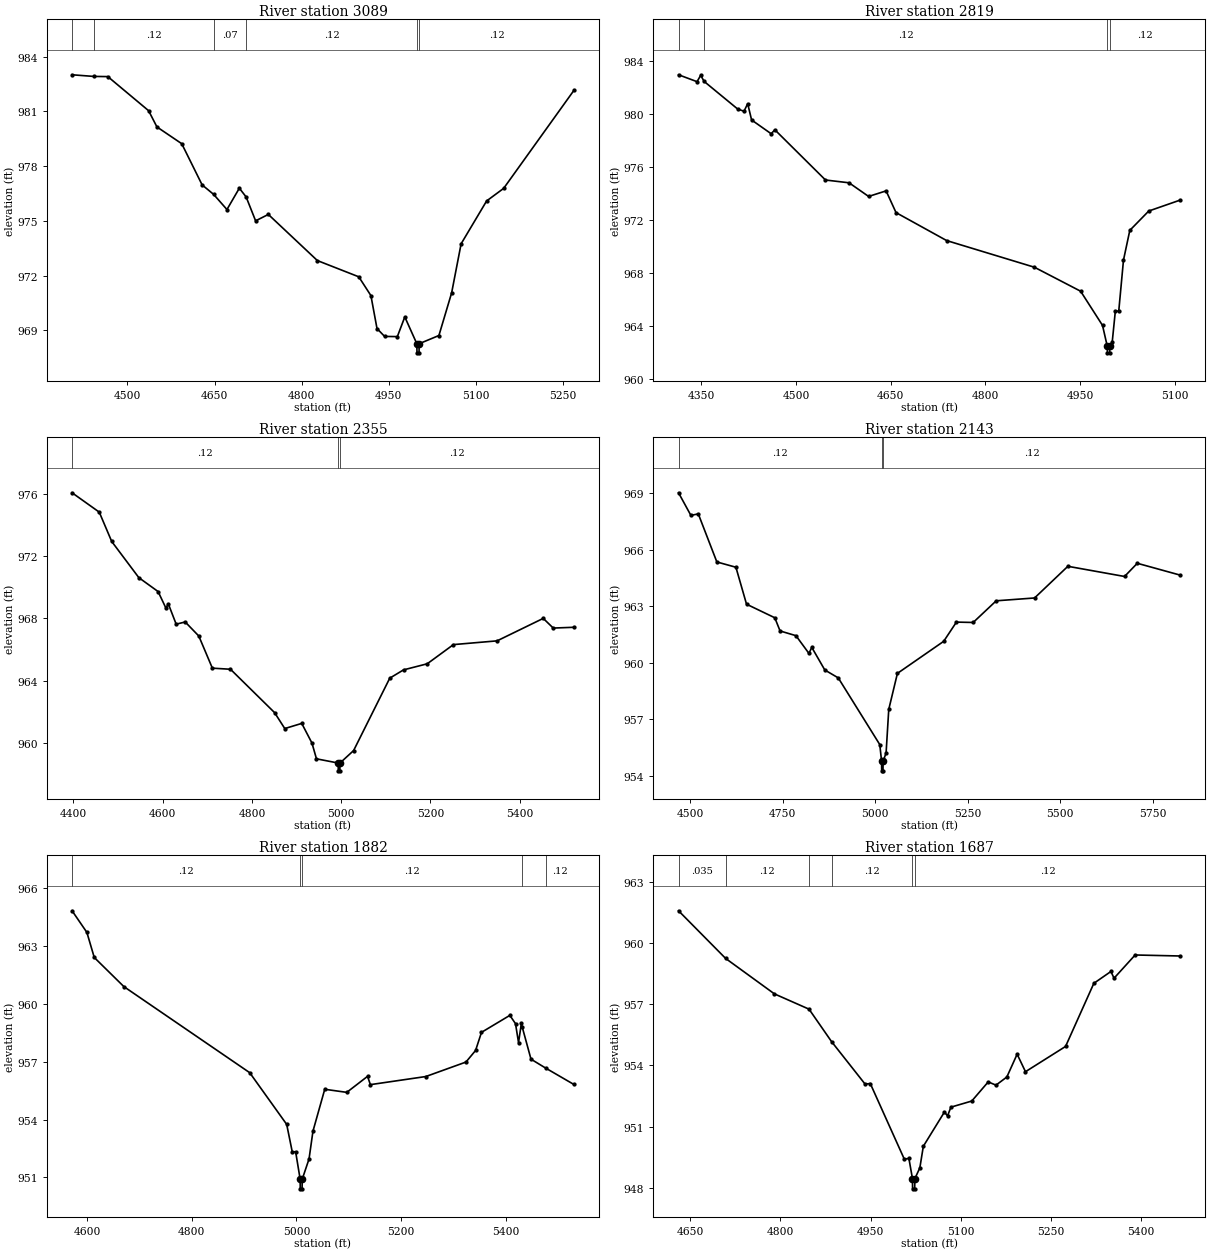
Type RM Length L Ch R = 1,3089,270,270,270
BEGIN DESCRIPTION:
X18134
END DESCRIPTION:
XS GIS Cut Line= 3
      2185451.38     13802734.83      2185055.54     13802387.61
      2184758.51     13802228.73
#Sta/Elev= 30
  4404.9  983.01  4442.2  982.92  4466.4  982.91  4536.6  981.04  4550.9  980.15
  4593.6  979.23  4628.7  976.97  4648.5  976.45  4671.4  975.62  4692.7  976.79
  4704.4  976.31  4720.7  975.00  4742.6  975.35  4827.0  972.82  4898.2  971.93
  4919.1  970.90  4929.6  969.09  4942.7  968.66  4964.6  968.65  4977.4  969.73
  4998.1  968.26  4998.4  967.76  5001.9  967.76  5002.1  968.26  5036.1  968.71
  5058.0  971.05  5074.3  973.74  5118.2  976.09  5147.5  976.78  5268.3  982.15
#Mann=6,-1,0
  4404.9   0.035       0  4442.2    0.12       0  4648.5    0.07       0
  4704.4    0.12       0  4998.1    0.05       0  5002.1    0.12       0
Bank Sta=4998.1,5002.1
Exp/Cntr=0.3,0.1

Type RM Length L Ch R = 1,2819,464,464,464
BEGIN DESCRIPTION:
Bear Creek Tributary 16 5.0
END DESCRIPTION:
XS GIS Cut Line= 3
      2185474.98     13802724.97      2185125.00     13802125.00
      2185024.99     13802125.00
#Sta/Elev= 30
  4314.0  982.98  4343.3  982.46  4349.1  982.94  4354.5  982.48  4407.8  980.39
  4417.7  980.23  4423.5  980.80  4429.7  979.57  4460.7  978.53  4466.5  978.83
  4546.7  975.04  4584.0  974.83  4615.0  973.80  4642.7  974.22  4658.4  972.58
  4738.6  970.47  4877.5  968.46  4950.7  966.65  4985.4  964.07  4992.9  962.50
  4993.2  962.00  4996.7  962.00  4996.9  962.50  5000.7  962.79  5005.7  965.15
  5011.1  965.15  5018.6  969.00  5028.6  971.24  5058.6  972.70  5108.6  973.53
#Mann=4,-1,0
  4314.0   0.035       0  4354.5    0.12       0  4992.9    0.05       0
  4996.9    0.12       0
Bank Sta=4992.9,4996.9
Exp/Cntr=0.3,0.1

Type RM Length L Ch R = 1,2355,212,212,212
BEGIN DESCRIPTION:
Bear Creek Tributary 16 4.0
END DESCRIPTION:
XS GIS Cut Line= 3
      2185424.99     13802525.05      2185525.00     13801925.00
      2185063.67     13801694.34
#Sta/Elev= 30
  4397.2  976.05  4458.1  974.81  4486.0  972.93  4546.8  970.61  4589.9  969.72
  4607.6  968.65  4612.7  968.94  4630.4  967.63  4650.7  967.77  4681.1  966.87
  4711.5  964.81  4752.1  964.74  4850.9  961.96  4873.7  960.94  4911.7  961.27
  4934.6  960.01  4944.7  959.00  4993.4  958.73  4993.6  958.23  4997.1  958.23
  4997.4  958.73  5027.9  959.53  5108.9  964.17  5139.7  964.70  5192.8  965.09
  5251.5  966.32  5349.3  966.56  5452.7  968.00  5475.1  967.38  5521.3  967.43
#Mann=3,-1,0
  4397.2    0.12       0  4993.4    0.05       0  4997.4    0.12       0
Bank Sta=4993.4,4997.4
Exp/Cntr=0.3,0.1

Type RM Length L Ch R = 1,2143,261,261,261
BEGIN DESCRIPTION:
X18133
END DESCRIPTION:
XS GIS Cut Line= 6
      2185508.56     13802338.27      2185523.69     13802138.61
      2185658.10     13801979.39      2185725.23     13801861.68
      2185698.34     13801729.50      2185045.07     13801549.91
#Sta/Elev= 30
  4468.5  969.01  4501.9  967.81  4521.9  967.89  4572.1  965.34  4623.6  965.06
  4652.3  963.10  4728.7  962.38  4743.0  961.68  4785.9  961.43  4821.0  960.49
  4828.7  960.81  4863.9  959.61  4900.3  959.19  5012.6  955.65  5017.4  954.76
  5017.7  954.26  5021.2  954.26  5021.4  954.76  5029.6  955.21  5036.8  957.52
  5060.2  959.43  5185.3  961.13  5219.7  962.15  5265.0  962.13  5327.3  963.28
  5431.0  963.43  5521.0  965.11  5674.2  964.57  5708.7  965.27  5825.0  964.64
#Mann=3,-1,0
  4468.5    0.12       0  5017.4    0.05       0  5021.4    0.12       0
Bank Sta=5017.4,5021.4
Exp/Cntr=0.3,0.1

Type RM Length L Ch R = 1,1882,195,195,195
BEGIN DESCRIPTION:
Bear Creek Tributary 16 3.0
END DESCRIPTION:
XS GIS Cut Line= 4
      2185625.02     13802224.98      2185925.00     13801925.00
      2185987.56     13801831.17      2186150.72     13801442.21
#Sta/Elev= 30
  4571.3  964.82  4599.6  963.70  4613.7  962.40  4670.3  960.89  4910.7  956.43
  4981.4  953.75  4992.0  952.33  4998.5  952.33  5007.1  950.91  5007.3  950.41
  5010.8  950.41  5011.1  950.91  5024.1  951.96  5031.6  953.40  5054.1  955.57
  5096.2  955.41  5135.9  956.24  5141.3  955.81  5247.2  956.23  5323.9  956.98
  5342.3  957.58  5353.6  958.52  5407.8  959.40  5418.6  958.97  5424.4  957.99
  5429.9  959.00  5431.3  958.81  5448.2  957.13  5476.1  956.67  5530.1  955.82
#Mann=5,-1,0
  4571.3    0.12       0  5007.1    0.05       0  5011.1    0.12       0
  5431.3    0.07       0  5476.1    0.12       0
Bank Sta=5007.1,5011.1
Exp/Cntr=0.3,0.1

Type RM Length L Ch R = 1,1687,256,256,256
BEGIN DESCRIPTION:
X18132
END DESCRIPTION:
XS GIS Cut Line= 3
      2185871.54     13802325.07      2186093.74     13802012.61
      2186208.76     13801575.81
#Sta/Elev= 30
  4630.4  961.59  4708.8  959.25  4790.0  957.51  4847.6  956.76  4885.0  955.17
  4940.9  953.08  4949.5  953.11  5006.1  949.40  5013.8  949.43  5019.7  948.44
  5019.9  947.94  5023.4  947.94  5023.7  948.44  5032.0  948.97  5037.8  950.03
  5072.9  951.71  5078.1  951.52  5083.7  951.95  5118.4  952.25  5145.8  953.19
  5158.7  953.03  5176.8  953.43  5193.9  954.55  5207.8  953.69  5274.5  954.93
  5321.6  958.03  5350.0  958.61  5355.2  958.28  5390.3  959.42  5465.5  959.37
#Mann=6,-1,0
  4630.4   0.035       0  4708.8    0.12       0  4847.6   0.035       0
  4885.0    0.12       0  5019.7    0.05       0  5023.7    0.12       0
Bank Sta=5019.7,5023.7
Exp/Cntr=0.3,0.1

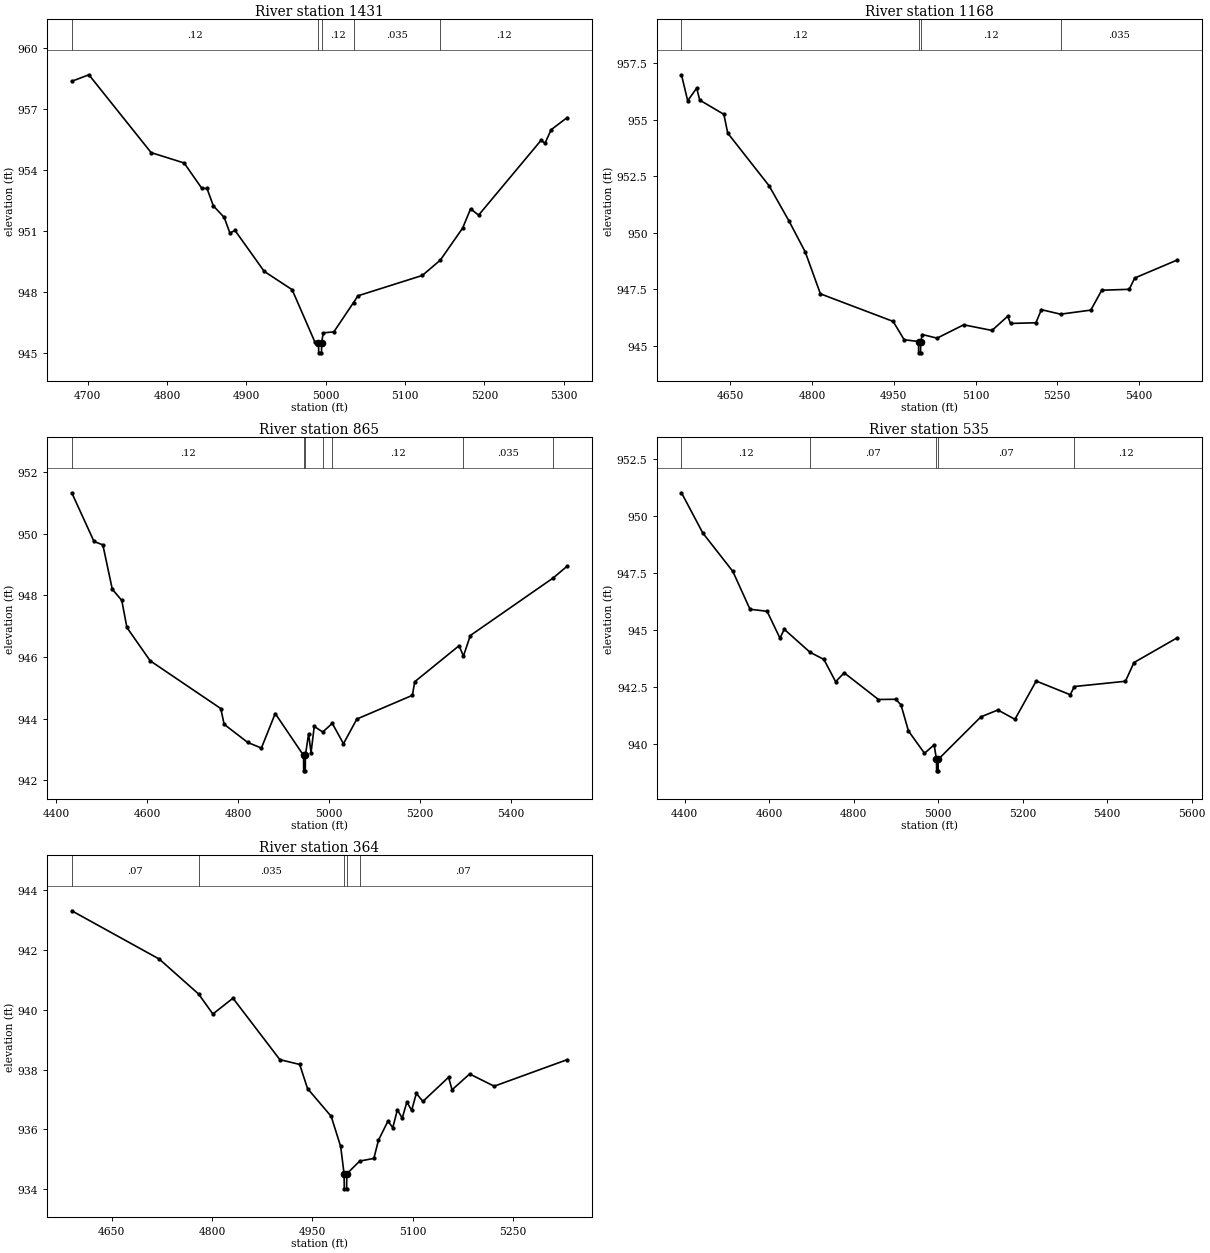
Type RM Length L Ch R = 1,1431,263,263,263
BEGIN DESCRIPTION:
Bear Creek Tributary 16 2.0
END DESCRIPTION:
XS GIS Cut Line= 3
      2186125.02     13802324.97      2186325.00     13802075.00
      2186274.99     13801774.96
#Sta/Elev= 30
  4679.9  958.36  4701.5  958.68  4779.9  954.86  4821.5  954.35  4843.9  953.10
  4850.3  953.10  4858.4  952.24  4872.0  951.68  4879.2  950.91  4885.6  951.04
  4922.4  949.03  4957.6  948.13  4986.4  945.55  4990.8  945.53  4991.1  945.03
  4994.6  945.03  4994.8  945.53  4996.8  946.01  5010.2  946.06  5035.0  947.50
  5040.6  947.83  5121.7  948.83  5144.3  949.58  5172.4  951.15  5182.5  952.10
  5192.6  951.79  5271.2  955.46  5276.3  955.32  5283.9  955.98  5304.2  956.58
#Mann=5,-1,0
  4679.9    0.12       0  4990.8    0.05       0  4994.8    0.12       0
  5035.0   0.035       0  5144.3    0.12       0
Bank Sta=4990.8,4994.8
Exp/Cntr=0.3,0.1

Type RM Length L Ch R = 1,1168,303,303,303
BEGIN DESCRIPTION:
X18131
END DESCRIPTION:
XS GIS Cut Line= 3
      2186239.61     13802325.08      2186548.60     13802165.39
      2186617.81     13801608.18
#Sta/Elev= 30
  4560.3  956.99  4571.7  955.84  4588.2  956.40  4593.8  955.87  4638.1  955.24
  4645.2  954.41  4721.1  952.08  4757.7  950.52  4787.5  949.15  4815.3  947.30
  4948.8  946.08  4969.0  945.27  4995.4  945.19  4995.6  944.69  4999.1  944.69
  4999.4  945.19  5002.4  945.50  5029.4  945.34  5078.3  945.93  5130.2  945.68
  5159.1  946.31  5164.2  945.99  5210.8  946.02  5220.9  946.60  5256.0  946.40
  5311.6  946.58  5331.7  947.46  5382.1  947.50  5392.2  948.00  5469.6  948.79
#Mann=4,-1,0
  4560.3    0.12       0  4995.4    0.05       0  4999.4    0.12       0
  5256.0   0.035       0
Bank Sta=4995.4,4999.4
Exp/Cntr=0.3,0.1

Type RM Length L Ch R = 1,865,330,330,330
BEGIN DESCRIPTION:
X18130
END DESCRIPTION:
XS GIS Cut Line= 4
      2186399.32     13802262.60      2186722.21     13802168.86
      2186822.47     13801908.85      2186745.22     13801440.47
#Sta/Elev= 30
  4433.8  951.33  4482.8  949.75  4502.2  949.64  4523.0  948.20  4543.8  947.84
  4555.1  946.96  4606.3  945.88  4761.6  944.33  4768.9  943.82  4820.9  943.23
  4850.9  943.05  4881.3  944.17  4943.6  942.81  4943.9  942.31  4947.4  942.31
  4947.6  942.81  4954.7  943.51  4960.1  942.90  4967.1  943.75  4985.8  943.57
  5006.8  943.85  5031.4  943.19  5060.8  943.99  5183.0  944.76  5188.1  945.20
  5285.7  946.37  5295.2  946.03  5310.4  946.70  5492.9  948.57  5523.4  948.95
#Mann=7,-1,0
  4433.8    0.12       0  4943.6    0.05       0  4947.6    0.12       0
  4985.8    0.07       0  5006.8    0.12       0  5295.2   0.035       0
  5492.9    0.12       0
Bank Sta=4943.6,4947.6
Exp/Cntr=0.3,0.1

Type RM Length L Ch R = 1,535,171,171,171
BEGIN DESCRIPTION:
Bear Creek Tributary 16 1.0
END DESCRIPTION:
XS GIS Cut Line= 3
      2186425.02     13802275.00      2187025.00     13802175.00
      2186962.66     13801613.91
#Sta/Elev= 30
  4392.3  951.01  4443.0  949.24  4513.9  947.56  4554.5  945.90  4595.0  945.81
  4625.5  944.63  4635.6  945.02  4696.8  944.01  4729.4  943.70  4757.2  942.72
  4777.5  943.11  4858.6  941.94  4899.2  941.95  4911.9  941.71  4929.6  940.56
  4967.6  939.58  4990.4  939.95  4996.0  939.31  4996.3  938.81  4999.8  938.81
  5000.0  939.31  5101.2  941.18  5141.4  941.48  5181.7  941.07  5232.0  942.75
  5312.5  942.15  5322.5  942.51  5443.3  942.74  5463.4  943.56  5565.1  944.64
#Mann=5,-1,0
  4392.3    0.12       0  4696.8    0.07       0  4996.0    0.05       0
  5000.0    0.07       0  5322.5    0.12       0
Bank Sta=4996,5000
Exp/Cntr=0.3,0.1

Type RM Length L Ch R = 1,364,0,0,0
BEGIN DESCRIPTION:
X18129
END DESCRIPTION:
XS GIS Cut Line= 4
      2186774.30     13802293.86      2187114.57     13802311.22
      2187246.51     13802182.75      2187315.38     13801978.30
#Sta/Elev= 30
  4590.3  943.32  4721.2  941.70  4779.9  940.53  4801.3  939.86  4831.3  940.39
  4901.4  938.33  4931.0  938.17  4942.8  937.36  4978.1  936.43  4992.3  935.42
  4997.4  934.50  4997.7  934.00  5001.2  934.00  5001.4  934.50  5020.7  934.93
  5041.9  935.02  5048.8  935.63  5063.0  936.27  5070.2  936.05  5077.1  936.65
  5084.3  936.37  5091.3  936.91  5098.4  936.63  5105.4  937.20  5115.2  936.93
  5153.6  937.74  5158.8  937.32  5185.1  937.85  5221.8  937.44  5330.9  938.33
#Mann=5,-1,0
  4590.3    0.07       0  4779.9   0.035       0  4997.4   0.035       0
  5001.4   0.035       0  5020.7    0.07       0
Bank Sta=4997.4,5001.4
Exp/Cntr=0.3,0.1

Chan Stop Cuts=-1