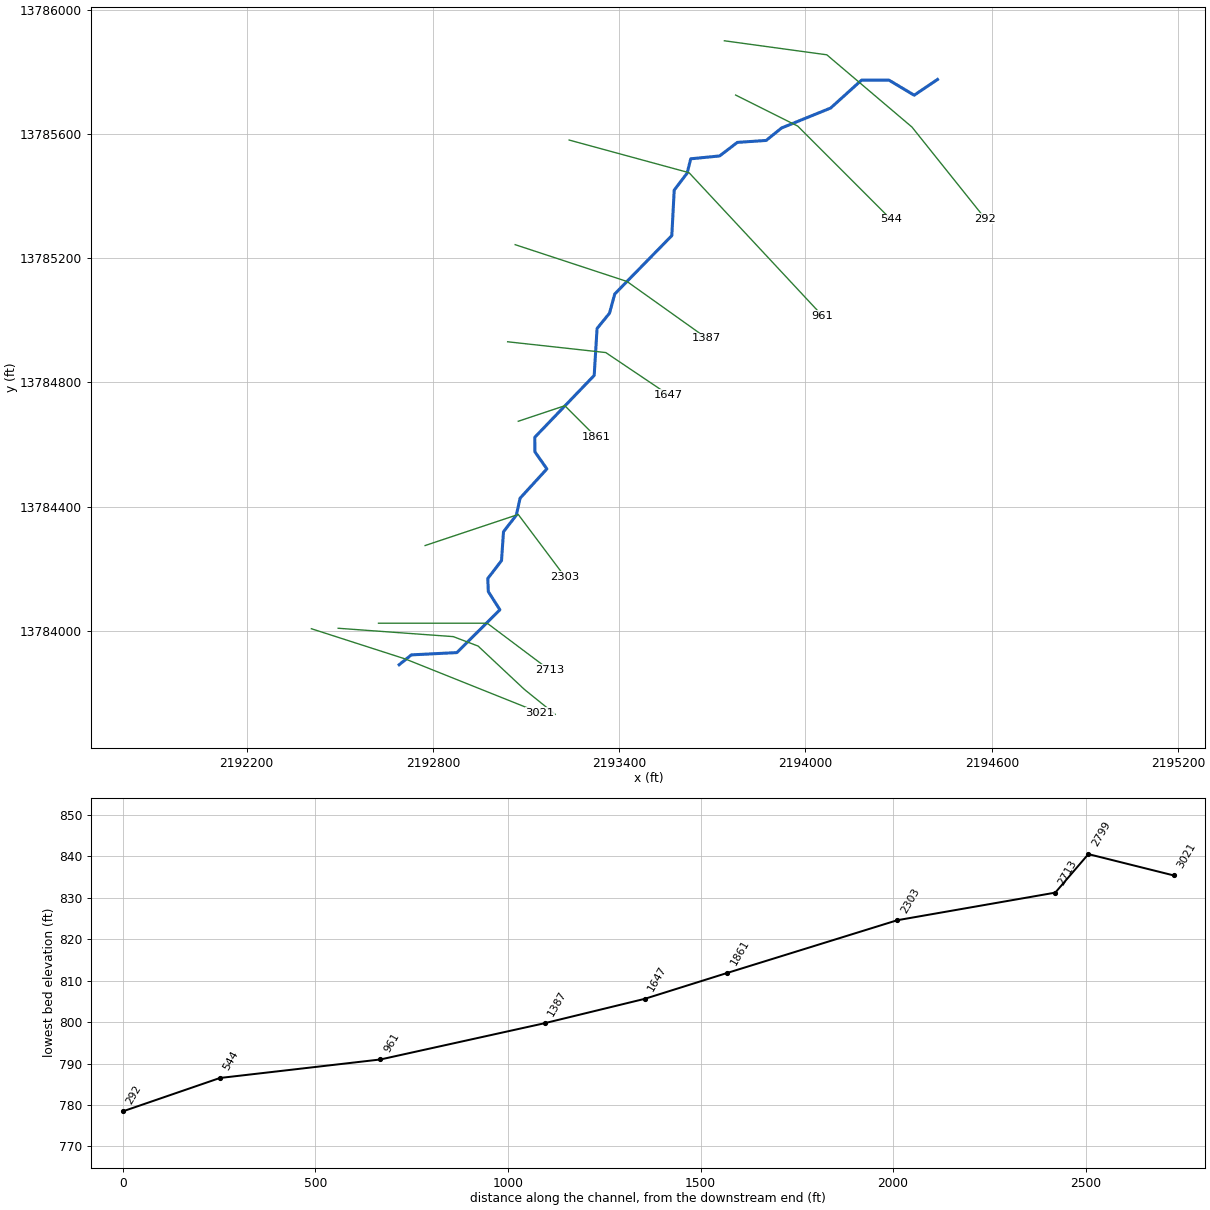
--- Bear Creek Tributary 2.prj (project) ---

Proj Title=Bear Creek Tributary 2 Base Level Engineering
Current Plan=p01
Default Exp/Contr=0.3,0.1
English Units
Geom File=g01
Flow File=f01
Plan File=p01
BEGIN DESCRIPTION:
Bear Creek Tributary 2
END DESCRIPTION:

--- Bear Creek Tributary 2.p01 (plan) ---

Plan Title=Multiple Run
Short Identifier=Multiple
Geom File=g01
Flow File=f01
Subcritical Flow
K Sum by GR= 0
Std Step Tol= 0.01
Critical Tol= 0.01
Num of Std Step Trials= 20
Max Error Tol= 0.3
Flow Tol Ratio= 0.001
Split Flow NTrial= 30
Split Flow Tol= 0.02
Split Flow Ratio= 0.02
Log Output Level= 0
Friction Slope Method= 1
Unsteady Friction Slope Method= 2
Unsteady Bridges Friction Slope Method= 1
Parabolic Critical Depth
Global Vel Dist=  1 , 1 , 1
Global Log Level= 0
CheckData=True
Encroach Param= -1, 0, 0, 0
BEGIN DESCRIPTION:
Multiple Run
END DESCRIPTION:

--- Bear Creek Tributary 2.f01 (steady flow) ---

Flow Title=Multiple
Number of Profiles=7
Profile Names=10-year,25-year,50-year,1pct_min,100-year,1pct_plu,500-year
River Rch & RM= Bear Creek Tribu,Reach-1,3021
     704    1165    1593    1057    2110    4209    3658
Boundary for River Rch & Prof#=Bear Creek Tribu,Reach-1,1
Up Type=0
Dn Type=3
Dn Slope=0.005
Boundary for River Rch & Prof#=Bear Creek Tribu,Reach-1,2
Up Type=0
Dn Type=3
Dn Slope=0.005
Boundary for River Rch & Prof#=Bear Creek Tribu,Reach-1,3
Up Type=0
Dn Type=3
Dn Slope=0.005
Boundary for River Rch & Prof#=Bear Creek Tribu,Reach-1,4
Up Type=0
Dn Type=3
Dn Slope=0.005
Boundary for River Rch & Prof#=Bear Creek Tribu,Reach-1,5
Up Type=0
Dn Type=3
Dn Slope=0.005
Boundary for River Rch & Prof#=Bear Creek Tribu,Reach-1,6
Up Type=0
Dn Type=3
Dn Slope=0.005
Boundary for River Rch & Prof#=Bear Creek Tribu,Reach-1,7
Up Type=0
Dn Type=3
Dn Slope=0.005

--- Bear Creek Tributary 2.g01 (geometry) ---

Geom Title=Existing Conditions

River Reach=Bear Creek Tribu,Reach-1
Reach XY= 30
      2192691.41     13783891.41      2192730.80     13783923.07
      2192877.45     13783930.46      2193015.85     13784068.27
      2192978.62     13784126.63      2192976.86     13784168.87
      2193021.11     13784226.58      2193027.44     13784319.44
      2193068.86     13784372.83      2193080.86     13784427.30
      2193167.17     13784521.60      2193128.59     13784576.65
      2193128.16     13784623.35      2193319.53     13784822.55
      2193328.76     13784973.44      2193368.86     13785022.83
      2193385.76     13785084.68      2193569.53     13785272.55
      2193577.24     13785419.09      2193618.70     13785473.22
      2193630.44     13785519.75      2193723.33     13785528.89
      2193780.57     13785572.53      2193873.42     13785578.83
      2193922.82     13785618.88      2194081.05     13785683.16
      2194180.49     13785772.91      2194269.04     13785772.82
      2194349.95     13785724.39      2194425.00     13785775.00

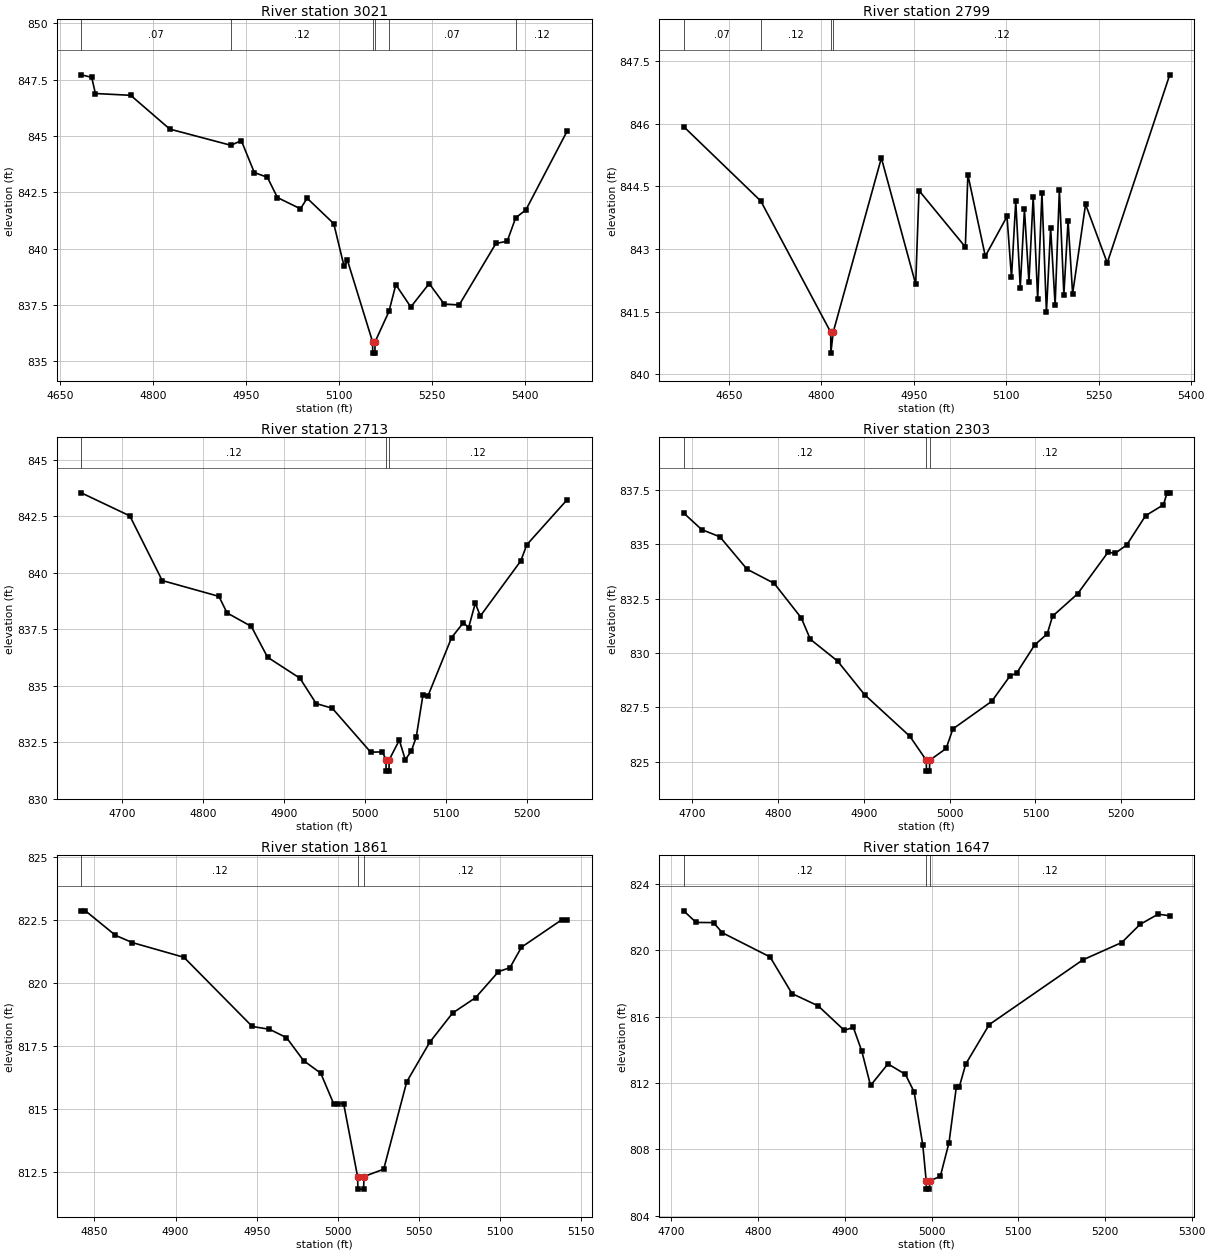
Type RM Length L Ch R = 1,3021,222,222,222
BEGIN DESCRIPTION:
X18136
END DESCRIPTION:
XS GIS Cut Line= 3
      2192408.90     13784007.24      2192710.98     13783910.01
      2193145.01     13783736.40
#Sta/Elev= 30
  4683.6  847.72  4700.5  847.61  4706.5  846.89  4763.5  846.81  4826.6  845.31
  4925.4  844.59  4942.1  844.80  4963.1  843.38  4984.2  843.17  5000.4  842.27
  5037.6  841.77  5048.4  842.24  5091.4  841.11  5108.1  839.21  5113.5  839.48
  5154.1  835.86  5154.3  835.36  5157.8  835.36  5158.1  835.86  5180.5  837.21
  5191.6  838.40  5215.8  837.41  5245.5  838.45  5269.7  837.54  5293.9  837.50
  5353.2  840.23  5371.5  840.33  5385.1  841.37  5401.6  841.72  5468.4  845.23
#Mann=6,-1,0
  4683.6    0.07       0  4925.4    0.12       0  5154.1    0.05       0
  5158.1    0.12       0  5180.5    0.07       0  5385.1    0.12       0
Bank Sta=5154.1,5158.1
Exp/Cntr=0.3,0.1

Type RM Length L Ch R = 1,2799,86,86,86
BEGIN DESCRIPTION:
Bear Creek Tributary 2 7.0
END DESCRIPTION:
XS GIS Cut Line= 5
      2192495.08     13784008.76      2192865.79     13783981.85
      2192945.65     13783951.46      2193094.95     13783811.71
      2193193.91     13783731.85
#Sta/Elev= 30
  4576.7  845.93  4701.8  844.15  4815.3  841.01  4815.5  840.51  4819.3  841.01
  4897.5  845.18  4953.2  842.16  4958.6  844.40  5033.8  843.05  5037.9  844.78
  5066.2  842.83  5101.4  843.78  5108.7  842.32  5115.6  844.15  5122.9  842.08
  5129.7  843.95  5137.0  842.21  5143.9  844.25  5151.2  841.81  5158.1  844.34
  5165.4  841.49  5172.2  843.51  5179.5  841.66  5186.4  844.41  5193.7  841.91
  5200.5  843.68  5207.9  841.93  5228.9  844.07  5264.1  842.67  5365.5  847.17
#Mann=4,-1,0
  4576.7    0.07       0  4701.8    0.12       0  4815.3    0.05       0
  4819.3    0.12       0
Bank Sta=4815.3,4819.3
Exp/Cntr=0.3,0.1

Type RM Length L Ch R = 1,2713,410,410,410
BEGIN DESCRIPTION:
Bear Creek Tributary 2 6.0
END DESCRIPTION:
XS GIS Cut Line= 3
      2192624.97     13784025.00      2192975.00     13784025.00
      2193174.97     13783875.02
#Sta/Elev= 30
  4649.6  843.53  4709.6  842.51  4749.6  839.65  4819.6  838.95  4829.6  838.22
  4859.6  837.62  4879.6  836.26  4919.6  835.33  4939.6  834.21  4959.6  834.00
  5006.9  832.06  5021.5  832.07  5025.8  831.72  5026.0  831.22  5029.5  831.22
  5029.8  831.72  5042.3  832.59  5049.6  831.73  5056.9  832.09  5063.2  832.73
  5071.5  834.59  5077.8  834.56  5106.9  837.13  5121.5  837.79  5127.8  837.56
  5136.1  838.65  5142.3  838.08  5192.3  840.52  5199.6  841.23  5249.6  843.23
#Mann=3,-1,0
  4649.6    0.12       0  5025.8    0.05       0  5029.8    0.12       0
Bank Sta=5025.8,5029.8
Exp/Cntr=0.3,0.1

Type RM Length L Ch R = 1,2303,442,442,442
BEGIN DESCRIPTION:
Bear Creek Tributary 2 5.0
END DESCRIPTION:
XS GIS Cut Line= 3
      2192775.03     13784275.01      2193075.00     13784375.00
      2193225.00     13784174.99
#Sta/Elev= 30
  4690.2  836.43  4711.2  835.67  4732.3  835.34  4764.0  833.85  4795.6  833.20
  4827.2  831.61  4837.7  830.63  4869.4  829.63  4901.0  828.08  4953.7  826.17
  4972.8  825.07  4973.0  824.57  4976.5  824.57  4976.8  825.07  4995.9  825.61
  5003.8  826.51  5049.1  827.78  5069.9  828.92  5078.3  829.09  5099.1  830.37
  5113.7  830.88  5119.9  831.69  5149.1  832.72  5184.5  834.63  5192.9  834.58
  5206.4  834.97  5228.3  836.31  5249.1  836.81  5253.3  837.36  5256.4  837.36
#Mann=3,-1,0
  4690.2    0.12       0  4972.8    0.05       0  4976.8    0.12       0
Bank Sta=4972.8,4976.8
Exp/Cntr=0.3,0.1

Type RM Length L Ch R = 1,1861,214,214,214
BEGIN DESCRIPTION:
Bear Creek Tributary 2 4.0
END DESCRIPTION:
XS GIS Cut Line= 3
      2193074.99     13784675.00      2193225.00     13784725.00
      2193324.97     13784625.03
#Sta/Elev= 27
  4841.9  822.86  4844.5  822.86  4863.0  821.89  4873.5  821.60  4905.2  821.02
  4947.3  818.28  4957.9  818.17  4968.4  817.84  4978.9  816.93  4989.5  816.43
  4997.4  815.23  5000.0  815.23  5003.6  815.23  5012.2  812.34  5012.4  811.84
  5015.9  811.84  5016.2  812.34  5028.3  812.63  5042.5  816.09  5056.6  817.65
  5070.7  818.81  5084.9  819.42  5099.0  820.45  5106.1  820.61  5113.2  821.42
  5137.9  822.50  5141.4  822.50
#Mann=3,-1,0
  4841.9    0.12       0  5012.2    0.05       0  5016.2    0.12       0
Bank Sta=5012.2,5016.2
Exp/Cntr=0.3,0.1

Type RM Length L Ch R = 1,1647,260,260,260
BEGIN DESCRIPTION:
X18137
END DESCRIPTION:
XS GIS Cut Line= 3
      2193040.81     13784930.85      2193356.81     13784896.13
      2193558.21     13784760.70
#Sta/Elev= 30
  4714.1  822.38  4728.4  821.68  4748.5  821.67  4758.6  821.06  4813.7  819.60
  4839.0  817.39  4869.2  816.65  4899.4  815.17  4909.7  815.36  4919.5  813.92
  4929.6  811.85  4949.7  813.15  4969.8  812.52  4979.9  811.46  4989.9  808.24
  4993.8  806.10  4994.0  805.60  4997.5  805.60  4997.8  806.10  5010.1  806.37
  5020.1  808.40  5028.6  811.77  5032.0  811.77  5039.4  813.14  5066.5  815.52
  5174.4  819.42  5219.4  820.47  5240.4  821.56  5261.4  822.18  5274.7  822.08
#Mann=3,-1,0
  4714.1    0.12       0  4993.8    0.05       0  4997.8    0.12       0
Bank Sta=4993.8,4997.8
Exp/Cntr=0.3,0.1

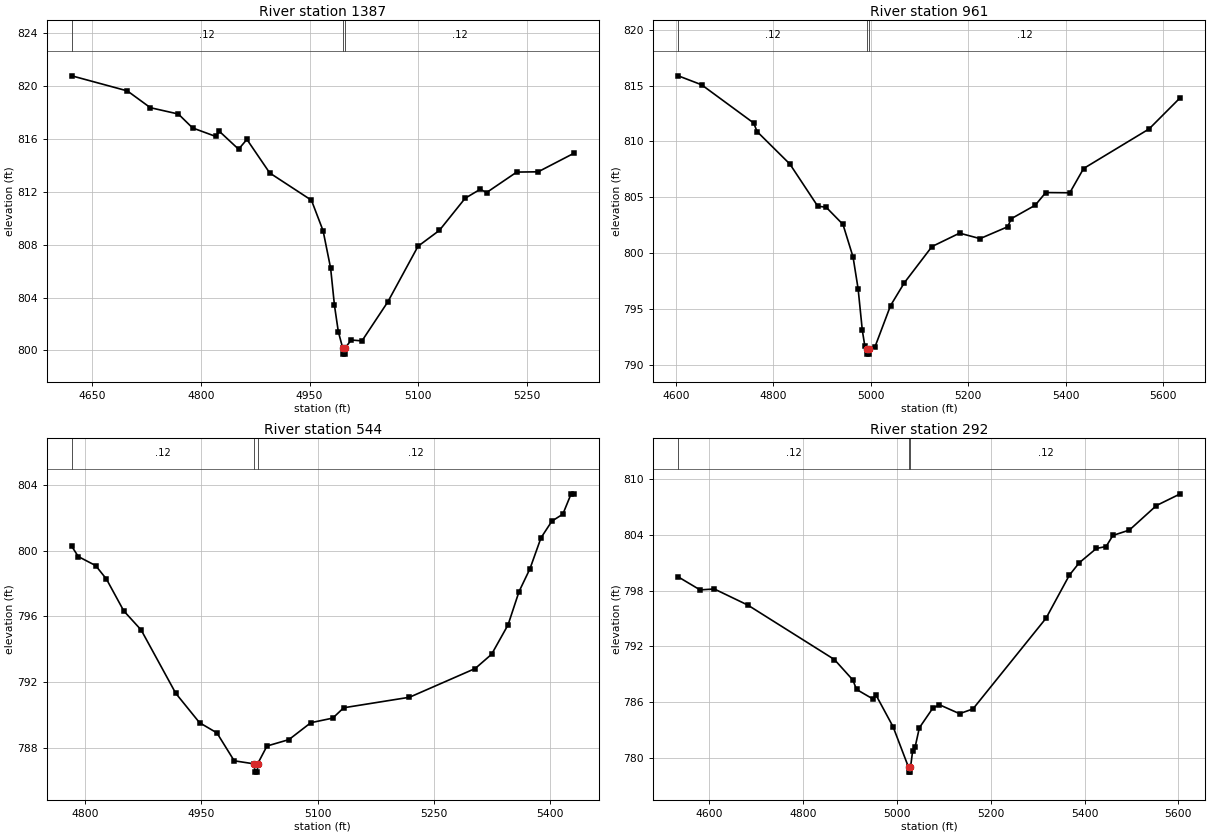
Type RM Length L Ch R = 1,1387,426,426,426
BEGIN DESCRIPTION:
Bear Creek Tributary 2 3.0
END DESCRIPTION:
XS GIS Cut Line= 3
      2193065.11     13785243.36      2193425.00     13785125.00
      2193681.60     13784942.40
#Sta/Elev= 30
  4621.4  820.77  4698.2  819.63  4730.0  818.36  4768.7  817.88  4788.3  816.83
  4820.1  816.19  4825.4  816.57  4851.9  815.22  4863.4  815.96  4895.0  813.42
  4952.6  811.36  4968.7  809.05  4979.1  806.22  4984.4  803.41  4989.7  801.43
  4995.6  800.22  4995.9  799.72  4999.4  799.72  4999.6  800.22  5007.6  800.79
  5022.4  800.72  5058.1  803.67  5099.9  807.88  5129.4  809.08  5165.0  811.51
  5185.9  812.19  5194.6  811.94  5236.3  813.49  5265.9  813.51  5315.2  814.91
#Mann=3,-1,0
  4621.4    0.12       0  4995.6    0.05       0  4999.6    0.12       0
Bank Sta=4995.6,4999.6
Exp/Cntr=0.3,0.1

Type RM Length L Ch R = 1,961,417,417,417
BEGIN DESCRIPTION:
Bear Creek Tributary 2 2.0
END DESCRIPTION:
XS GIS Cut Line= 3
      2193238.77     13785580.15      2193625.00     13785475.00
      2194054.74     13785014.17
#Sta/Elev= 30
  4604.7  815.87  4652.6  815.07  4759.5  811.65  4766.6  810.88  4833.8  807.98
  4891.0  804.21  4908.2  804.12  4942.8  802.58  4963.5  799.66  4973.9  796.81
  4982.5  793.10  4987.7  791.69  4992.6  791.48  4992.9  790.98  4996.4  790.98
  4996.6  791.48  5008.4  791.62  5040.4  795.32  5068.7  797.36  5125.4  800.60
  5182.1  801.80  5224.1  801.31  5280.8  802.37  5288.1  803.09  5337.4  804.30
  5358.9  805.43  5408.3  805.41  5436.6  807.58  5571.0  811.12  5635.1  813.92
#Mann=3,-1,0
  4604.7    0.12       0  4992.6    0.05       0  4996.6    0.12       0
Bank Sta=4992.6,4996.6
Exp/Cntr=0.3,0.1

Type RM Length L Ch R = 1,544,252,252,252
BEGIN DESCRIPTION:
Bear Creek Tributary 2 1.0
END DESCRIPTION:
XS GIS Cut Line= 3
      2193774.98     13785725.01      2193975.00     13785625.00
      2194275.01     13785324.99
#Sta/Elev= 30
  4782.7  800.26  4791.1  799.64  4813.5  799.09  4827.4  798.27  4849.8  796.33
  4872.2  795.17  4916.9  791.31  4947.6  789.52  4970.0  788.90  4992.3  787.20
  5018.5  787.01  5018.7  786.51  5022.2  786.51  5022.5  787.01  5034.6  788.10
  5062.9  788.49  5091.2  789.52  5119.5  789.80  5133.6  790.43  5218.5  791.07
  5303.3  792.82  5324.5  793.69  5345.7  795.48  5359.9  797.51  5374.0  798.90
  5388.2  800.78  5402.3  801.80  5416.4  802.22  5427.1  803.46  5430.6  803.46
#Mann=3,-1,0
  4782.7    0.12       0  5018.5    0.05       0  5022.5    0.12       0
Bank Sta=5018.5,5022.5
Exp/Cntr=0.3,0.1

Type RM Length L Ch R = 1,292,0,0,0
BEGIN DESCRIPTION:
X18135
END DESCRIPTION:
XS GIS Cut Line= 4
      2193738.78     13785899.59      2194068.62     13785854.46
      2194342.93     13785621.82      2194579.01     13785326.72
#Sta/Elev= 30
  4533.7  799.47  4580.3  798.07  4610.6  798.17  4682.3  796.43  4866.6  790.58
  4906.1  788.37  4913.8  787.36  4948.9  786.33  4955.5  786.74  4991.8  783.34
  5024.9  778.96  5025.2  778.46  5028.7  778.46  5028.9  778.96  5033.5  780.73
  5038.9  781.19  5047.8  783.23  5076.4  785.34  5090.6  785.71  5133.5  784.75
  5162.1  785.26  5318.0  795.03  5367.6  799.65  5388.7  800.99  5425.2  802.53
  5446.0  802.74  5460.4  803.93  5495.6  804.51  5553.3  807.15  5604.2  808.41
#Mann=3,-1,0
  4533.7    0.12       0  5024.9    0.05       0  5028.9    0.12       0
Bank Sta=5024.9,5028.9
Exp/Cntr=0.3,0.1

Chan Stop Cuts=-1