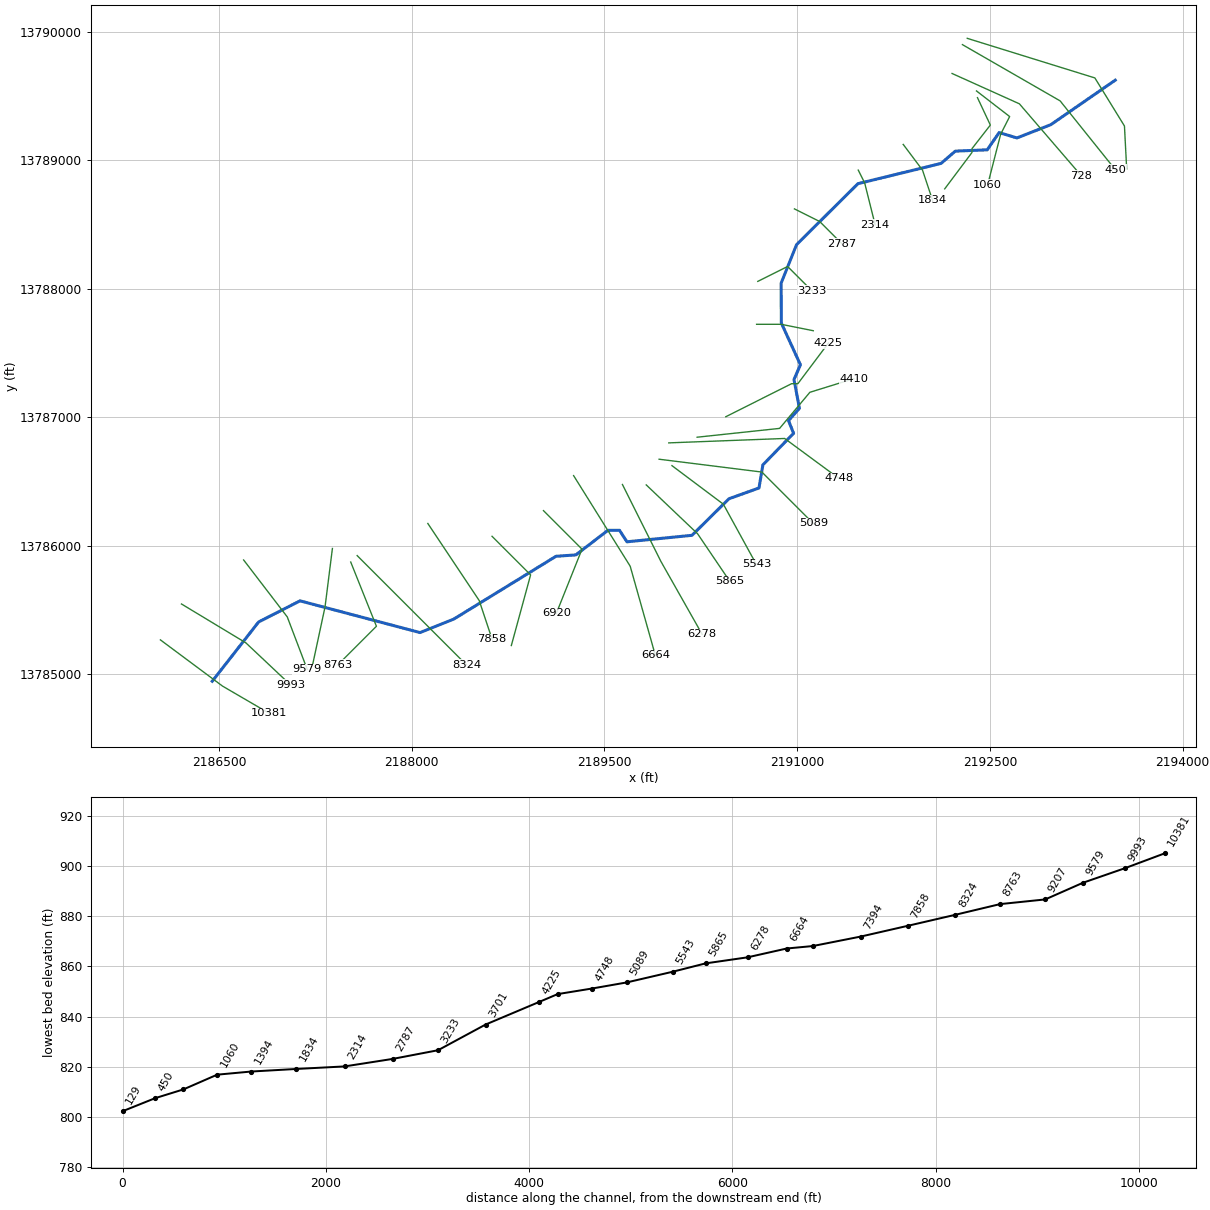
--- Bear Creek Tributary 3.prj (project) ---

Proj Title=Bear Creek Tributary 3 Base Level Engineering
Current Plan=p01
Default Exp/Contr=0.3,0.1
English Units
Geom File=g01
Flow File=f01
Plan File=p01
BEGIN DESCRIPTION:
Bear Creek Tributary 3
END DESCRIPTION:

--- Bear Creek Tributary 3.p01 (plan) ---

Plan Title=Multiple Run
Short Identifier=Multiple
Geom File=g01
Flow File=f01
Subcritical Flow
K Sum by GR= 0
Std Step Tol= 0.01
Critical Tol= 0.01
Num of Std Step Trials= 20
Max Error Tol= 0.3
Flow Tol Ratio= 0.001
Split Flow NTrial= 30
Split Flow Tol= 0.02
Split Flow Ratio= 0.02
Log Output Level= 0
Friction Slope Method= 1
Unsteady Friction Slope Method= 2
Unsteady Bridges Friction Slope Method= 1
Parabolic Critical Depth
Global Vel Dist=  1 , 1 , 1
Global Log Level= 0
CheckData=True
Encroach Param= -1, 0, 0, 0
BEGIN DESCRIPTION:
Multiple Run
END DESCRIPTION:

--- Bear Creek Tributary 3.f01 (steady flow) ---

Flow Title=Multiple
Number of Profiles=7
Profile Names=10-year,25-year,50-year,1pct_min,100-year,1pct_plu,500-year
River Rch & RM= Bear Creek Tribu,Reach-1,10381
     448     716     955     619    1235    2465    2042
River Rch & RM= Bear Creek Tribu,Reach-1,9207
     838    1382    1884    1244    2482    4952    4261
River Rch & RM= Bear Creek Tribu,Reach-1,5865
    1324    2247    3123    2099    4187    8355    7456
Boundary for River Rch & Prof#=Bear Creek Tribu,Reach-1,1
Up Type=0
Dn Type=3
Dn Slope=0.005
Boundary for River Rch & Prof#=Bear Creek Tribu,Reach-1,2
Up Type=0
Dn Type=3
Dn Slope=0.005
Boundary for River Rch & Prof#=Bear Creek Tribu,Reach-1,3
Up Type=0
Dn Type=3
Dn Slope=0.005
Boundary for River Rch & Prof#=Bear Creek Tribu,Reach-1,4
Up Type=0
Dn Type=3
Dn Slope=0.005
Boundary for River Rch & Prof#=Bear Creek Tribu,Reach-1,5
Up Type=0
Dn Type=3
Dn Slope=0.005
Boundary for River Rch & Prof#=Bear Creek Tribu,Reach-1,6
Up Type=0
Dn Type=3
Dn Slope=0.005
Boundary for River Rch & Prof#=Bear Creek Tribu,Reach-1,7
Up Type=0
Dn Type=3
Dn Slope=0.005

--- Bear Creek Tributary 3.g01 (geometry) ---

Geom Title=Existing Conditions

River Reach=Bear Creek Tribu,Reach-1
Reach XY= 30
      2186447.25     13784947.25      2186808.25     13785408.54
      2187130.56     13785572.74      2188064.31     13785325.77
      2188327.29     13785430.84      2189122.56     13785919.52
      2189277.44     13785930.48      2189526.57     13786121.56
      2189616.95     13786121.81      2189674.70     13786032.26
      2190181.18     13786082.83      2190468.55     13786367.26
      2190702.30     13786451.09      2190732.82     13786631.19
      2190971.64     13786876.71      2190932.37     13786975.09
      2191017.18     13787071.58      2190974.65     13787295.15
      2191024.91     13787409.61      2190876.36     13787734.65
      2190874.64     13788045.15      2190994.78     13788345.09
      2191472.57     13788819.48      2192119.51     13788977.27
      2192230.45     13789072.81      2192478.58     13789082.89
      2192571.33     13789217.30      2192709.73     13789175.37
      2192973.50     13789278.62      2193475.00     13789625.00

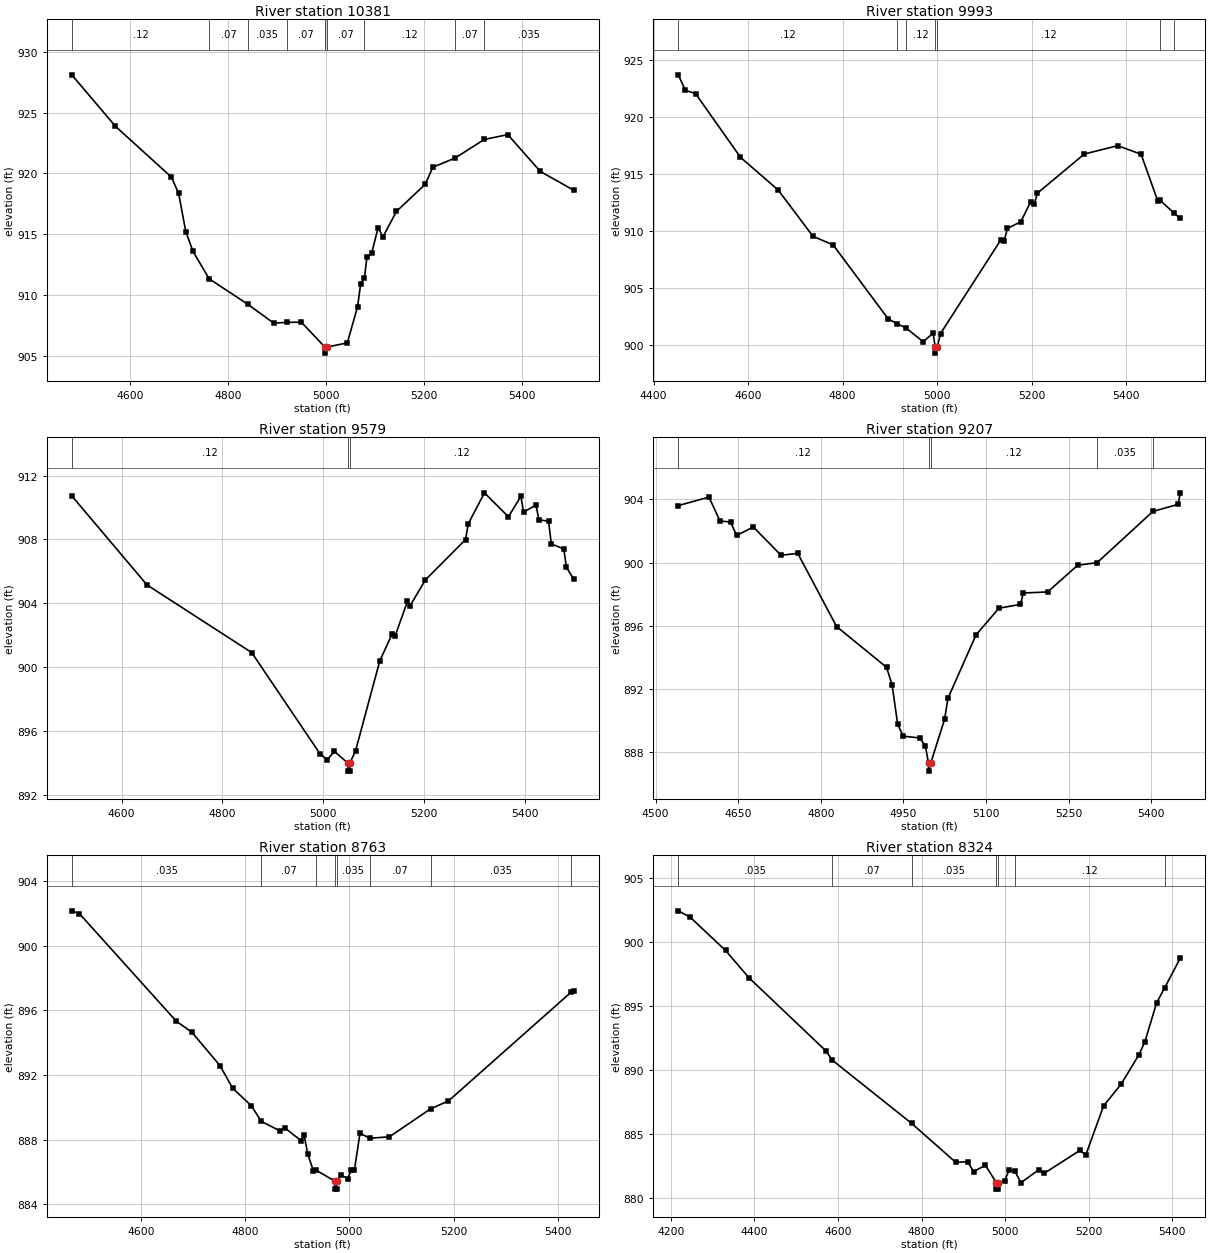
Type RM Length L Ch R = 1,10381,388,388,388
BEGIN DESCRIPTION:
X18142
END DESCRIPTION:
XS GIS Cut Line= 3
      2186043.59     13785269.06      2186527.27     13784909.18
      2186891.47     13784696.97
#Sta/Elev= 30
  4481.5  928.11  4570.5  923.88  4684.9  919.69  4699.5  918.35  4714.2  915.20
  4728.8  913.58  4761.8  911.33  4840.3  909.24  4893.5  907.68  4920.3  907.74
  4949.8  907.76  4997.9  905.71  4998.1  905.21  5001.9  905.71  5043.7  906.05
  5064.6  909.03  5070.8  910.87  5078.7  911.42  5083.7  913.09  5093.3  913.43
  5106.6  915.53  5116.5  914.78  5143.9  916.87  5202.6  919.10  5218.3  920.51
  5263.6  921.26  5323.0  922.79  5371.1  923.19  5437.5  920.16  5505.9  918.61
#Mann=9,-1,0
  4481.5    0.12       0  4761.8    0.07       0  4840.3   0.035       0
  4920.3    0.07       0  4997.9    0.05       0  5001.9    0.07       0
  5078.7    0.12       0  5263.6    0.07       0  5323.0   0.035       0
Bank Sta=4997.9,5001.9
Exp/Cntr=0.3,0.1

Type RM Length L Ch R = 1,9993,414,414,414
BEGIN DESCRIPTION:
Bear Creek Tributary 3 21.0
END DESCRIPTION:
XS GIS Cut Line= 3
      2186207.70     13785548.35      2186708.66     13785246.05
      2187055.92     13784918.88
#Sta/Elev= 30
  4452.2  923.71  4467.5  922.35  4488.8  922.07  4583.9  916.48  4663.5  913.62
  4737.3  909.56  4780.0  908.80  4896.4  902.32  4916.0  901.88  4933.2  901.55
  4970.2  900.33  4991.5  901.05  4996.0  899.82  4996.2  899.32  5000.0  899.82
  5007.1  901.04  5134.5  909.23  5141.8  909.17  5148.6  910.25  5176.9  910.83
  5198.0  912.60  5205.3  912.36  5212.1  913.34  5311.3  916.77  5382.1  917.50
  5431.4  916.75  5467.0  912.62  5470.7  912.74  5500.6  911.62  5514.4  911.12
#Mann=7,-1,0
  4452.2    0.12       0  4916.0    0.07       0  4933.2    0.12       0
  4996.0    0.05       0  5000.0    0.12       0  5470.7   0.035       0
  5500.6    0.07       0
Bank Sta=4996,5000
Exp/Cntr=0.3,0.1

Type RM Length L Ch R = 1,9579,372,372,372
BEGIN DESCRIPTION:
Bear Creek Tributary 3 20.0
END DESCRIPTION:
XS GIS Cut Line= 3
      2186691.38     13785890.99      2187031.13     13785447.59
      2187186.35     13785039.40
#Sta/Elev= 30
  4501.3  910.73  4650.4  905.15  4858.0  900.91  4993.1  894.58  5007.6  894.19
  5022.1  894.72  5048.6  893.98  5048.8  893.48  5052.3  893.48  5052.6  893.98
  5064.0  894.77  5111.9  900.39  5136.7  902.10  5142.0  901.93  5166.8  904.12
  5172.1  903.85  5202.2  905.46  5281.9  907.99  5287.3  908.98  5319.4  910.92
  5366.9  909.42  5391.6  910.70  5397.0  909.71  5421.8  910.16  5427.1  909.23
  5446.5  909.14  5451.9  907.72  5476.6  907.40  5482.0  906.25  5496.6  905.49
#Mann=3,-1,0
  4501.3    0.12       0  5048.6    0.05       0  5052.6    0.12       0
Bank Sta=5048.6,5052.6
Exp/Cntr=0.3,0.1

Type RM Length L Ch R = 1,9207,444,444,444
BEGIN DESCRIPTION:
Bear Creek Tributary 3 19.0
END DESCRIPTION:
XS GIS Cut Line= 3
      2187382.39     13785980.28      2187325.00     13785525.00
      2187229.89     13785082.39
#Sta/Elev= 30
  4541.1  903.61  4596.8  904.15  4617.0  902.64  4636.1  902.57  4647.2  901.72
  4677.4  902.26  4727.8  900.47  4758.1  900.59  4828.6  895.96  4919.3  893.38
  4929.4  892.27  4939.5  889.78  4949.6  889.02  4979.8  888.91  4989.9  888.39
  4995.5  887.31  4995.7  886.81  4999.5  887.31  5024.7  890.09  5030.7  891.41
  5081.8  895.43  5123.4  897.12  5162.5  897.36  5167.7  898.08  5211.9  898.15
  5266.4  899.84  5301.6  900.00  5402.9  903.24  5448.5  903.69  5452.7  904.42
#Mann=5,-1,0
  4541.1    0.12       0  4995.5    0.05       0  4999.5    0.12       0
  5301.6   0.035       0  5402.9    0.07       0
Bank Sta=4995.5,4999.5
Exp/Cntr=0.3,0.1

Type RM Length L Ch R = 1,8763,439,439,439
BEGIN DESCRIPTION:
Bear Creek Tributary 3 18.0
END DESCRIPTION:
XS GIS Cut Line= 3
      2187525.00     13785874.99      2187725.00     13785375.00
      2187424.98     13785074.98
#Sta/Elev= 30
  4467.6  902.17  4482.4  901.99  4668.2  895.33  4697.8  894.66  4751.7  892.59
  4775.9  891.20  4812.2  890.09  4831.1  889.13  4866.1  888.56  4876.9  888.71
  4907.8  887.93  4913.2  888.28  4919.9  887.14  4930.7  886.09  4935.1  886.13
  4971.8  885.44  4972.0  884.94  4975.5  884.94  4975.8  885.44  4984.6  885.80
  4996.7  885.59  5003.4  886.11  5009.6  886.11  5020.2  888.39  5039.6  888.09
  5076.8  888.18  5155.6  889.91  5190.0  890.40  5425.4  897.14  5430.4  897.19
#Mann=8,-1,0
  4467.6   0.035       0  4831.1    0.07       0  4935.1   0.035       0
  4971.8   0.035       0  4975.8   0.035       0  5039.6    0.07       0
  5155.6   0.035       0  5425.4    0.07       0
Bank Sta=4971.8,4975.8
Exp/Cntr=0.3,0.1

Type RM Length L Ch R = 1,8324,466,466,466
BEGIN DESCRIPTION:
Bear Creek Tributary 3 17.0
END DESCRIPTION:
XS GIS Cut Line= 3
      2187574.98     13785925.02      2188125.00     13785375.00
      2188424.99     13785075.01
#Sta/Elev= 30
  4217.5  902.46  4245.8  901.97  4330.7  899.36  4387.2  897.21  4571.1  891.50
  4586.1  890.78  4776.1  885.83  4882.2  882.77  4910.5  882.83  4924.6  882.05
  4952.9  882.55  4979.2  881.18  4979.5  880.68  4983.0  880.68  4983.2  881.18
  4998.9  881.34  5009.5  882.14  5023.3  882.11  5037.8  881.18  5080.2  882.18
  5094.3  881.93  5179.2  883.71  5193.3  883.35  5235.8  887.19  5278.2  888.91
  5320.6  891.20  5334.8  892.22  5363.0  895.27  5381.9  896.42  5419.6  898.76
#Mann=7,-1,0
  4217.5   0.035       0  4586.1    0.07       0  4776.1   0.035       0
  4979.2   0.035       0  4983.2   0.035       0  5023.3    0.12       0
  5381.9   0.035       0
Bank Sta=4979.2,4983.2
Exp/Cntr=0.3,0.1

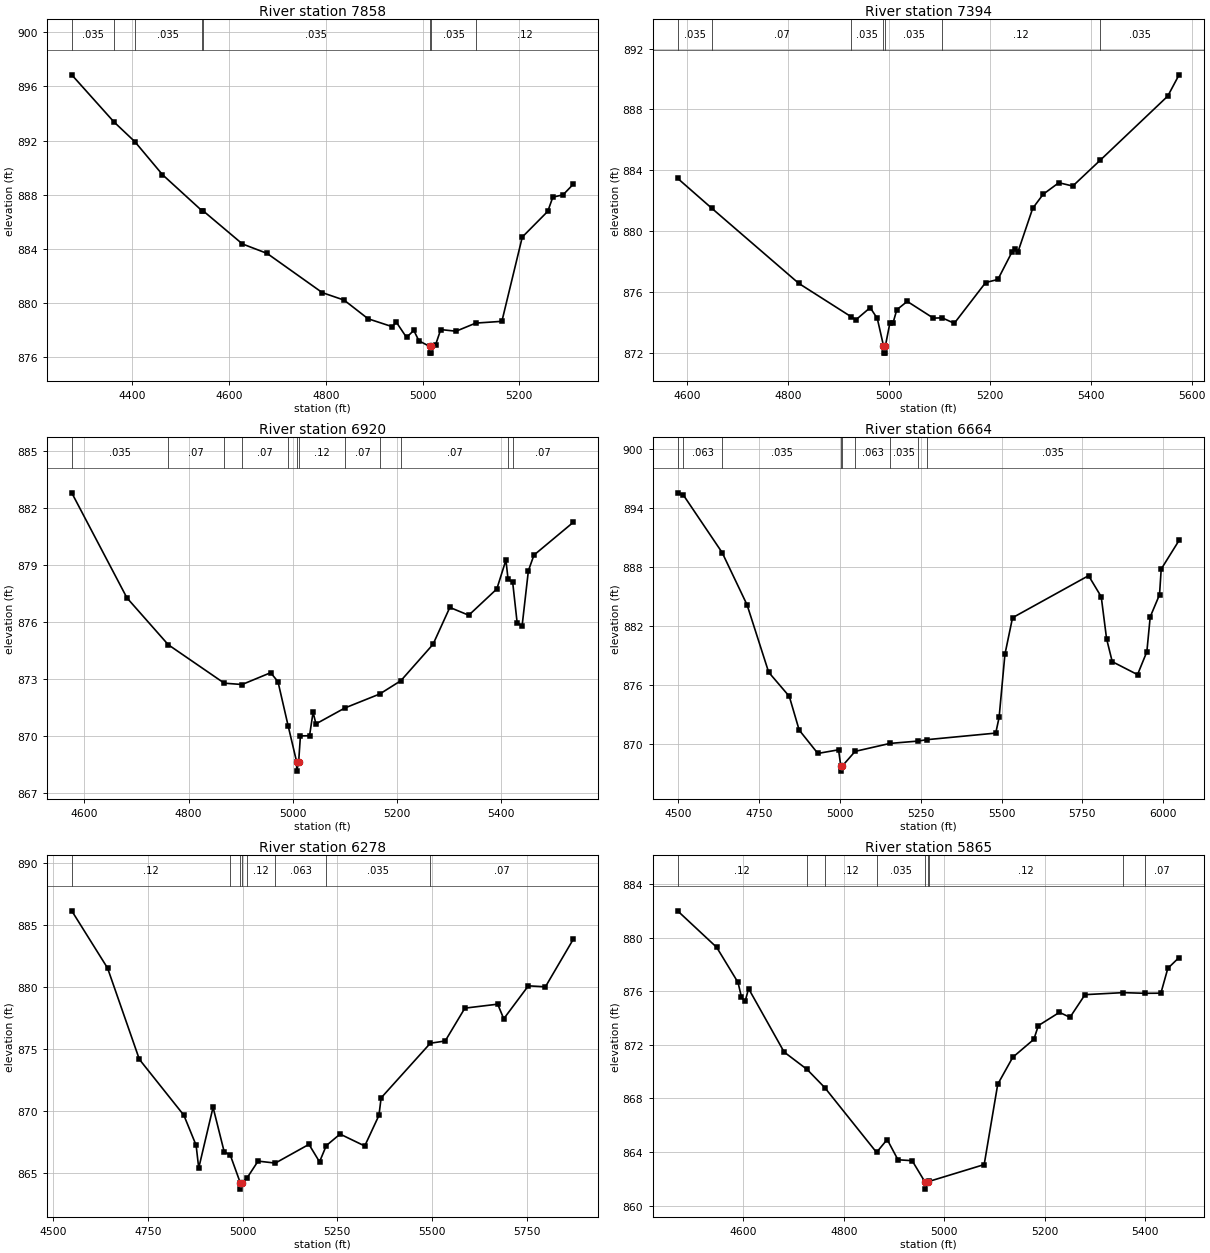
Type RM Length L Ch R = 1,7858,464,464,464
BEGIN DESCRIPTION:
Bear Creek Tributary 3 16.0
END DESCRIPTION:
XS GIS Cut Line= 3
      2188125.02     13786174.96      2188525.00     13785575.00
      2188625.00     13785274.99
#Sta/Elev= 30
  4274.4  896.86  4361.4  893.39  4404.9  891.92  4462.1  889.48  4543.3  886.83
  4545.4  886.83  4627.4  884.36  4678.5  883.66  4792.7  880.76  4837.7  880.21
  4887.3  878.83  4936.9  878.25  4945.9  878.57  4966.9  877.45  4981.9  877.97
  4992.5  877.20  5014.5  876.79  5014.8  876.29  5018.3  876.29  5018.5  876.79
  5027.1  876.92  5037.6  878.03  5069.3  877.91  5110.1  878.51  5164.1  878.64
  5206.3  884.87  5259.0  886.77  5269.5  887.82  5290.6  887.99  5311.7  888.77
#Mann=8,-1,0
  4274.4   0.035       0  4361.4    0.07       0  4404.9   0.035       0
  4543.3    0.07       0  4545.4   0.035       0  5014.5   0.035       0
  5018.5   0.035       0  5110.1    0.12       0
Bank Sta=5014.5,5018.5
Exp/Cntr=0.3,0.1

Type RM Length L Ch R = 1,7394,474,474,474
BEGIN DESCRIPTION:
Bear Creek Tributary 3 15.0
END DESCRIPTION:
XS GIS Cut Line= 3
      2188624.96     13786075.04      2188925.00     13785775.00
      2188775.00     13785225.00
#Sta/Elev= 30
  4580.7  883.47  4648.9  881.49  4821.2  876.56  4925.4  874.36  4934.3  874.17
  4962.6  874.97  4976.7  874.26  4988.9  872.48  4989.1  871.98  4992.6  871.98
  4992.9  872.48  5001.5  873.93  5007.6  873.93  5015.4  874.83  5036.1  875.38
  5087.9  874.28  5105.2  874.30  5129.4  873.94  5191.6  876.62  5215.8  876.82
  5243.4  878.60  5250.3  878.85  5255.5  878.62  5284.9  881.50  5305.6  882.42
  5336.7  883.18  5364.3  882.96  5419.1  884.67  5552.6  888.87  5575.1  890.27
#Mann=7,-1,0
  4580.7   0.035       0  4648.9    0.07       0  4925.4   0.035       0
  4988.9   0.035       0  4992.9   0.035       0  5105.2    0.12       0
  5419.1   0.035       0
Bank Sta=4988.9,4992.9
Exp/Cntr=0.3,0.1

Type RM Length L Ch R = 1,6920,256,256,256
BEGIN DESCRIPTION:
Bear Creek Tributary 3 14.0
END DESCRIPTION:
XS GIS Cut Line= 3
      2189025.03     13786274.97      2189325.00     13785975.00
      2189125.01     13785475.04
#Sta/Elev= 30
  4575.7  882.79  4681.7  877.27  4761.0  874.81  4868.5  872.79  4902.7  872.72
  4957.5  873.34  4971.6  872.87  4991.1  870.55  5007.3  868.67  5007.6  868.17
  5011.3  868.67  5014.7  870.02  5032.2  870.03  5039.0  871.27  5044.4  870.65
  5100.2  871.49  5166.8  872.22  5207.5  872.92  5269.2  874.83  5301.5  876.77
  5337.8  876.36  5391.7  877.74  5409.2  879.26  5413.3  878.24  5422.1  878.10
  5430.7  875.97  5440.2  875.79  5452.3  878.70  5463.0  879.52  5538.4  881.24
#Mann=12,-1,0
  4575.7   0.035       0  4761.0    0.07       0  4868.5   0.035       0
  4902.7    0.07       0  4991.1    0.12       0  5007.3    0.05       0
  5011.3    0.12       0  5100.2    0.07       0  5166.8    0.12       0
  5207.5    0.07       0  5413.3    0.12       0  5422.1    0.07       0
Bank Sta=5007.3,5011.3
Exp/Cntr=0.3,0.1

Type RM Length L Ch R = 1,6664,386,386,386
BEGIN DESCRIPTION:
Bear Creek Tributary 3 13.0
END DESCRIPTION:
XS GIS Cut Line= 3
      2189259.65     13786547.40      2189700.14     13785842.04
      2189895.66     13785149.10
#Sta/Elev= 30
  4497.5  895.51  4515.3  895.29  4635.4  889.43  4712.5  884.11  4779.4  877.25
  4843.1  874.80  4873.7  871.37  4931.5  868.99  4995.5  869.36  5002.6  867.69
  5002.9  867.19  5006.6  867.69  5046.8  869.20  5154.7  870.01  5242.2  870.25
  5268.6  870.39  5481.9  871.06  5492.3  872.66  5510.3  879.08  5533.8  882.80
  5769.1  887.08  5808.3  884.93  5824.8  880.66  5842.3  878.33  5920.6  877.01
  5949.4  879.34  5959.8  882.89  5988.6  885.14  5993.8  887.75  6049.1  890.67
#Mann=9,-1,0
  4497.5   0.035       0  4515.3   0.063       0  4635.4   0.035       0
  5002.6   0.035       0  5006.6   0.035       0  5046.8   0.063       0
  5154.7   0.035       0  5242.2   0.063       0  5268.6   0.035       0
Bank Sta=5002.6,5006.6
Exp/Cntr=0.3,0.1

Type RM Length L Ch R = 1,6278,413,413,413
BEGIN DESCRIPTION:
X18141
END DESCRIPTION:
XS GIS Cut Line= 3
      2189639.67     13786478.36      2189939.11     13785879.47
      2190260.62     13785311.09
#Sta/Elev= 30
  4549.5  886.11  4644.0  881.49  4727.8  874.13  4845.2  869.62  4877.5  867.20
  4884.4  865.36  4922.2  870.26  4951.5  866.68  4967.7  866.40  4994.1  864.16
  4994.4  863.66  4998.2  864.16  5012.2  864.58  5040.9  865.92  5086.4  865.76
  5175.1  867.27  5203.0  865.86  5220.8  867.17  5257.2  868.10  5322.2  867.14
  5359.7  869.61  5365.4  871.02  5495.2  875.43  5534.4  875.61  5586.3  878.26
  5672.9  878.58  5688.8  877.40  5753.7  880.06  5798.7  879.98  5872.1  883.81
#Mann=8,-1,0
  4549.5    0.12       0  4967.7    0.07       0  4994.1    0.05       0
  4998.2    0.07       0  5012.2    0.12       0  5086.4   0.063       0
  5220.8   0.035       0  5495.2    0.07       0
Bank Sta=4994.1,4998.2
Exp/Cntr=0.3,0.1

Type RM Length L Ch R = 1,5865,322,322,322
BEGIN DESCRIPTION:
Bear Creek Tributary 3 12.0
END DESCRIPTION:
XS GIS Cut Line= 3
      2189825.03     13786474.97      2190224.15     13786095.41
      2190474.98     13785725.03
#Sta/Elev= 30
  4469.2  881.99  4547.0  879.27  4589.5  876.65  4596.4  875.55  4603.6  875.23
  4610.5  876.19  4681.3  871.46  4726.8  870.17  4762.1  868.81  4865.2  863.98
  4886.4  864.94  4907.8  863.43  4936.1  863.36  4962.1  861.74  4962.5  861.24
  4966.7  861.74  4970.0  861.82  5079.4  863.07  5106.4  869.06  5136.3  871.07
  5178.3  872.41  5187.2  873.43  5229.2  874.42  5250.2  874.05  5280.1  875.74
  5355.7  875.89  5399.0  875.84  5431.1  875.85  5444.9  877.70  5467.3  878.51
#Mann=9,-1,0
  4469.2    0.12       0  4726.8     0.1       0  4762.1    0.12       0
  4865.2   0.035       0  4962.1    0.05       0  4966.7   0.035       0
  4970.0    0.12       0  5355.7   0.035       0  5399.0    0.07       0
Bank Sta=4962.1,4966.7
Exp/Cntr=0.3,0.1

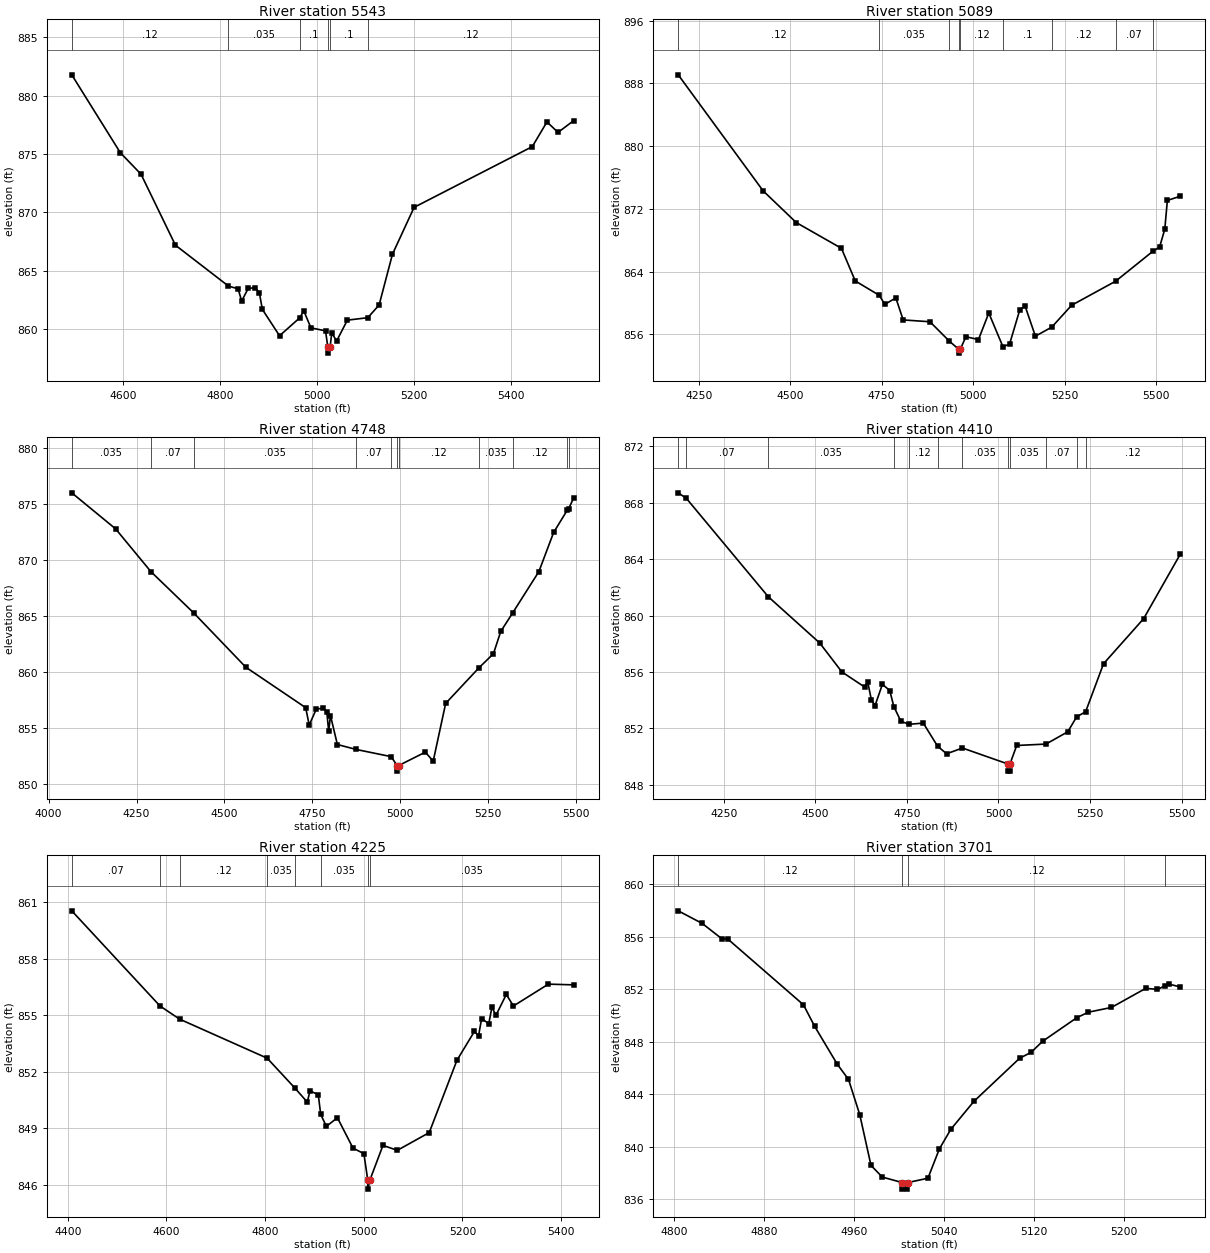
Type RM Length L Ch R = 1,5543,454,454,454
BEGIN DESCRIPTION:
Bear Creek Tributary 3 11.0
END DESCRIPTION:
XS GIS Cut Line= 3
      2190024.98     13786625.01      2190425.00     13786325.00
      2190681.94     13785856.45
#Sta/Elev= 30
  4494.3  881.79  4594.3  875.11  4637.0  873.26  4707.9  867.17  4817.2  863.66
  4837.0  863.43  4844.3  862.38  4857.9  863.47  4872.4  863.52  4880.8  863.08
  4887.0  861.66  4922.4  859.40  4963.7  860.93  4972.4  861.53  4987.0  860.08
  5017.1  859.82  5021.9  858.41  5022.2  857.91  5026.5  858.41  5029.9  859.65
  5039.9  858.95  5062.1  860.74  5104.2  860.95  5127.5  862.04  5155.0  866.40
  5199.6  870.42  5443.1  875.63  5473.3  877.75  5496.1  876.85  5528.7  877.87
#Mann=6,-1,0
  4494.3    0.12       0  4817.2   0.035       0  4963.7     0.1       0
  5021.9    0.05       0  5026.5     0.1       0  5104.2    0.12       0
Bank Sta=5021.9,5026.5
Exp/Cntr=0.3,0.1

Type RM Length L Ch R = 1,5089,341,341,341
BEGIN DESCRIPTION:
Bear Creek Tributary 3 10.0
END DESCRIPTION:
XS GIS Cut Line= 3
      2189925.01     13786675.00      2190725.00     13786575.00
      2191125.00     13786175.00
#Sta/Elev= 30
  4194.1  889.09  4425.9  874.31  4516.6  870.26  4640.0  866.98  4677.8  862.82
  4743.3  860.99  4758.5  859.84  4788.7  860.65  4808.8  857.85  4881.9  857.62
  4934.6  855.16  4960.2  854.12  4960.5  853.62  4964.8  854.12  4980.2  855.71
  5014.5  855.35  5042.7  858.73  5081.2  854.45  5099.3  854.75  5127.6  859.17
  5141.7  859.64  5170.0  855.78  5214.9  856.94  5269.0  859.72  5389.4  862.79
  5490.7  866.59  5509.4  867.14  5523.6  869.42  5530.6  873.08  5566.0  873.62
#Mann=9,-1,0
  4194.1    0.12       0  4743.3   0.035       0  4934.6    0.12       0
  4960.2    0.05       0  4964.8    0.12       0  5081.2     0.1       0
  5214.9    0.12       0  5389.4    0.07       0  5490.7    0.12       0
Bank Sta=4960.2,4964.8
Exp/Cntr=0.3,0.1

Type RM Length L Ch R = 1,4748,338,338,338
BEGIN DESCRIPTION:
Bear Creek Tributary 3 9.0
END DESCRIPTION:
XS GIS Cut Line= 3
      2190000.39     13786802.21      2190902.06     13786836.51
      2191325.00     13786525.00
#Sta/Elev= 30
  4065.8  875.97  4190.5  872.76  4290.9  868.95  4413.7  865.24  4560.8  860.44
  4730.9  856.84  4740.9  855.29  4760.9  856.70  4780.9  856.81  4790.9  856.46
  4796.4  854.74  4801.4  856.14  4821.0  853.56  4874.3  853.12  4974.0  852.48
  4990.8  851.69  4991.2  851.19  4995.5  851.69  5071.1  852.88  5093.5  852.08
  5128.9  857.22  5224.2  860.41  5264.7  861.64  5285.6  863.63  5319.5  865.28
  5394.0  868.96  5435.9  872.44  5474.4  874.41  5478.9  874.57  5493.4  875.55
#Mann=11,-1,0
  4065.8   0.035       0  4290.9    0.07       0  4413.7   0.035       0
  4874.3    0.07       0  4974.0    0.12       0  4990.8    0.05       0
  4995.5    0.12       0  5224.2   0.035       0  5319.5    0.12       0
  5474.4   0.035       0  5478.9    0.12       0
Bank Sta=4990.8,4995.5
Exp/Cntr=0.3,0.1

Type RM Length L Ch R = 1,4410,185,185,185
BEGIN DESCRIPTION:
Bear Creek Tributary 3 8.5
END DESCRIPTION:
XS GIS Cut Line= 4
      2190220.84     13786846.30      2190862.85     13786914.92
      2191098.53     13787195.92      2191440.57     13787301.89
#Sta/Elev= 30
  4125.9  868.71  4148.0  868.32  4371.5  861.34  4512.2  858.05  4572.6  856.00
  4634.6  854.93  4643.0  855.30  4653.0  854.03  4663.1  853.61  4683.2  855.12
  4703.3  854.68  4714.4  853.54  4733.5  852.51  4755.3  852.28  4794.8  852.37
  4833.8  850.73  4858.5  850.19  4901.7  850.60  5026.6  849.46  5026.9  848.96
  5030.9  848.96  5031.3  849.46  5049.8  850.78  5129.7  850.88  5189.1  851.75
  5213.7  852.82  5237.9  853.17  5286.8  856.58  5396.3  859.78  5496.4  864.36
#Mann=12,-1,0
  4125.9   0.035       0  4148.0    0.07       0  4371.5   0.035       0
  4714.4    0.07       0  4755.3    0.12       0  4833.8    0.07       0
  4901.7   0.035       0  5026.6   0.035       0  5031.3   0.035       0
  5129.7    0.07       0  5213.7   0.035       0  5237.9    0.12       0
Bank Sta=5026.6,5031.3
Exp/Cntr=0.3,0.1

Type RM Length L Ch R = 1,4225,524,524,524
BEGIN DESCRIPTION:
Bear Creek Tributary 3 8.0
END DESCRIPTION:
XS GIS Cut Line= 4
      2190443.87     13787005.58      2190955.96     13787262.85
      2191004.97     13787262.85      2191242.67     13787578.97
#Sta/Elev= 30
  4408.2  860.54  4587.0  855.49  4626.9  854.79  4804.2  852.72  4860.2  851.14
  4885.5  850.39  4891.0  850.98  4907.8  850.79  4912.7  849.74  4924.2  849.10
  4946.6  849.56  4978.1  847.95  5000.3  847.65  5008.0  846.27  5008.3  845.77
  5012.7  846.27  5038.9  848.09  5068.1  847.83  5132.7  848.77  5188.9  852.61
  5224.3  854.14  5232.6  853.90  5238.9  854.82  5253.4  854.55  5259.7  855.42
  5268.0  855.00  5288.9  856.10  5303.4  855.49  5374.2  856.65  5425.8  856.61
#Mann=8,-1,0
  4408.2    0.07       0  4587.0   0.035       0  4626.9    0.12       0
  4804.2   0.035       0  4860.2    0.12       0  4912.7   0.035       0
  5008.0   0.035       0  5012.7   0.035       0
Bank Sta=5008,5012.7
Exp/Cntr=0.3,0.1

Type RM Length L Ch R = 1,3701,468,468,468
BEGIN DESCRIPTION:
Bear Creek Tributary 3 7.0
END DESCRIPTION:
XS GIS Cut Line= 4
      2190683.73     13787725.00      2190725.00     13787725.00
      2190875.00     13787725.00      2191124.98     13787675.00
#Sta/Elev= 30
  4803.6  857.99  4824.9  857.03  4842.4  855.86  4847.4  855.86  4914.9  850.83
  4924.9  849.18  4944.9  846.31  4954.9  845.15  4964.9  842.47  4974.9  838.60
  4984.9  837.71  5002.6  837.29  5002.9  836.79  5007.2  836.79  5007.6  837.29
  5025.5  837.62  5035.7  839.86  5045.9  841.35  5066.3  843.47  5107.0  846.76
  5117.2  847.21  5127.4  848.05  5158.0  849.86  5168.2  850.27  5188.6  850.63
  5219.2  852.09  5229.4  852.00  5236.3  852.28  5239.6  852.41  5249.8  852.19
#Mann=4,-1,0
  4803.6    0.12       0  5002.6    0.05       0  5007.6    0.12       0
  5236.3   0.035       0
Bank Sta=5002.6,5007.6
Exp/Cntr=0.3,0.1

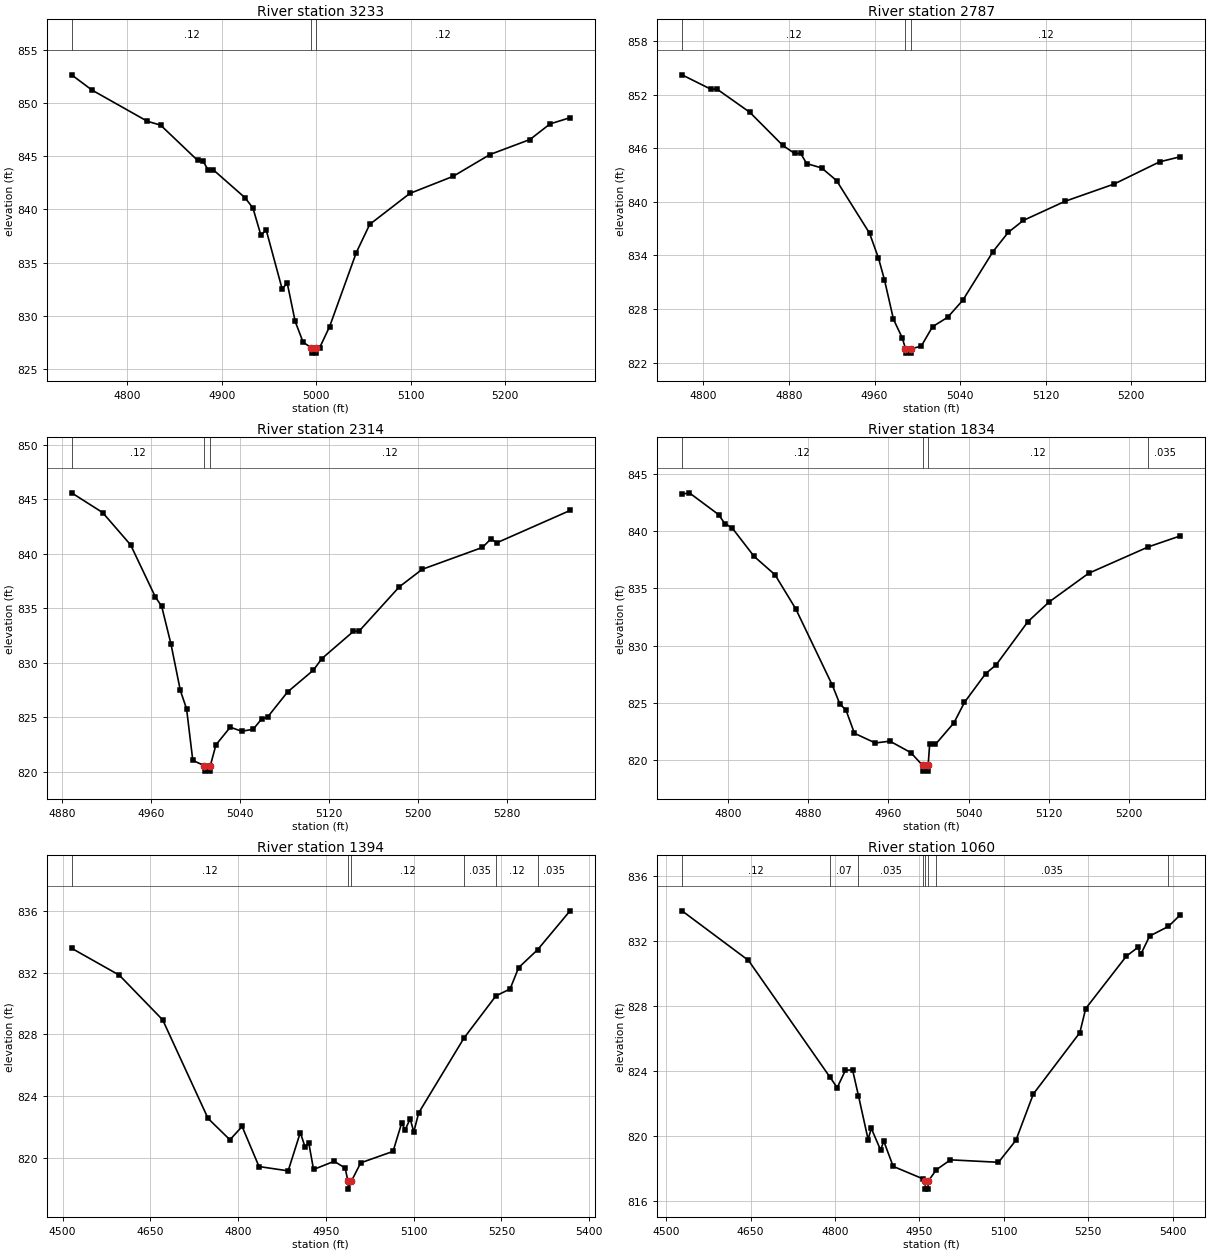
Type RM Length L Ch R = 1,3233,446,446,446
BEGIN DESCRIPTION:
Bear Creek Tributary 3 6.0
END DESCRIPTION:
XS GIS Cut Line= 5
      2190693.16     13788059.08      2190825.00     13788125.00
      2190925.00     13788175.00      2191025.00     13788075.00
      2191115.07     13787984.93
#Sta/Elev= 30
  4740.8  852.63  4762.4  851.20  4821.1  848.27  4835.1  847.91  4874.2  844.61
  4879.8  844.57  4885.4  843.71  4891.0  843.71  4924.5  841.10  4932.9  840.13
  4941.3  837.59  4946.9  838.08  4963.7  832.58  4969.3  833.06  4977.6  829.50
  4986.0  827.55  4994.7  827.02  4995.1  826.52  4999.4  826.52  4999.7  827.02
  5003.5  827.02  5014.1  829.01  5042.4  835.96  5056.6  838.60  5099.0  841.50
  5145.0  843.11  5183.9  845.15  5226.3  846.56  5247.5  848.02  5268.8  848.61
#Mann=3,-1,0
  4740.8    0.12       0  4994.7    0.05       0  4999.7    0.12       0
Bank Sta=4994.7,4999.7
Exp/Cntr=0.3,0.1

Type RM Length L Ch R = 1,2787,473,473,473
BEGIN DESCRIPTION:
Bear Creek Tributary 3 5.0
END DESCRIPTION:
XS GIS Cut Line= 5
      2190978.30     13788623.35      2191075.00     13788575.00
      2191175.00     13788525.00      2191275.00     13788425.00
      2191348.87     13788351.13
#Sta/Elev= 30
  4780.1  854.22  4807.2  852.60  4812.7  852.63  4843.5  850.02  4874.2  846.32
  4885.4  845.41  4891.0  845.41  4896.6  844.28  4910.6  843.79  4924.5  842.38
  4955.3  836.49  4963.7  833.69  4969.3  831.25  4977.7  826.84  4986.0  824.73
  4988.9  823.55  4989.3  823.05  4993.9  823.05  4994.3  823.55  5003.6  823.82
  5014.2  826.01  5028.3  827.06  5042.4  828.96  5070.7  834.42  5084.9  836.57
  5099.0  837.91  5137.9  840.05  5183.9  841.99  5226.3  844.47  5245.9  845.05
#Mann=3,-1,0
  4780.1    0.12       0  4988.9    0.05       0  4994.3    0.12       0
Bank Sta=4988.9,4994.3
Exp/Cntr=0.3,0.1

Type RM Length L Ch R = 1,2314,480,480,480
BEGIN DESCRIPTION:
Bear Creek Tributary 3 4.0
END DESCRIPTION:
XS GIS Cut Line= 4
      2191475.02     13788924.96      2191525.00     13788825.00
      2191575.00     13788625.00      2191606.62     13788498.51
#Sta/Elev= 30
  4888.3  845.59  4916.2  843.78  4941.4  840.81  4963.7  836.02  4969.3  835.18
  4977.7  831.70  4986.1  827.45  4991.7  825.77  4997.3  821.04  5007.6  820.55
  5008.1  820.05  5012.7  820.05  5013.1  820.55  5018.1  822.46  5031.0  824.08
  5041.3  823.71  5051.6  823.89  5059.3  824.85  5064.5  825.00  5082.5  827.31
  5105.7  829.31  5113.4  830.38  5141.8  832.88  5146.9  832.90  5183.0  836.96
  5203.6  838.57  5257.8  840.58  5265.5  841.37  5270.6  841.00  5336.6  843.97
#Mann=3,-1,0
  4888.3    0.12       0  5007.6    0.05       0  5013.1    0.12       0
Bank Sta=5007.6,5013.1
Exp/Cntr=0.3,0.1

Type RM Length L Ch R = 1,1834,440,440,440
BEGIN DESCRIPTION:
Bear Creek Tributary 3 3.0
END DESCRIPTION:
XS GIS Cut Line= 4
      2191825.01     13789124.99      2191975.00     13788925.00
      2192025.00     13788775.00      2192053.11     13788690.66
#Sta/Elev= 30
  4754.3  843.23  4761.6  843.35  4790.7  841.45  4797.0  840.66  4804.3  840.28
  4826.2  837.79  4847.0  836.19  4867.8  833.19  4904.3  826.51  4911.6  824.90
  4917.8  824.35  4926.2  822.33  4947.0  821.48  4961.6  821.64  4982.4  820.64
  4994.2  819.52  4994.6  819.02  4999.3  819.02  4999.7  819.52  5001.2  821.35
  5006.9  821.35  5025.4  823.24  5035.9  825.03  5057.0  827.54  5067.5  828.31
  5099.2  832.09  5120.2  833.80  5159.8  836.32  5219.4  838.63  5251.3  839.59
#Mann=4,-1,0
  4754.3    0.12       0  4994.2    0.05       0  4999.7    0.12       0
  5219.4   0.035       0
Bank Sta=4994.2,4999.7
Exp/Cntr=0.3,0.1

Type RM Length L Ch R = 1,1394,334,334,334
BEGIN DESCRIPTION:
Bear Creek Tributary 3 2.0
END DESCRIPTION:
XS GIS Cut Line= 5
      2192402.86     13789488.87      2192503.00     13789275.55
      2192360.41     13789092.70      2192360.01     13789062.21
      2192147.76     13788779.04
#Sta/Elev= 30
  4515.5  833.57  4597.1  831.83  4671.2  828.94  4748.7  822.57  4786.1  821.19
  4806.9  822.05  4835.8  819.46  4885.6  819.18  4906.4  821.66  4914.5  820.72
  4920.8  821.00  4929.0  819.27  4964.3  819.80  4983.0  819.36  4987.9  818.50
  4988.4  818.00  4993.5  818.50  5009.6  819.70  5064.9  820.44  5079.5  822.26
  5085.7  821.84  5094.1  822.55  5100.3  821.70  5108.7  822.93  5186.0  827.76
  5240.6  830.49  5264.9  830.94  5279.5  832.32  5311.8  833.47  5367.4  835.99
#Mann=6,-1,0
  4515.5    0.12       0  4987.9    0.05       0  4993.5    0.12       0
  5186.0   0.035       0  5240.6    0.12       0  5311.8   0.035       0
Bank Sta=4987.9,4993.5
Exp/Cntr=0.3,0.1

Type RM Length L Ch R = 1,1060,332,332,332
BEGIN DESCRIPTION:
Bear Creek Tributary 3 1.0
END DESCRIPTION:
XS GIS Cut Line= 4
      2192395.21     13789541.14      2192653.20     13789341.94
      2192583.54     13789204.80      2192482.32     13788811.88
#Sta/Elev= 30
  4528.2  833.86  4646.3  830.81  4790.3  823.67  4803.9  822.99  4818.4  824.05
  4831.1  824.09  4841.6  822.50  4858.8  819.80  4864.4  820.49  4881.0  819.15
  4886.6  819.70  4903.3  818.15  4957.0  817.37  4960.1  817.25  4960.5  816.75
  4965.2  816.75  4965.7  817.25  4980.0  817.94  5005.0  818.55  5090.4  818.40
  5121.3  819.75  5152.3  822.60  5234.9  826.37  5245.3  827.85  5317.5  831.07
  5337.9  831.61  5343.1  831.18  5358.9  832.31  5392.2  832.90  5413.7  833.62
#Mann=8,-1,0
  4528.2    0.12       0  4790.3    0.07       0  4841.6   0.035       0
  4957.0    0.07       0  4960.1   0.035       0  4965.7    0.07       0
  4980.0   0.035       0  5392.2    0.12       0
Bank Sta=4960.1,4965.7
Exp/Cntr=0.3,0.1

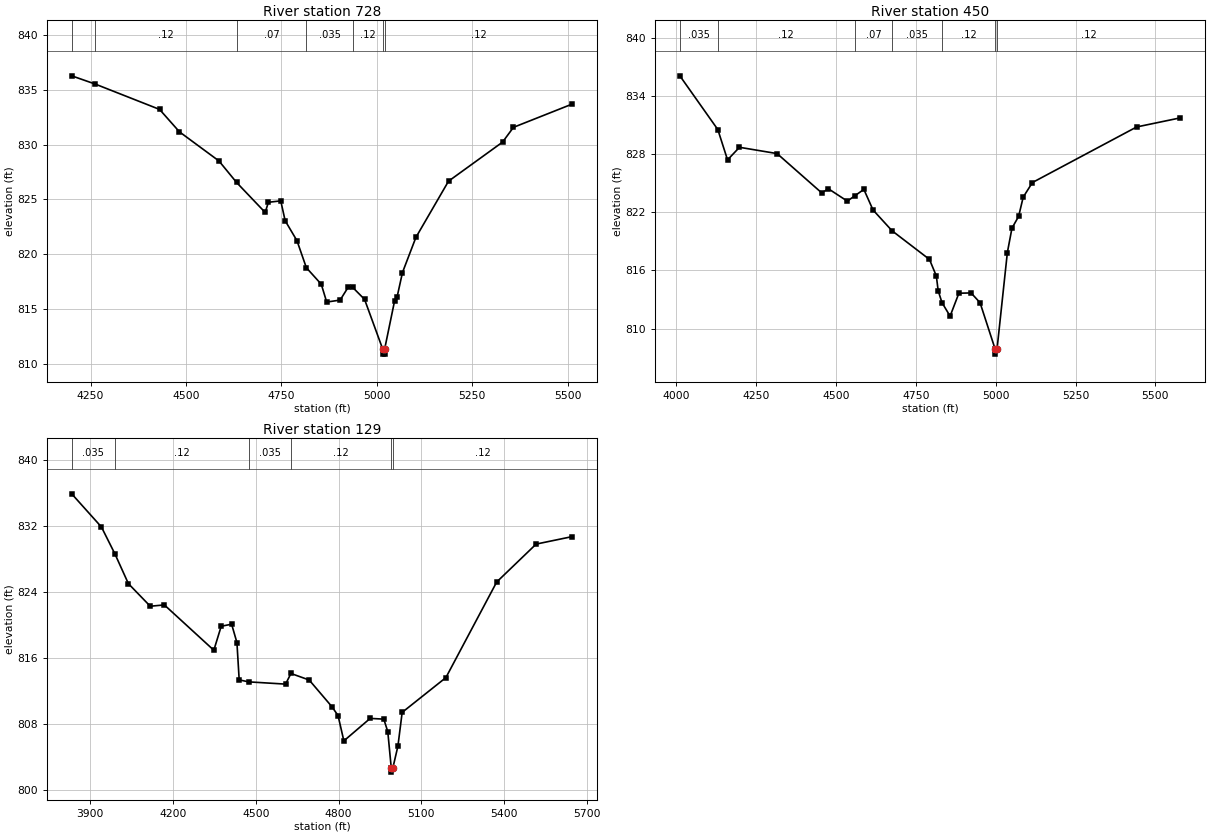
Type RM Length L Ch R = 1,728,278,278,278
BEGIN DESCRIPTION:
X18140
END DESCRIPTION:
XS GIS Cut Line= 3
      2192205.02     13789677.14      2192729.05     13789441.03
      2193209.89     13788882.45
#Sta/Elev= 30
  4200.5  836.30  4261.9  835.55  4430.8  833.23  4482.9  831.18  4586.4  828.52
  4632.7  826.55  4707.6  823.81  4716.0  824.74  4748.4  824.87  4759.9  823.06
  4790.9  821.23  4815.5  818.76  4854.6  817.25  4868.8  815.62  4904.0  815.80
  4925.9  817.02  4936.6  816.97  4968.0  815.87  5015.2  811.36  5015.7  810.86
  5020.4  810.86  5020.9  811.36  5046.6  815.70  5053.2  816.07  5067.4  818.32
  5102.6  821.53  5188.1  826.67  5329.7  830.24  5358.2  831.59  5512.3  833.72
#Mann=7,-1,0
  4200.5   0.035       0  4261.9    0.12       0  4632.7    0.07       0
  4815.5   0.035       0  4936.6    0.12       0  5015.2    0.05       0
  5020.9    0.12       0
Bank Sta=5015.2,5020.9
Exp/Cntr=0.3,0.1

Type RM Length L Ch R = 1,450,321,321,321
BEGIN DESCRIPTION:
X18139
END DESCRIPTION:
XS GIS Cut Line= 3
      2192285.68     13789901.69      2193045.76     13789464.07
      2193477.65     13788925.65
#Sta/Elev= 30
  4011.1  836.10  4130.0  830.55  4160.4  827.42  4197.8  828.72  4315.6  828.07
  4455.0  824.02  4476.5  824.43  4535.5  823.16  4558.9  823.71  4587.3  824.37
  4615.9  822.25  4675.5  820.10  4792.7  817.14  4814.2  815.43  4820.0  813.90
  4831.9  812.68  4857.3  811.28  4884.8  813.65  4923.0  813.68  4951.1  812.67
  4998.5  807.86  4999.0  807.36  5004.2  807.86  5036.6  817.85  5051.0  820.37
  5071.8  821.58  5086.2  823.57  5115.0  825.08  5441.5  830.82  5578.4  831.76
#Mann=7,-1,0
  4011.1   0.035       0  4130.0    0.12       0  4558.9    0.07       0
  4675.5   0.035       0  4831.9    0.12       0  4998.5    0.05       0
  5004.2    0.12       0
Bank Sta=4998.5,5004.2
Exp/Cntr=0.3,0.1

Type RM Length L Ch R = 1,129,0,0,0
BEGIN DESCRIPTION:
X18138
END DESCRIPTION:
XS GIS Cut Line= 4
      2192323.06     13789950.66      2193316.41     13789642.58
      2193546.74     13789268.28      2193564.02     13788934.34
#Sta/Elev= 30
  3833.0  835.90  3940.7  831.88  3989.8  828.60  4038.5  825.00  4117.7  822.26
  4168.8  822.42  4348.1  816.92  4374.8  819.83  4412.6  820.08  4431.8  817.85
  4440.0  813.32  4475.3  813.08  4608.1  812.81  4627.6  814.10  4693.6  813.31
  4776.3  810.06  4798.3  808.99  4819.3  805.92  4914.7  808.65  4964.1  808.56
  4978.5  807.04  4991.1  802.63  4991.5  802.13  4996.8  802.63  5015.2  805.28
  5030.6  809.38  5189.1  813.60  5373.2  825.20  5516.1  829.80  5646.9  830.71
#Mann=6,-1,0
  3833.0   0.035       0  3989.8    0.12       0  4475.3   0.035       0
  4627.6    0.12       0  4991.1    0.05       0  4996.8    0.12       0
Bank Sta=4991.1,4996.8
Exp/Cntr=0.3,0.1

Chan Stop Cuts=-1