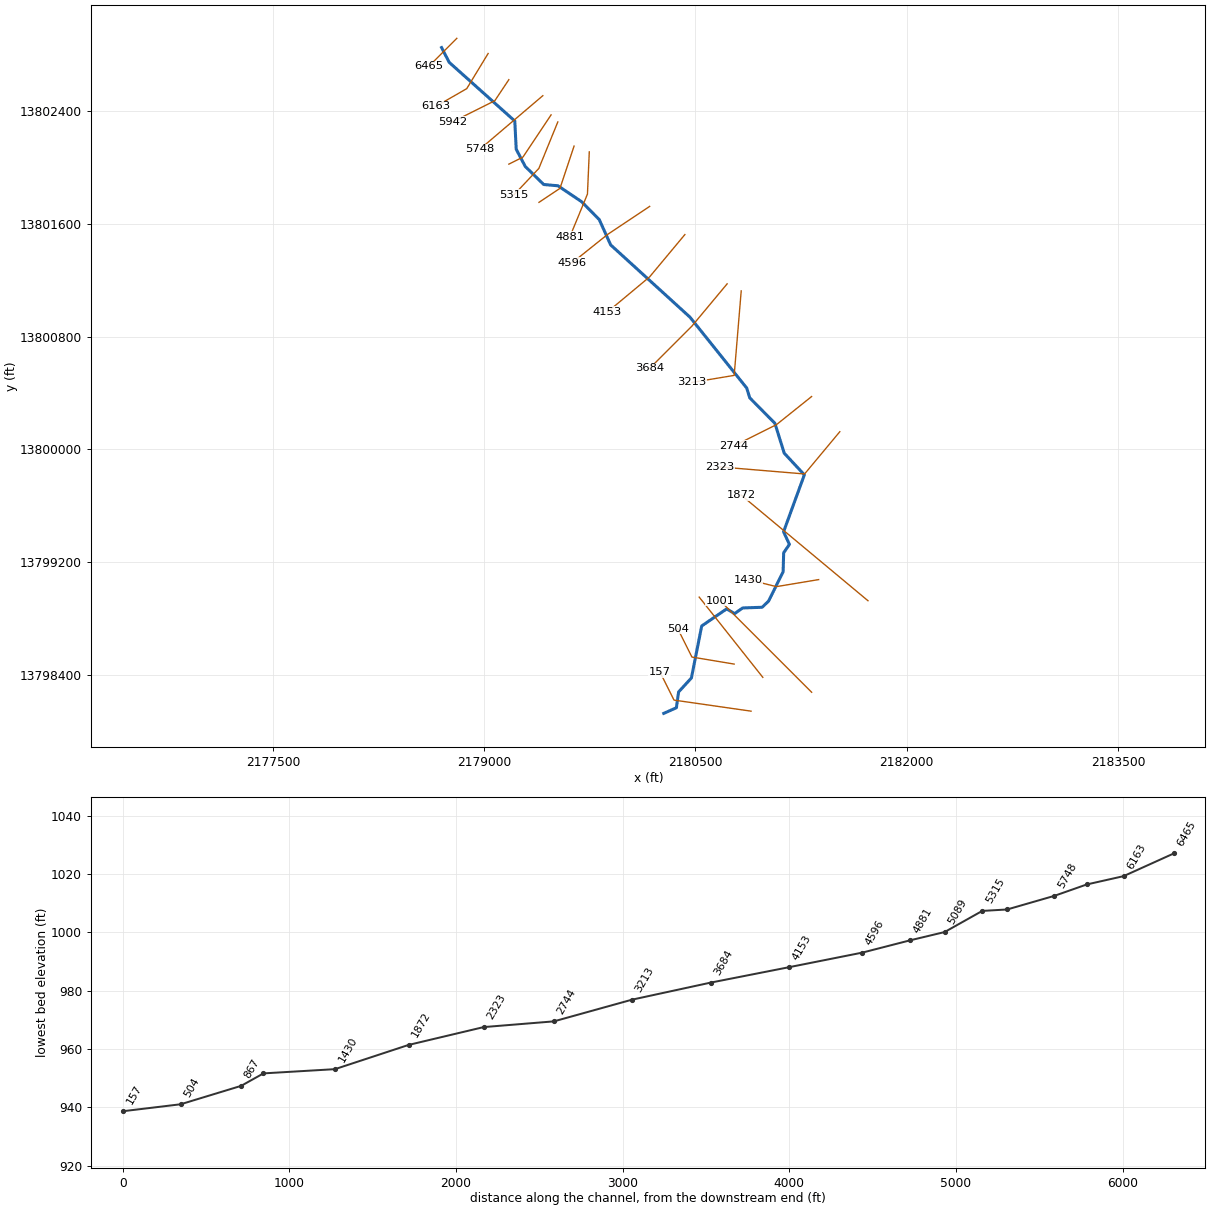
--- Bear Creek Tributary 5.prj (project) ---

Proj Title=Bear Creek Tributary 5 Base Level Engineering
Current Plan=p01
Default Exp/Contr=0.3,0.1
English Units
Geom File=g01
Flow File=f01
Plan File=p01
BEGIN DESCRIPTION:
Bear Creek Tributary 5
END DESCRIPTION:

--- Bear Creek Tributary 5.p01 (plan) ---

Plan Title=Multiple Run
Short Identifier=Multiple
Geom File=g01
Flow File=f01
Subcritical Flow
K Sum by GR= 0
Std Step Tol= 0.01
Critical Tol= 0.01
Num of Std Step Trials= 20
Max Error Tol= 0.3
Flow Tol Ratio= 0.001
Split Flow NTrial= 30
Split Flow Tol= 0.02
Split Flow Ratio= 0.02
Log Output Level= 0
Friction Slope Method= 1
Unsteady Friction Slope Method= 2
Unsteady Bridges Friction Slope Method= 1
Parabolic Critical Depth
Global Vel Dist=  1 , 1 , 1
Global Log Level= 0
CheckData=True
Encroach Param= -1, 0, 0, 0
BEGIN DESCRIPTION:
Multiple Run
END DESCRIPTION:

--- Bear Creek Tributary 5.f01 (steady flow) ---

Flow Title=Multiple
Number of Profiles=7
Profile Names=10-year,25-year,50-year,1pct_min,100-year,1pct_plu,500-year
River Rch & RM= Bear Creek Tribu,Reach-1,6465
     451     726     976     638    1273    2539    2136
River Rch & RM= Bear Creek Tribu,Reach-1,4596
     901    1509    2080    1389    2771    5529    4868
Boundary for River Rch & Prof#=Bear Creek Tribu,Reach-1,1
Up Type=0
Dn Type=3
Dn Slope=0.005
Boundary for River Rch & Prof#=Bear Creek Tribu,Reach-1,2
Up Type=0
Dn Type=3
Dn Slope=0.005
Boundary for River Rch & Prof#=Bear Creek Tribu,Reach-1,3
Up Type=0
Dn Type=3
Dn Slope=0.005
Boundary for River Rch & Prof#=Bear Creek Tribu,Reach-1,4
Up Type=0
Dn Type=3
Dn Slope=0.005
Boundary for River Rch & Prof#=Bear Creek Tribu,Reach-1,5
Up Type=0
Dn Type=3
Dn Slope=0.005
Boundary for River Rch & Prof#=Bear Creek Tribu,Reach-1,6
Up Type=0
Dn Type=3
Dn Slope=0.005
Boundary for River Rch & Prof#=Bear Creek Tribu,Reach-1,7
Up Type=0
Dn Type=3
Dn Slope=0.005

--- Bear Creek Tributary 5.g01 (geometry) ---

Geom Title=Existing Conditions

River Reach=Bear Creek Tribu,Reach-1
Reach XY= 30
      2178697.37     13802852.63      2178751.27     13802748.17
      2179217.19     13802331.19      2179227.24     13802130.93
      2179291.64     13802008.32      2179422.57     13801880.52
      2179523.50     13801871.37      2179691.71     13801758.43
      2179817.09     13801631.15      2179898.01     13801451.53
      2180461.37     13800938.21      2180864.22     13800434.68
      2180885.78     13800365.32      2181064.24     13800184.68
      2181130.52     13799972.57      2181273.39     13799818.96
      2181125.82     13799414.29      2181167.41     13799325.01
      2181126.56     13799265.40      2181122.64     13799130.52
      2181019.29     13798922.42      2180973.75     13798878.45
      2180835.44     13798873.61      2180778.21     13798833.29
      2180721.67     13798866.99      2180544.45     13798745.55
      2180471.44     13798376.47      2180380.54     13798277.42
      2180364.74     13798164.90      2180275.00     13798125.00

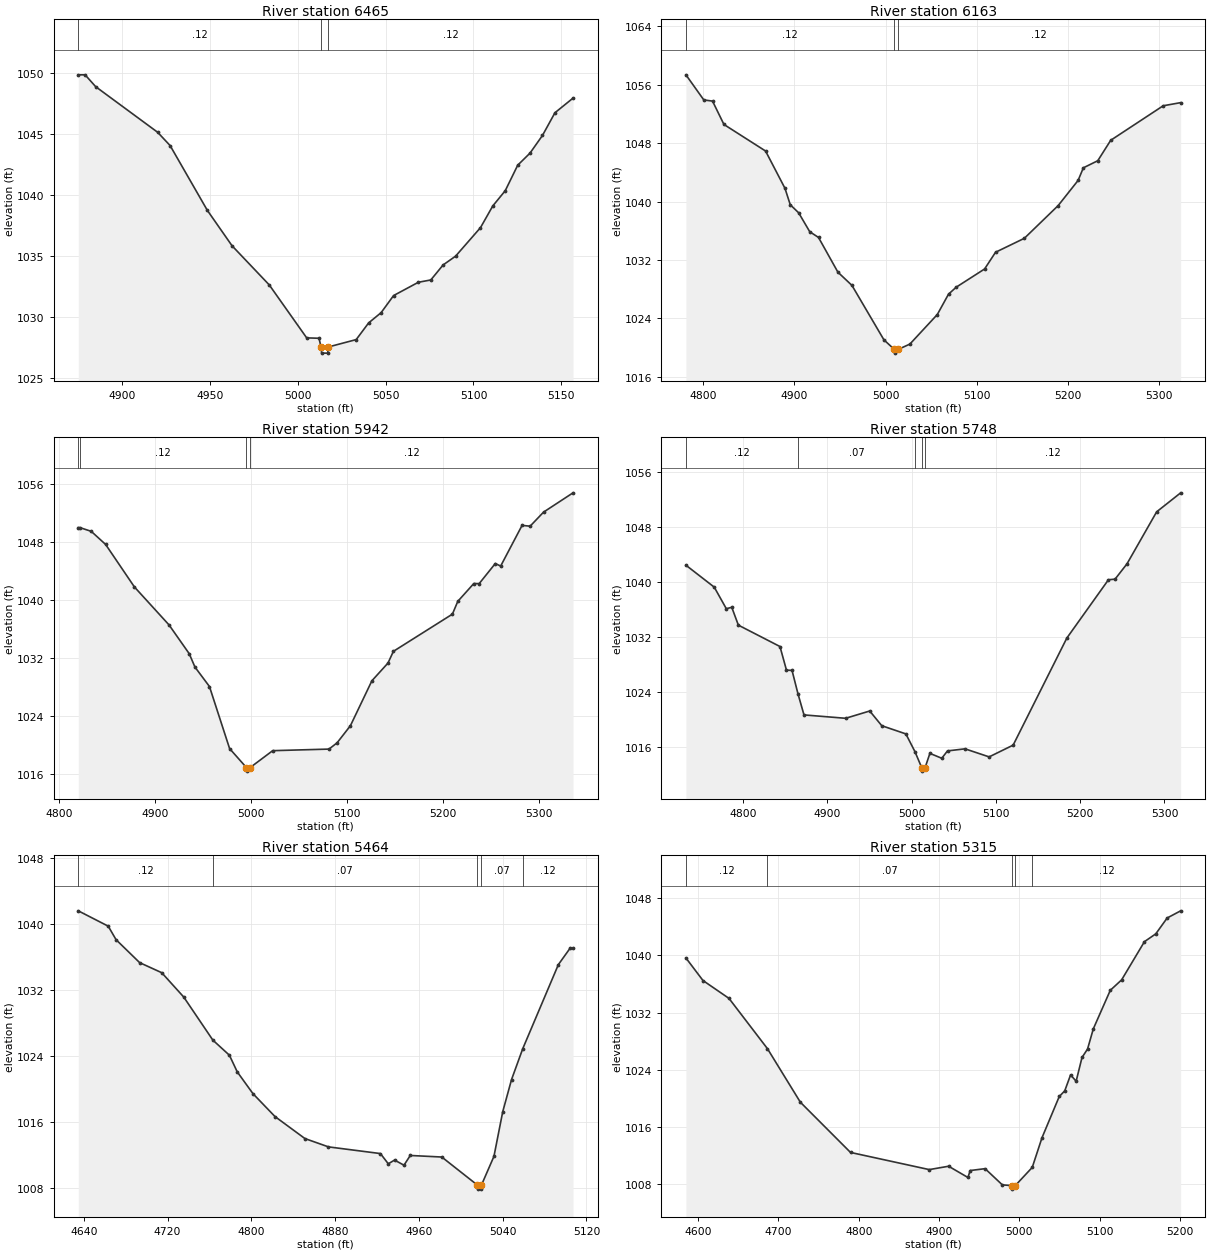
Type RM Length L Ch R = 1,6465,302,302,302
BEGIN DESCRIPTION:
Bear Creek Tributary 5 14.0
END DESCRIPTION:
XS GIS Cut Line= 3
      2178805.50     13802918.43      2178705.47     13802818.40
      2178606.24     13802719.17
#Sta/Elev= 30
  4874.9 1049.86  4878.8 1049.86  4884.8 1048.89  4920.1 1045.15  4927.2 1044.06
  4948.4 1038.75  4962.5 1035.84  4983.7 1032.63  5005.0 1028.29  5012.0 1028.26
  5013.2 1027.54  5013.5 1027.04  5017.0 1027.04  5017.2 1027.54  5033.2 1028.15
  5040.3 1029.52  5047.4 1030.36  5054.5 1031.76  5068.6 1032.85  5075.7 1033.04
  5082.7 1034.27  5089.8 1034.99  5104.0 1037.33  5111.0 1039.11  5118.1 1040.36
  5125.2 1042.45  5132.2 1043.44  5139.3 1044.89  5146.4 1046.75  5156.7 1047.95
#Mann=3,-1,0
  4874.9    0.12       0  5013.2    0.05       0  5017.2    0.12       0
Bank Sta=5013.2,5017.2
Exp/Cntr=0.3,0.1

Type RM Length L Ch R = 1,6163,221,221,221
BEGIN DESCRIPTION:
X18145
END DESCRIPTION:
XS GIS Cut Line= 3
      2179027.83     13802810.66      2178875.94     13802561.13
      2178658.38     13802436.19
#Sta/Elev= 30
  4780.9 1057.37  4800.5 1053.93  4810.1 1053.77  4822.6 1050.57  4868.3 1046.93
  4889.6 1041.82  4895.4 1039.57  4904.6 1038.47  4916.8 1035.87  4926.4 1035.09
  4947.7 1030.33  4963.1 1028.52  4998.2 1021.06  5009.7 1019.74  5009.9 1019.24
  5013.7 1019.74  5026.7 1020.48  5056.8 1024.53  5069.1 1027.32  5077.6 1028.28
  5108.7 1030.77  5120.7 1033.06  5152.3 1034.97  5189.4 1039.45  5211.3 1042.90
  5217.1 1044.63  5232.9 1045.60  5247.1 1048.40  5304.7 1053.13  5323.9 1053.56
#Mann=3,-1,0
  4780.9    0.12       0  5009.7    0.05       0  5013.7    0.12       0
Bank Sta=5009.7,5013.7
Exp/Cntr=0.3,0.1

Type RM Length L Ch R = 1,5942,194,194,194
BEGIN DESCRIPTION:
Bear Creek Tributary 5 13.0
END DESCRIPTION:
XS GIS Cut Line= 3
      2179174.97     13802624.96      2179075.00     13802475.00
      2178775.04     13802325.02
#Sta/Elev= 30
  4819.8 1049.97  4821.6 1049.97  4833.3 1049.46  4848.3 1047.65  4878.3 1041.79
  4914.4 1036.55  4935.4 1032.59  4941.4 1030.74  4956.5 1028.06  4977.5 1019.50
  4995.0 1016.89  4995.3 1016.39  4999.0 1016.89  5022.4 1019.21  5081.1 1019.43
  5089.5 1020.29  5103.4 1022.65  5125.8 1028.85  5142.6 1031.30  5148.2 1032.91
  5209.7 1038.04  5215.3 1039.80  5232.0 1042.26  5237.6 1042.25  5254.4 1045.02
  5260.0 1044.67  5282.3 1050.28  5290.7 1050.17  5304.7 1052.11  5335.4 1054.77
#Mann=4,-1,0
  4819.8    0.07       0  4821.6    0.12       0  4995.0    0.05       0
  4999.0    0.12       0
Bank Sta=4995,4999
Exp/Cntr=0.3,0.1

Type RM Length L Ch R = 1,5748,284,284,284
BEGIN DESCRIPTION:
X18144
END DESCRIPTION:
XS GIS Cut Line= 2
      2179416.28     13802511.19      2178968.99     13802130.89
#Sta/Elev= 30
  4732.1 1042.42  4765.7 1039.23  4780.0 1036.10  4786.5 1036.30  4794.3 1033.71
  4843.7 1030.60  4851.4 1027.17  4858.0 1027.13  4865.1 1023.71  4872.2 1020.66
  4921.6 1020.17  4950.2 1021.23  4964.5 1019.09  4993.1 1017.90  5003.9 1015.31
  5011.9 1012.99  5012.1 1012.49  5015.9 1012.99  5021.6 1015.07  5035.7 1014.36
  5042.5 1015.43  5063.3 1015.73  5091.9 1014.56  5120.4 1016.27  5184.1 1031.83
  5233.5 1040.31  5241.3 1040.39  5255.5 1042.62  5290.7 1050.18  5319.2 1052.94
#Mann=5,-1,0
  4732.1    0.12       0  4865.1    0.07       0  5003.9    0.12       0
  5011.9    0.05       0  5015.9    0.12       0
Bank Sta=5011.9,5015.9
Exp/Cntr=0.3,0.1

Type RM Length L Ch R = 1,5464,149,149,149
BEGIN DESCRIPTION:
Bear Creek Tributary 5 12.0
END DESCRIPTION:
XS GIS Cut Line= 3
      2179475.02     13802375.04      2179275.00     13802075.00
      2179175.00     13802025.00
#Sta/Elev= 30
  4634.8 1041.54  4663.4 1039.68  4670.9 1038.04  4693.4 1035.26  4714.5 1034.04
  4735.5 1031.09  4763.3 1025.87  4779.1 1024.04  4786.6 1022.02  4801.6 1019.38
  4822.6 1016.61  4851.2 1013.94  4873.7 1012.93  4923.3 1012.12  4930.8 1010.88
  4936.8 1011.33  4945.8 1010.71  4951.8 1011.89  4981.9 1011.70  5015.8 1008.31
  5016.0 1007.81  5019.5 1007.81  5019.8 1008.31  5031.7 1011.78  5040.1 1017.20
  5048.5 1021.09  5059.2 1024.83  5093.2 1035.02  5104.4 1037.01  5107.2 1037.01
#Mann=5,-1,0
  4634.8    0.12       0  4763.3    0.07       0  5015.8    0.05       0
  5019.8    0.07       0  5059.2    0.12       0
Bank Sta=5015.8,5019.8
Exp/Cntr=0.3,0.1

Type RM Length L Ch R = 1,5315,226,226,226
BEGIN DESCRIPTION:
X18146
END DESCRIPTION:
XS GIS Cut Line= 3
      2179522.66     13802324.62      2179388.09     13801994.72
      2179210.17     13801805.95
#Sta/Elev= 30
  4585.0 1039.63  4606.2 1036.48  4638.6 1033.98  4686.4 1026.96  4727.4 1019.47
  4789.8 1012.45  4887.8 1010.05  4911.9 1010.52  4935.9 1008.95  4938.8 1009.92
  4957.3 1010.18  4978.8 1007.91  4990.9 1007.82  4991.2 1007.32  4994.9 1007.82
  5016.0 1010.36  5028.1 1014.50  5049.6 1020.27  5056.4 1021.05  5063.7 1023.29
  5070.6 1022.40  5077.9 1025.72  5084.8 1026.90  5092.0 1029.73  5113.1 1035.11
  5127.2 1036.57  5155.6 1041.91  5169.7 1043.00  5183.9 1045.22  5200.7 1046.22
#Mann=5,-1,0
  4585.0    0.12       0  4686.4    0.07       0  4990.9    0.05       0
  4994.9    0.07       0  5016.0    0.12       0
Bank Sta=4990.9,4994.9
Exp/Cntr=0.3,0.1

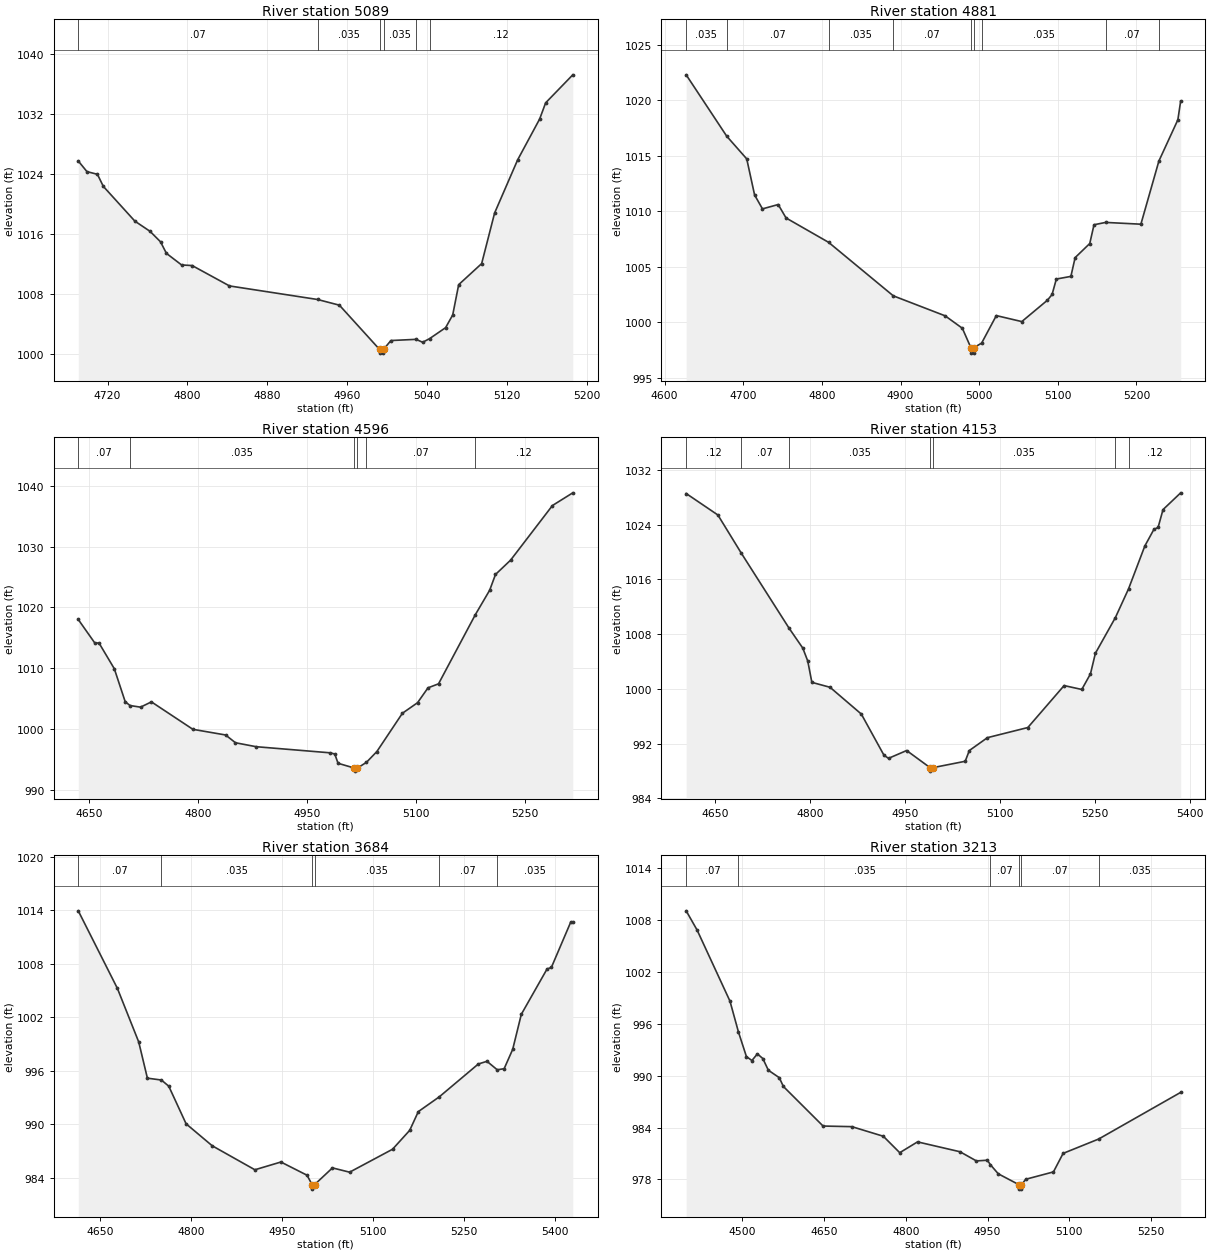
Type RM Length L Ch R = 1,5089,208,208,208
BEGIN DESCRIPTION:
Bear Creek Tributary 5 11.0
END DESCRIPTION:
XS GIS Cut Line= 3
      2179638.11     13802153.22      2179538.11     13801853.21
      2179389.03     13801753.83
#Sta/Elev= 30
  4690.7 1025.72  4699.4 1024.30  4709.9 1023.94  4715.8 1022.33  4747.4 1017.69
  4762.6 1016.33  4773.1 1014.93  4779.0 1013.39  4794.2 1011.84  4804.8 1011.76
  4842.2 1009.04  4930.4 1007.23  4952.3 1006.47  4992.5 1000.57  4992.8 1000.07
  4996.3 1000.07  4996.5 1000.57  5003.9 1001.75  5029.1 1001.91  5035.7 1001.52
  5042.6 1002.00  5058.7 1003.47  5065.8 1005.16  5071.8 1009.21  5094.8 1012.02
  5107.8 1018.78  5130.9 1025.88  5152.9 1031.32  5158.9 1033.48  5186.1 1037.22
#Mann=6,-1,0
  4690.7    0.07       0  4930.4   0.035       0  4992.5   0.035       0
  4996.5   0.035       0  5029.1    0.07       0  5042.6    0.12       0
Bank Sta=4992.5,4996.5
Exp/Cntr=0.3,0.1

Type RM Length L Ch R = 1,4881,285,285,285
BEGIN DESCRIPTION:
X18143
END DESCRIPTION:
XS GIS Cut Line= 3
      2179746.17     13802111.92      2179733.15     13801812.43
      2179608.01     13801508.23
#Sta/Elev= 30
  4627.5 1022.28  4679.0 1016.76  4704.5 1014.71  4714.5 1011.46  4724.5 1010.21
  4744.5 1010.60  4754.5 1009.39  4808.5 1007.20  4890.8 1002.38  4956.7 1000.58
  4978.6  999.46  4989.4  997.72  4989.7  997.22  4993.2  997.22  4993.4  997.72
  5003.1  998.12  5021.8 1000.60  5054.2 1000.06  5086.7 1001.98  5092.7 1002.50
  5098.1 1003.89  5116.6 1004.13  5122.0 1005.82  5140.6 1007.09  5146.0 1008.78
  5160.8 1008.99  5205.6 1008.83  5228.5 1014.52  5252.6 1018.23  5256.2 1019.93
#Mann=9,-1,0
  4627.5   0.035       0  4679.0    0.07       0  4808.5   0.035       0
  4890.8    0.07       0  4989.4    0.05       0  4993.4    0.07       0
  5003.1   0.035       0  5160.8    0.07       0  5228.5    0.12       0
Bank Sta=4989.4,4993.4
Exp/Cntr=0.3,0.1

Type RM Length L Ch R = 1,4596,443,443,443
BEGIN DESCRIPTION:
Bear Creek Tributary 5 10.0
END DESCRIPTION:
XS GIS Cut Line= 3
      2180175.03     13801725.02      2179875.00     13801525.00
      2179625.04     13801325.03
#Sta/Elev= 30
  4634.6 1017.99  4657.2 1014.15  4663.2 1014.11  4684.2 1009.89  4699.2 1004.46
  4705.8 1003.83  4720.3 1003.56  4735.3 1004.43  4792.4  999.91  4837.4  998.98
  4851.0  997.70  4879.5  997.05  4981.7  996.04  4987.7  995.84  4992.2  994.32
  5014.8  993.53  5015.0  993.03  5018.8  993.53  5031.3  994.48  5045.6  996.25
  5080.8 1002.56  5101.6 1004.29  5116.0 1006.74  5130.5 1007.40  5181.2 1018.79
  5200.9 1022.81  5208.9 1025.40  5229.7 1027.76  5287.3 1036.75  5315.3 1038.84
#Mann=6,-1,0
  4634.6    0.07       0  4705.8   0.035       0  5014.8   0.035       0
  5018.8   0.035       0  5031.3    0.07       0  5181.2    0.12       0
Bank Sta=5014.8,5018.8
Exp/Cntr=0.3,0.1

Type RM Length L Ch R = 1,4153,469,469,469
BEGIN DESCRIPTION:
Bear Creek Tributary 5 9.0
END DESCRIPTION:
XS GIS Cut Line= 3
      2180425.02     13801525.02      2180175.00     13801225.00
      2179875.04     13800975.03
#Sta/Elev= 30
  4604.4 1028.55  4654.5 1025.41  4691.5 1019.83  4766.8 1008.89  4788.6 1005.96
  4796.4 1004.08  4802.9 1000.96  4831.6 1000.24  4881.0  996.33  4916.8  990.31
  4924.0  989.86  4952.6  991.00  4989.7  988.49  4989.9  987.99  4993.7  988.49
  5045.1  989.43  5051.6  991.00  5080.2  992.88  5144.0  994.36  5201.3 1000.49
  5229.2  999.92  5242.9 1002.20  5250.7 1005.21  5282.3 1010.43  5303.0 1014.61
  5328.8 1020.89  5343.1 1023.31  5349.7 1023.59  5357.5 1026.20  5385.4 1028.65
#Mann=7,-1,0
  4604.4    0.12       0  4691.5    0.07       0  4766.8   0.035       0
  4989.7   0.035       0  4993.7   0.035       0  5282.3    0.07       0
  5303.0    0.12       0
Bank Sta=4989.7,4993.7
Exp/Cntr=0.3,0.1

Type RM Length L Ch R = 1,3684,471,471,471
BEGIN DESCRIPTION:
Bear Creek Tributary 5 8.0
END DESCRIPTION:
XS GIS Cut Line= 3
      2180725.02     13801175.03      2180475.00     13800875.00
      2180175.01     13800575.01
#Sta/Elev= 30
  4614.5 1013.92  4679.0 1005.22  4714.1  999.22  4728.4  995.16  4751.5  994.95
  4763.6  994.26  4792.2  990.04  4835.2  987.58  4905.5  984.89  4948.4  985.76
  4991.4  984.28  4999.8  983.22  5000.0  982.72  5003.8  983.22  5033.3  985.10
  5061.6  984.62  5132.3  987.19  5160.6  989.31  5174.8  991.41  5209.4  993.07
  5273.7  996.75  5287.9  997.05  5304.8  996.10  5316.2  996.22  5330.3  998.39
  5344.5 1002.32  5386.9 1007.40  5394.0 1007.57  5425.8 1012.64  5429.3 1012.64
#Mann=6,-1,0
  4614.5    0.07       0  4751.5   0.035       0  4999.8   0.035       0
  5003.8   0.035       0  5209.4    0.07       0  5304.8   0.035       0
Bank Sta=4999.8,5003.8
Exp/Cntr=0.3,0.1

Type RM Length L Ch R = 1,3213,469,469,469
BEGIN DESCRIPTION:
Bear Creek Tributary 5 7.0
END DESCRIPTION:
XS GIS Cut Line= 3
      2180825.00     13801125.04      2180775.00     13800525.00
      2180474.96     13800474.99
#Sta/Elev= 30
  4397.6 1009.04  4417.7 1006.81  4477.9  998.60  4493.5  995.02  4508.0  992.20
  4518.1  991.74  4528.1  992.51  4538.1  991.97  4548.2  990.62  4568.2  989.76
  4575.8  988.74  4648.5  984.17  4701.2  984.10  4758.9  982.99  4789.0  981.09
  4821.6  982.34  4899.4  981.20  4929.5  980.14  4949.5  980.22  4955.2  979.70
  4969.6  978.65  5007.9  977.38  5008.1  976.88  5011.6  976.88  5011.9  977.38
  5020.0  978.02  5070.7  978.87  5088.4  981.01  5153.6  982.67  5303.9  988.06
#Mann=6,-1,0
  4397.6    0.07       0  4493.5   0.035       0  4955.2    0.07       0
  5007.9    0.05       0  5011.9    0.07       0  5153.6   0.035       0
Bank Sta=5007.9,5011.9
Exp/Cntr=0.3,0.1

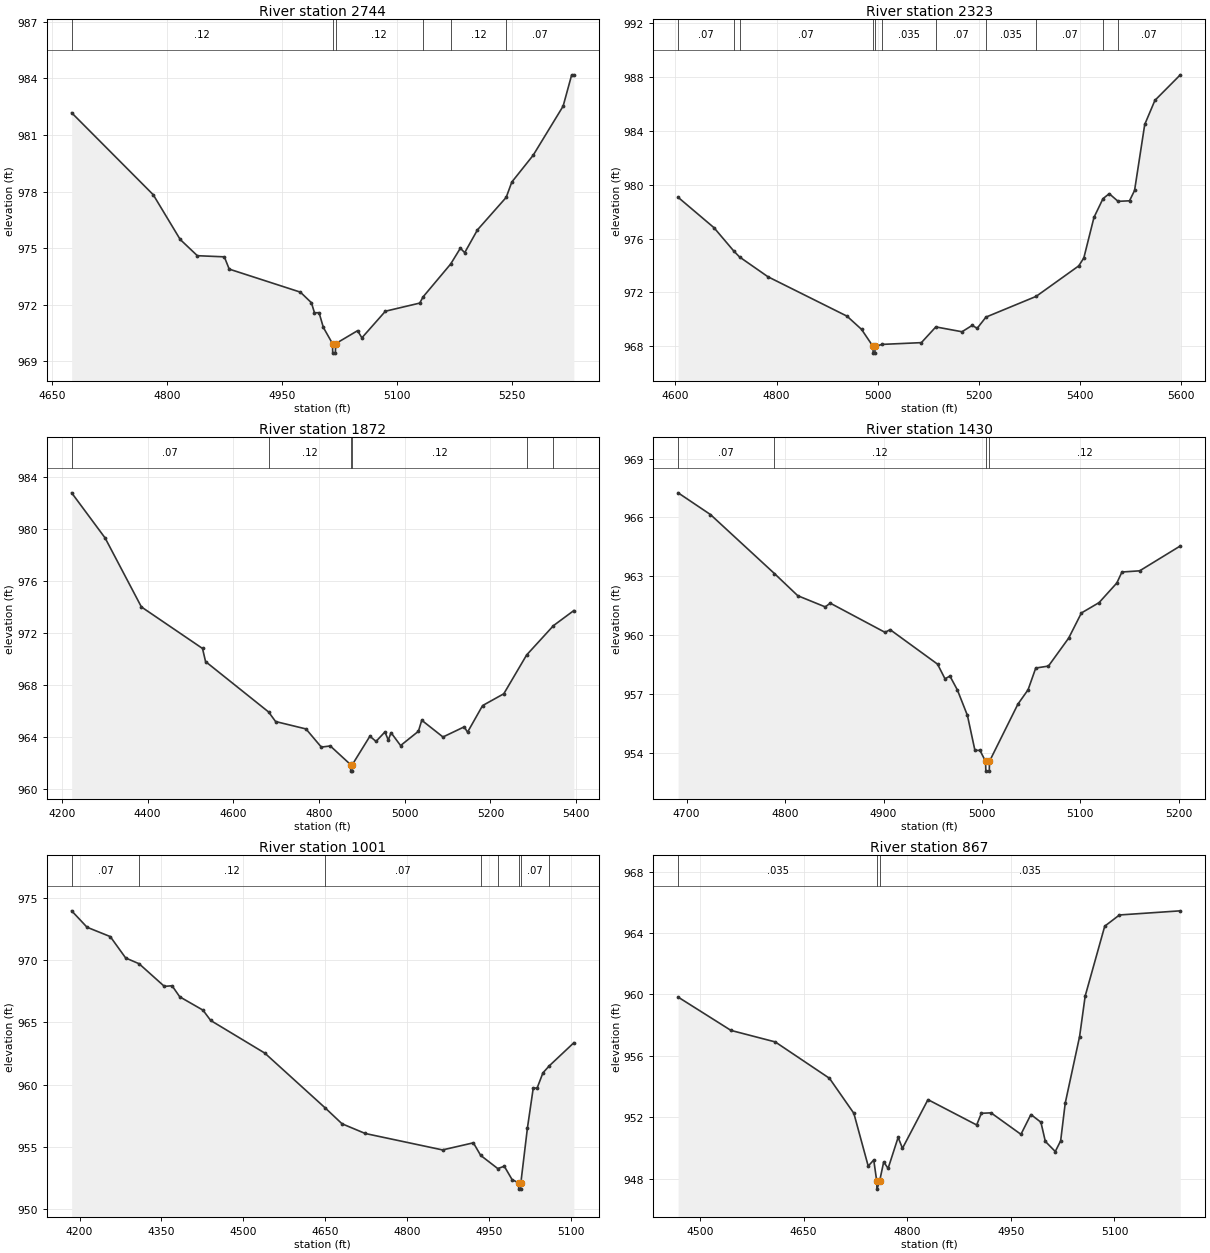
Type RM Length L Ch R = 1,2744,421,421,421
BEGIN DESCRIPTION:
Bear Creek Tributary 5 6.0
END DESCRIPTION:
XS GIS Cut Line= 3
      2181325.03     13800375.03      2181075.00     13800175.00
      2180775.01     13800025.00
#Sta/Elev= 30
  4675.5  982.17  4782.0  977.83  4817.2  975.46  4839.6  974.60  4874.8  974.54
  4881.2  973.89  4974.1  972.67  4988.5  972.11  4992.5  971.58  4998.5  971.58
  5004.1  970.80  5016.1  969.94  5016.3  969.44  5019.8  969.44  5020.1  969.94
  5048.8  970.63  5054.4  970.25  5085.1  971.66  5129.9  972.09  5134.3  972.42
  5170.3  974.16  5183.0  975.00  5188.6  974.76  5205.3  975.97  5242.8  977.69
  5250.1  978.50  5278.0  979.92  5317.1  982.52  5328.3  984.18  5331.1  984.18
#Mann=6,-1,0
  4675.5    0.12       0  5016.1    0.05       0  5020.1    0.12       0
  5134.3    0.07       0  5170.3    0.12       0  5242.8    0.07       0
Bank Sta=5016.1,5020.1
Exp/Cntr=0.3,0.1

Type RM Length L Ch R = 1,2323,451,451,451
BEGIN DESCRIPTION:
Bear Creek Tributary 5 5.0
END DESCRIPTION:
XS GIS Cut Line= 3
      2181524.98     13800124.97      2181275.00     13799825.00
      2180674.95     13799875.00
#Sta/Elev= 30
  4605.4  979.07  4676.3  976.81  4715.3  975.08  4726.9  974.63  4783.0  973.16
  4939.2  970.23  4967.9  969.25  4990.6  967.98  4990.9  967.48  4994.4  967.48
  4994.6  967.98  5008.7  968.13  5086.2  968.26  5114.8  969.43  5166.5  969.07
  5186.5  969.54  5196.6  969.33  5213.9  970.16  5313.0  971.70  5397.3  973.97
  5407.3  974.56  5427.4  977.58  5445.2  978.97  5457.5  979.34  5475.0  978.77
  5497.6  978.81  5507.6  979.58  5527.7  984.49  5547.8  986.28  5598.0  988.18
#Mann=11,-1,0
  4605.4    0.07       0  4715.3    0.12       0  4726.9    0.07       0
  4990.6    0.05       0  4994.6    0.07       0  5008.7   0.035       0
  5114.8    0.07       0  5213.9   0.035       0  5313.0    0.07       0
  5445.2   0.035       0  5475.0    0.07       0
Bank Sta=4990.6,4994.6
Exp/Cntr=0.3,0.1

Type RM Length L Ch R = 1,1872,442,442,442
BEGIN DESCRIPTION:
Bear Creek Tributary 5 4.0
END DESCRIPTION:
XS GIS Cut Line= 3
      2181725.02     13798924.99      2181125.00     13799425.00
      2180824.97     13799675.03
#Sta/Elev= 30
  4223.0  982.80  4301.1  979.32  4385.7  974.01  4528.3  970.81  4535.4  969.80
  4682.4  965.92  4698.8  965.18  4769.7  964.61  4805.5  963.21  4826.4  963.30
  4873.8  961.86  4874.1  961.36  4877.6  961.36  4877.8  961.86  4918.8  964.05
  4933.1  963.65  4953.9  964.38  4961.7  963.75  4968.2  964.32  4990.4  963.33
  5032.0  964.43  5039.8  965.28  5089.3  963.99  5138.8  964.77  5146.6  964.36
  5181.7  966.41  5231.2  967.32  5284.5  970.31  5347.1  972.57  5394.6  973.73
#Mann=6,-1,0
  4223.0    0.07       0  4682.4    0.12       0  4873.8    0.05       0
  4877.8    0.12       0  5284.5    0.07       0  5347.1   0.035       0
Bank Sta=4873.8,4877.8
Exp/Cntr=0.3,0.1

Type RM Length L Ch R = 1,1430,429,429,429
BEGIN DESCRIPTION:
Bear Creek Tributary 5 3.0
END DESCRIPTION:
XS GIS Cut Line= 3
      2181374.97     13799075.00      2181075.00     13799025.00
      2180874.96     13799075.01
#Sta/Elev= 30
  4691.3  967.25  4724.2  966.14  4789.2  963.13  4812.9  962.00  4840.8  961.43
  4845.9  961.62  4901.6  960.13  4906.7  960.27  4954.9  958.51  4962.5  957.76
  4967.5  957.90  4975.1  957.19  4985.3  955.89  4992.9  954.11  4998.0  954.11
  5003.7  953.55  5004.0  953.05  5007.5  953.05  5007.7  953.55  5036.6  956.47
  5046.9  957.20  5054.7  958.31  5067.6  958.41  5088.2  959.84  5101.1  961.12
  5119.1  961.65  5137.1  962.65  5142.3  963.21  5160.3  963.27  5201.6  964.54
#Mann=4,-1,0
  4691.3    0.07       0  4789.2    0.12       0  5003.7    0.05       0
  5007.7    0.12       0
Bank Sta=5003.7,5007.7
Exp/Cntr=0.3,0.1

Type RM Length L Ch R = 1,1001,134,134,134
BEGIN DESCRIPTION:
Bear Creek Tributary 5 2.0
END DESCRIPTION:
XS GIS Cut Line= 3
      2181324.97     13798275.03      2180725.00     13798875.00
      2180674.99     13798925.01
#Sta/Elev= 30
  4185.6  973.96  4213.8  972.64  4256.3  971.89  4284.5  970.17  4309.0  969.71
  4355.3  967.89  4369.4  967.94  4383.5  967.05  4426.0  965.98  4440.1  965.15
  4539.1  962.53  4649.8  958.12  4680.5  956.85  4723.0  956.07  4864.4  954.75
  4920.9  955.32  4934.3  954.31  4965.6  953.25  4977.5  953.44  4991.7  952.37
  5003.8  952.10  5004.0  951.60  5007.5  951.60  5007.8  952.10  5019.9  956.53
  5030.5  959.72  5037.6  959.72  5048.2  960.94  5059.7  961.50  5104.8  963.36
#Mann=8,-1,0
  4185.6    0.07       0  4309.0    0.12       0  4649.8    0.07       0
  4934.3   0.035       0  4965.6    0.07       0  5003.8    0.05       0
  5007.8    0.07       0  5059.7   0.035       0
Bank Sta=5003.8,5007.8
Exp/Cntr=0.3,0.1

Type RM Length L Ch R = 1,867,363,363,363
BEGIN DESCRIPTION:
Bear Creek Tributary 5 1.5
END DESCRIPTION:
XS GIS Cut Line= 2
      2180978.29     13798381.02      2180526.63     13798950.70
#Sta/Elev= 30
  4468.3  959.83  4544.8  957.66  4608.9  956.91  4687.4  954.54  4722.7  952.26
  4743.5  948.82  4751.5  949.22  4755.9  947.82  4756.1  947.32  4759.9  947.82
  4765.9  949.09  4772.3  948.67  4786.8  950.69  4793.1  949.98  4830.0  953.15
  4900.5  951.50  4907.3  952.26  4921.3  952.29  4964.6  950.89  4979.0  952.18
  4993.5  951.68  4999.9  950.43  5014.3  949.77  5022.1  950.47  5028.7  952.92
  5049.5  957.26  5057.6  959.90  5085.9  964.45  5107.2  965.18  5195.3  965.45
#Mann=3,-1,0
  4468.3   0.035       0  4755.9   0.035       0  4759.9   0.035       0
Bank Sta=4755.9,4759.9
Exp/Cntr=0.3,0.1

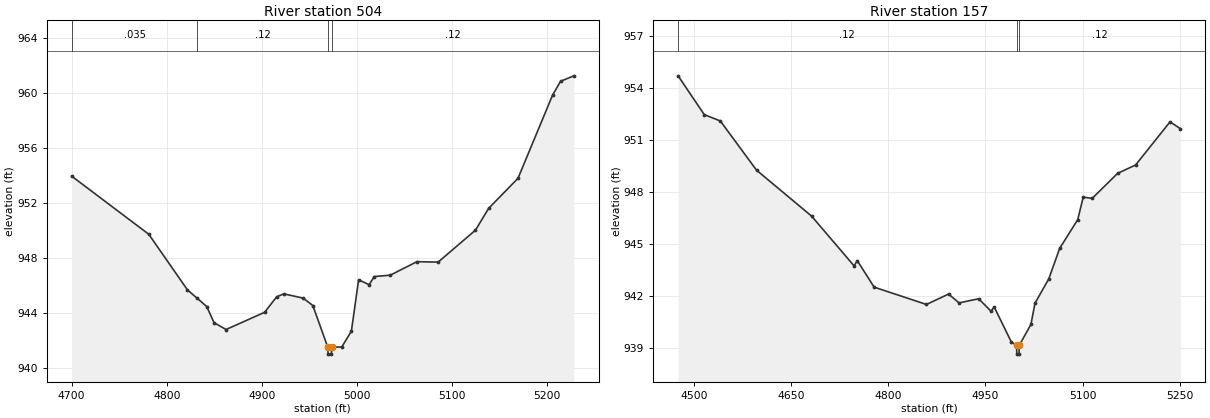
Type RM Length L Ch R = 1,504,347,347,347
BEGIN DESCRIPTION:
Bear Creek Tributary 5 1.0
END DESCRIPTION:
XS GIS Cut Line= 3
      2180775.04     13798474.99      2180475.00     13798525.00
      2180375.00     13798725.01
#Sta/Elev= 30
  4700.1  953.95  4781.2  949.72  4821.8  945.68  4832.2  945.06  4842.1  944.47
  4849.7  943.30  4862.4  942.80  4902.9  944.05  4915.6  945.18  4923.2  945.39
  4943.5  945.08  4953.6  944.54  4969.3  941.51  4969.6  941.01  4973.1  941.01
  4973.3  941.51  4984.0  941.53  4994.1  942.68  5001.7  946.41  5012.7  946.06
  5018.3  946.65  5035.0  946.75  5063.0  947.73  5085.3  947.70  5124.5  950.02
  5138.4  951.61  5169.2  953.79  5205.5  959.83  5213.9  960.84  5227.9  961.24
#Mann=4,-1,0
  4700.1   0.035       0  4832.2    0.12       0  4969.3    0.05       0
  4973.3    0.12       0
Bank Sta=4969.3,4973.3
Exp/Cntr=0.3,0.1

Type RM Length L Ch R = 1,157,0,0,0
BEGIN DESCRIPTION:
Bear Creek Tributary 5 0.5
END DESCRIPTION:
XS GIS Cut Line= 3
      2180894.99     13798140.77      2180347.78     13798219.28
      2180247.79     13798419.26
#Sta/Elev= 30
  4474.8  954.70  4515.2  952.46  4540.1  952.09  4596.0  949.25  4681.3  946.59
  4746.8  943.72  4751.8  944.02  4777.9  942.49  4858.7  941.49  4892.9  942.09
  4909.2  941.58  4939.5  941.82  4958.5  941.10  4963.5  941.34  4990.0  939.32
  4998.1  939.12  4998.4  938.62  5001.9  938.62  5002.1  939.12  5020.3  940.34
  5026.5  941.56  5047.9  942.97  5064.7  944.73  5092.6  946.39  5101.1  947.69
  5115.0  947.62  5154.1  949.06  5182.1  949.55  5235.3  952.04  5251.2  951.65
#Mann=3,-1,0
  4474.8    0.12       0  4998.1    0.05       0  5002.1    0.12       0
Bank Sta=4998.1,5002.1
Exp/Cntr=0.3,0.1

Chan Stop Cuts=-1