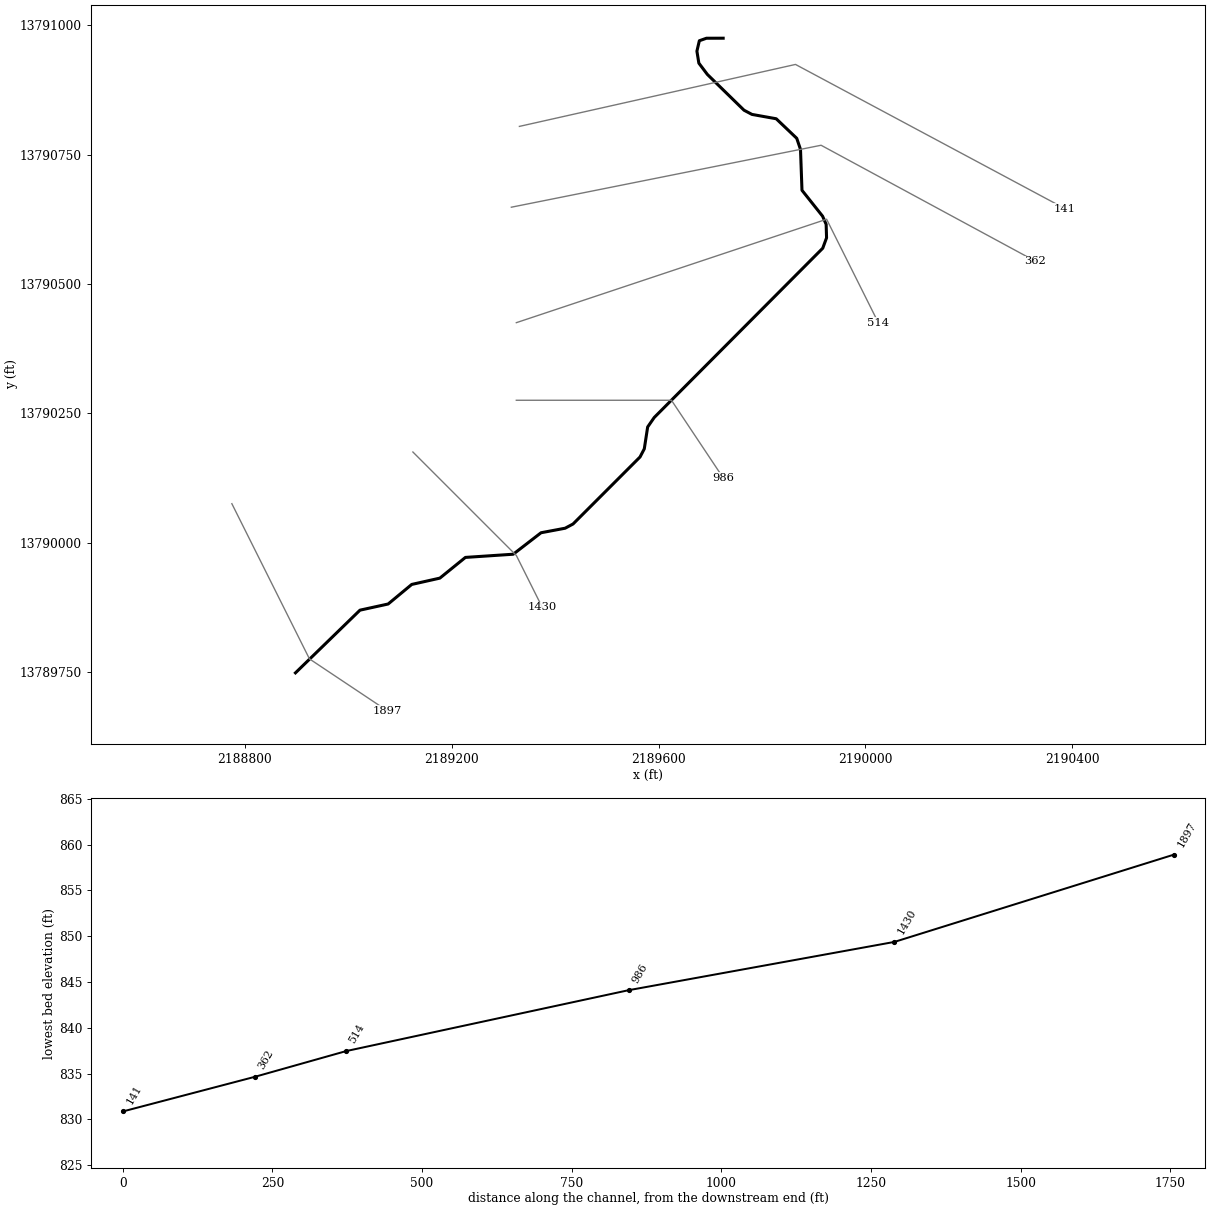
--- Bear Creek Tributary 6.prj (project) ---

Proj Title=Bear Creek Tributary 6 Base Level Engineering
Current Plan=p01
Default Exp/Contr=0.3,0.1
English Units
Geom File=g01
Flow File=f01
Plan File=p01
BEGIN DESCRIPTION:
Bear Creek Tributary 6
END DESCRIPTION:

--- Bear Creek Tributary 6.p01 (plan) ---

Plan Title=Multiple Run
Short Identifier=Multiple
Geom File=g01
Flow File=f01
Subcritical Flow
K Sum by GR= 0
Std Step Tol= 0.01
Critical Tol= 0.01
Num of Std Step Trials= 20
Max Error Tol= 0.3
Flow Tol Ratio= 0.001
Split Flow NTrial= 30
Split Flow Tol= 0.02
Split Flow Ratio= 0.02
Log Output Level= 0
Friction Slope Method= 1
Unsteady Friction Slope Method= 2
Unsteady Bridges Friction Slope Method= 1
Parabolic Critical Depth
Global Vel Dist=  1 , 1 , 1
Global Log Level= 0
CheckData=True
Encroach Param= -1, 0, 0, 0
BEGIN DESCRIPTION:
Multiple Run
END DESCRIPTION:

--- Bear Creek Tributary 6.f01 (steady flow) ---

Flow Title=Multiple
Number of Profiles=7
Profile Names=10-year,25-year,50-year,1pct_min,100-year,1pct_plu,500-year
River Rch & RM= Bear Creek Tribu,Reach-1,1897
     360     567     751     484     965    1926    1573
Boundary for River Rch & Prof#=Bear Creek Tribu,Reach-1,1
Up Type=0
Dn Type=3
Dn Slope=0.005
Boundary for River Rch & Prof#=Bear Creek Tribu,Reach-1,2
Up Type=0
Dn Type=3
Dn Slope=0.005
Boundary for River Rch & Prof#=Bear Creek Tribu,Reach-1,3
Up Type=0
Dn Type=3
Dn Slope=0.005
Boundary for River Rch & Prof#=Bear Creek Tribu,Reach-1,4
Up Type=0
Dn Type=3
Dn Slope=0.005
Boundary for River Rch & Prof#=Bear Creek Tribu,Reach-1,5
Up Type=0
Dn Type=3
Dn Slope=0.005
Boundary for River Rch & Prof#=Bear Creek Tribu,Reach-1,6
Up Type=0
Dn Type=3
Dn Slope=0.005
Boundary for River Rch & Prof#=Bear Creek Tribu,Reach-1,7
Up Type=0
Dn Type=3
Dn Slope=0.005

--- Bear Creek Tributary 6.g01 (geometry) ---

Geom Title=Existing Conditions

River Reach=Bear Creek Tribu,Reach-1
Reach XY= 30
      2188897.95     13789747.95      2189022.70     13789869.18
      2189077.19     13789881.10      2189122.80     13789918.92
      2189177.18     13789931.12      2189226.58     13789971.17
      2189319.03     13789977.33      2189372.83     13790018.86
      2189419.38     13790027.61      2189434.68     13790035.76
      2189564.22     13790165.32      2189572.47     13790181.05
      2189578.98     13790223.35      2189591.65     13790241.67
      2189917.52     13790568.94      2189924.91     13790589.04
      2189924.12     13790615.13      2189917.21     13790630.91
      2189877.39     13790680.97      2189874.53     13790759.91
      2189867.26     13790781.45      2189827.57     13790819.26
      2189780.67     13790827.66      2189765.31     13790835.78
      2189694.42     13790904.97      2189677.97     13790926.79
      2189674.21     13790949.94      2189678.93     13790970.08
      2189692.63     13790974.93      2189725.00     13790975.00

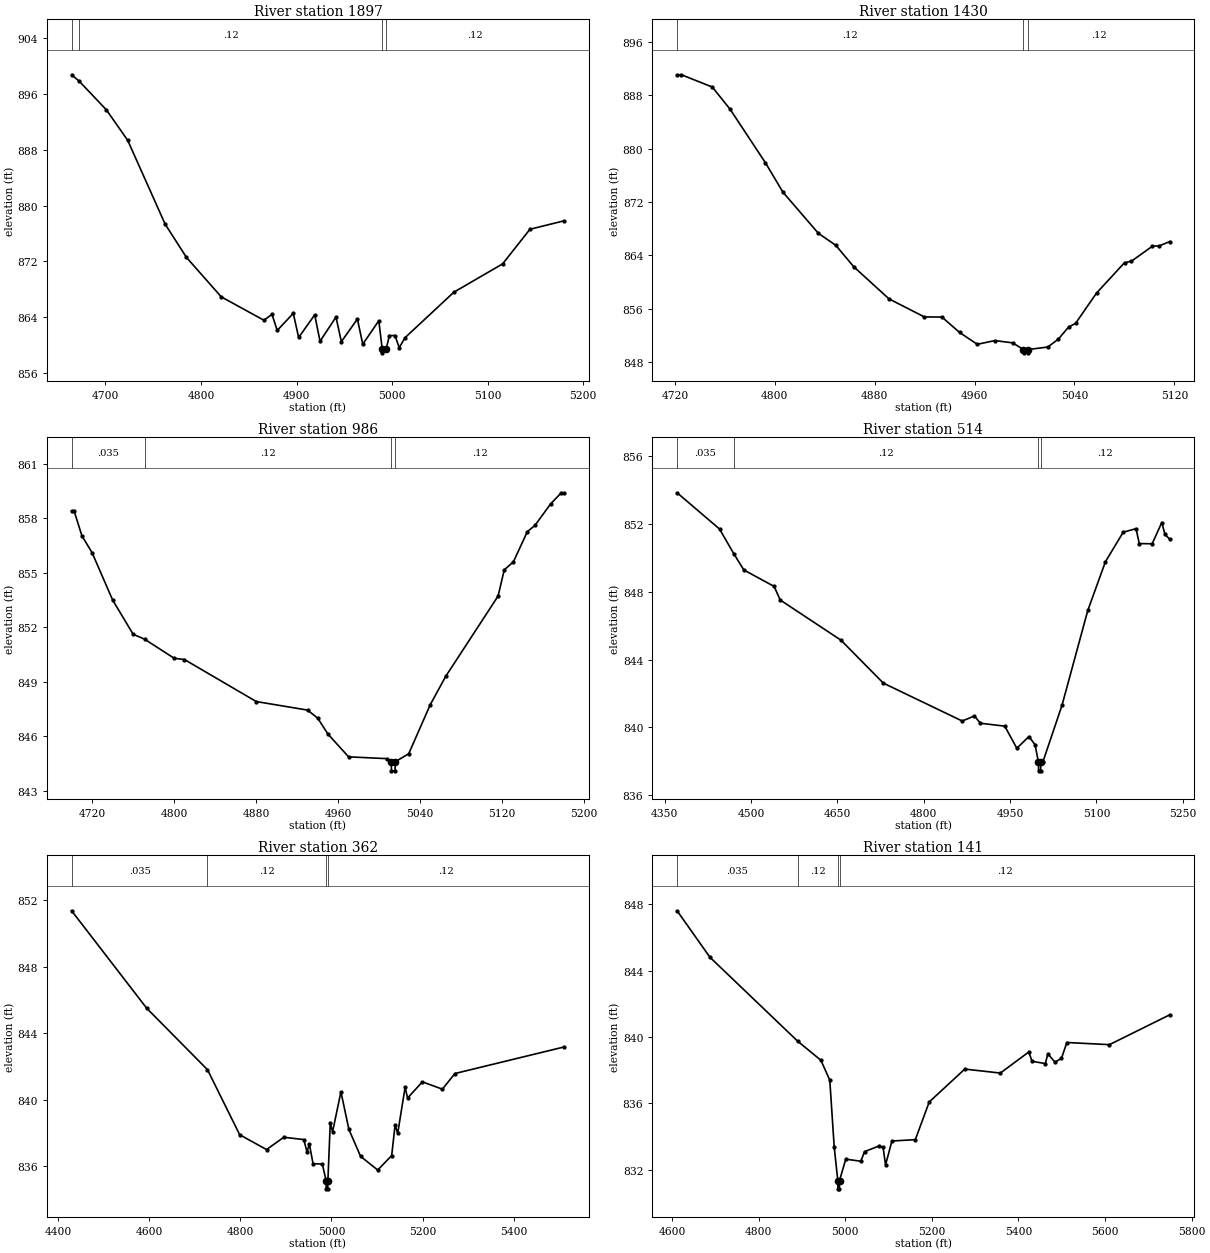
Type RM Length L Ch R = 1,1897,467,467,467
BEGIN DESCRIPTION:
Bear Creek Tributary 6 4.0
END DESCRIPTION:
XS GIS Cut Line= 3
      2188774.99     13790075.02      2188925.00     13789775.00
      2189074.99     13789675.01
#Sta/Elev= 30
  4664.6  898.77  4672.4  897.87  4701.0  893.74  4723.3  889.37  4762.5  877.35
  4784.8  872.58  4821.2  866.93  4865.9  863.57  4874.3  864.42  4879.8  862.11
  4896.6  864.57  4902.2  861.10  4919.0  864.35  4924.6  860.56  4941.3  864.03
  4946.9  860.50  4963.7  863.75  4969.3  860.14  4986.1  863.50  4989.7  859.40
  4989.9  858.90  4993.7  859.40  4997.2  861.38  5003.0  861.38  5007.5  859.65
  5013.6  861.08  5064.6  867.59  5115.7  871.66  5144.3  876.62  5180.3  877.84
#Mann=4,-1,0
  4664.6   0.035       0  4672.4    0.12       0  4989.7    0.05       0
  4993.7    0.12       0
Bank Sta=4989.7,4993.7
Exp/Cntr=0.3,0.1

Type RM Length L Ch R = 1,1430,444,444,444
BEGIN DESCRIPTION:
Bear Creek Tributary 6 3.0
END DESCRIPTION:
XS GIS Cut Line= 3
      2189125.03     13790174.97      2189325.00     13789975.00
      2189375.00     13789875.01
#Sta/Elev= 30
  4721.8  891.10  4725.3  891.10  4750.0  889.26  4764.2  885.94  4792.5  877.91
  4806.6  873.47  4834.9  867.32  4849.0  865.49  4863.2  862.30  4891.5  857.47
  4919.8  854.76  4933.9  854.74  4948.0  852.43  4962.2  850.65  4976.3  851.21
  4990.5  850.87  4999.1  849.87  4999.3  849.37  5002.8  849.37  5003.1  849.87
  5018.6  850.24  5027.0  851.40  5035.3  853.24  5040.9  853.79  5057.7  858.34
  5080.1  862.90  5085.7  863.13  5102.4  865.37  5108.0  865.43  5116.4  866.07
#Mann=3,-1,0
  4721.8    0.12       0  4999.1    0.05       0  5003.1    0.12       0
Bank Sta=4999.1,5003.1
Exp/Cntr=0.3,0.1

Type RM Length L Ch R = 1,986,472,472,472
BEGIN DESCRIPTION:
Bear Creek Tributary 6 2.0
END DESCRIPTION:
XS GIS Cut Line= 3
      2189324.99     13790275.00      2189625.00     13790275.00
      2189725.01     13790124.99
#Sta/Elev= 30
  4700.3  858.38  4702.8  858.38  4710.3  857.03  4720.3  856.09  4740.3  853.49
  4760.3  851.61  4771.4  851.34  4800.3  850.29  4810.3  850.22  4880.3  847.91
  4930.3  847.44  4940.3  846.99  4950.3  846.11  4970.3  844.87  5007.8  844.77
  5011.8  844.60  5012.1  844.10  5015.6  844.10  5015.8  844.60  5028.9  845.04
  5049.9  847.74  5064.9  849.29  5116.0  853.71  5122.0  855.15  5131.0  855.60
  5144.5  857.25  5152.0  857.60  5167.1  858.77  5177.6  859.39  5180.6  859.39
#Mann=4,-1,0
  4700.3   0.035       0  4771.4    0.12       0  5011.8    0.05       0
  5015.8    0.12       0
Bank Sta=5011.8,5015.8
Exp/Cntr=0.3,0.1

Type RM Length L Ch R = 1,514,152,152,152
BEGIN DESCRIPTION:
Bear Creek Tributary 6 1.0
END DESCRIPTION:
XS GIS Cut Line= 3
      2189325.04     13790425.01      2189925.00     13790625.00
      2190024.99     13790425.02
#Sta/Elev= 30
  4371.4  853.81  4445.1  851.68  4469.8  850.23  4487.3  849.27  4540.0  848.30
  4550.6  847.50  4656.0  845.14  4729.7  842.61  4866.8  840.38  4887.9  840.68
  4898.4  840.25  4940.6  840.08  4961.6  838.78  4982.7  839.47  4993.3  838.98
  4999.2  837.95  4999.4  837.45  5002.9  837.45  5003.2  837.95  5006.6  837.95
  5040.1  841.31  5084.9  846.89  5115.6  849.76  5146.4  851.49  5168.7  851.70
  5174.3  850.82  5196.7  850.81  5213.4  852.06  5219.0  851.36  5227.4  851.07
#Mann=4,-1,0
  4371.4   0.035       0  4469.8    0.12       0  4999.2    0.05       0
  5003.2    0.12       0
Bank Sta=4999.2,5003.2
Exp/Cntr=0.3,0.1

Type RM Length L Ch R = 1,362,221,221,221
BEGIN DESCRIPTION:
X18148
END DESCRIPTION:
XS GIS Cut Line= 3
      2189315.38     13790648.25      2189914.32     13790768.03
      2190328.34     13790544.10
#Sta/Elev= 30
  4429.8  851.36  4594.7  845.50  4728.0  841.81  4798.7  837.90  4857.7  837.01
  4895.5  837.75  4939.3  837.61  4946.5  836.87  4951.6  837.34  4959.7  836.16
  4980.1  836.14  4988.3  835.15  4988.6  834.65  4992.1  834.65  4992.3  835.15
  4997.5  838.61  5002.6  838.08  5020.9  840.48  5038.4  838.22  5064.1  836.60
  5101.7  835.78  5132.3  836.65  5139.8  838.49  5145.5  837.98  5161.7  840.74
  5167.3  840.11  5199.7  841.08  5243.5  840.64  5271.1  841.58  5511.3  843.18
#Mann=4,-1,0
  4429.8   0.035       0  4728.0    0.12       0  4988.3    0.05       0
  4992.3    0.12       0
Bank Sta=4988.3,4992.3
Exp/Cntr=0.3,0.1

Type RM Length L Ch R = 1,141,0,0,0
BEGIN DESCRIPTION:
X18147
END DESCRIPTION:
XS GIS Cut Line= 3
      2189330.98     13790804.49      2189864.84     13790924.28
      2190385.66     13790645.65
#Sta/Elev= 30
  4611.8  847.60  4687.7  844.80  4890.6  839.74  4943.9  838.60  4964.4  837.40
  4974.6  833.38  4982.9  831.36  4983.1  830.86  4986.6  830.86  4986.9  831.36
  5001.3  832.65  5036.1  832.52  5044.6  833.10  5077.1  833.43  5087.4  833.37
  5093.1  832.30  5107.9  833.74  5161.9  833.82  5194.0  836.09  5276.1  838.07
  5358.2  837.83  5424.0  839.10  5431.3  838.54  5462.2  838.40  5467.9  838.99
  5484.2  838.49  5499.3  838.71  5511.8  839.67  5610.1  839.54  5749.6  841.34
#Mann=4,-1,0
  4611.8   0.035       0  4890.6    0.12       0  4982.9    0.05       0
  4986.9    0.12       0
Bank Sta=4982.9,4986.9
Exp/Cntr=0.3,0.1

Chan Stop Cuts=-1