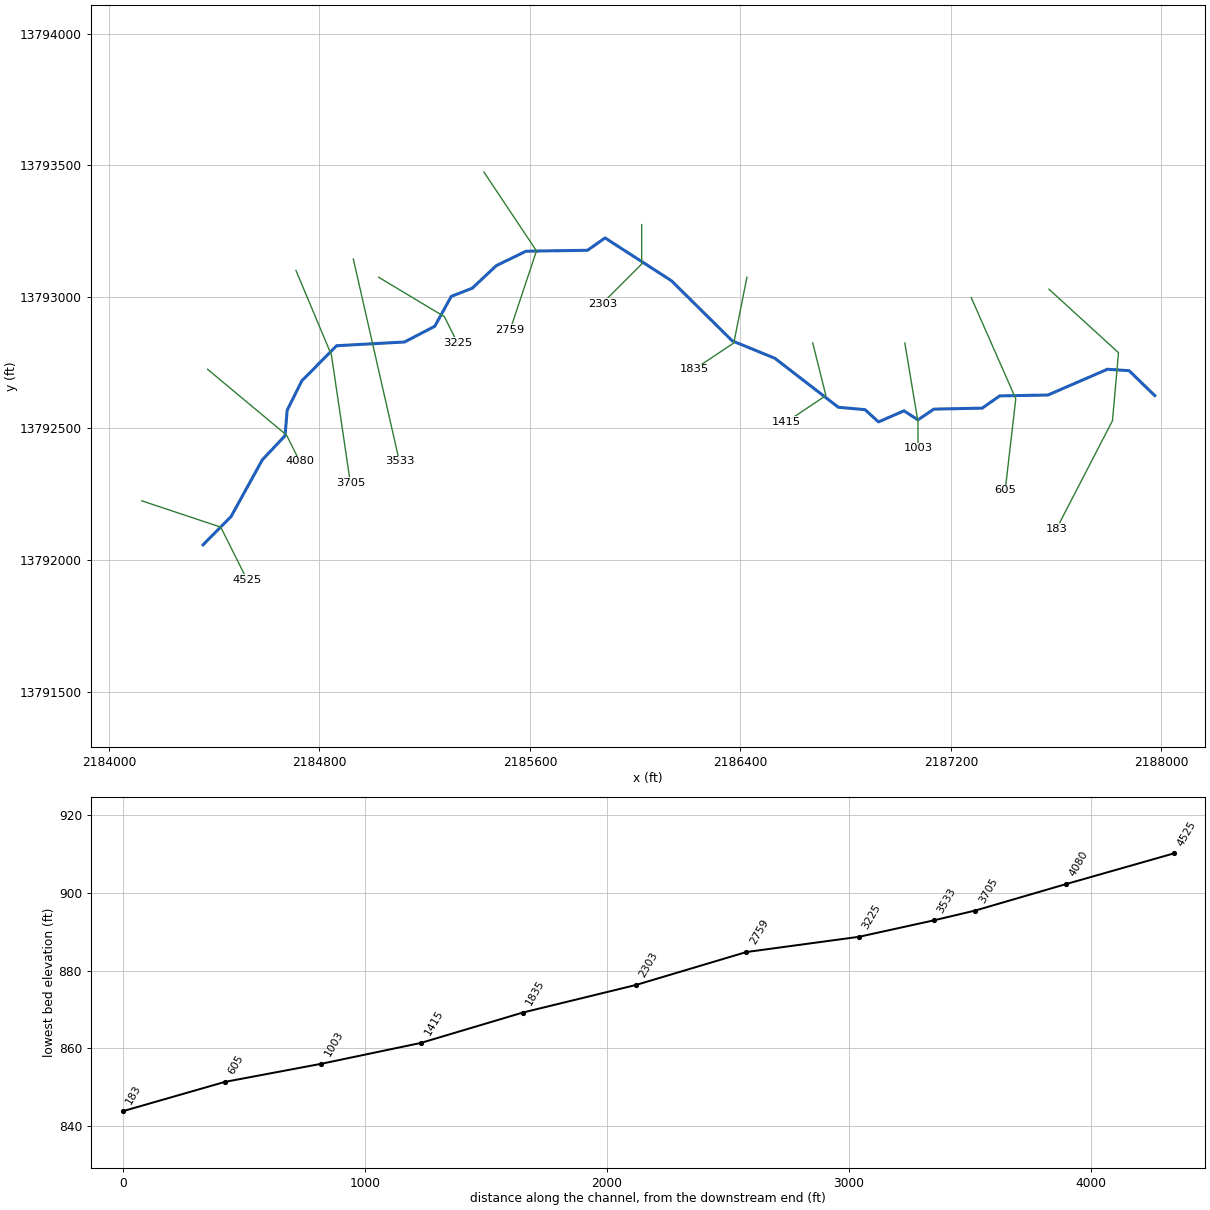
--- Bear Creek Tributary 7.prj (project) ---

Proj Title=Bear Creek Tributary 7 Base Level Engineering
Current Plan=p01
Default Exp/Contr=0.3,0.1
English Units
Geom File=g01
Flow File=f01
Plan File=p01
BEGIN DESCRIPTION:
Bear Creek Tributary 7
END DESCRIPTION:

--- Bear Creek Tributary 7.p01 (plan) ---

Plan Title=Multiple Run
Short Identifier=Multiple
Geom File=g01
Flow File=f01
Subcritical Flow
K Sum by GR= 0
Std Step Tol= 0.01
Critical Tol= 0.01
Num of Std Step Trials= 20
Max Error Tol= 0.3
Flow Tol Ratio= 0.001
Split Flow NTrial= 30
Split Flow Tol= 0.02
Split Flow Ratio= 0.02
Log Output Level= 0
Friction Slope Method= 1
Unsteady Friction Slope Method= 2
Unsteady Bridges Friction Slope Method= 1
Parabolic Critical Depth
Global Vel Dist=  1 , 1 , 1
Global Log Level= 0
CheckData=True
Encroach Param= -1, 0, 0, 0
BEGIN DESCRIPTION:
Multiple Run
END DESCRIPTION:

--- Bear Creek Tributary 7.f01 (steady flow) ---

Flow Title=Multiple
Number of Profiles=7
Profile Names=10-year,25-year,50-year,1pct_min,100-year,1pct_plu,500-year
River Rch & RM= Bear Creek Tribu,Reach-1,4525
     545     885    1194     782    1561    3114    2637
River Rch & RM= Bear Creek Tribu,Reach-1,1003
     782    1299    1780    1183    2361    4710    4105
Boundary for River Rch & Prof#=Bear Creek Tribu,Reach-1,1
Up Type=0
Dn Type=3
Dn Slope=0.005
Boundary for River Rch & Prof#=Bear Creek Tribu,Reach-1,2
Up Type=0
Dn Type=3
Dn Slope=0.005
Boundary for River Rch & Prof#=Bear Creek Tribu,Reach-1,3
Up Type=0
Dn Type=3
Dn Slope=0.005
Boundary for River Rch & Prof#=Bear Creek Tribu,Reach-1,4
Up Type=0
Dn Type=3
Dn Slope=0.005
Boundary for River Rch & Prof#=Bear Creek Tribu,Reach-1,5
Up Type=0
Dn Type=3
Dn Slope=0.005
Boundary for River Rch & Prof#=Bear Creek Tribu,Reach-1,6
Up Type=0
Dn Type=3
Dn Slope=0.005
Boundary for River Rch & Prof#=Bear Creek Tribu,Reach-1,7
Up Type=0
Dn Type=3
Dn Slope=0.005

--- Bear Creek Tributary 7.g01 (geometry) ---

Geom Title=Existing Conditions

River Reach=Bear Creek Tribu,Reach-1
Reach XY= 30
      2184357.65     13792057.65      2184464.25     13792165.31
      2184583.18     13792381.04      2184669.46     13792472.58
      2184677.33     13792569.03      2184733.14     13792681.06
      2184865.20     13792814.52      2185123.45     13792828.75
      2185238.56     13792888.48      2185301.17     13793002.13
      2185381.02     13793033.18      2185472.71     13793119.16
      2185585.50     13793173.80      2185819.07     13793177.29
      2185885.71     13793224.28      2186138.21     13793061.37
      2186368.94     13792833.14      2186531.05     13792766.84
      2186772.57     13792580.51      2186873.59     13792571.61
      2186925.00     13792525.00      2187021.74     13792567.01
      2187074.90     13792532.77      2187135.43     13792573.62
      2187319.06     13792577.26      2187385.51     13792623.78
      2187569.06     13792627.26      2187795.10     13792725.10
      2187877.45     13792719.67      2187975.00     13792625.00

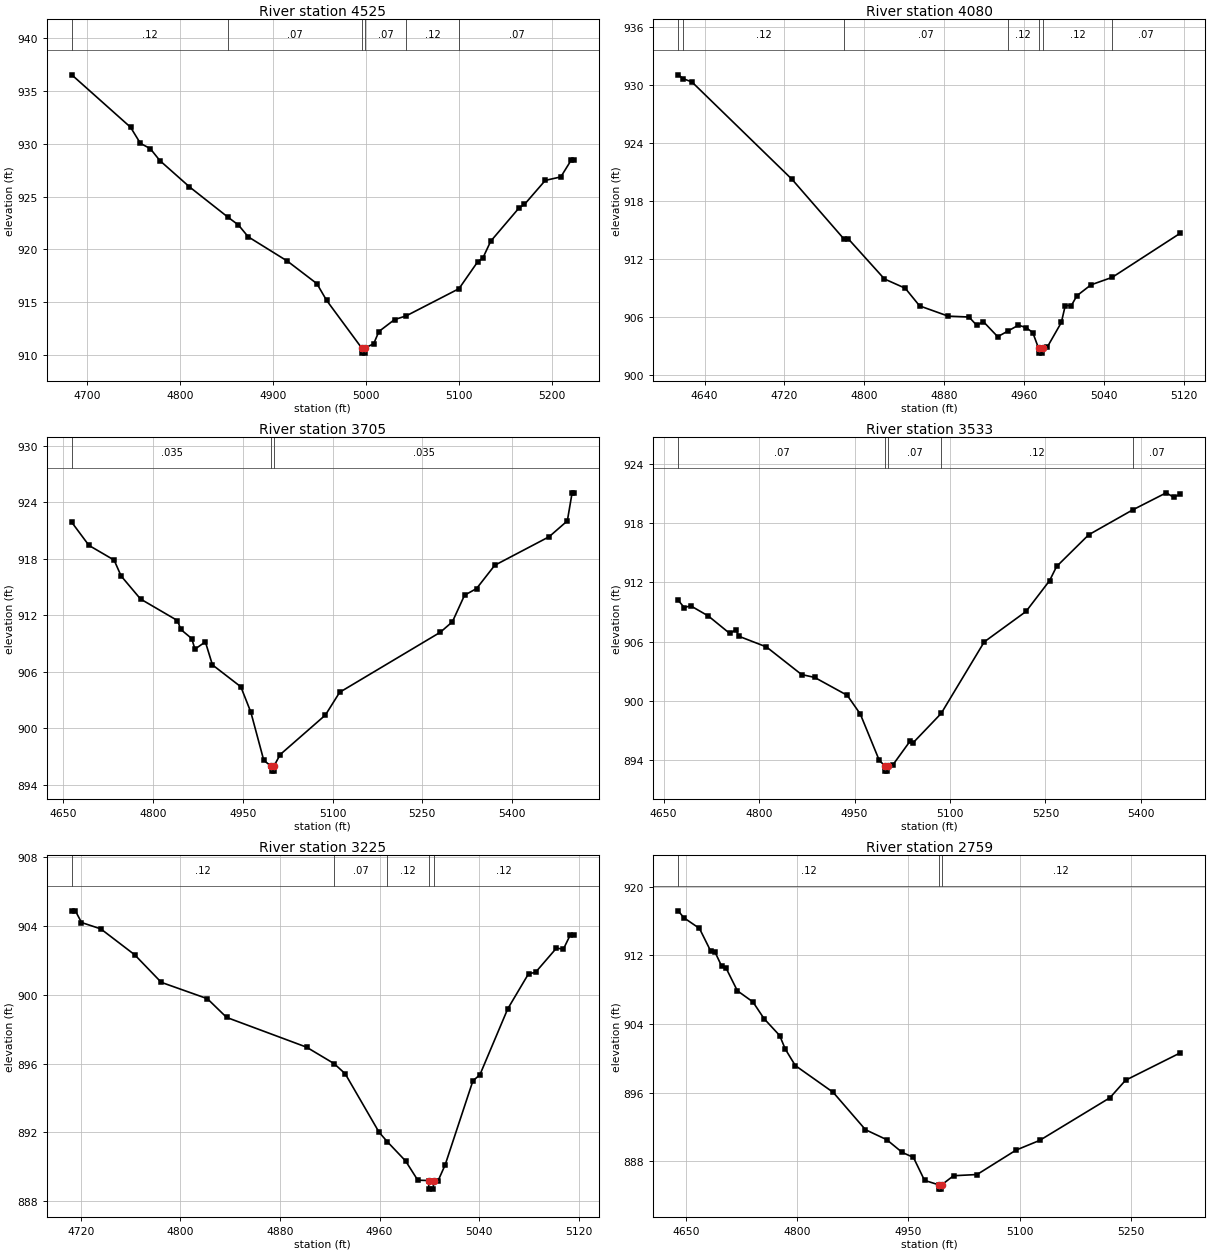
Type RM Length L Ch R = 1,4525,445,445,445
BEGIN DESCRIPTION:
Bear Creek Tributary 7 10.0
END DESCRIPTION:
XS GIS Cut Line= 3
      2184125.02     13792224.99      2184425.00     13792125.00
      2184524.99     13791925.01
#Sta/Elev= 30
  4683.5  936.55  4746.7  931.58  4757.3  930.05  4767.8  929.56  4778.3  928.41
  4810.0  925.93  4851.3  923.06  4862.7  922.31  4873.2  921.19  4915.4  918.88
  4947.0  916.75  4957.5  915.16  4995.1  910.66  4995.3  910.16  4998.8  910.16
  4999.1  910.66  5008.1  911.05  5013.7  912.21  5030.5  913.34  5043.0  913.69
  5099.8  916.27  5119.9  918.82  5125.5  919.18  5133.9  920.77  5164.6  923.95
  5170.2  924.26  5192.6  926.54  5209.3  926.87  5220.5  928.47  5223.3  928.47
#Mann=6,-1,0
  4683.5    0.12       0  4851.3    0.07       0  4995.1    0.05       0
  4999.1    0.07       0  5043.0    0.12       0  5099.8    0.07       0
Bank Sta=4995.1,4999.1
Exp/Cntr=0.3,0.1

Type RM Length L Ch R = 1,4080,375,375,375
BEGIN DESCRIPTION:
Bear Creek Tributary 7 9.0
END DESCRIPTION:
XS GIS Cut Line= 3
      2184375.01     13792724.99      2184675.00     13792475.00
      2184725.00     13792375.00
#Sta/Elev= 30
  4613.7  931.09  4618.9  930.68  4627.4  930.35  4727.6  920.26  4779.8  914.05
  4783.6  914.13  4820.0  909.95  4840.8  908.99  4855.2  907.16  4883.8  906.10
  4904.6  906.01  4912.4  905.14  4918.9  905.54  4933.3  903.97  4943.6  904.56
  4954.1  905.17  4961.9  904.90  4968.4  904.40  4974.2  902.77  4974.5  902.27
  4978.0  902.27  4978.2  902.77  4982.7  902.86  4997.0  905.45  5000.9  907.20
  5007.0  907.20  5012.6  908.22  5026.6  909.34  5047.9  910.12  5116.0  914.69
#Mann=7,-1,0
  4613.7   0.035       0  4618.9    0.12       0  4779.8    0.07       0
  4943.6    0.12       0  4974.2    0.05       0  4978.2    0.12       0
  5047.9    0.07       0
Bank Sta=4974.2,4978.2
Exp/Cntr=0.3,0.1

Type RM Length L Ch R = 1,3705,172,172,172
BEGIN DESCRIPTION:
Bear Creek Tributary 7 8.0
END DESCRIPTION:
XS GIS Cut Line= 3
      2184710.76     13793100.94      2184845.70     13792779.38
      2184917.47     13792294.19
#Sta/Elev= 30
  4664.2  921.87  4692.9  919.42  4735.0  917.86  4746.6  916.18  4779.1  913.73
  4840.9  911.44  4846.4  910.50  4864.7  909.53  4870.1  908.41  4887.5  909.18
  4899.3  906.74  4946.8  904.41  4963.5  901.72  4985.1  896.61  4997.8  895.96
  4998.1  895.46  5001.6  895.46  5001.8  895.96  5012.6  897.22  5088.1  901.41
  5112.0  903.83  5280.2  910.20  5300.4  911.31  5320.7  914.13  5340.8  914.84
  5371.2  917.31  5462.1  920.34  5492.5  922.02  5500.5  925.00  5503.4  925.00
#Mann=3,-1,0
  4664.2   0.035       0  4997.8   0.035       0  5001.8   0.035       0
Bank Sta=4997.8,5001.8
Exp/Cntr=0.3,0.1

Type RM Length L Ch R = 1,3533,308,308,308
BEGIN DESCRIPTION:
X18150
END DESCRIPTION:
XS GIS Cut Line= 2
      2184928.97     13793143.94      2185104.07     13792374.62
#Sta/Elev= 30
  4672.9  910.18  4682.4  909.44  4692.3  909.63  4720.3  908.59  4753.9  906.83
  4763.3  907.20  4768.5  906.54  4811.5  905.47  4866.7  902.68  4887.2  902.39
  4938.5  900.58  4959.0  898.69  4988.8  894.01  4998.0  893.42  4998.2  892.92
  5001.7  892.92  5002.0  893.42  5010.3  893.56  5037.0  895.93  5042.1  895.79
  5086.1  898.75  5153.8  905.98  5219.4  909.05  5256.4  912.16  5267.5  913.60
  5317.9  916.80  5386.9  919.31  5439.7  921.04  5451.3  920.60  5461.9  920.90
#Mann=5,-1,0
  4672.9    0.07       0  4998.0    0.05       0  5002.0    0.07       0
  5086.1    0.12       0  5386.9    0.07       0
Bank Sta=4998,5002
Exp/Cntr=0.3,0.1

Type RM Length L Ch R = 1,3225,466,466,466
BEGIN DESCRIPTION:
Bear Creek Tributary 7 7.0
END DESCRIPTION:
XS GIS Cut Line= 3
      2185024.98     13793075.01      2185275.00     13792925.00
      2185325.01     13792824.98
#Sta/Elev= 30
  4712.7  904.89  4715.6  904.89  4720.5  904.21  4736.0  903.84  4763.3  902.33
  4784.6  900.73  4821.6  899.78  4837.1  898.69  4901.3  896.96  4923.5  896.00
  4932.4  895.41  4959.6  892.01  4966.2  891.46  4980.9  890.34  4990.7  889.22
  4999.4  889.20  4999.6  888.70  5003.1  888.70  5003.4  889.20  5007.1  889.20
  5012.7  890.11  5035.0  895.00  5040.6  895.35  5063.0  899.19  5079.7  901.23
  5085.3  901.31  5102.1  902.72  5107.7  902.66  5113.3  903.50  5116.1  903.50
#Mann=5,-1,0
  4712.7    0.12       0  4923.5    0.07       0  4966.2    0.12       0
  4999.4    0.05       0  5003.4    0.12       0
Bank Sta=4999.4,5003.4
Exp/Cntr=0.3,0.1

Type RM Length L Ch R = 1,2759,456,456,456
BEGIN DESCRIPTION:
Bear Creek Tributary 7 6.0
END DESCRIPTION:
XS GIS Cut Line= 3
      2185424.98     13793475.03      2185625.00     13793175.00
      2185525.01     13792875.02
#Sta/Elev= 30
  4639.9  917.18  4647.4  916.38  4668.5  915.13  4683.5  912.52  4689.5  912.37
  4698.5  910.72  4704.5  910.49  4719.6  907.87  4740.6  906.57  4755.6  904.62
  4776.6  902.66  4784.2  901.08  4797.7  899.16  4848.8  896.04  4892.3  891.69
  4920.9  890.53  4941.9  889.04  4956.9  888.47  4971.9  885.79  4991.0  885.27
  4991.2  884.77  4994.7  884.77  4995.0  885.27  5011.0  886.33  5042.7  886.47
  5095.4  889.32  5127.0  890.44  5221.8  895.41  5242.9  897.45  5316.7  900.64
#Mann=3,-1,0
  4639.9    0.12       0  4991.0    0.05       0  4995.0    0.12       0
Bank Sta=4991,4995
Exp/Cntr=0.3,0.1

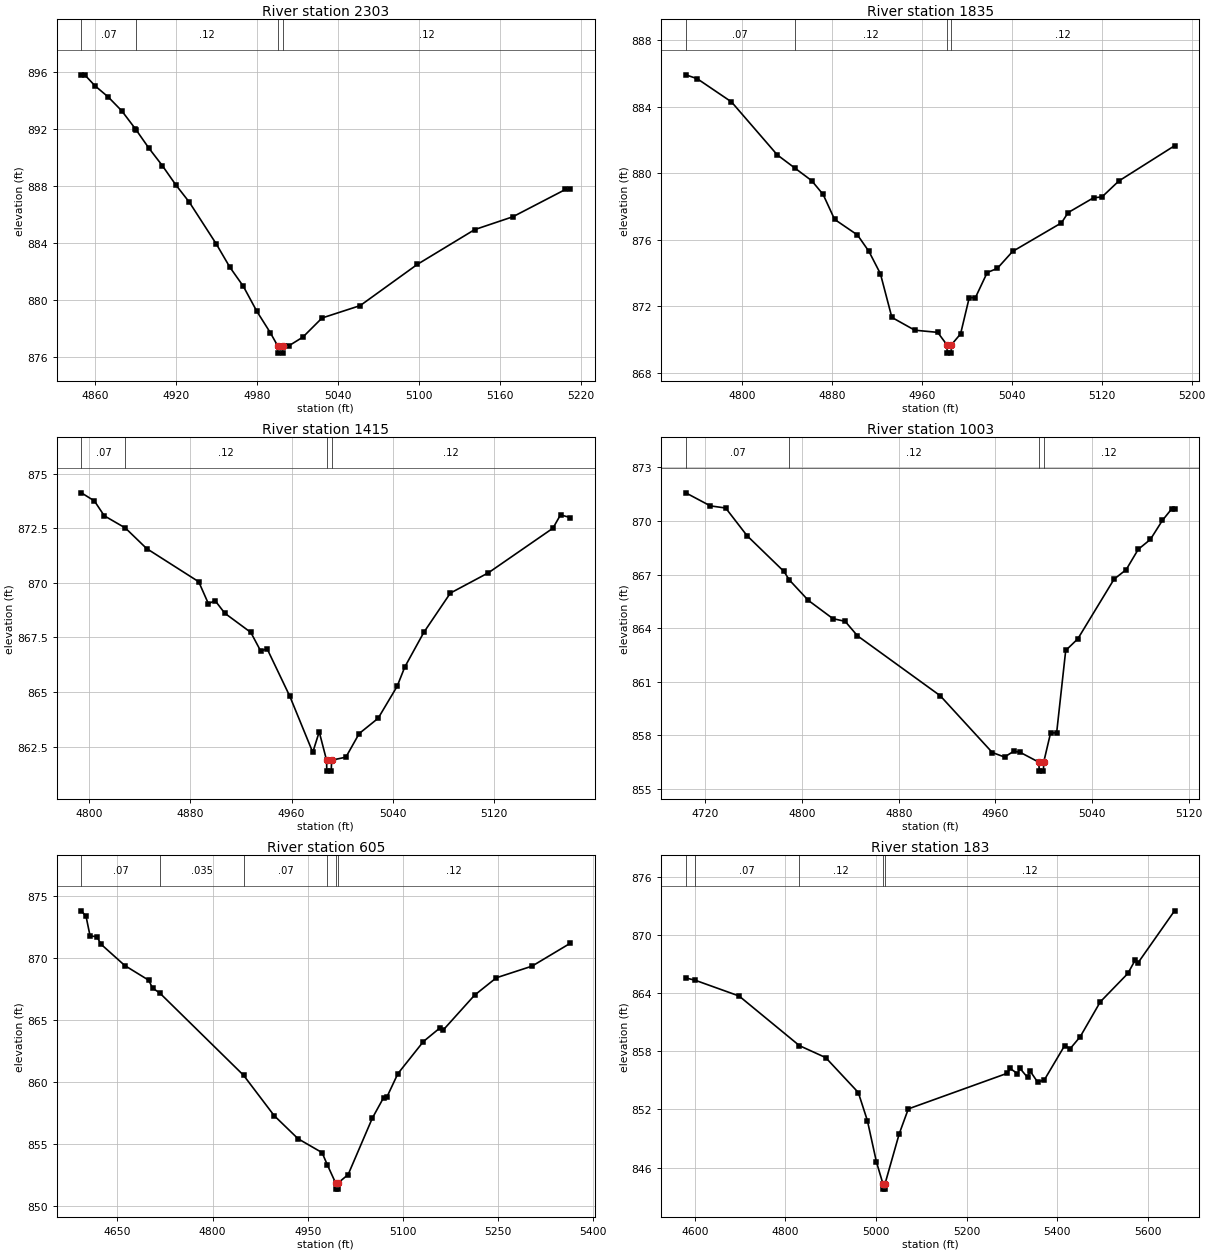
Type RM Length L Ch R = 1,2303,468,468,468
BEGIN DESCRIPTION:
Bear Creek Tributary 7 5.0
END DESCRIPTION:
XS GIS Cut Line= 3
      2186025.00     13793274.99      2186025.00     13793125.00
      2185875.02     13792975.02
#Sta/Elev= 30
  4849.8  895.78  4852.3  895.78  4859.8  895.02  4869.8  894.22  4879.8  893.25
  4889.8  892.00  4890.4  891.92  4899.8  890.65  4909.8  889.42  4919.8  888.07
  4929.8  886.86  4949.8  883.93  4959.8  882.31  4969.8  880.97  4979.8  879.22
  4989.8  877.72  4995.3  876.79  4995.5  876.29  4999.0  876.29  4999.3  876.79
  4999.8  876.79  5003.3  876.79  5013.9  877.41  5028.1  878.75  5056.4  879.62
  5098.8  882.51  5141.2  884.94  5169.5  885.84  5208.4  887.75  5211.9  887.75
#Mann=4,-1,0
  4849.8    0.07       0  4890.4    0.12       0  4995.3    0.05       0
  4999.3    0.12       0
Bank Sta=4995.3,4999.3
Exp/Cntr=0.3,0.1

Type RM Length L Ch R = 1,1835,420,420,420
BEGIN DESCRIPTION:
Bear Creek Tributary 7 4.0
END DESCRIPTION:
XS GIS Cut Line= 3
      2186424.99     13793074.95      2186375.00     13792825.00
      2186224.98     13792724.99
#Sta/Elev= 30
  4749.5  885.93  4759.6  885.70  4790.2  884.30  4831.0  881.11  4846.6  880.32
  4861.6  879.56  4871.8  878.73  4882.0  877.23  4902.4  876.29  4912.6  875.30
  4922.8  873.96  4933.0  871.33  4953.4  870.56  4973.8  870.43  4982.0  869.68
  4982.3  869.18  4985.8  869.18  4986.0  869.68  4994.2  870.34  5001.9  872.52
  5007.4  872.52  5017.9  874.03  5026.9  874.28  5040.5  875.30  5084.0  877.02
  5090.0  877.64  5112.6  878.53  5120.1  878.58  5135.1  879.54  5184.7  881.66
#Mann=4,-1,0
  4749.5    0.07       0  4846.6    0.12       0  4982.0    0.05       0
  4986.0    0.12       0
Bank Sta=4982,4986
Exp/Cntr=0.3,0.1

Type RM Length L Ch R = 1,1415,412,412,412
BEGIN DESCRIPTION:
Bear Creek Tributary 7 3.0
END DESCRIPTION:
XS GIS Cut Line= 3
      2186675.00     13792825.02      2186725.00     13792625.00
      2186574.96     13792524.97
#Sta/Elev= 30
  4793.8  874.12  4804.1  873.75  4811.9  873.07  4828.6  872.51  4845.4  871.57
  4886.6  870.05  4894.3  869.04  4899.5  869.19  4907.2  868.61  4927.8  867.73
  4935.6  866.88  4940.7  866.98  4958.7  864.80  4976.8  862.24  4981.9  863.18
  4987.7  861.88  4987.9  861.38  4991.4  861.38  4991.7  861.88  5003.0  862.02
  5013.5  863.10  5028.5  863.80  5043.5  865.26  5049.6  866.15  5064.6  867.73
  5085.6  869.53  5115.7  870.46  5166.7  872.50  5172.7  873.11  5180.3  872.99
#Mann=4,-1,0
  4793.8    0.07       0  4828.6    0.12       0  4987.7    0.05       0
  4991.7    0.12       0
Bank Sta=4987.7,4991.7
Exp/Cntr=0.3,0.1

Type RM Length L Ch R = 1,1003,398,398,398
BEGIN DESCRIPTION:
Bear Creek Tributary 7 2.0
END DESCRIPTION:
XS GIS Cut Line= 3
      2187024.99     13792825.05      2187075.00     13792525.00
      2187075.00     13792424.99
#Sta/Elev= 30
  4703.9  871.57  4724.2  870.84  4736.9  870.72  4754.6  869.17  4785.1  867.17
  4789.6  866.69  4805.3  865.55  4825.6  864.53  4835.7  864.38  4845.9  863.57
  4914.3  860.22  4957.4  857.04  4967.5  856.79  4975.1  857.11  4980.2  857.06
  4995.9  856.50  4996.2  856.00  4999.7  856.00  4999.9  856.50  5005.6  858.14
  5010.6  858.14  5018.1  862.75  5028.1  863.40  5058.1  866.74  5068.1  867.27
  5078.1  868.41  5088.1  868.96  5098.1  870.03  5105.6  870.66  5108.1  870.66
#Mann=4,-1,0
  4703.9    0.07       0  4789.6    0.12       0  4995.9    0.05       0
  4999.9    0.12       0
Bank Sta=4995.9,4999.9
Exp/Cntr=0.3,0.1

Type RM Length L Ch R = 1,605,422,422,422
BEGIN DESCRIPTION:
X18149
END DESCRIPTION:
XS GIS Cut Line= 3
      2187277.36     13792997.58      2187446.75     13792612.86
      2187406.55     13792265.44
#Sta/Elev= 30
  4593.2  873.83  4600.6  873.38  4606.9  871.81  4617.9  871.73  4624.0  871.14
  4661.6  869.41  4699.4  868.22  4705.3  867.59  4716.5  867.20  4848.8  860.54
  4897.0  857.28  4934.7  855.41  4972.5  854.29  4980.7  853.31  4993.8  851.84
  4994.1  851.34  4997.6  851.34  4997.8  851.84  5013.6  852.52  5051.7  857.08
  5069.5  858.74  5074.6  858.78  5091.9  860.67  5132.2  863.27  5158.3  864.37
  5163.4  864.20  5212.7  867.01  5247.1  868.42  5303.3  869.36  5363.3  871.20
#Mann=6,-1,0
  4593.2    0.07       0  4716.5   0.035       0  4848.8    0.07       0
  4980.7    0.12       0  4993.8    0.05       0  4997.8    0.12       0
Bank Sta=4993.8,4997.8
Exp/Cntr=0.3,0.1

Type RM Length L Ch R = 1,183,0,0,0
BEGIN DESCRIPTION:
Bear Creek Tributary 7 1.0
END DESCRIPTION:
XS GIS Cut Line= 4
      2187573.06     13793029.16      2187837.20     13792787.99
      2187814.23     13792529.61      2187602.02     13792119.53
#Sta/Elev= 30
  4579.9  865.56  4600.3  865.33  4697.5  863.70  4830.8  858.58  4888.7  857.35
  4960.7  853.75  4980.7  850.86  5000.8  846.58  5015.4  844.29  5015.6  843.79
  5019.1  843.79  5019.4  844.29  5051.0  849.49  5071.1  852.06  5289.9  855.74
  5295.5  856.24  5312.0  855.70  5317.7  856.23  5334.2  855.31  5339.8  855.97
  5356.3  854.84  5371.1  855.03  5416.1  858.58  5428.4  858.27  5450.5  859.50
  5494.9  863.10  5555.6  866.02  5572.1  867.42  5577.7  867.09  5658.7  872.48
#Mann=5,-1,0
  4579.9   0.035       0  4600.3    0.07       0  4830.8    0.12       0
  5015.4    0.05       0  5019.4    0.12       0
Bank Sta=5015.4,5019.4
Exp/Cntr=0.3,0.1

Chan Stop Cuts=-1