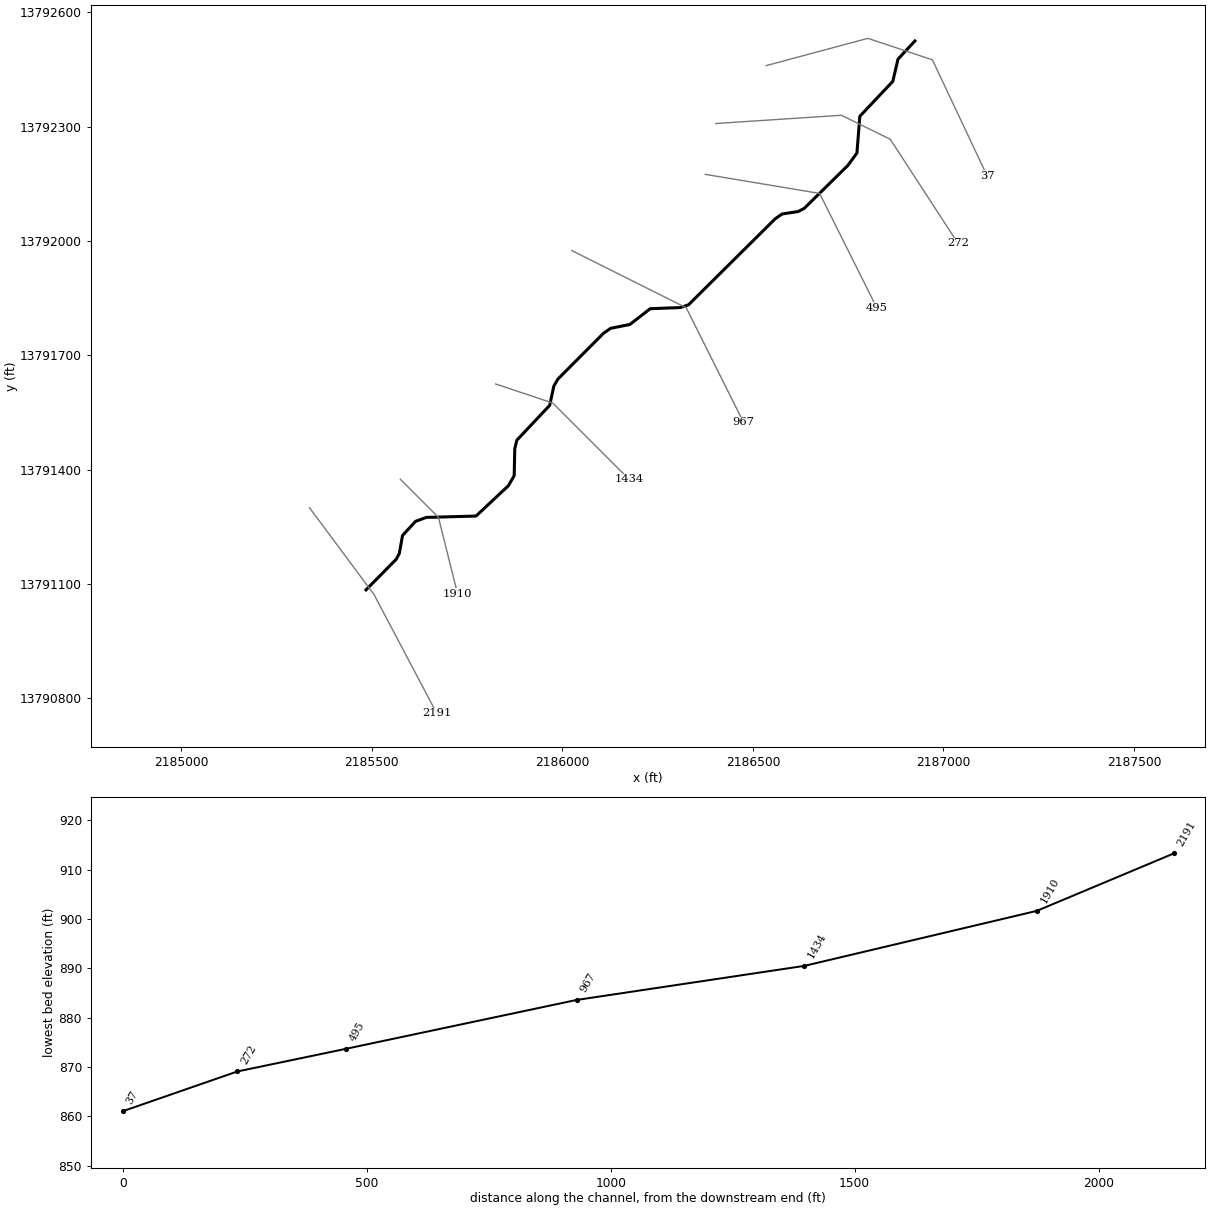
--- Bear Creek Tributary 8.prj (project) ---

Proj Title=Bear Creek Tributary 8 Base Level Engineering
Current Plan=p01
Default Exp/Contr=0.3,0.1
English Units
Geom File=g01
Flow File=f01
Plan File=p01
BEGIN DESCRIPTION:
Bear Creek Tributary 8
END DESCRIPTION:

--- Bear Creek Tributary 8.p01 (plan) ---

Plan Title=Multiple Run
Short Identifier=Multiple
Geom File=g01
Flow File=f01
Subcritical Flow
K Sum by GR= 0
Std Step Tol= 0.01
Critical Tol= 0.01
Num of Std Step Trials= 20
Max Error Tol= 0.3
Flow Tol Ratio= 0.001
Split Flow NTrial= 30
Split Flow Tol= 0.02
Split Flow Ratio= 0.02
Log Output Level= 0
Friction Slope Method= 1
Unsteady Friction Slope Method= 2
Unsteady Bridges Friction Slope Method= 1
Parabolic Critical Depth
Global Vel Dist=  1 , 1 , 1
Global Log Level= 0
CheckData=True
Encroach Param= -1, 0, 0, 0
BEGIN DESCRIPTION:
Multiple Run
END DESCRIPTION:

--- Bear Creek Tributary 8.f01 (steady flow) ---

Flow Title=Multiple
Number of Profiles=7
Profile Names=10-year,25-year,50-year,1pct_min,100-year,1pct_plu,500-year
River Rch & RM= Bear Creek Tribu,Reach-1,2191
     381     606     809     525    1047    2090    1734
Boundary for River Rch & Prof#=Bear Creek Tribu,Reach-1,1
Up Type=0
Dn Type=3
Dn Slope=0.005
Boundary for River Rch & Prof#=Bear Creek Tribu,Reach-1,2
Up Type=0
Dn Type=3
Dn Slope=0.005
Boundary for River Rch & Prof#=Bear Creek Tribu,Reach-1,3
Up Type=0
Dn Type=3
Dn Slope=0.005
Boundary for River Rch & Prof#=Bear Creek Tribu,Reach-1,4
Up Type=0
Dn Type=3
Dn Slope=0.005
Boundary for River Rch & Prof#=Bear Creek Tribu,Reach-1,5
Up Type=0
Dn Type=3
Dn Slope=0.005
Boundary for River Rch & Prof#=Bear Creek Tribu,Reach-1,6
Up Type=0
Dn Type=3
Dn Slope=0.005
Boundary for River Rch & Prof#=Bear Creek Tribu,Reach-1,7
Up Type=0
Dn Type=3
Dn Slope=0.005

--- Bear Creek Tributary 8.g01 (geometry) ---

Geom Title=Existing Conditions

River Reach=Bear Creek Tribu,Reach-1
Reach XY= 30
      2185484.77     13791084.77      2185564.31     13791165.30
      2185572.36     13791180.67      2185580.72     13791227.59
      2185614.88     13791264.65      2185643.12     13791274.94
      2185773.54     13791278.54      2185858.56     13791358.21
      2185873.69     13791384.63      2185875.14     13791454.94
      2185880.54     13791477.42      2185966.82     13791568.96
      2185977.64     13791619.36      2185988.63     13791638.21
      2186108.32     13791758.36      2186126.63     13791771.06
      2186177.17     13791781.14      2186230.56     13791822.55
      2186309.78     13791825.52      2186331.17     13791832.86
      2186558.33     13792058.35      2186576.65     13792071.02
      2186618.95     13792077.53      2186634.68     13792085.78
      2186748.82     13792198.13      2186772.85     13792230.89
      2186780.54     13792327.42      2186866.93     13792418.92
      2186880.70     13792477.35      2186925.00     13792525.00

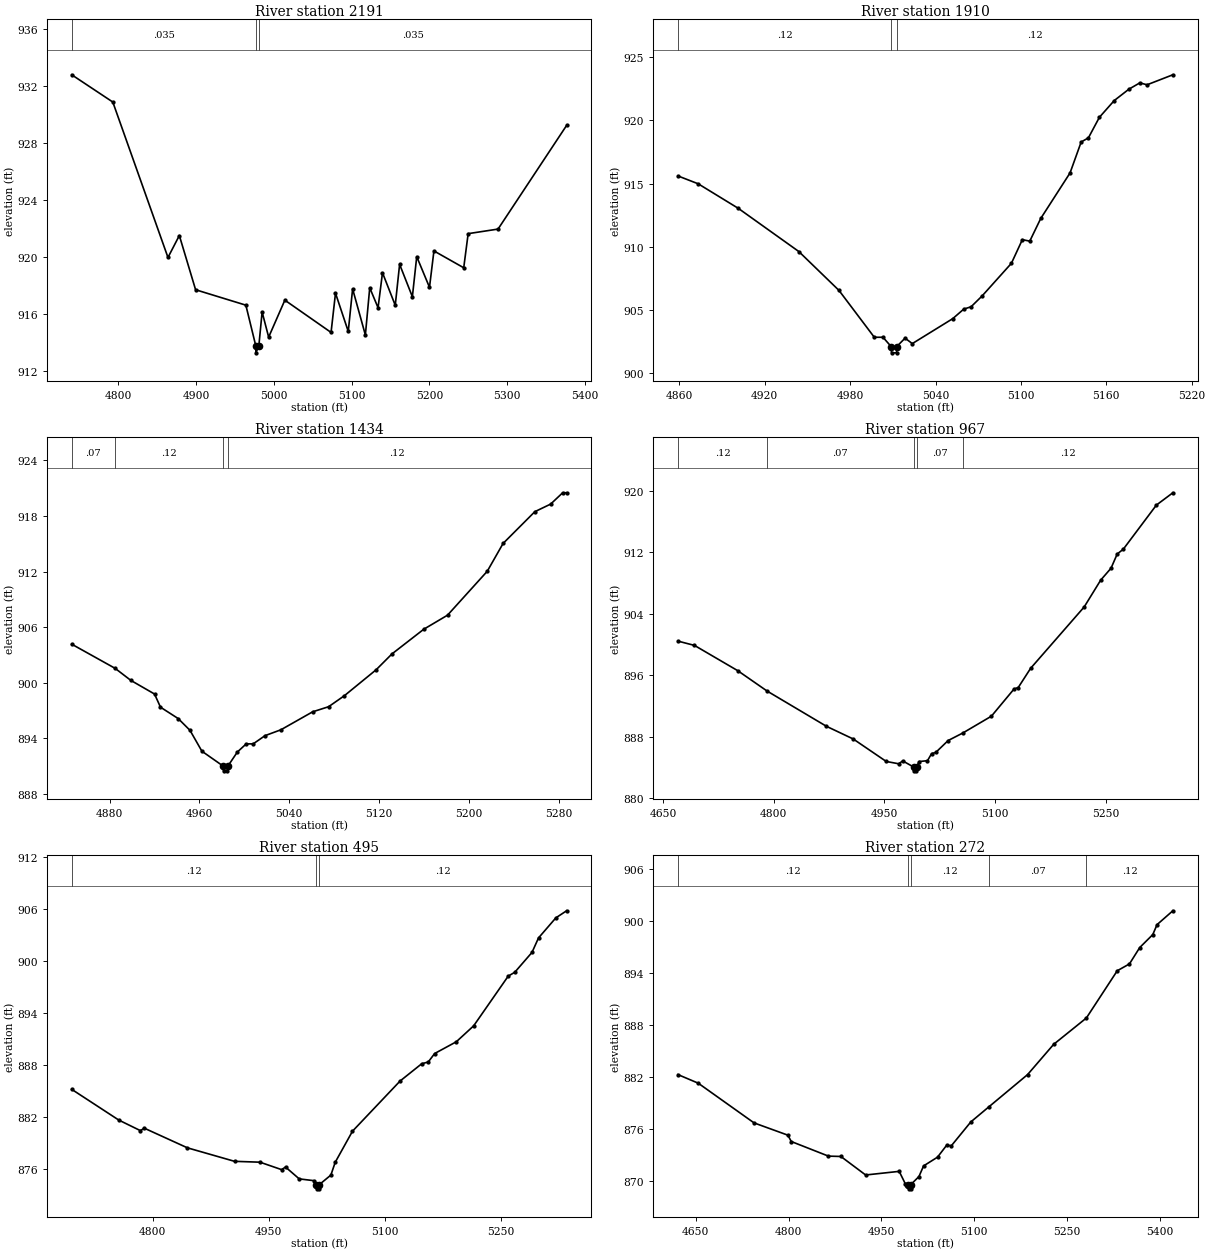
Type RM Length L Ch R = 1,2191,281,281,281
BEGIN DESCRIPTION:
X18153
END DESCRIPTION:
XS GIS Cut Line= 3
      2185336.83     13791300.11      2185506.10     13791072.25
      2185670.47     13790760.82
#Sta/Elev= 30
  4740.3  932.76  4793.1  930.85  4864.0  919.96  4878.6  921.50  4899.5  917.70
  4964.1  916.62  4976.8  913.78  4977.0  913.28  4980.8  913.78  4985.0  916.14
  4993.4  914.38  5014.2  916.97  5073.6  914.71  5079.3  917.46  5095.7  914.78
  5101.3  917.76  5117.7  914.53  5123.3  917.84  5134.0  916.44  5139.7  918.89
  5156.1  916.61  5161.7  919.48  5178.1  917.21  5183.7  920.02  5200.1  917.87
  5205.8  920.42  5244.1  919.24  5249.8  921.63  5288.2  921.95  5376.3  929.21
#Mann=3,-1,0
  4740.3   0.035       0  4976.8   0.035       0  4980.8   0.035       0
Bank Sta=4976.8,4980.8
Exp/Cntr=0.3,0.1

Type RM Length L Ch R = 1,1910,476,476,476
BEGIN DESCRIPTION:
Bear Creek Tributary 8 4.0
END DESCRIPTION:
XS GIS Cut Line= 3
      2185574.99     13791375.01      2185675.00     13791275.00
      2185725.00     13791074.99
#Sta/Elev= 30
  4859.1  915.60  4873.3  914.98  4901.5  913.04  4944.0  909.63  4972.2  906.56
  4997.0  902.86  5003.1  902.86  5008.8  902.13  5009.1  901.63  5012.6  901.63
  5012.8  902.13  5018.6  902.79  5023.7  902.36  5052.1  904.33  5059.8  905.08
  5065.0  905.27  5072.7  906.12  5093.3  908.70  5101.0  910.57  5106.2  910.45
  5113.9  912.24  5134.5  915.84  5142.3  918.28  5147.4  918.61  5155.1  920.23
  5165.5  921.55  5175.8  922.45  5183.5  922.95  5188.6  922.80  5206.7  923.59
#Mann=3,-1,0
  4859.1    0.12       0  5008.8    0.05       0  5012.8    0.12       0
Bank Sta=5008.8,5012.8
Exp/Cntr=0.3,0.1

Type RM Length L Ch R = 1,1434,467,467,467
BEGIN DESCRIPTION:
Bear Creek Tributary 8 3.0
END DESCRIPTION:
XS GIS Cut Line= 3
      2185824.97     13791625.01      2185975.00     13791575.00
      2186175.01     13791374.99
#Sta/Elev= 30
  4846.2  904.16  4884.9  901.55  4898.9  900.25  4920.0  898.78  4925.3  897.36
  4941.1  896.13  4951.6  894.86  4962.2  892.61  4981.3  890.99  4981.5  890.49
  4985.0  890.49  4985.3  890.99  4993.8  892.52  5001.7  893.40  5007.9  893.40
  5018.5  894.29  5032.6  894.92  5060.9  896.86  5075.1  897.41  5089.2  898.60
  5117.5  901.40  5131.6  903.11  5159.9  905.77  5181.1  907.29  5216.5  912.03
  5230.6  915.03  5258.9  918.46  5273.0  919.28  5283.7  920.50  5287.2  920.50
#Mann=4,-1,0
  4846.2    0.07       0  4884.9    0.12       0  4981.3    0.05       0
  4985.3    0.12       0
Bank Sta=4981.3,4985.3
Exp/Cntr=0.3,0.1

Type RM Length L Ch R = 1,967,472,472,472
BEGIN DESCRIPTION:
Bear Creek Tributary 8 2.0
END DESCRIPTION:
XS GIS Cut Line= 3
      2186024.99     13791975.00      2186325.00     13791825.00
      2186474.99     13791525.02
#Sta/Elev= 30
  4670.1  900.45  4692.5  899.89  4751.2  896.60  4791.0  893.95  4871.4  889.37
  4907.7  887.72  4952.4  884.80  4969.2  884.50  4974.8  884.87  4989.5  884.08
  4989.8  883.58  4993.3  883.58  4993.5  884.08  4997.1  884.79  5008.3  884.90
  5013.9  885.82  5019.5  885.97  5036.3  887.52  5056.2  888.50  5095.0  890.69
  5125.7  894.23  5131.3  894.41  5148.1  896.91  5220.7  904.89  5243.1  908.38
  5257.1  909.93  5265.5  911.78  5273.8  912.41  5318.6  918.14  5340.9  919.74
#Mann=5,-1,0
  4670.1    0.12       0  4791.0    0.07       0  4989.5    0.05       0
  4993.5    0.07       0  5056.2    0.12       0
Bank Sta=4989.5,4993.5
Exp/Cntr=0.3,0.1

Type RM Length L Ch R = 1,495,223,223,223
BEGIN DESCRIPTION:
Bear Creek Tributary 8 1.0
END DESCRIPTION:
XS GIS Cut Line= 3
      2186375.01     13792175.00      2186675.00     13792125.00
      2186824.98     13791825.04
#Sta/Elev= 30
  4695.6  885.19  4756.4  881.64  4784.3  880.42  4789.4  880.70  4845.1  878.43
  4906.0  876.87  4938.9  876.77  4966.8  875.91  4971.9  876.21  4989.6  874.84
  5008.1  874.64  5011.7  874.19  5012.0  873.69  5015.5  873.69  5015.7  874.19
  5030.5  875.28  5036.1  876.76  5058.4  880.35  5119.9  886.15  5147.9  888.15
  5156.3  888.35  5164.6  889.33  5192.6  890.69  5215.0  892.53  5259.7  898.28
  5268.1  898.72  5290.4  901.02  5298.8  902.69  5321.2  905.01  5335.1  905.83
#Mann=3,-1,0
  4695.6    0.12       0  5011.7    0.05       0  5015.7    0.12       0
Bank Sta=5011.7,5015.7
Exp/Cntr=0.3,0.1

Type RM Length L Ch R = 1,272,235,235,235
BEGIN DESCRIPTION:
X18152
END DESCRIPTION:
XS GIS Cut Line= 4
      2186402.40     13792308.36      2186732.23     13792330.06
      2186860.27     13792267.13      2187038.25     13791993.65
#Sta/Elev= 30
  4621.3  882.29  4654.0  881.30  4744.2  876.71  4798.9  875.29  4804.3  874.56
  4864.4  872.87  4884.5  872.83  4924.5  870.69  4978.7  871.11  4988.4  869.70
  4993.6  869.59  4993.9  869.09  4997.4  869.09  4997.6  869.59  5010.6  870.51
  5018.1  871.74  5040.6  872.75  5055.2  874.11  5063.1  874.08  5094.4  876.82
  5123.5  878.56  5186.1  882.29  5228.3  885.79  5281.1  888.83  5331.0  894.29
  5350.7  895.08  5367.3  896.97  5388.4  898.47  5395.3  899.62  5420.8  901.22
#Mann=5,-1,0
  4621.3    0.12       0  4993.6    0.05       0  4997.6    0.12       0
  5123.5    0.07       0  5281.1    0.12       0
Bank Sta=4993.6,4997.6
Exp/Cntr=0.3,0.1

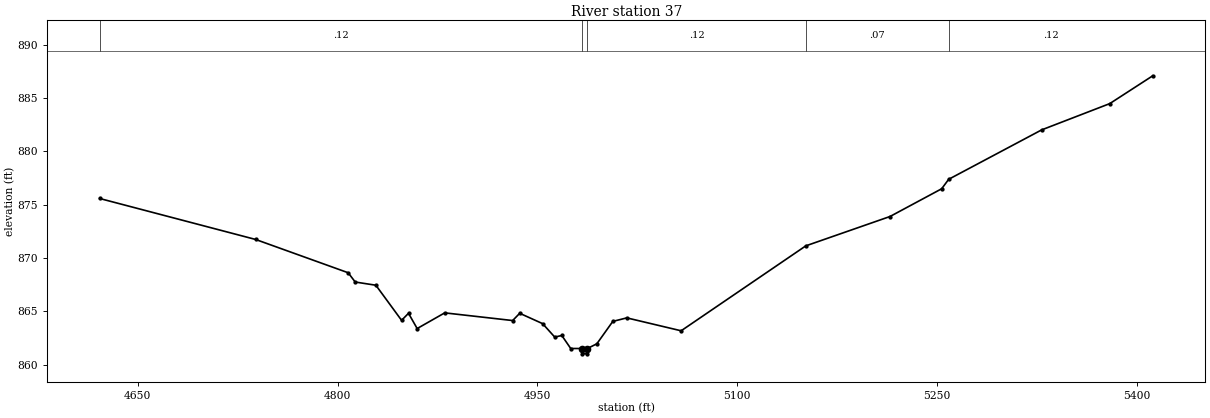
Type RM Length L Ch R = 1,37,0,0,0
BEGIN DESCRIPTION:
X18151
END DESCRIPTION:
XS GIS Cut Line= 4
      2186534.73     13792460.26      2186801.67     13792531.88
      2186970.94     13792475.46      2187114.17     13792171.64
#Sta/Elev= 30
  4621.3  875.59  4738.4  871.75  4807.9  868.63  4813.2  867.76  4828.7  867.46
  4848.0  864.17  4853.2  864.83  4859.7  863.40  4880.4  864.87  4931.4  864.15
  4936.7  864.83  4953.9  863.86  4963.0  862.60  4968.3  862.75  4975.0  861.53
  4983.5  861.53  4983.8  861.03  4987.3  861.03  4987.5  861.53  4994.6  861.97
  5006.6  864.07  5017.1  864.40  5057.9  863.19  5151.5  871.15  5214.7  873.90
  5253.5  876.50  5258.8  877.39  5328.6  882.02  5379.7  884.48  5412.0  887.09
#Mann=5,-1,0
  4621.3    0.12       0  4983.5    0.05       0  4987.5    0.12       0
  5151.5    0.07       0  5258.8    0.12       0
Bank Sta=4983.5,4987.5
Exp/Cntr=0.3,0.1

Chan Stop Cuts=-1