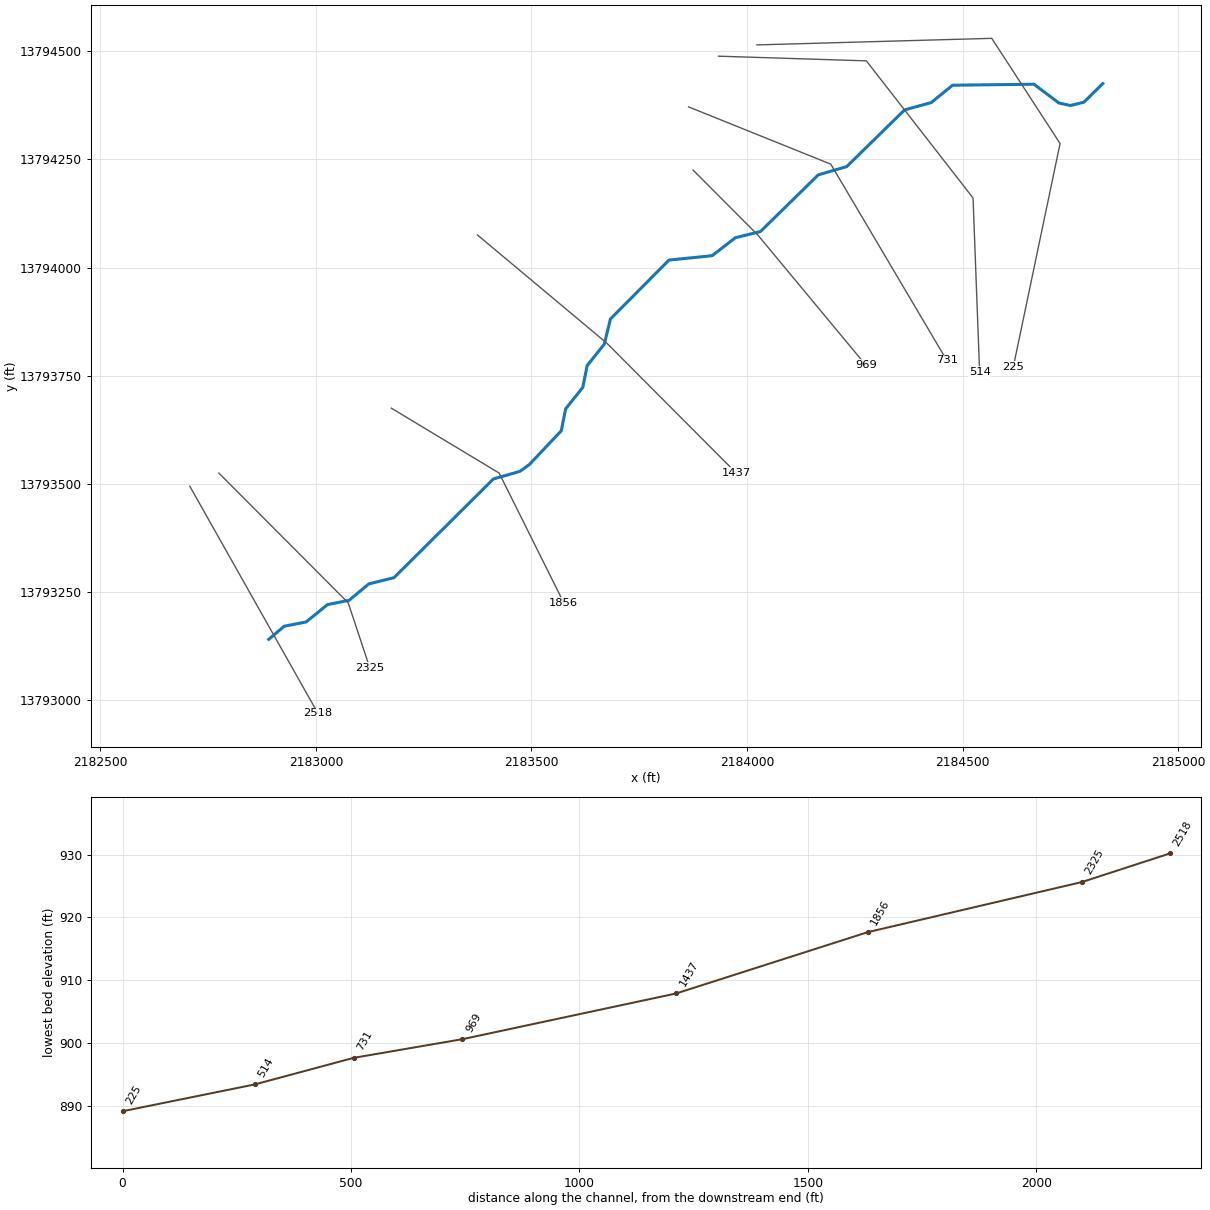
--- Bear Creek Tributary 9.prj (project) ---

Proj Title=Bear Creek Tributary 9 Base Level Engineering
Current Plan=p01
Default Exp/Contr=0.3,0.1
English Units
Geom File=g01
Flow File=f01
Plan File=p01
BEGIN DESCRIPTION:
Bear Creek Tributary 9
END DESCRIPTION:

--- Bear Creek Tributary 9.p01 (plan) ---

Plan Title=Multiple Run
Short Identifier=Multiple
Geom File=g01
Flow File=f01
Subcritical Flow
K Sum by GR= 0
Std Step Tol= 0.01
Critical Tol= 0.01
Num of Std Step Trials= 20
Max Error Tol= 0.3
Flow Tol Ratio= 0.001
Split Flow NTrial= 30
Split Flow Tol= 0.02
Split Flow Ratio= 0.02
Log Output Level= 0
Friction Slope Method= 1
Unsteady Friction Slope Method= 2
Unsteady Bridges Friction Slope Method= 1
Parabolic Critical Depth
Global Vel Dist=  1 , 1 , 1
Global Log Level= 0
CheckData=True
Encroach Param= -1, 0, 0, 0
BEGIN DESCRIPTION:
Multiple Run
END DESCRIPTION:

--- Bear Creek Tributary 9.f01 (steady flow) ---

Flow Title=Multiple
Number of Profiles=7
Profile Names=10-year,25-year,50-year,1pct_min,100-year,1pct_plu,500-year
River Rch & RM= Bear Creek Tribu,Reach-1,2518
     344     542     717     462     921    1838    1500
Boundary for River Rch & Prof#=Bear Creek Tribu,Reach-1,1
Up Type=0
Dn Type=3
Dn Slope=0.005
Boundary for River Rch & Prof#=Bear Creek Tribu,Reach-1,2
Up Type=0
Dn Type=3
Dn Slope=0.005
Boundary for River Rch & Prof#=Bear Creek Tribu,Reach-1,3
Up Type=0
Dn Type=3
Dn Slope=0.005
Boundary for River Rch & Prof#=Bear Creek Tribu,Reach-1,4
Up Type=0
Dn Type=3
Dn Slope=0.005
Boundary for River Rch & Prof#=Bear Creek Tribu,Reach-1,5
Up Type=0
Dn Type=3
Dn Slope=0.005
Boundary for River Rch & Prof#=Bear Creek Tribu,Reach-1,6
Up Type=0
Dn Type=3
Dn Slope=0.005
Boundary for River Rch & Prof#=Bear Creek Tribu,Reach-1,7
Up Type=0
Dn Type=3
Dn Slope=0.005

--- Bear Creek Tributary 9.g01 (geometry) ---

Geom Title=Existing Conditions

River Reach=Bear Creek Tribu,Reach-1
Reach XY= 30
      2182890.73     13793140.73      2182926.59     13793171.04
      2182977.28     13793180.88      2183026.72     13793220.85
      2183077.20     13793231.08      2183122.81     13793268.90
      2183181.06     13793283.14      2183411.79     13793511.37
      2183473.36     13793528.97      2183495.13     13793544.77
      2183569.17     13793622.69      2183579.19     13793673.26
      2183618.92     13793722.80      2183629.16     13793773.28
      2183668.90     13793822.81      2183683.14     13793881.06
      2183818.83     13794017.14      2183919.03     13794027.33
      2183972.83     13794068.86      2184031.06     13794083.14
      2184165.32     13794214.22      2184231.05     13794233.16
      2184365.32     13794364.24      2184427.17     13794381.14
      2184476.55     13794421.25      2184665.35     13794423.61
      2184722.78     13794380.37      2184749.95     13794374.39
      2184781.15     13794381.95      2184825.00     13794425.00

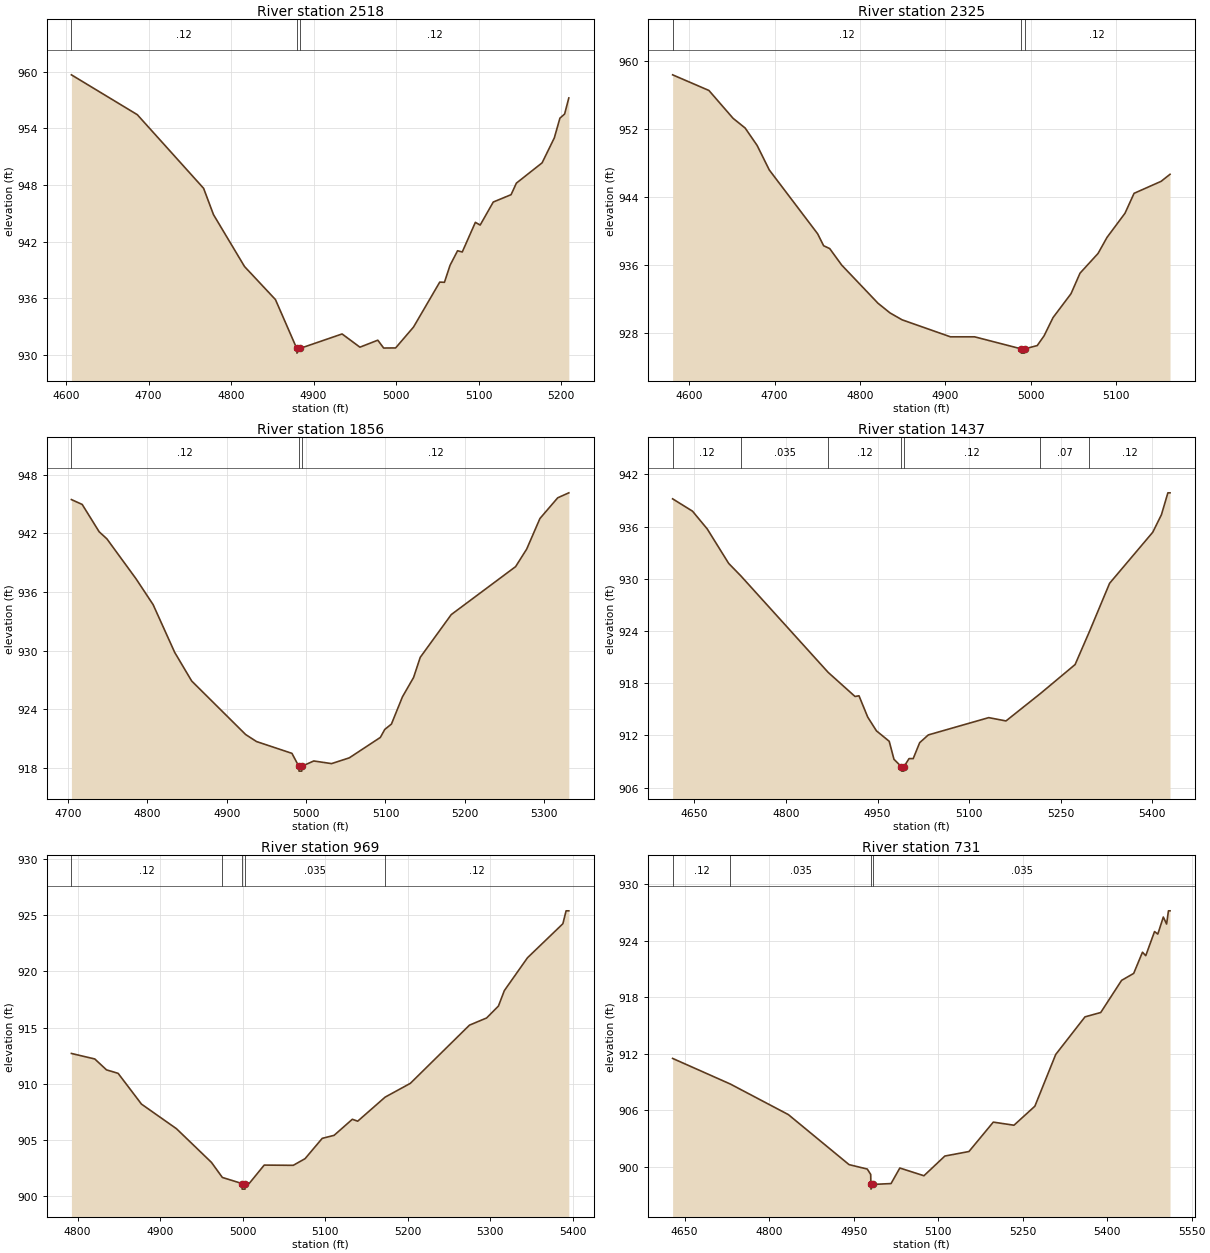
Type RM Length L Ch R = 1,2518,193,193,193
BEGIN DESCRIPTION:
X18157
END DESCRIPTION:
XS GIS Cut Line= 2
      2182707.67     13793494.50      2183004.79     13792969.66
#Sta/Elev= 30
  4606.4  959.66  4686.3  955.44  4766.7  947.64  4778.7  944.85  4816.3  939.36
  4853.8  935.86  4879.6  930.69  4879.9  930.19  4883.6  930.69  4934.6  932.22
  4956.2  930.82  4977.9  931.56  4985.0  930.73  4999.5  930.74  5021.2  932.95
  5053.0  937.71  5058.7  937.69  5065.5  939.49  5074.6  941.03  5080.3  940.90
  5096.2  944.04  5102.0  943.75  5117.9  946.19  5139.5  946.97  5145.9  948.19
  5177.1  950.34  5191.9  952.98  5198.7  955.07  5204.4  955.51  5209.5  957.21
#Mann=3,-1,0
  4606.4    0.12       0  4879.6    0.05       0  4883.6    0.12       0
Bank Sta=4879.6,4883.6
Exp/Cntr=0.3,0.1

Type RM Length L Ch R = 1,2325,469,469,469
BEGIN DESCRIPTION:
Bear Creek Tributary 9 4.0
END DESCRIPTION:
XS GIS Cut Line= 3
      2182774.97     13793525.03      2183075.00     13793225.00
      2183124.99     13793075.02
#Sta/Elev= 30
  4580.7  958.39  4623.2  956.55  4651.5  953.27  4665.6  952.13  4679.7  950.07
  4693.9  947.19  4750.5  939.68  4757.5  938.27  4764.6  937.94  4778.7  935.99
  4821.2  931.50  4835.3  930.36  4849.4  929.55  4906.0  927.55  4934.3  927.55
  4988.9  926.13  4989.1  925.63  4992.6  925.63  4992.9  926.13  5007.6  926.52
  5015.6  927.66  5026.1  929.81  5047.2  932.63  5057.7  935.04  5078.8  937.36
  5089.3  939.25  5110.4  942.10  5121.0  944.44  5152.6  945.85  5163.1  946.68
#Mann=3,-1,0
  4580.7    0.12       0  4988.9    0.05       0  4992.9    0.12       0
Bank Sta=4988.9,4992.9
Exp/Cntr=0.3,0.1

Type RM Length L Ch R = 1,1856,419,419,419
BEGIN DESCRIPTION:
Bear Creek Tributary 9 3.0
END DESCRIPTION:
XS GIS Cut Line= 3
      2183174.99     13793675.01      2183425.00     13793525.00
      2183575.01     13793224.97
#Sta/Elev= 30
  4704.1  945.46  4717.7  944.96  4739.1  942.16  4748.8  941.44  4785.7  937.33
  4807.1  934.70  4834.3  929.81  4855.7  926.88  4923.7  921.40  4937.4  920.68
  4982.1  919.47  4990.7  918.15  4991.0  917.65  4994.5  917.65  4994.7  918.15
  5009.6  918.69  5032.0  918.42  5054.4  919.01  5093.5  921.10  5099.1  921.92
  5107.5  922.47  5121.4  925.26  5135.4  927.24  5143.8  929.30  5182.9  933.68
  5264.0  938.59  5278.0  940.39  5294.7  943.52  5317.1  945.64  5331.1  946.15
#Mann=3,-1,0
  4704.1    0.12       0  4990.7    0.05       0  4994.7    0.12       0
Bank Sta=4990.7,4994.7
Exp/Cntr=0.3,0.1

Type RM Length L Ch R = 1,1437,468,468,468
BEGIN DESCRIPTION:
Bear Creek Tributary 9 2.0
END DESCRIPTION:
XS GIS Cut Line= 3
      2183374.97     13794075.03      2183675.00     13793825.00
      2183974.99     13793525.01
#Sta/Elev= 30
  4614.3  939.20  4646.9  937.78  4671.0  935.74  4706.1  931.78  4726.1  930.34
  4869.1  919.25  4913.1  916.48  4919.6  916.56  4933.9  914.11  4948.2  912.53
  4969.1  911.33  4976.9  909.26  4989.2  908.40  4989.4  907.90  4992.9  907.90
  4993.2  908.40  5001.6  909.34  5008.4  909.34  5019.0  911.17  5033.1  912.06
  5132.1  914.05  5160.4  913.67  5216.8  916.82  5273.6  920.15  5297.0  923.93
  5330.1  929.49  5400.8  935.36  5415.0  937.37  5425.6  939.89  5429.1  939.89
#Mann=7,-1,0
  4614.3    0.12       0  4726.1   0.035       0  4869.1    0.12       0
  4989.2    0.05       0  4993.2    0.12       0  5216.8    0.07       0
  5297.0    0.12       0
Bank Sta=4989.2,4993.2
Exp/Cntr=0.3,0.1

Type RM Length L Ch R = 1,969,238,238,238
BEGIN DESCRIPTION:
Bear Creek Tributary 9 1.0
END DESCRIPTION:
XS GIS Cut Line= 3
      2183874.97     13794225.03      2184025.00     13794075.00
      2184275.01     13793774.99
#Sta/Elev= 30
  4792.6  912.70  4820.9  912.21  4835.1  911.24  4849.2  910.93  4877.5  908.19
  4919.9  906.00  4962.3  903.00  4975.5  901.66  4999.2  901.12  4999.5  900.62
  5003.0  900.62  5003.2  901.12  5008.0  901.12  5026.2  902.76  5061.4  902.74
  5075.7  903.33  5096.5  905.14  5110.9  905.41  5133.0  906.84  5139.5  906.67
  5172.7  908.81  5203.3  910.04  5274.9  915.22  5295.7  915.86  5310.0  916.92
  5317.2  918.30  5345.2  921.22  5388.1  924.25  5392.0  925.40  5395.3  925.40
#Mann=5,-1,0
  4792.6    0.12       0  4975.5   0.035       0  4999.2   0.035       0
  5003.2   0.035       0  5172.7    0.12       0
Bank Sta=4999.2,5003.2
Exp/Cntr=0.3,0.1

Type RM Length L Ch R = 1,731,217,217,217
BEGIN DESCRIPTION:
X18156
END DESCRIPTION:
XS GIS Cut Line= 3
      2183864.34     13794371.21      2184194.24     13794238.82
      2184463.36     13793785.22
#Sta/Elev= 30
  4628.7  911.52  4731.2  908.80  4834.1  905.56  4941.9  900.25  4974.2  899.78
  4980.3  899.21  4980.6  898.15  4980.8  897.65  4984.6  898.15  5016.4  898.24
  5032.0  899.89  5074.8  899.07  5111.9  901.16  5154.7  901.64  5197.9  904.76
  5234.6  904.43  5271.7  906.45  5308.7  911.94  5360.7  915.93  5388.6  916.39
  5425.6  919.80  5447.1  920.54  5462.7  922.79  5468.5  922.42  5484.1  924.98
  5489.9  924.71  5499.7  926.52  5505.5  925.78  5508.8  927.18  5511.6  927.18
#Mann=4,-1,0
  4628.7    0.12       0  4731.2   0.035       0  4980.6   0.035       0
  4984.6   0.035       0
Bank Sta=4980.6,4984.6
Exp/Cntr=0.3,0.1

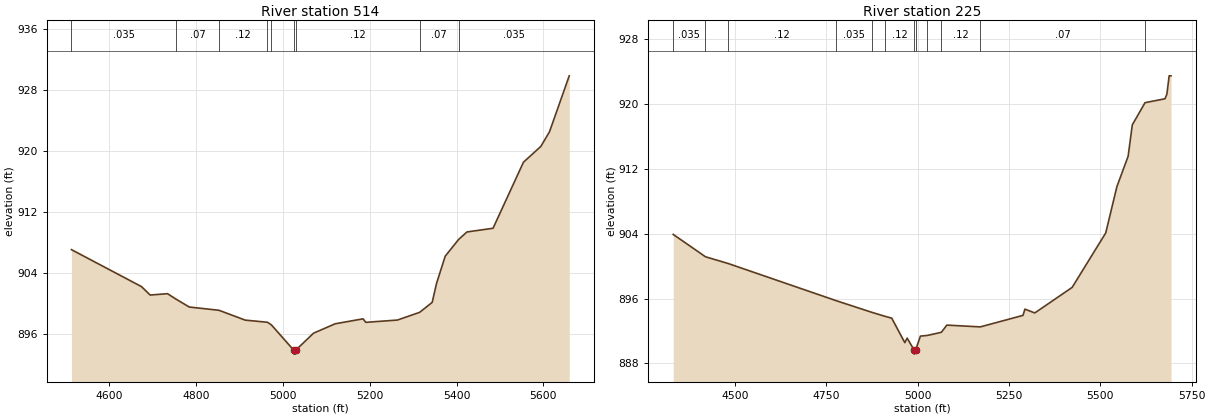
Type RM Length L Ch R = 1,514,289,289,289
BEGIN DESCRIPTION:
X18155
END DESCRIPTION:
XS GIS Cut Line= 4
      2183933.81     13794488.39      2184276.70     13794477.54
      2184524.10     13794160.69      2184539.27     13793759.63
#Sta/Elev= 30
  4513.1  907.12  4674.4  902.27  4694.4  901.16  4734.4  901.34  4754.4  900.61
  4784.4  899.59  4853.0  899.16  4913.4  897.87  4964.5  897.59  4973.7  897.24
  5025.3  893.91  5025.6  893.41  5029.1  893.41  5029.3  893.91  5070.7  896.16
  5120.5  897.39  5184.7  898.04  5191.0  897.58  5263.8  897.88  5314.9  898.89
  5343.9  900.20  5353.9  902.69  5373.9  906.26  5404.7  908.45  5424.0  909.44
  5484.0  909.92  5554.1  918.59  5594.1  920.66  5614.1  922.59  5659.5  929.92
#Mann=9,-1,0
  4513.1   0.035       0  4754.4    0.07       0  4853.0    0.12       0
  4964.5    0.07       0  4973.7    0.12       0  5025.3    0.05       0
  5029.3    0.12       0  5314.9    0.07       0  5404.7   0.035       0
Bank Sta=5025.3,5029.3
Exp/Cntr=0.3,0.1

Type RM Length L Ch R = 1,225,0,0,0
BEGIN DESCRIPTION:
X18154
END DESCRIPTION:
XS GIS Cut Line= 4
      2184022.79     13794514.43      2184567.50     13794529.62
      2184725.92     13794286.56      2184617.42     13793770.08
#Sta/Elev= 30
  4330.7  903.92  4419.0  901.16  4481.8  900.32  4777.1  895.74  4875.6  894.29
  4911.6  893.80  4928.9  893.59  4964.7  890.57  4971.2  891.12  4990.3  889.65
  4990.6  889.15  4994.3  889.65  5007.4  891.37  5026.8  891.46  5064.7  891.84
  5079.9  892.73  5171.5  892.51  5288.3  893.93  5293.5  894.70  5320.6  894.23
  5422.8  897.38  5514.8  904.10  5545.4  909.82  5576.1  913.56  5587.5  917.43
  5622.4  920.17  5677.0  920.65  5682.2  921.22  5688.4  923.48  5693.5  923.48
#Mann=12,-1,0
  4330.7   0.035       0  4419.0    0.07       0  4481.8    0.12       0
  4777.1   0.035       0  4875.6    0.07       0  4911.6    0.12       0
  4990.3    0.05       0  4994.3    0.12       0  5026.8    0.07       0
  5064.7    0.12       0  5171.5    0.07       0  5622.4   0.035       0
Bank Sta=4990.3,4994.3
Exp/Cntr=0.3,0.1

Chan Stop Cuts=-1