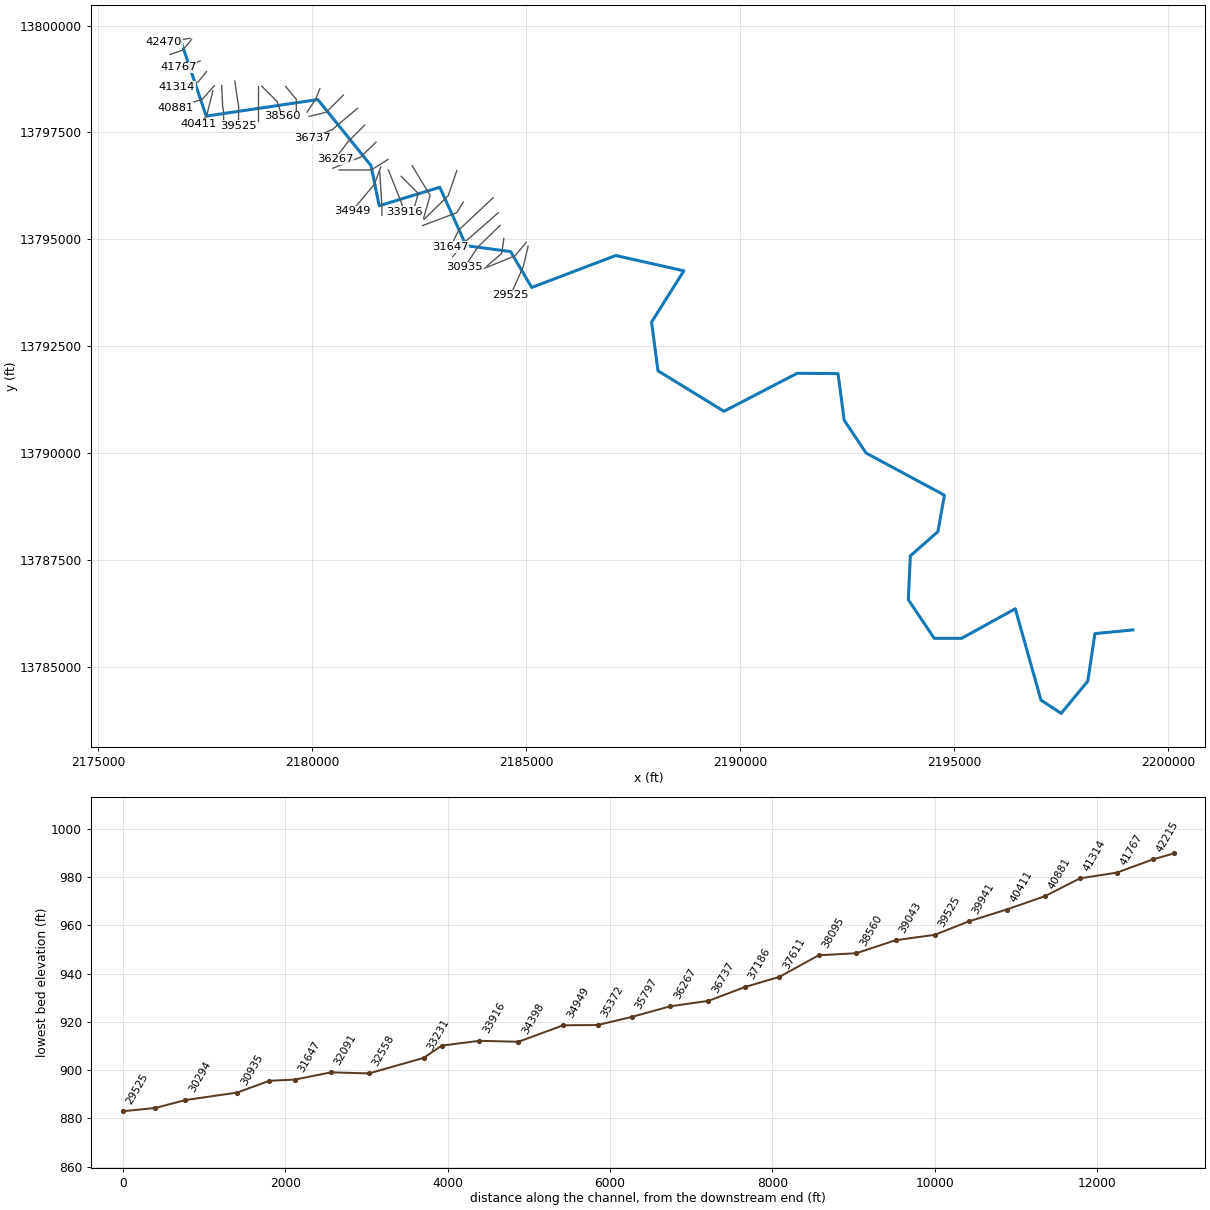
--- Bear Creek.prj (project) ---

Proj Title=Bear Creek Base Level Engineering
Current Plan=p01
Default Exp/Contr=0.3,0.1
English Units
Geom File=g01
Flow File=f01
Plan File=p01
Y Axis Title=Elevation
X Axis Title(PF)=Main Channel Distance
X Axis Title(XS)=Station
BEGIN DESCRIPTION:
Bear Creek
END DESCRIPTION:
DSS Export Rating Curves= 0
DSS Export Rating Curve Sorted= 0
DSS Export Volume Flow Curves= 0
DXF OffsetX= 0
DXF OffsetY= 0
DXF ScaleX= 1
DXF ScaleY= 10

--- Bear Creek.p01 (plan) ---

Plan Title=Multiple Run
Short Identifier=Multiple
Geom File=g01
Flow File=f01
Subcritical Flow
K Sum by GR= 0
Std Step Tol= 0.01
Critical Tol= 0.01
Num of Std Step Trials= 20
Max Error Tol= 0.3
Flow Tol Ratio= 0.001
Split Flow NTrial= 30
Split Flow Tol= 0.02
Split Flow Ratio= 0.02
Log Output Level= 0
Friction Slope Method= 1
Unsteady Friction Slope Method= 2
Unsteady Bridges Friction Slope Method= 1
Parabolic Critical Depth
Global Vel Dist=  1 , 1 , 1
Global Log Level= 0
CheckData=True
Encroach Param= -1, 0, 0, 0
BEGIN DESCRIPTION:
Multiple Run
END DESCRIPTION:

--- Bear Creek.f01 (steady flow) ---

Flow Title=Multiple
Number of Profiles=7
Profile Names=10-year,25-year,50-year,1pct_min,100-year,1pct_plu,500-year
River Rch & RM= Bear Creek,Reach-1,42470
     719    1189    1627    1079    2154    4297    3733
River Rch & RM= Bear Creek,Reach-1,40411
    1043    1758    2434    1631    3254    6493    5762
River Rch & RM= Bear Creek,Reach-1,37186
    1684    2916    4109    2799    5585   11143   10220
River Rch & RM= Bear Creek,Reach-1,35372
    1662    2872    4042    2750    5486   10947   10013
River Rch & RM= Bear Creek,Reach-1,34949
    1875    3250    4581    3119    6222   12415   11377
River Rch & RM= Bear Creek,Reach-1,31647
    2006    3487    4926    3360    6704   13377   12306
River Rch & RM= Bear Creek,Reach-1,30294
    2051    3564    5032    3431    6845   13657   12551
River Rch & RM= Bear Creek,Reach-1,29525
    2164    3753    5290    3598    7179   14325   13104
River Rch & RM= Bear Creek,Reach-1,22979
    2535    4424    6265    4278    8535   17030   15704
River Rch & RM= Bear Creek,Reach-1,20388
    2513    4382    6200    4231    8441   16842   15506
River Rch & RM= Bear Creek,Reach-1,19916
    2600    4535    6418    4379    8738   17434   16051
River Rch & RM= Bear Creek,Reach-1,18166
    3802    6727    9611    6614   13196   26330   24657
River Rch & RM= Bear Creek,Reach-1,13949
    4369    7755   11104    7653   15269   30466   28619
River Rch & RM= Bear Creek,Reach-1,8419
    4515    8013   11472    7904   15770   31466   29541
River Rch & RM= Bear Creek,Reach-1,4518
    4551    8069   11544    7947   15856   31637   29653
Boundary for River Rch & Prof#=Bear Creek,Reach-1,1
Up Type=0
Dn Type=3
Dn Slope=0.005
Boundary for River Rch & Prof#=Bear Creek,Reach-1,2
Up Type=0
Dn Type=3
Dn Slope=0.005
Boundary for River Rch & Prof#=Bear Creek,Reach-1,3
Up Type=0
Dn Type=3
Dn Slope=0.005
Boundary for River Rch & Prof#=Bear Creek,Reach-1,4
Up Type=0
Dn Type=3
Dn Slope=0.005
Boundary for River Rch & Prof#=Bear Creek,Reach-1,5
Up Type=0
Dn Type=3
Dn Slope=0.005
Boundary for River Rch & Prof#=Bear Creek,Reach-1,6
Up Type=0
Dn Type=3
Dn Slope=0.005
Boundary for River Rch & Prof#=Bear Creek,Reach-1,7
Up Type=0
Dn Type=3
Dn Slope=0.005

--- Bear Creek.g01 (geometry) ---

Geom Title=Existing Conditions
Program Version=4.10

River Reach=Bear Creek      ,Reach-1
Reach XY= 30
      2176908.76     13799691.24      2177518.92     13797883.13
       2180127.3     13798269.17      2181369.54     13796727.45
      2181561.68     13795788.37      2182977.43     13796219.48
      2183594.37       13794855.      2184631.06     13794717.52
      2185126.45     13793878.53      2187090.22     13794624.75
      2188681.21      13794267.2      2187927.14     13793069.03
      2188076.96     13791930.88      2189618.41     13790984.47
      2191330.86     13791872.92      2192284.83     13791864.53
      2192428.55     13790776.47      2192941.46     13790007.87
      2194771.39      13789023.5      2194619.15     13788172.71
      2193975.06     13787604.97      2193926.97     13786580.89
      2194533.41     13785678.38      2195173.54     13785678.54
      2196427.47     13786369.55      2197028.16     13784233.34
      2197500.04     13783924.49      2198121.25     13784676.55
      2198288.46     13785788.56        2199175.       13785875.

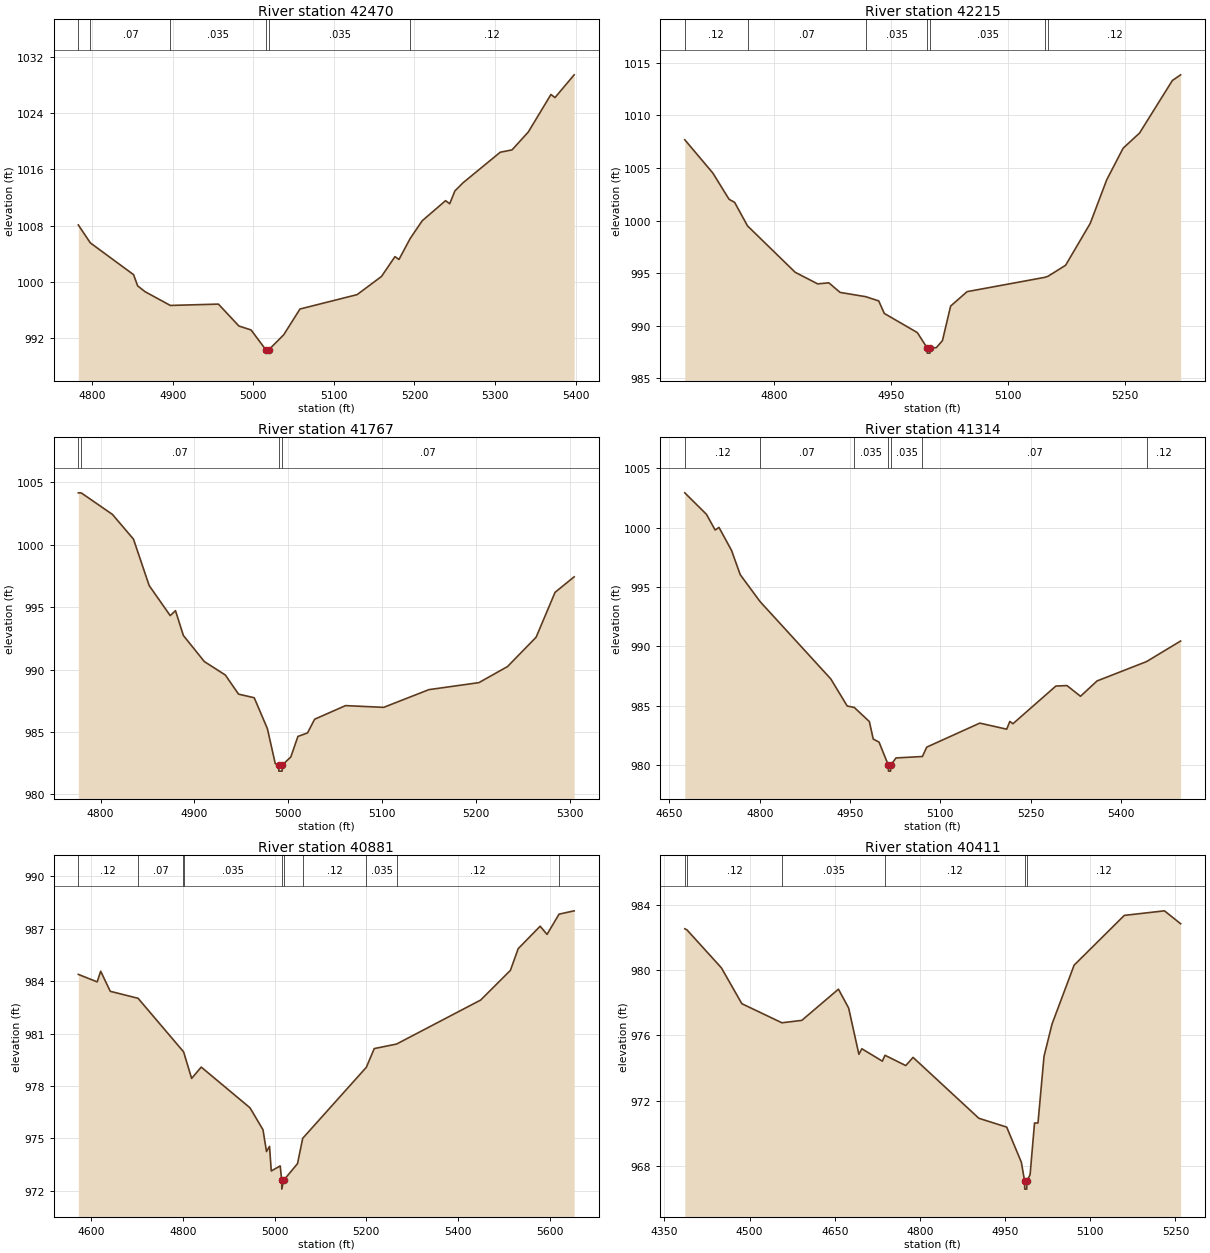
Type RM Length L Ch R = 1 ,42470   ,255,255,255
BEGIN DESCRIPTION:
X18098
END DESCRIPTION:
XS GIS Cut Line= 2
      2177136.85     13799700.69      2176528.78     13799605.99
#Sta/Elev= 30
  4782.8 1008.09  4797.7 1005.54  4851.4 1001.01  4856.4  999.42  4865.6  998.59
    4897  996.63  4956.7  996.82  4982.1   993.7  4997.2  993.14  5015.4  990.34
  5015.7  989.84  5019.4  990.34  5037.7  992.45  5057.9  996.12  5128.8  998.17
  5159.1 1000.76  5175.8 1003.58  5180.8 1003.18  5194.6 1006.15  5209.7  1008.7
  5238.6 1011.55  5243.7 1011.11  5250.2 1012.94  5260.3  1014.1  5306.5 1018.45
  5321.1 1018.78  5341.3 1021.33  5369.4 1026.67  5374.4 1026.23  5398.2 1029.47
#Mann= 6 ,-1 , 0
  4782.8     .12       0  4797.7     .07       0    4897    .035       0
  5015.4    .035       0  5019.4    .035       0  5194.6     .12       0
Bank Sta=5015.4,5019.4
XS Rating Curve= 0 ,0
Exp/Cntr=0.3,0.1

Type RM Length L Ch R = 1 ,42215   ,448,448,448
BEGIN DESCRIPTION:
Bear Creek 81.0
END DESCRIPTION:
XS GIS Cut Line= 3
        2177175.       13799675.        2176975.       13799425.
      2176674.99       13799325.
#Sta/Elev= 30
  4684.9 1007.67  4720.9 1004.51  4741.7 1002.02  4748.9 1001.72  4765.4  999.49
  4826.6  995.08  4855.4  993.98  4869.8  994.08  4884.2  993.17  4917.3  992.76
  4933.8  992.36    4941  991.17  4983.4  989.35  4995.9   987.9  4996.1   987.4
  4999.6   987.4  4999.9   987.9  5007.7  987.92  5015.6  988.59  5026.1  991.87
  5047.2  993.24    5147   994.6  5151.3  994.71  5173.7  995.75  5205.3  999.73
  5226.4 1003.86  5247.5 1006.87  5268.6 1008.31  5310.7  1013.3  5321.3 1013.84
#Mann= 7 ,-1 , 0
  4684.9     .12       0  4765.4     .07       0  4917.3    .035       0
  4995.9    .035       0  4999.9    .035       0    5147     .07       0
  5151.3     .12       0
Bank Sta=4995.9,4999.9
XS Rating Curve= 0 ,0
Exp/Cntr=0.3,0.1

Type RM Length L Ch R = 1 ,41767   ,453,453,453
BEGIN DESCRIPTION:
Bear Creek 80.0
END DESCRIPTION:
XS GIS Cut Line= 3
      2177374.98     13799174.99        2177175.       13799075.
      2176875.02       13799025.
#Sta/Elev= 30
  4776.4 1004.16  4779.6 1004.15  4812.7 1002.43  4835.1 1000.45  4851.8  996.73
  4874.2  994.32  4879.8  994.72  4888.2  992.73  4910.5  990.64  4932.9  989.56
  4946.9  988.03  4963.6  987.74  4977.6  985.27    4986  982.46  4989.6  982.36
  4989.8  981.86  4993.3  981.86  4993.6  982.36  5002.5  982.99  5010.1  984.64
  5020.3  984.92  5027.9  986.02  5060.8  987.11  5101.4  986.97  5149.5  988.39
  5202.7  988.95  5233.2  990.24  5263.6  992.59  5283.8  996.19  5304.1  997.43
#Mann= 4 ,-1 , 0
  4776.4     .12       0  4779.6     .07       0  4989.6     .05       0
  4993.6     .07       0
Bank Sta=4989.6,4993.6
XS Rating Curve= 0 ,0
Exp/Cntr=0.3,0.1

Type RM Length L Ch R = 1 ,41314   ,433,433,433
BEGIN DESCRIPTION:
Bear Creek 79.0
END DESCRIPTION:
XS GIS Cut Line= 3
      2177525.01     13798925.02        2177325.       13798675.
      2176832.23     13798571.97
#Sta/Elev= 30
  4675.6 1002.93  4711.6 1001.12    4726   999.8  4732.4 1000.02  4753.3  998.08
  4767.7  996.04  4800.6  993.78  4918.1  987.27  4945.4  984.99  4957.1  984.87
  4982.2  983.68  4988.6  982.21  4998.3  981.95  5013.7  980.01  5013.9  979.51
  5017.4  979.51  5017.7  980.01  5026.4  980.62  5070.3  980.74  5077.5  981.53
  5165.6  983.55  5210.3  983.04  5215.5  983.69  5220.7   983.5    5292  986.67
  5310.4  986.71  5332.9  985.81  5360.4   987.1  5442.7  988.73  5499.2  990.46
#Mann= 7 ,-1 , 0
  4675.6     .12       0  4800.6     .07       0  4957.1    .035       0
  5013.7    .035       0  5017.7    .035       0  5070.3     .07       0
  5442.7     .12       0
Bank Sta=5013.7,5017.7
XS Rating Curve= 0 ,0
Exp/Cntr=0.3,0.1

Type RM Length L Ch R = 1 ,40881   ,470,470,470
BEGIN DESCRIPTION:
Bear Creek 78.0
END DESCRIPTION:
XS GIS Cut Line= 3
      2177706.23     13798591.98        2177425.       13798275.
      2176798.61     13798077.96
#Sta/Elev= 30
  4572.4  984.39  4613.5  983.96  4621.1  984.57    4642  983.42  4702.6  983.02
  4800.6  979.99  4801.7  979.96  4819.3  978.43  4840.2  979.08  4946.4  976.75
  4974.8  975.49  4982.4  974.24    4989  974.54  4992.8  973.13  5012.3  973.42
  5015.6  972.59  5015.8  972.09  5019.6  972.59    5050  973.55  5061.3     975
    5200  979.07  5217.2  980.14  5265.9   980.4  5449.1  982.92  5513.9  984.62
  5530.8  985.86  5578.7  987.15  5593.7  986.68  5619.9  987.84  5652.8  988.03
#Mann= 10 ,-1 , 0
  4572.4     .12       0  4702.6     .07       0  4800.6     .12       0
  4801.7    .035       0  5015.6    .035       0  5019.6    .035       0
  5061.3     .12       0    5200    .035       0  5265.9     .12       0
  5619.9     .07       0
Bank Sta=5015.6,5019.6
XS Rating Curve= 0 ,0
Exp/Cntr=0.3,0.1

Type RM Length L Ch R = 1 ,40411   ,470,470,470
BEGIN DESCRIPTION:
Bear Creek 77.0
END DESCRIPTION:
XS GIS Cut Line= 4
      2177674.99     13798474.98        2177525.       13797875.
        2177475.       13797825.      2177344.86     13797694.86
#Sta/Elev= 30
  4385.9  982.53  4389.8  982.46  4450.3  980.14  4486.4  977.94    4557  976.77
    4592  976.92  4656.5  978.83  4674.5  977.67  4692.5  974.84  4697.7  975.18
  4733.8  974.42  4738.5  974.78    4775  974.15  4787.9  974.65  4903.8  970.92
  4952.8  970.38  4978.6  968.23  4984.3  967.08  4984.6  966.58  4988.1  966.58
  4988.3  967.08    4994  967.46  5001.8  970.63  5007.9  970.63  5018.5  974.71
  5032.6  976.69  5071.5   980.3  5159.9  983.35  5230.6  983.63  5259.1  982.84
#Mann= 6 ,-1 , 0
  4385.9     .07       0  4389.8     .12       0    4557    .035       0
  4738.5     .12       0  4984.3     .05       0  4988.3     .12       0
Bank Sta=4984.3,4988.3
XS Rating Curve= 0 ,0
Exp/Cntr=0.3,0.1

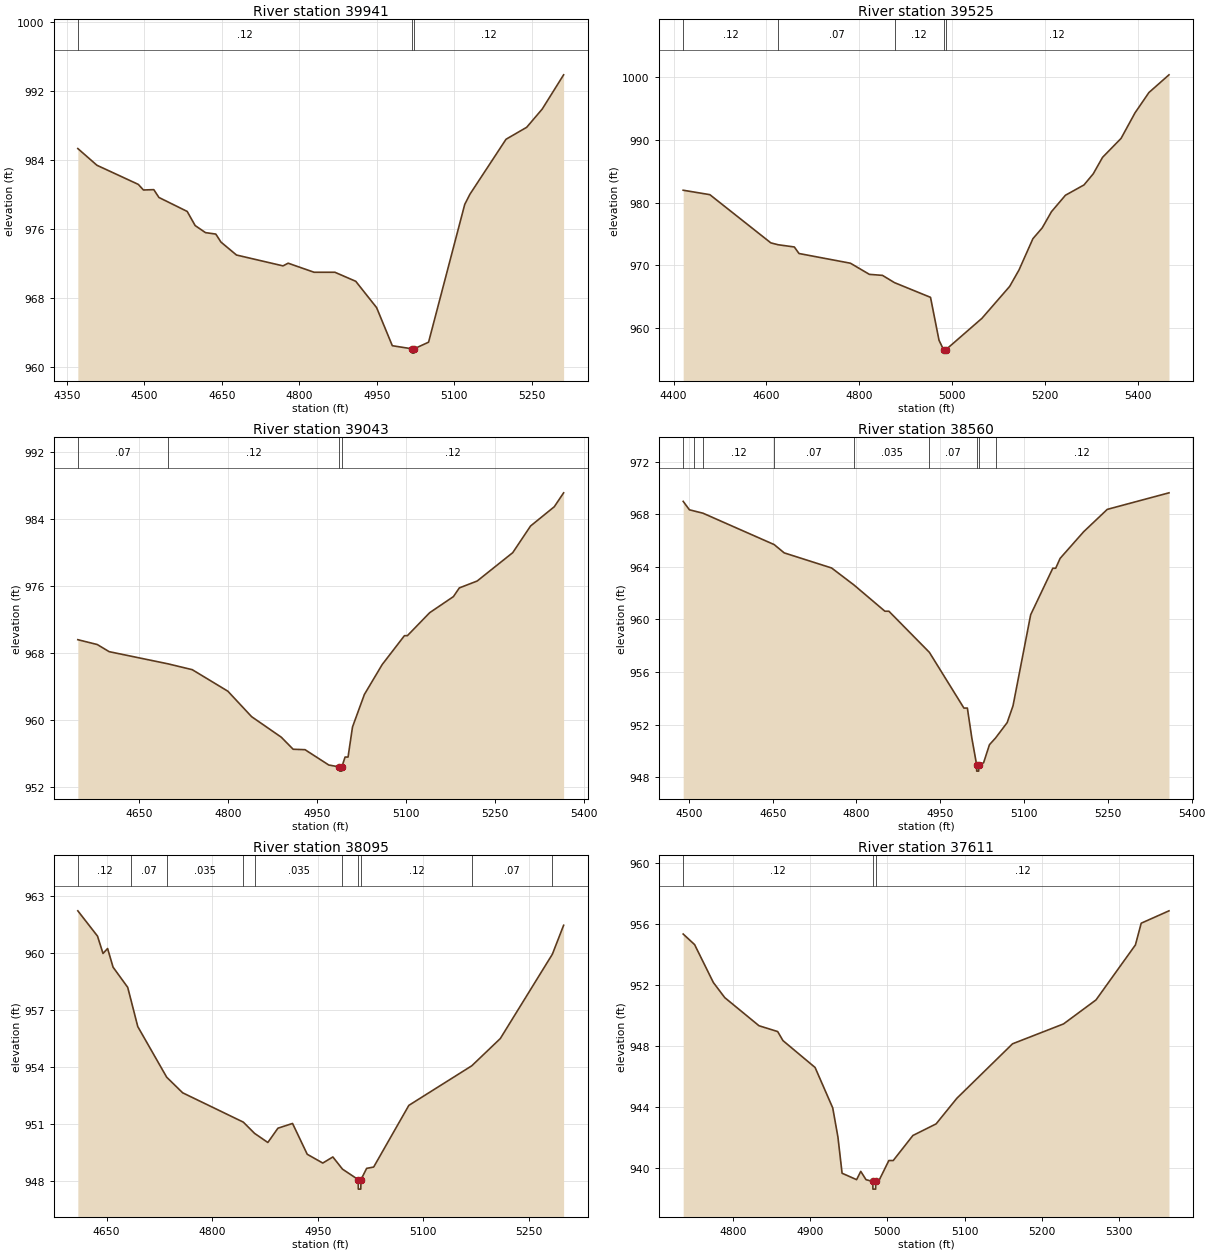
Type RM Length L Ch R = 1 ,39941   ,416,416,416
BEGIN DESCRIPTION:
Bear Creek 76.0
END DESCRIPTION:
XS GIS Cut Line= 5
      2177881.01     13798601.96      2177900.98     13798132.46
        2177925.       13797975.        2177925.       13797825.
        2177925.     13797663.51
#Sta/Elev= 30
  4371.1  985.36  4408.1  983.42  4488.2   981.2  4498.2  980.55  4518.2  980.59
  4528.2  979.68  4582.9  978.06  4598.3  976.42  4618.3   975.6  4638.3  975.43
  4648.3   974.5  4678.3     973  4768.4  971.74  4778.4  972.05  4828.5     971
  4868.8     971  4909.3  969.95  4949.7  966.89  4980.1  962.47  5018.3  962.11
  5018.6  961.61  5022.1  961.61  5022.3  962.11  5050.3  962.88  5120.3  978.87
  5130.3  980.05  5200.3  986.44  5240.3  987.83  5270.3  989.94  5311.8  993.92
#Mann= 3 ,-1 , 0
  4371.1     .12       0  5018.3     .05       0  5022.3     .12       0
Bank Sta=5018.3,5022.3
XS Rating Curve= 0 ,0
Exp/Cntr=0.3,0.1

Type RM Length L Ch R = 1 ,39525   ,482,482,482
BEGIN DESCRIPTION:
Bear Creek 75.0
END DESCRIPTION:
XS GIS Cut Line= 5
      2178185.67      13798701.8      2178255.58     13798237.34
        2178275.       13798125.        2178275.       13797875.
        2178275.      13797661.8
#Sta/Elev= 30
  4420.7  981.95  4478.1  981.25  4609.6  973.59  4625.5  973.29  4660.2  972.94
  4670.3   971.9  4781.1  970.36    4822  968.59  4850.1  968.43  4876.2  967.27
  4953.7  964.94    4972  958.13  4982.1  956.58  4982.4  956.08  4985.9  956.08
  4986.1  956.58  5064.4   961.6  5124.4  966.69  5144.4  969.29  5174.4  974.26
  5194.4  975.97  5214.4  978.55  5244.4  981.15  5284.4  982.79  5304.4  984.56
  5324.4  987.17  5364.4  990.19  5394.4  994.24  5424.4  997.47  5467.6 1000.28
#Mann= 5 ,-1 , 0
  4420.7     .12       0  4625.5     .07       0  4876.2     .12       0
  4982.1     .05       0  4986.1     .12       0
Bank Sta=4982.1,4986.1
XS Rating Curve= 0 ,0
Exp/Cntr=0.3,0.1

Type RM Length L Ch R = 1 ,39043   ,483,483,483
BEGIN DESCRIPTION:
Bear Creek 74.0
END DESCRIPTION:
XS GIS Cut Line= 5
        2178725.     13798577.85        2178725.       13798375.
        2178725.       13798125.        2178725.       13798025.
        2178725.     13797759.35
#Sta/Elev= 30
    4547  969.54  4579.8  968.96  4599.8  968.11  4699.4  966.65  4739.8  965.96
  4799.8  963.39  4839.8  960.35  4889.8   957.9  4909.8  956.46  4929.8  956.41
  4969.8  954.58  4987.8  954.35  4988.1  953.85  4991.6  953.85  4991.8  954.35
  4997.3  955.53  5002.3  955.53  5009.8  959.12  5029.8     963  5059.8  966.57
  5097.3  970.02  5102.3  970.02  5139.8  972.76  5179.8  974.68  5189.8  975.72
  5219.8  976.54  5279.8  979.93  5309.8  983.11  5349.8  985.41  5365.5  987.07
#Mann= 4 ,-1 , 0
    4547     .07       0  4699.4     .12       0  4987.8     .05       0
  4991.8     .12       0
Bank Sta=4987.8,4991.8
XS Rating Curve= 0 ,0
Exp/Cntr=0.3,0.1

Type RM Length L Ch R = 1 ,38560   ,465,465,465
BEGIN DESCRIPTION:
Bear Creek 73.0
END DESCRIPTION:
XS GIS Cut Line= 5
      2178817.15     13798582.85        2179075.       13798325.
        2179175.       13798225.        2179225.       13798075.
      2179289.96     13797880.13
#Sta/Elev= 30
  4489.8  968.99  4500.9  968.35  4509.1  968.26  4525.2  968.09  4652.7   965.7
  4670.6  965.07  4755.5  963.92  4795.4  962.63  4850.9  960.63    4858  960.63
  4930.5   957.5  4992.3  953.26  4998.5  953.26  5006.4     951    5015  948.96
  5015.2  948.46  5018.7  948.46    5019  948.96  5027.5  949.09    5038  950.47
  5048.9  950.98  5069.7  952.15  5080.2  953.43  5111.8  960.36  5151.4   963.9
  5156.6   963.9  5164.5  964.65  5206.7  966.68  5248.9  968.38  5359.4  969.64
#Mann= 9 ,-1 , 0
  4489.8     .07       0  4509.1    .094       0  4525.2     .12       0
  4652.7     .07       0  4795.4    .035       0  4930.5     .07       0
    5015     .05       0    5019     .07       0  5048.9     .12       0
Bank Sta=5015,5019
XS Rating Curve= 0 ,0
Exp/Cntr=0.3,0.1

Type RM Length L Ch R = 1 ,38095   ,484,484,484
BEGIN DESCRIPTION:
Bear Creek 72.0
END DESCRIPTION:
XS GIS Cut Line= 3
      2179375.01     13798574.99        2179625.       13798275.
        2179625.       13797975.
#Sta/Elev= 30
  4609.1  962.21  4637.1  960.88  4644.9  959.97  4651.4  960.23  4659.2  959.25
    4680  958.19  4684.6  957.53  4694.3  956.13  4735.4  953.47  4758.1  952.65
  4844.3  951.11  4860.3  950.52  4879.2  950.04  4893.5  950.79  4914.3  951.04
  4935.2  949.42  4957.3  948.96  4971.6  949.28  4985.3  948.64  5007.6  948.09
  5007.8  947.59  5011.3  947.59  5011.6  948.09  5019.6  948.68  5029.6  948.75
  5079.6  951.99  5169.1  954.07  5209.6   955.5  5283.6  959.93  5299.6  961.45
#Mann= 10 ,-1 , 0
  4609.1     .12       0  4684.6     .07       0  4735.4    .035       0
  4844.3     .07       0  4860.3    .035       0  4985.3     .12       0
  5007.6     .05       0  5011.6     .12       0  5169.1     .07       0
  5283.6     .12       0
Bank Sta=5007.6,5011.6
XS Rating Curve= 0 ,0
Exp/Cntr=0.3,0.1

Type RM Length L Ch R = 1 ,37611   ,425,425,425
BEGIN DESCRIPTION:
Bear Creek 71.0
END DESCRIPTION:
XS GIS Cut Line= 3
      2180175.01     13798525.01        2180075.       13798275.
      2179875.02     13797975.02
#Sta/Elev= 30
  4735.3  955.33  4750.1  954.64  4774.4  952.16  4789.2  951.17  4833.6  949.33
  4857.8  948.95  4864.6  948.36  4906.3   946.6  4929.2  943.95  4935.9  942.05
  4941.3  939.68  4960.1  939.26  4965.5   939.8  4972.3  939.26    4981  939.14
  4981.3  938.64  4984.8  938.64    4985  939.14  4989.8  939.27  5001.9  940.51
  5007.6  940.51  5033.1  942.15  5063.2  942.91  5090.2  944.59  5162.3  948.15
  5228.4  949.45  5270.5  951.02  5321.6  954.62  5329.1  956.04  5365.1  956.85
#Mann= 3 ,-1 , 0
  4735.3     .12       0    4981     .05       0    4985     .12       0
Bank Sta=4981,4985
XS Rating Curve= 0 ,0
Exp/Cntr=0.3,0.1

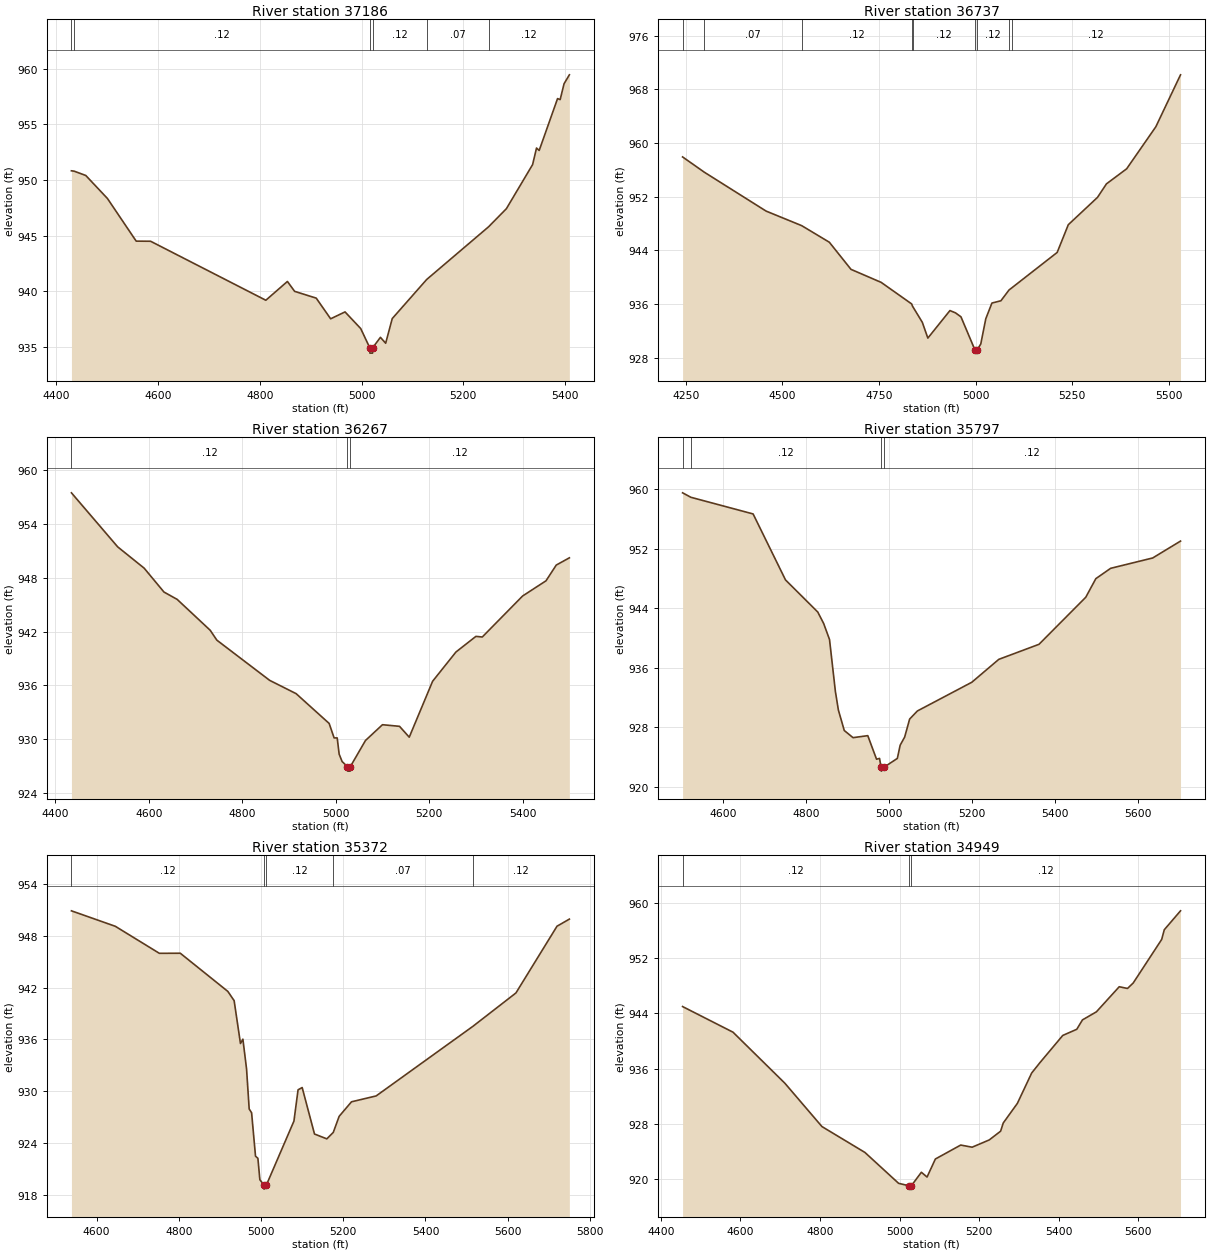
Type RM Length L Ch R = 1 ,37186   ,449,449,449
BEGIN DESCRIPTION:
Bear Creek 70.0
END DESCRIPTION:
XS GIS Cut Line= 3
      2180724.97     13798374.97        2180325.       13797975.
      2179924.96     13797874.99
#Sta/Elev= 30
  4430.2  950.83  4435.4   950.8  4458.4  950.41  4500.9  948.34  4557.4   944.5
  4585.7  944.49    4812  939.18  4854.4  940.87  4868.6  939.98    4911  939.37
  4939.3  937.51  4967.6  938.13  4998.4  936.63    5016  934.92  5016.5  934.42
  5021.6  934.42  5022.1  934.92  5037.1  935.84  5047.4  935.31  5060.3  937.53
    5128  941.05  5249.5  945.79  5284.5  947.42    5336  951.39  5343.7  952.88
  5348.9  952.66    5385  957.33  5390.1  957.24  5397.8  958.67  5408.2  959.47
#Mann= 6 ,-1 , 0
  4430.2    .035       0  4435.4     .12       0    5016     .05       0
  5022.1     .12       0    5128     .07       0  5249.5     .12       0
Bank Sta=5016,5022.1
XS Rating Curve= 0 ,0
Exp/Cntr=0.3,0.1

Type RM Length L Ch R = 1 ,36737   ,470,470,470
BEGIN DESCRIPTION:
Bear Creek 69.0
END DESCRIPTION:
XS GIS Cut Line= 3
      2181057.39     13798067.51        2180475.       13797575.
      2179993.61     13797363.32
#Sta/Elev= 30
  4241.9  957.93  4297.7  955.67    4458  949.86  4550.2  947.69  4621.7  945.22
  4677.7  941.18  4755.8  939.24  4834.7  936.03    4837  935.69  4862.3  933.29
  4876.6  930.94  4933.8  935.04  4948.1   934.7  4962.3  934.11  4998.3   929.2
  4998.8   928.7  5004.4   929.2  5013.6  930.06  5026.5  933.81  5042.4  936.16
  5065.7   936.5  5086.9  938.12  5093.8  938.42  5211.3   943.7  5240.1  947.83
  5315.6   951.9  5338.9  953.92  5391.1  956.16  5466.6  962.42  5530.5  970.16
#Mann= 9 ,-1 , 0
  4241.9    .035       0  4297.7     .07       0  4550.2     .12       0
  4834.7    .035       0    4837     .12       0  4998.3     .05       0
  5004.4     .12       0  5086.9    .035       0  5093.8     .12       0
Bank Sta=4998.3,5004.4
XS Rating Curve= 0 ,0
Exp/Cntr=0.3,0.1

Type RM Length L Ch R = 1 ,36267   ,470,470,470
BEGIN DESCRIPTION:
Bear Creek 68.0
END DESCRIPTION:
XS GIS Cut Line= 3
      2181225.02     13797675.02        2180825.       13797275.
      2180525.01     13796875.01
#Sta/Elev= 30
  4434.3  957.45  4533.3  951.43  4589.9  949.06  4632.3   946.4  4660.6  945.58
  4731.3  942.14  4745.5  941.04  4858.6  936.56  4915.2  935.08  4985.9  931.76
  4996.5  930.15  5003.1  930.15  5007.3  928.34  5013.6  927.52    5025  926.95
  5025.5  926.45  5030.7  926.45  5031.2  926.95  5063.6  929.86    5100  931.62
  5136.5  931.44  5157.3  930.23  5207.3  936.46  5257.3  939.72    5300  941.46
  5313.6  941.39    5400  945.96    5450  947.65  5471.9   949.4    5500  950.21
#Mann= 3 ,-1 , 0
  4434.3     .12       0    5025     .05       0  5031.2     .12       0
Bank Sta=5025,5031.2
XS Rating Curve= 0 ,0
Exp/Cntr=0.3,0.1

Type RM Length L Ch R = 1 ,35797   ,425,425,425
BEGIN DESCRIPTION:
Bear Creek 67.0
END DESCRIPTION:
XS GIS Cut Line= 3
      2181486.91      13797273.4        2181125.       13796925.
      2180479.01     13796664.49
#Sta/Elev= 30
  4502.5  959.49  4522.5  958.89  4672.3  956.65  4750.3  947.78    4828  943.46
  4842.1  941.93  4856.3  939.76  4870.4  932.79  4877.6  930.29  4891.8  927.53
  4912.9  926.57  4948.4  926.84  4969.5  923.67  4976.7  923.78  4980.5  922.57
    4981  922.07  4986.8  922.57  5019.6  923.78  5026.4  925.56  5037.2  926.65
  5049.2  929.07  5067.9  930.16  5198.9  934.02  5263.9   937.1  5360.6  939.12
  5473.3  945.45  5497.5  947.95  5533.2  949.34  5634.4  950.73  5701.4     953
#Mann= 4 ,-1 , 0
  4502.5    .035       0  4522.5     .12       0  4980.5     .05       0
  4986.8     .12       0
Bank Sta=4980.5,4986.8
XS Rating Curve= 0 ,0
Exp/Cntr=0.3,0.1

Type RM Length L Ch R = 1 ,35372   ,423,423,423
BEGIN DESCRIPTION:
Bear Creek 66.0
END DESCRIPTION:
XS GIS Cut Line= 3
      2181766.59     13796868.87        2181375.       13796625.
      2180625.02       13796625.
#Sta/Elev= 30
  4538.8  950.89  4645.5   949.1  4752.7  945.97  4803.6  945.98  4919.3  941.56
  4934.6  940.49    4950  935.53  4955.9  936.03  4964.8  932.59  4971.2  927.95
  4977.1  927.51  4986.6  922.48  4992.4  922.24  4997.2  919.76  5006.9  919.17
  5007.4  918.67  5013.3  919.17  5080.1  926.55  5090.1  930.17  5100.1  930.43
  5130.1  925.05  5160.1  924.49  5175.8  925.24  5190.1   927.1  5220.1  928.78
  5280.1  929.46  5515.5  937.52  5620.1  941.38  5720.1  949.11  5750.1  949.93
#Mann= 5 ,-1 , 0
  4538.8     .12       0  5006.9     .05       0  5013.3     .12       0
  5175.8     .07       0  5515.5     .12       0
Bank Sta=5006.9,5013.3
XS Rating Curve= 0 ,0
Exp/Cntr=0.3,0.1

Type RM Length L Ch R = 1 ,34949   ,551,551,551
BEGIN DESCRIPTION:
X18099
END DESCRIPTION:
XS GIS Cut Line= 3
      2181596.83     13796694.12      2181451.98     13796294.54
      2180922.58     13795660.26
#Sta/Elev= 30
  4454.8     945  4581.5  941.29    4712  933.89  4804.9  927.63    4913  923.88
  4997.6  919.41  5022.5  919.07    5023  918.57  5029.8  919.07  5054.8  921.01
  5069.1  920.32    5090  922.93  5153.7  924.95  5182.4  924.64  5225.3  925.69
    5254  926.96  5260.5  928.14    5296  930.98    5332  935.38  5352.9  936.89
  5410.1  940.82  5445.3  941.71  5459.6  943.07  5494.7  944.24    5552  947.87
  5572.8  947.62  5587.1  948.41  5658.7  954.72  5665.2  956.12    5706  958.86
#Mann= 3 ,-1 , 0
  4454.8     .12       0  5022.5     .05       0  5029.8     .12       0
Bank Sta=5022.5,5029.8
XS Rating Curve= 0 ,0
Exp/Cntr=0.3,0.1

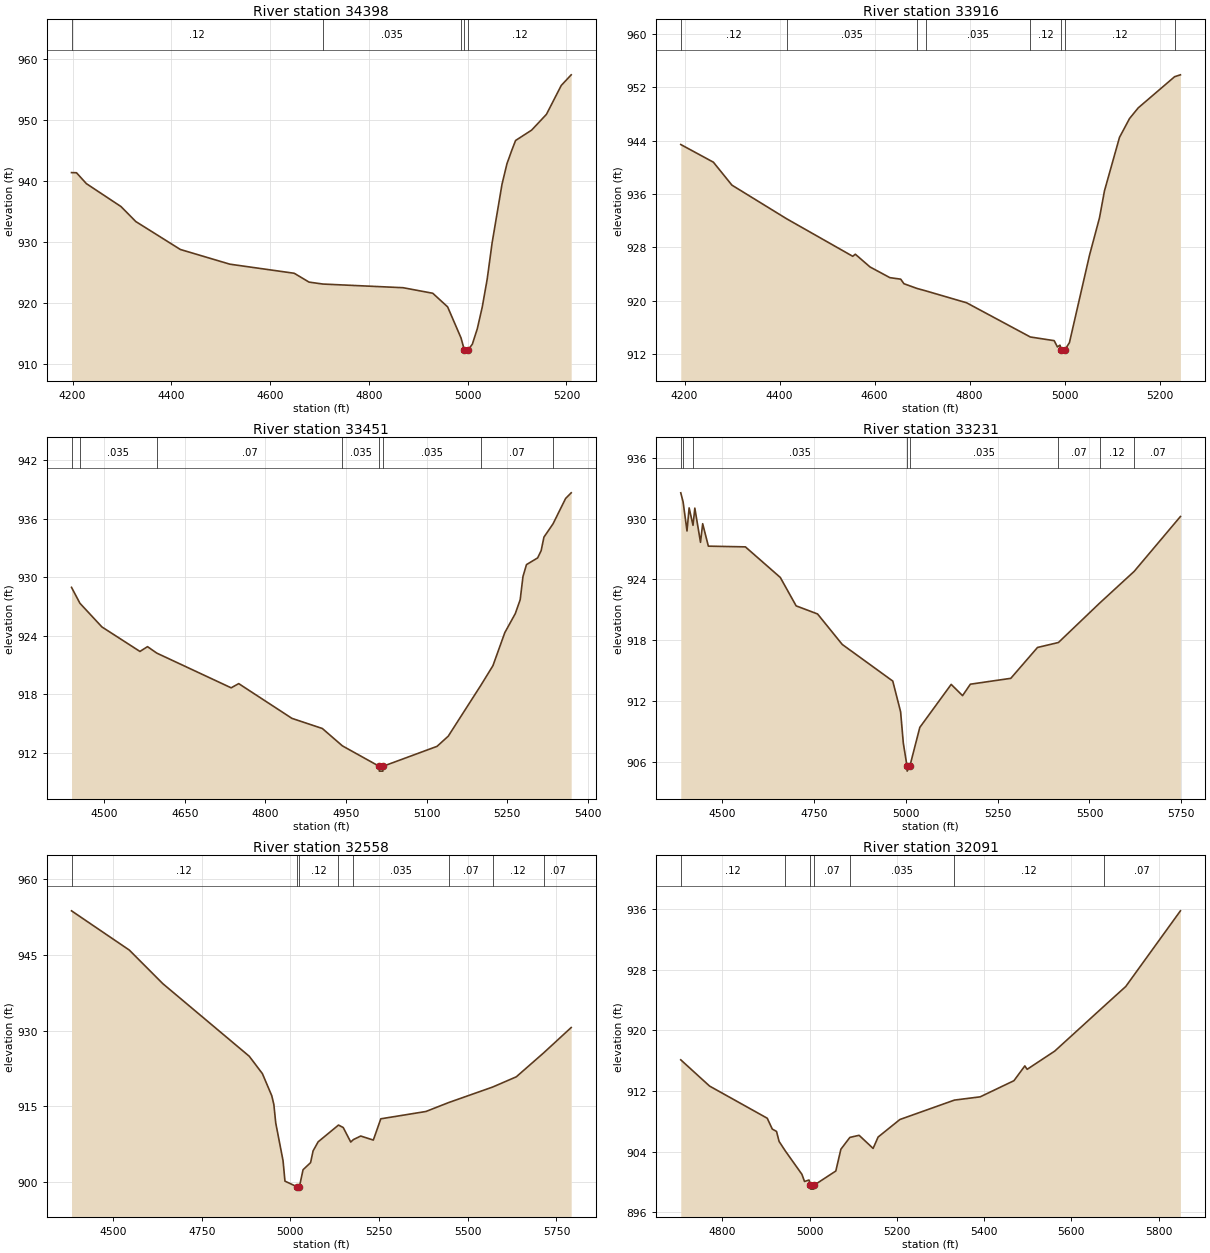
Type RM Length L Ch R = 1 ,34398   ,482,482,482
BEGIN DESCRIPTION:
Bear Creek 65.0
END DESCRIPTION:
XS GIS Cut Line= 4
        2181575.       13796575.        2181625.       13795775.
        2181625.       13795675.        2181625.     13795564.86
#Sta/Elev= 30
    4198  941.35    4208  941.33  4228.1  939.54  4298.2  935.78  4328.2  933.32
  4418.4  928.74  4518.6  926.33  4648.9  924.84  4678.9  923.39  4707.1  923.07
  4869.3  922.47  4929.4  921.56  4959.5  919.33  4986.7  914.22  4993.4  912.24
  4993.9  911.74  5000.8  912.24  5009.6  913.22  5019.6  915.74  5029.6  919.29
  5039.6  923.86  5049.6  929.83  5069.6  939.43  5079.6   942.8  5089.6  945.05
  5097.1  946.62  5129.6  948.32  5159.6  950.91  5189.6  955.65  5209.7  957.39
#Mann= 5 ,-1 , 0
    4198     .12       0  4707.1    .035       0  4986.7     .12       0
  4993.4     .05       0  5000.8     .12       0
Bank Sta=4993.4,5000.8
XS Rating Curve= 0 ,0
Exp/Cntr=0.3,0.1

Type RM Length L Ch R = 1 ,33916   ,465,465,465
BEGIN DESCRIPTION:
Bear Creek 64.0
END DESCRIPTION:
XS GIS Cut Line= 4
        2181775.     13796624.99        2182075.       13795875.
        2182125.       13795725.      2182152.23      13795643.3
#Sta/Elev= 30
  4191.9  943.41  4260.6  940.76  4299.6  937.32  4414.7  932.28    4554  926.65
  4559.4  926.96  4590.4  925.05  4632.1  923.45    4655  923.22  4661.7  922.54
  4689.2  921.83  4708.1  921.46  4793.7  919.68  4927.9  914.55  4978.1     914
  4984.9  913.06  4990.2  913.32  4993.2  912.63  4993.7  912.13  5000.2  912.13
  5000.7  912.63  5010.2   913.7  5052.4  926.79  5073.5  932.42    5084  936.47
  5115.6  944.48  5136.7   947.3  5155.1  948.91  5231.7  953.58  5243.9  953.86
#Mann= 8 ,-1 , 0
  4191.9     .12       0  4414.7    .035       0  4689.2     .12       0
  4708.1    .035       0  4927.9     .12       0  4993.2     .05       0
  5000.7     .12       0  5231.7    .035       0
Bank Sta=4993.2,5000.7
XS Rating Curve= 0 ,0
Exp/Cntr=0.3,0.1

Type RM Length L Ch R = 1 ,33451   ,220,220,220
BEGIN DESCRIPTION:
Bear Creek 63.0
END DESCRIPTION:
XS GIS Cut Line= 3
        2182075.       13796475.        2182475.       13796075.
        2182375.     13795724.99
#Sta/Elev= 30
  4439.1  928.97  4454.7  927.34  4495.7  924.91  4566.4   922.4  4580.5  922.89
  4597.7  922.23  4736.1  918.67  4750.2   919.1  4849.2  915.54  4905.8   914.5
  4943.1  912.72  5011.4  910.63  5011.9  910.13  5018.4  910.13  5018.9  910.63
  5119.2  912.67    5140  913.71  5201.1  918.96  5223.2  920.94  5245.3  924.33
  5264.8  926.28  5273.9   927.7  5279.1  930.08  5285.6   931.3  5306.4  931.99
  5312.9  932.73  5318.1  934.12    5335  935.48  5358.4  938.08  5368.8  938.66
#Mann= 8 ,-1 , 0
  4439.1     .12       0  4454.7    .035       0  4597.7     .07       0
  4943.1    .035       0  5011.4    .035       0  5018.9    .035       0
  5201.1     .07       0    5335    .035       0
Bank Sta=5011.4,5018.9
XS Rating Curve= 0 ,0
Exp/Cntr=0.3,0.1

Type RM Length L Ch R = 1 ,33231   ,673,673,673
BEGIN DESCRIPTION:
Bear Creek 62.0
END DESCRIPTION:
XS GIS Cut Line= 3
      2182330.97     13796724.08      2182750.51     13796029.83
      2182600.01     13795500.38
#Sta/Elev= 30
  4386.3  932.56  4392.7  931.66  4403.3  928.79  4409.1  931.07  4419.7  929.35
  4424.6  931.05  4440.1  927.67    4446  929.51  4461.5  927.29  4562.4  927.22
  4657.5   924.2  4700.7  921.39  4759.1  920.59  4826.3  917.58    4964  913.96
  4985.4  910.92  4992.8  907.82  5002.8  905.56  5003.3  905.06  5010.6  905.56
  5037.7  909.38  5123.2  913.63  5154.2  912.52  5175.5  913.65  5285.7  914.23
  5358.4  917.28  5415.5  917.77  5527.7  921.66  5621.9   924.8  5747.9  930.22
#Mann= 8 ,-1 , 0
  4386.3    .035       0  4392.7     .07       0  4419.7    .035       0
  5002.8    .035       0  5010.6    .035       0  5415.5     .07       0
  5527.7     .12       0  5621.9     .07       0
Bank Sta=5002.8,5010.6
XS Rating Curve= 0 ,0
Exp/Cntr=0.3,0.1

Type RM Length L Ch R = 1 ,32558   ,467,467,467
BEGIN DESCRIPTION:
Bear Creek 61.0
END DESCRIPTION:
XS GIS Cut Line= 3
       2183374.8     13796609.16        2183175.       13796025.
      2182610.65     13795470.45
#Sta/Elev= 30
  4382.9   953.7  4545.8  945.93  4640.3  939.28    4884  924.91    4921  921.47
  4947.4   917.1  4953.3  915.36  4958.6   911.7  4979.2  904.24  4984.6  900.19
  5017.6  899.11  5018.1  898.61  5025.4  899.11  5035.6  902.45  5056.8  903.85
  5063.9  906.18  5078.1  907.97  5135.5  911.29  5148.8  910.81    5170  907.93
  5177.6  908.42  5198.2  909.12  5233.7  908.32  5254.8  912.53  5382.1  913.98
  5445.8  915.74  5570.2  918.82  5636.7  920.84    5714  925.59  5791.5   930.6
#Mann= 8 ,-1 , 0
  4382.9     .12       0  5017.6     .05       0  5025.4     .12       0
  5135.5     .07       0  5177.6    .035       0  5445.8     .07       0
  5570.2     .12       0    5714     .07       0
Bank Sta=5017.6,5025.4
XS Rating Curve= 0 ,0
Exp/Cntr=0.3,0.1

Type RM Length L Ch R = 1 ,32091   ,444,444,444
BEGIN DESCRIPTION:
Bear Creek 60.0
END DESCRIPTION:
XS GIS Cut Line= 3
        2183525.       13795875.        2183375.       13795625.
      2182575.05     13795325.02
#Sta/Elev= 30
  4704.3  916.11  4770.4  912.65  4902.6  908.41  4914.2  906.98  4923.9  906.67
  4929.8  905.35  4944.4  904.07  4982.2  901.01  4988.1  900.07  4998.5  900.26
  5001.7  899.56  5002.2  899.06  5009.1  899.06  5009.6  899.56  5059.9  901.45
  5071.5  904.32  5092.1  905.88  5113.3  906.16  5145.4  904.43  5156.9  905.93
  5206.8  908.24  5331.8   910.8    5391  911.23  5468.4  913.36  5493.4  915.31
  5498.7  914.86  5561.9  917.26  5674.5  923.16  5724.8  925.78  5850.2  935.76
#Mann= 7 ,-1 , 0
  4704.3     .12       0  4944.4     .07       0  5001.7     .05       0
  5009.6     .07       0  5092.1    .035       0  5331.8     .12       0
  5674.5     .07       0
Bank Sta=5001.7,5009.6
XS Rating Curve= 0 ,0
Exp/Cntr=0.3,0.1

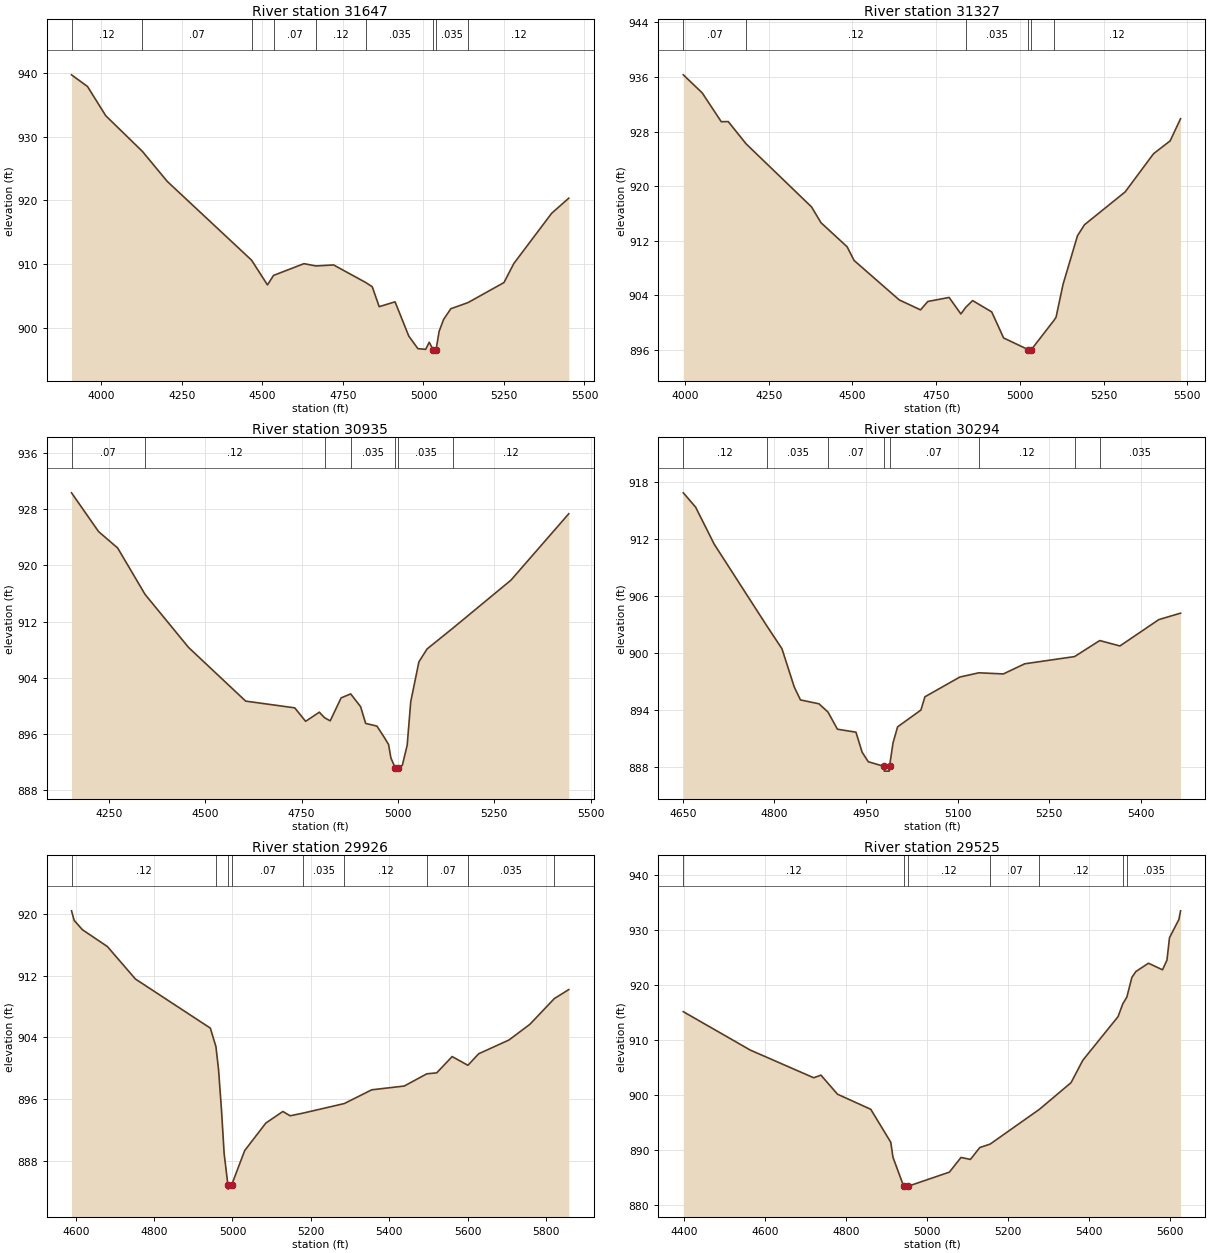
Type RM Length L Ch R = 1 ,31647   ,320,320,320
BEGIN DESCRIPTION:
Bear Creek 59.0
END DESCRIPTION:
XS GIS Cut Line= 3
      2184225.02     13795975.02        2183425.       13795225.
      2183225.01     13794825.02
#Sta/Elev= 30
  3907.4  939.69    3957  937.86  4013.7  933.28  4127.5  927.69  4204.6  922.99
  4466.3  910.65  4515.8  906.77  4534.6  908.26  4629.1   910.1  4666.2  909.74
    4721   909.9  4820.7  907.15  4841.1  906.48  4862.6  903.36  4911.9  904.12
  4954.4  898.76  4982.8  896.78  5006.8  896.67    5018  897.78  5030.5  896.58
    5031  896.08    5039  896.58  5048.7   899.5  5062.7  901.37  5085.1  903.04
  5138.5     904    5250  907.14  5280.7  910.13  5398.1     918  5451.2  920.36
#Mann= 9 ,-1 , 0
  3907.4     .12       0  4127.5     .07       0  4466.3     .12       0
  4534.6     .07       0  4666.2     .12       0  4820.7    .035       0
  5030.5    .035       0    5039    .035       0  5138.5     .12       0
Bank Sta=5030.5,5039
XS Rating Curve= 0 ,0
Exp/Cntr=0.3,0.1

Type RM Length L Ch R = 1 ,31327   ,392,392,392
BEGIN DESCRIPTION:
Bear Creek 58.0
END DESCRIPTION:
XS GIS Cut Line= 3
      2184345.02     13795624.93      2183545.03     13794924.94
      2183279.93     13794596.47
#Sta/Elev= 30
  3994.7  936.31  4051.1  933.67  4108.1  929.44    4129  929.46    4182  926.21
  4377.6  916.96  4406.1  914.63  4483.9  911.12  4504.8  909.11  4639.6  903.33
  4703.2  901.87    4725   903.1  4788.6  903.69  4823.7  901.27  4838.2  902.24
  4858.8  903.23  4915.8  901.57  4951.4  897.75  5025.4  896.03  5025.9  895.53
  5033.9  896.03  5101.4  900.31    5108  900.79  5128.8   905.6    5172  912.73
  5192.8  914.34  5314.3  919.15  5399.1  924.75  5448.7  926.63  5479.8  929.88
#Mann= 6 ,-1 , 0
  3994.7     .07       0    4182     .12       0  4838.2    .035       0
  5025.4    .035       0  5033.9    .035       0  5101.4     .12       0
Bank Sta=5025.4,5033.9
XS Rating Curve= 0 ,0
Exp/Cntr=0.3,0.1

Type RM Length L Ch R = 1 ,30935   ,641,641,641
BEGIN DESCRIPTION:
Bear Creek 57.0
END DESCRIPTION:
XS GIS Cut Line= 3
      2184388.68     13795330.64      2183859.26      13794816.2
      2183559.79     13794352.02
#Sta/Elev= 30
    4153  930.35  4223.3  924.82  4272.7  922.49  4343.9  915.87  4456.6  908.32
    4605  900.66  4732.3   899.7  4760.6  897.78  4796.1  899.08  4809.8  898.29
  4824.4  897.85  4852.7  901.12  4877.6  901.69  4903.4  899.86  4916.4  897.48
  4945.7   897.1  4966.8  895.31  4975.9  894.47    4982  892.55  4992.8  891.18
  4993.3  890.68  5001.4  891.18  5011.6  891.51  5024.2  894.38  5033.4  900.57
  5054.6  906.25  5075.7  908.09  5143.7   911.1  5293.5   917.9  5443.6  927.37
#Mann= 7 ,-1 , 0
    4153     .07       0  4343.9     .12       0  4809.8     .07       0
  4877.6    .035       0  4992.8    .035       0  5001.4    .035       0
  5143.7     .12       0
Bank Sta=4992.8,5001.4
XS Rating Curve= 0 ,0
Exp/Cntr=0.3,0.1

Type RM Length L Ch R = 1 ,30294   ,368,368,368
BEGIN DESCRIPTION:
Bear Creek 56.0
END DESCRIPTION:
XS GIS Cut Line= 3
        2184475.       13795025.        2184425.       13794675.
      2184075.02     13794375.02
#Sta/Elev= 30
  4650.7   916.9  4670.9  915.39  4701.2   911.5  4787.9  902.83  4812.3  900.46
  4832.5  896.41  4842.6  895.06  4872.9  894.65  4887.7  893.78  4903.2  891.97
  4933.5  891.66  4943.6  889.55  4953.7  888.54  4979.5  888.05    4980  887.55
    4988  887.55  4988.5  888.05  4994.2  890.52  5001.7  892.22  5039.9  893.99
  5046.5  895.39  5103.6  897.47  5134.8  897.92  5174.9   897.8    5210  898.87
  5291.6  899.63  5332.8  901.32  5365.9  900.75  5429.6  903.53  5465.2  904.21
#Mann= 8 ,-1 , 0
  4650.7     .12       0  4787.9    .035       0  4887.7     .07       0
  4979.5     .05       0  4988.5     .07       0  5134.8     .12       0
  5291.6     .07       0  5332.8    .035       0
Bank Sta=4979.5,4988.5
XS Rating Curve= 0 ,0
Exp/Cntr=0.3,0.1

Type RM Length L Ch R = 1 ,29926   ,401,401,401
BEGIN DESCRIPTION:
Bear Creek 55.0
END DESCRIPTION:
XS GIS Cut Line= 3
        2184998.     13794931.11      2184733.27     13794616.43
      2183939.55     13794291.95
#Sta/Elev= 30
  4589.3  920.39  4596.2  919.14  4617.1  917.94  4680.8  915.76  4752.3  911.55
  4943.5  905.18  4957.7  902.79  4964.4  899.82  4972.1  894.45  4978.7  888.91
  4988.4   884.8  4988.9   884.3  4997.5   884.8  5031.1   889.3  5085.1  892.87
  5128.5  894.37  5147.1  893.81  5180.3  894.16  5285.4   895.4  5355.2  897.18
  5438.3  897.67  5495.6  899.25  5521.1  899.38  5560.4  901.49  5600.7  900.36
    5628  901.85  5705.4  903.64  5758.9  905.68  5821.1  909.01    5858  910.18
#Mann= 9 ,-1 , 0
  4589.3     .12       0  4957.7     .07       0  4988.4     .05       0
  4997.5     .07       0  5180.3    .035       0  5285.4     .12       0
  5495.6     .07       0  5600.7    .035       0  5821.1     .12       0
Bank Sta=4988.4,4997.5
XS Rating Curve= 0 ,0
Exp/Cntr=0.3,0.1

Type RM Length L Ch R = 1 ,29525   ,558,558,558
BEGIN DESCRIPTION:
X18100
END DESCRIPTION:
XS GIS Cut Line= 3
      2185042.93     13794846.22      2184933.05      13794376.7
       2184629.2     13793694.29
#Sta/Elev= 30
  4397.7  915.18  4563.3   908.2  4720.1  903.17  4737.9  903.65  4778.9  900.18
  4861.1  897.44  4910.6  891.44    4916  888.72  4942.6  883.43  4943.1  882.93
  4952.3  883.43  5055.5  886.02  5084.2  888.69  5107.4  888.33  5130.7  890.49
  5156.1  891.11  5278.1  897.44  5356.2  902.28  5385.3  906.35  5472.4  914.28
  5484.1  916.61  5494.1  917.82  5506.6  921.42  5516.7  922.49  5547.6  923.99
  5582.3  922.79  5593.3  924.55  5599.6  928.63  5622.8  931.94  5626.9  933.51
#Mann= 7 ,-1 , 0
  4397.7     .12       0  4942.6     .05       0  4952.3     .12       0
  5156.1     .07       0  5278.1     .12       0  5484.1     .07       0
  5494.1    .035       0
Bank Sta=4942.6,4952.3
XS Rating Curve= 0 ,0
Exp/Cntr=0.3,0.1