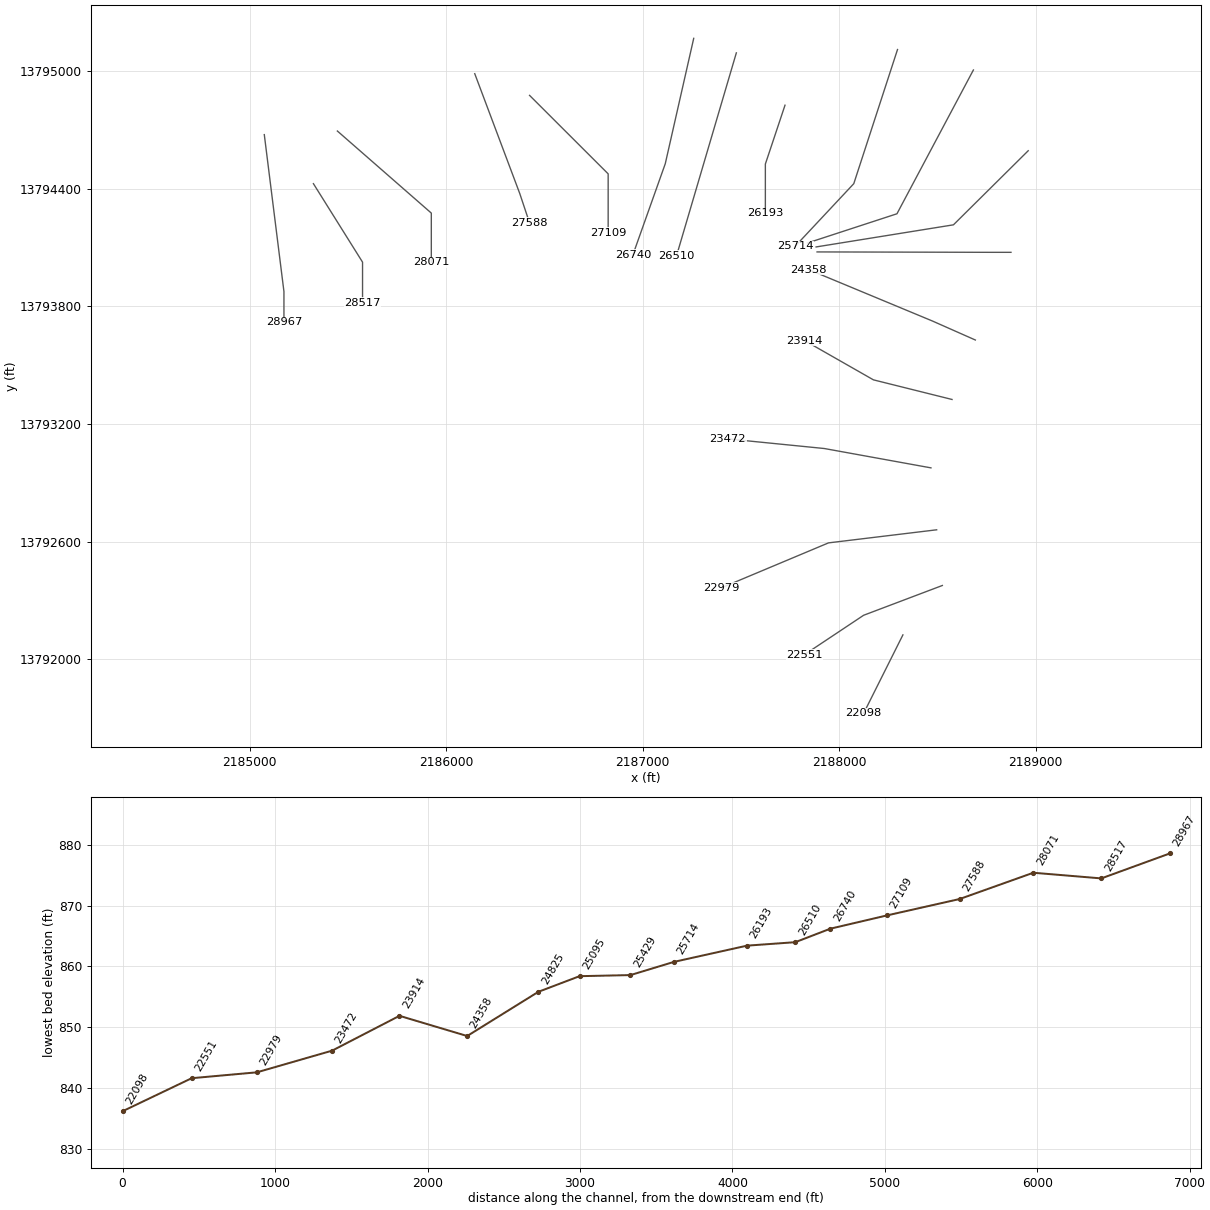
HEC-RAS study Bear Creek.prj: Bear Creek Base Level Engineering

--- Bear Creek.g01 (geometry) --- (continued)

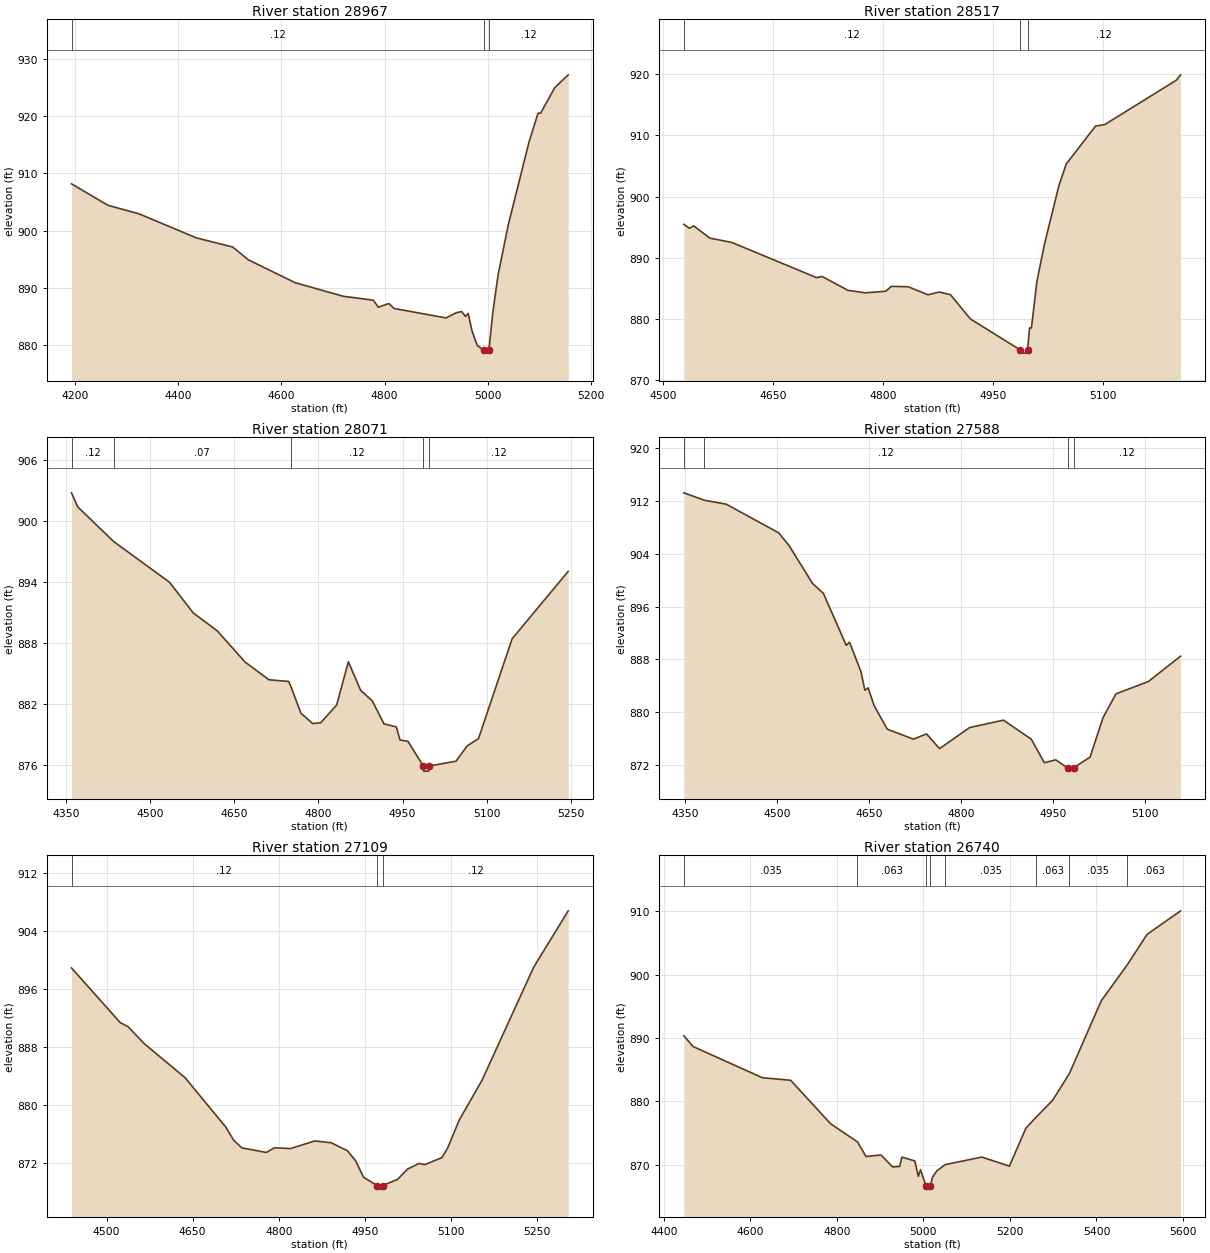
Type RM Length L Ch R = 1 ,28967   ,450,450,450
BEGIN DESCRIPTION:
Bear Creek 54.0
END DESCRIPTION:
XS GIS Cut Line= 4
        2185075.     13794675.03        2185175.       13793875.
        2185175.       13793775.        2185175.     13793718.96
#Sta/Elev= 30
  4193.3  908.17  4263.9  904.42  4324.3  902.92  4435.2  898.72  4505.7  897.12
    4536  894.88  4626.7  890.88  4719.9  888.51  4777.8  887.83  4787.9   886.6
  4808.1  887.25  4818.2  886.38  4918.9  884.72  4939.1  885.65  4949.2  885.83
  4956.7  884.98  4961.8   885.5  4969.3  882.43  4979.4  879.91  4992.2  879.07
  4992.7  878.57  5001.9  879.07  5009.6  885.72  5019.6  892.19  5039.6  901.07
  5079.6  915.46  5097.1  920.52  5102.1  920.52  5129.6     925  5155.6  927.23
#Mann= 3 ,-1 , 0
  4193.3     .12       0  4992.2     .05       0  5001.9     .12       0
Bank Sta=4992.2,5001.9
XS Rating Curve= 0 ,0
Exp/Cntr=0.3,0.1

Type RM Length L Ch R = 1 ,28517   ,446,446,446
BEGIN DESCRIPTION:
Bear Creek 53.0
END DESCRIPTION:
XS GIS Cut Line= 4
      2185325.01     13794424.99        2185575.       13794025.
        2185575.       13793925.        2185575.     13793818.98
#Sta/Elev= 30
    4528  895.47  4535.6  894.84  4541.5  895.22  4563.4  893.22  4593.4  892.52
    4709  886.78  4716.7  886.96    4752   884.7  4775.6   884.3  4803.3  884.55
    4811  885.35    4834  885.29  4861.1  883.98  4876.5  884.43  4891.8  883.99
  4918.9  880.04  4987.2  874.96  4987.7  874.46  4996.4  874.46  4996.9  874.96
  4999.7  878.57  5002.2  878.57  5009.7  886.14  5019.7  892.07  5039.7  901.78
  5049.7  905.31  5089.7   911.5  5102.2  911.74  5199.7  918.97  5205.7  919.86
#Mann= 3 ,-1 , 0
    4528     .12       0  4987.2     .05       0  4996.9     .12       0
Bank Sta=4987.2,4996.9
XS Rating Curve= 0 ,0
Exp/Cntr=0.3,0.1

Type RM Length L Ch R = 1 ,28071   ,483,483,483
BEGIN DESCRIPTION:
Bear Creek 52.0
END DESCRIPTION:
XS GIS Cut Line= 4
      2185446.93     13794693.31        2185525.       13794625.
        2185925.       13794275.        2185925.     13794025.05
#Sta/Elev= 30
  4360.1   902.8  4371.3  901.41  4435.1  898.01  4534.6     894  4577.3  890.96
    4620   889.2  4669.3  886.14    4712  884.39  4747.2  884.22  4750.9  883.75
    4769  881.09  4789.9  880.08  4804.1  880.15  4832.6   881.9  4853.5  886.16
  4875.3  883.36  4896.2   882.3    4917  880.04  4938.9  879.75  4945.5  878.46
  4959.8  878.32  4987.1  875.89  4987.6  875.39  4996.5  875.39    4997  875.89
  5045.3  876.37  5065.3  877.88  5085.3  878.58  5145.3  888.42  5245.3  895.07
#Mann= 5 ,-1 , 0
  4360.1     .12       0  4435.1     .07       0  4750.9     .12       0
  4987.1     .05       0    4997     .12       0
Bank Sta=4987.1,4997
XS Rating Curve= 0 ,0
Exp/Cntr=0.3,0.1

Type RM Length L Ch R = 1 ,27588   ,479,479,479
BEGIN DESCRIPTION:
Bear Creek 51.0
END DESCRIPTION:
XS GIS Cut Line= 4
      2186146.04     13794985.57        2186225.       13794775.
        2186375.       13794375.        2186425.       13794225.
#Sta/Elev= 30
  4347.5  913.27  4380.8  912.15  4416.6  911.55  4502.1  907.21    4519  905.29
  4557.3  899.54  4575.1  898.02  4612.4  890.14  4617.8  890.61  4636.5  886.12
  4642.7  883.33    4648   883.7  4657.8  881.02  4679.2  877.44  4721.9  875.92
  4743.3  876.71  4764.6  874.48  4813.6  877.68  4868.8   878.8  4914.1  875.92
  4935.5  872.35  4954.2  872.78  4973.3  871.57  4973.8  871.07  4983.2  871.57
  5010.1   873.2  5031.2  879.17  5052.3  882.79    5105  884.65  5157.7   888.5
#Mann= 4 ,-1 , 0
  4347.5     .07       0  4380.8     .12       0  4973.3     .05       0
  4983.2     .12       0
Bank Sta=4973.3,4983.2
XS Rating Curve= 0 ,0
Exp/Cntr=0.3,0.1

Type RM Length L Ch R = 1 ,27109   ,369,369,369
BEGIN DESCRIPTION:
Bear Creek 50.0
END DESCRIPTION:
XS GIS Cut Line= 3
      2186425.03     13794874.97        2186825.       13794475.
        2186825.     13794175.04
#Sta/Elev= 30
  4438.9  898.88  4523.7  891.35  4537.8  890.75  4566.1   888.4  4636.8  883.74
  4707.6  876.94  4721.7  875.09  4735.8  874.05  4778.3  873.42  4792.4  874.06
  4820.7  873.96  4863.1  875.01  4891.4  874.76  4919.7  873.66  4933.8  872.29
    4948  869.99  4971.3  868.86  4971.8  868.36  4980.7  868.36  4981.2  868.86
    5007   869.7  5024.5  871.13  5044.5   871.9  5054.5  871.74  5084.5  872.71
  5094.5  874.06  5114.5  877.88  5154.5  883.42  5244.5  899.01  5304.5  906.76
#Mann= 3 ,-1 , 0
  4438.9     .12       0  4971.3     .05       0  4981.2     .12       0
Bank Sta=4971.3,4981.2
XS Rating Curve= 0 ,0
Exp/Cntr=0.3,0.1

Type RM Length L Ch R = 1 ,26740   ,230,230,230
BEGIN DESCRIPTION:
Bear Creek 49.0
END DESCRIPTION:
XS GIS Cut Line= 3
      2187260.41     13795165.77      2187115.58     13794526.53
      2186950.76     13794062.04
#Sta/Elev= 30
  4446.2  890.36  4467.5  888.66  4627.8  883.74  4693.1  883.34  4785.3   876.5
  4847.5  873.64  4867.4  871.33  4901.9  871.57  4928.9  869.69  4945.1  869.77
  4950.2  871.23  4980.2  870.63  4988.2   868.2  4993.3  869.25  5005.9  866.69
  5006.4  866.19  5015.9  866.69  5021.2  868.09  5031.3  869.09  5050.3  870.05
  5135.1  871.24  5198.8  869.81  5236.9  875.79  5259.8  877.47  5298.7  880.19
  5337.6  884.42    5411  895.85  5470.9   901.5  5517.1  906.33  5594.5  910.04
#Mann= 8 ,-1 , 0
  4446.2    .035       0  4847.5    .063       0  5005.9    .063       0
  5015.9    .063       0  5050.3    .035       0  5259.8    .063       0
  5337.6    .035       0  5470.9    .063       0
Bank Sta=5005.9,5015.9
XS Rating Curve= 0 ,0
Exp/Cntr=0.3,0.1

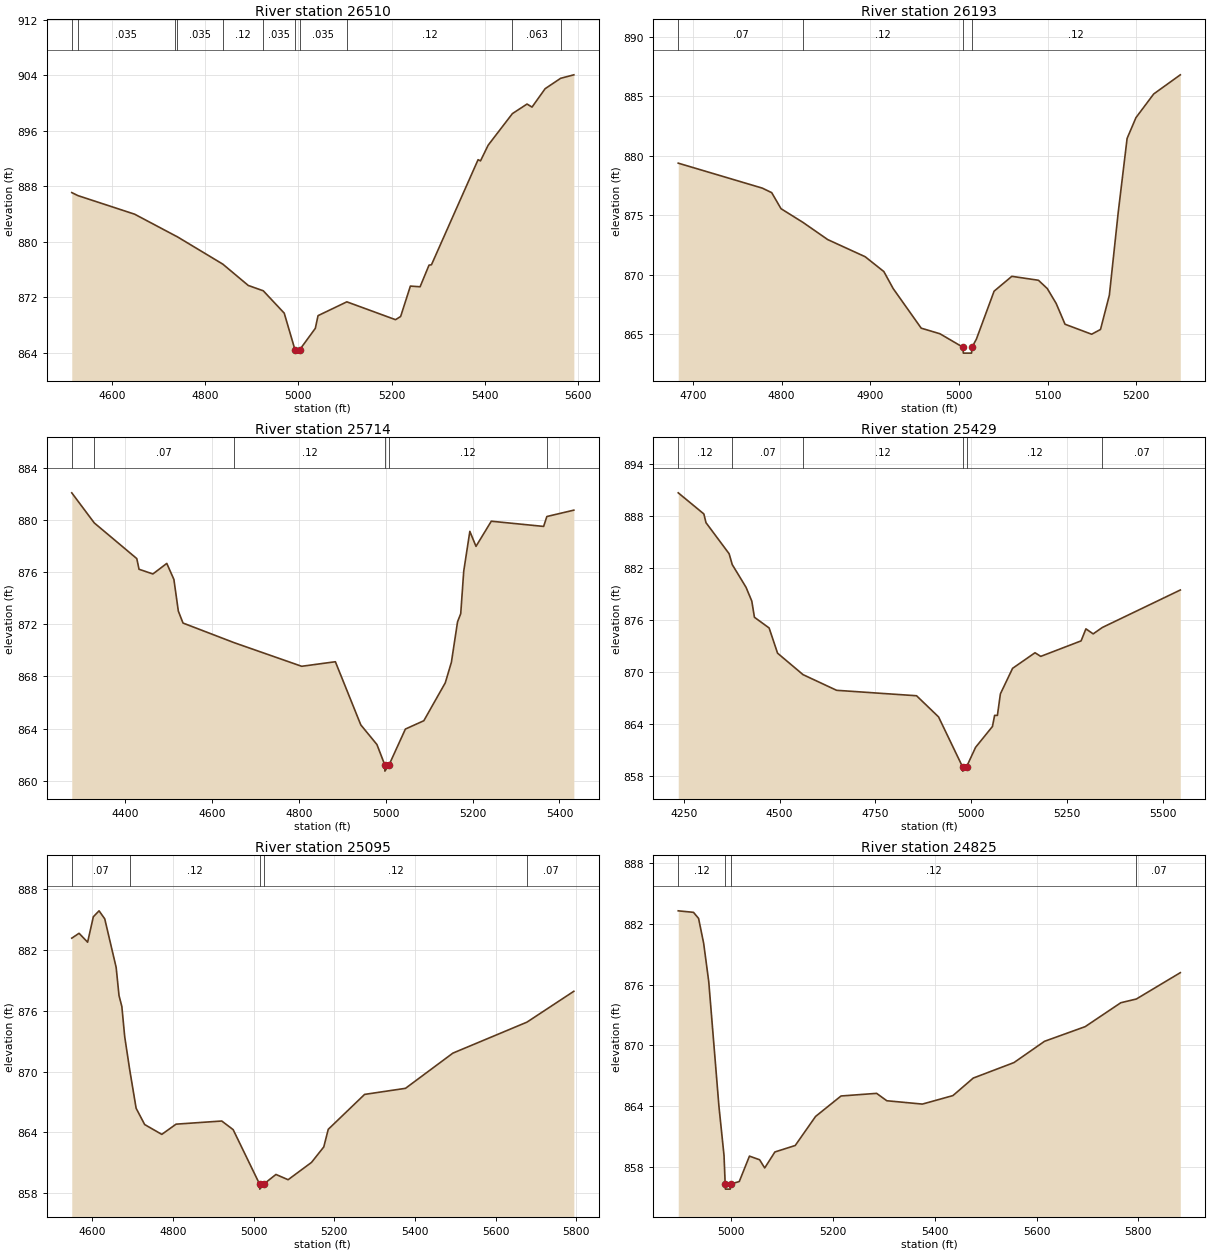
Type RM Length L Ch R = 1 ,26510   ,317,317,317
BEGIN DESCRIPTION:
X18103
END DESCRIPTION:
XS GIS Cut Line= 2
      2187477.32     13795091.74       2187173.3     13794058.65
#Sta/Elev= 30
  4513.9   887.1  4527.4  886.66  4648.7  883.99  4734.4  880.94  4740.2  880.74
  4837.9  876.79  4892.5  873.72  4924.7  872.95  4969.6  869.73  4992.6  864.47
  4993.1  863.97  5002.9  864.47  5036.3  867.54  5042.1  869.37  5103.9  871.36
  5208.3  868.79  5219.3  869.25  5240.2  873.63    5261  873.53  5280.2  876.65
  5285.4   876.7  5385.4  891.84  5390.6  891.67    5407  893.93    5459  898.48
  5490.4  899.86  5501.1  899.42  5529.2  902.07  5562.5  903.57  5590.8  904.07
#Mann= 11 ,-1 , 0
  4513.9    .063       0  4527.4    .035       0  4734.4     .12       0
  4740.2    .035       0  4837.9     .12       0  4924.7    .035       0
  4992.6    .035       0  5002.9    .035       0  5103.9     .12       0
    5459    .063       0  5562.5     .12       0
Bank Sta=4992.6,5002.9
XS Rating Curve= 0 ,0
Exp/Cntr=0.3,0.1

Type RM Length L Ch R = 1 ,26193   ,479,479,479
BEGIN DESCRIPTION:
Bear Creek 48.0
END DESCRIPTION:
XS GIS Cut Line= 3
      2187724.99     13794824.97        2187625.       13794525.
        2187625.       13794275.
#Sta/Elev= 30
  4683.4  879.38  4778.2  877.28  4788.8   876.9  4799.3  875.55  4824.2  874.39
    4852  872.95  4894.2  871.51  4915.3  870.26  4925.8  868.83  4957.4   865.5
  4978.5  865.03  5004.4   863.9  5004.9   863.4  5014.2   863.4  5014.7   863.9
  5019.6  864.57  5039.6  868.61  5059.6  869.86  5089.6  869.53  5099.6  868.83
  5109.6  867.58  5119.6  865.83  5149.6  864.99  5159.6  865.39  5169.6  868.28
  5179.6  875.25  5189.6  881.46  5199.6  883.21  5219.6   885.2  5249.6  886.81
#Mann= 4 ,-1 , 0
  4683.4     .07       0  4824.2     .12       0  5004.4     .05       0
  5014.7     .12       0
Bank Sta=5004.4,5014.7
XS Rating Curve= 0 ,0
Exp/Cntr=0.3,0.1

Type RM Length L Ch R = 1 ,25714   ,285,285,285
BEGIN DESCRIPTION:
Bear Creek 47.0
END DESCRIPTION:
XS GIS Cut Line= 3
      2188297.55     13795108.73        2188075.       13794425.
      2187776.11     13794105.29
#Sta/Elev= 30
  4276.4   882.1  4328.2  879.79  4426.2  877.05  4431.4  876.23  4463.3  875.87
  4495.3  876.68  4511.7  875.45  4521.9  873.02  4532.7   872.1  4650.8  870.59
  4806.1  868.78  4883.7  869.13  4942.3  864.28  4979.5  862.77  4997.3  861.23
  4997.8  860.73  5007.7  861.23    5045  863.96  5087.5   864.6  5136.9  867.51
    5151  869.09  5165.2   872.2  5172.5  872.82  5179.4  876.08  5193.5  879.14
  5207.7  877.99  5242.9  879.92  5363.5  879.52  5370.9  880.28  5433.1  880.77
#Mann= 6 ,-1 , 0
  4276.4     .12       0  4328.2     .07       0  4650.8     .12       0
  4997.3     .05       0  5007.7     .12       0  5370.9     .07       0
Bank Sta=4997.3,5007.7
XS Rating Curve= 0 ,0
Exp/Cntr=0.3,0.1

Type RM Length L Ch R = 1 ,25429   ,334,334,334
BEGIN DESCRIPTION:
X18101
END DESCRIPTION:
XS GIS Cut Line= 3
      2188683.71     13795004.45      2188294.72     13794271.57
       2187839.1     13794122.51
#Sta/Elev= 30
  4235.8  890.72  4302.6  888.28  4308.2  887.27  4368.5  883.68  4376.6  882.43
  4412.5  879.81  4427.6  878.21  4434.5  876.34  4472.8   875.1  4494.8  872.19
  4561.2  869.71  4648.7   867.9  4857.2  867.27  4914.5  864.83  4977.1  859.06
  4977.6  858.56  4987.6  859.06  5011.1  861.31  5055.1  863.72  5060.7     865
    5068     865  5075.8  867.49  5107.6  870.44  5166.1  872.24    5181  871.82
  5286.2  873.61  5298.8     875  5317.7  874.42  5341.6  875.16  5544.9  879.49
#Mann= 6 ,-1 , 0
  4235.8     .12       0  4376.6     .07       0  4561.2     .12       0
  4977.1     .05       0  4987.6     .12       0  5341.6     .07       0
Bank Sta=4977.1,4987.6
XS Rating Curve= 0 ,0
Exp/Cntr=0.3,0.1

Type RM Length L Ch R = 1 ,25095   ,270,270,270
BEGIN DESCRIPTION:
X18102
END DESCRIPTION:
XS GIS Cut Line= 3
      2188962.71     13794592.87      2188582.22      13794215.2
      2187883.16     13794102.45
#Sta/Elev= 30
  4549.4  883.18  4567.5  883.66  4588.7  882.78  4602.8  885.29    4617  885.88
  4631.1  885.09  4659.4  880.29  4666.5   877.5  4673.5  876.43  4680.6  873.44
  4692.8  870.22  4708.9  866.37  4730.1  864.76  4772.5  863.79  4807.9   864.8
  4921.1  865.11  4949.3  864.26  5014.8  858.88  5015.3  858.38  5025.3  858.88
  5055.4  859.83  5085.5  859.31  5143.5  861.02  5173.9  862.55    5185  864.29
  5275.1  867.74  5376.4  868.34  5493.9  871.82  5677.4  874.88  5793.6  877.93
#Mann= 5 ,-1 , 0
  4549.4     .07       0  4692.8     .12       0  5014.8     .05       0
  5025.3     .12       0  5677.4     .07       0
Bank Sta=5014.8,5025.3
XS Rating Curve= 0 ,0
Exp/Cntr=0.3,0.1

Type RM Length L Ch R = 1 ,24825   ,467,467,467
BEGIN DESCRIPTION:
Bear Creek 46.0
END DESCRIPTION:
XS GIS Cut Line= 3
      2188875.03       13794075.        2188775.       13794075.
      2187888.04     13794077.08
#Sta/Elev= 30
  4895.5   883.3  4925.5  883.15  4935.5  882.55  4945.5  880.09  4955.5   876.3
  4975.5     864  4985.5  859.14  4987.8  856.31  4988.3  855.81  4997.8  855.81
  4998.3  856.31  5015.5  856.56  5035.5  859.07  5055.5  858.71  5065.5   857.9
  5085.5  859.48  5125.5  860.12  5165.5  862.99  5215.5  865.01  5285.5  865.27
  5305.5  864.54  5375.5  864.21  5435.5  865.05  5475.5  866.78  5555.5  868.31
  5615.5  870.41  5695.5  871.86  5765.5  874.22  5796.1  874.59  5882.5  877.19
#Mann= 4 ,-1 , 0
  4895.5     .12       0  4987.8     .05       0  4998.3     .12       0
  5796.1     .07       0
Bank Sta=4987.8,4998.3
XS Rating Curve= 0 ,0
Exp/Cntr=0.3,0.1

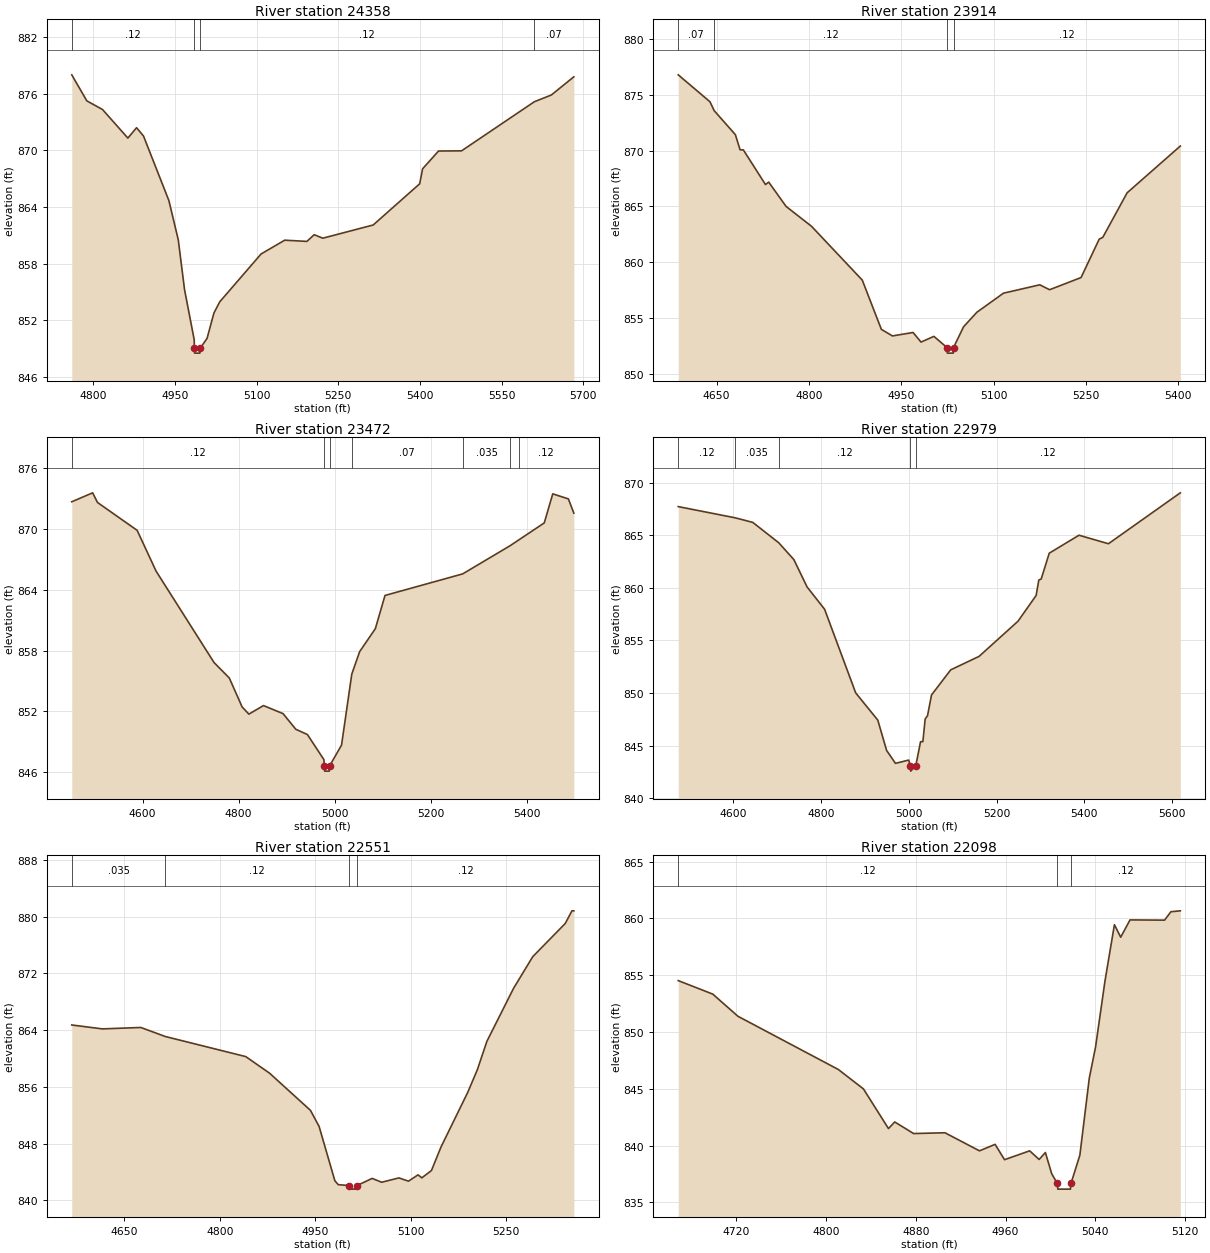
Type RM Length L Ch R = 1 ,24358   ,444,444,444
BEGIN DESCRIPTION:
Bear Creek 45.0
END DESCRIPTION:
XS GIS Cut Line= 3
      2188693.69     13793628.06        2188475.       13793725.
      2187845.01     13793987.23
#Sta/Elev= 30
  4760.8  878.01  4788.5  875.25  4817.2  874.34  4863.8  871.31  4879.7  872.41
  4892.5  871.53  4939.1  864.69  4956.3  860.54  4967.8  855.27  4985.6  849.94
  4985.8  849.04  4986.3  848.54  4995.9  848.54  4996.4  849.04  5009.2  850.11
  5021.7  852.78  5032.5  853.98  5108.3  859.04  5151.7   860.5  5192.4  860.37
  5205.8  861.08  5221.6  860.71  5314.1  862.11  5399.4  866.47  5404.8  868.06
    5434  869.94  5476.3  869.96  5609.9  875.16    5641  875.87  5682.4   877.8
#Mann= 4 ,-1 , 0
  4760.8     .12       0  4985.8     .05       0  4996.4     .12       0
  5609.9     .07       0
Bank Sta=4985.8,4996.4
XS Rating Curve= 0 ,0
Exp/Cntr=0.3,0.1

Type RM Length L Ch R = 1 ,23914   ,442,442,442
BEGIN DESCRIPTION:
Bear Creek 44.0
END DESCRIPTION:
XS GIS Cut Line= 3
        2188575.       13793325.        2188175.       13793425.
      2187825.02     13793624.99
#Sta/Elev= 30
  4587.7  876.79  4639.2  874.38  4646.1  873.58  4680.5  871.43  4688.2  870.07
  4693.4  870.07  4729.4  866.96  4734.6  867.18  4762.9     865  4804.2  863.22
  4886.6   858.4  4917.6  853.99  4935.6   853.4  4969.1  853.71    4982  852.85
  5002.9  853.36  5024.2  852.36  5024.7  851.86  5034.3  851.86  5034.8  852.36
  5051.1  854.22  5072.7  855.52  5115.9  857.23  5174.9  857.98  5190.8  857.54
  5241.9  858.63  5271.4  862.07  5277.2  862.23  5316.7  866.22  5403.1  870.41
#Mann= 4 ,-1 , 0
  4587.7     .07       0  4646.1     .12       0  5024.2     .05       0
  5034.8     .12       0
Bank Sta=5024.2,5034.8
XS Rating Curve= 0 ,0
Exp/Cntr=0.3,0.1

Type RM Length L Ch R = 1 ,23472   ,493,493,493
BEGIN DESCRIPTION:
Bear Creek 43.0
END DESCRIPTION:
XS GIS Cut Line= 3
      2188467.78     13792976.37        2187925.       13793075.
      2187433.71      13793124.1
#Sta/Elev= 30
  4452.5  872.64    4496  873.52  4506.1  872.57  4588.6  869.83  4628.1  865.81
  4748.7  856.82  4780.6  855.29  4807.2  852.45  4821.2  851.74  4851.7  852.58
  4892.4  851.79    4919  850.25  4943.2  849.73  4977.5  847.26  4978.5  846.63
    4979  846.13  4988.7  846.13  4989.2  846.63  5014.2  848.69  5035.5  855.67
  5051.9  857.89  5084.6  860.15  5104.7  863.42  5266.4  865.54  5365.7  868.33
  5382.8  868.87  5436.3  870.56    5454  873.42  5486.6  872.92  5497.9  871.52
#Mann= 7 ,-1 , 0
  4452.5     .12       0  4978.5     .05       0  4989.2     .12       0
  5035.5     .07       0  5266.4    .035       0  5365.7     .07       0
  5382.8     .12       0
Bank Sta=4978.5,4989.2
XS Rating Curve= 0 ,0
Exp/Cntr=0.3,0.1

Type RM Length L Ch R = 1 ,22979   ,428,428,428
BEGIN DESCRIPTION:
X18104
END DESCRIPTION:
XS GIS Cut Line= 3
      2188496.77     13792660.67      2187946.42     13792594.05
      2187401.91     13792365.24
#Sta/Elev= 30
  4474.1  867.72  4604.5  866.65  4644.1  866.22  4703.4  864.28  4737.8  862.68
    4768  860.08  4807.9  857.96  4878.8  850.01  4929.2  847.42  4949.3  844.54
  4969.5  843.31  4999.7  843.62  5003.7  843.07  5004.2  842.57  5015.8  843.07
  5026.7  845.37    5032  845.37  5037.2  847.52  5042.6  847.84  5051.7  849.81
  5095.5   852.2  5160.2  853.48  5248.9  856.82  5290.3  859.27  5296.4  860.74
  5301.8  860.83  5320.2  863.29    5388     865  5455.2  864.19  5619.1  869.03
#Mann= 5 ,-1 , 0
  4474.1     .12       0  4604.5    .035       0  4703.4     .12       0
  5003.7     .05       0  5015.8     .12       0
Bank Sta=5003.7,5015.8
XS Rating Curve= 0 ,0
Exp/Cntr=0.3,0.1

Type RM Length L Ch R = 1 ,22551   ,453,453,453
BEGIN DESCRIPTION:
Bear Creek 42.0
END DESCRIPTION:
XS GIS Cut Line= 3
      2188525.74     13792376.84        2188125.       13792225.
        2187825.       13792025.
#Sta/Elev= 30
  4567.5  864.72  4615.7  864.17    4676  864.37  4714.4   863.1  4840.9  860.27
  4878.4  857.93  4942.6   852.7  4956.2  850.44    4981  842.78  4986.3  842.23
  5003.5   842.1    5004   841.6  5015.2   841.6  5015.7   842.1  5039.6  843.11
  5054.6  842.57  5081.7  843.18  5096.7  842.72  5111.7  843.61  5117.7  843.19
  5132.8  844.22  5147.8  847.53  5189.8  855.22  5204.9  858.41  5219.9  862.41
  5261.9  869.89    5292  874.34  5343.1  879.02  5353.6   880.8  5356.6   880.8
#Mann= 4 ,-1 , 0
  4567.5    .035       0  4714.4     .12       0  5003.5     .05       0
  5015.7     .12       0
Bank Sta=5003.5,5015.7
XS Rating Curve= 0 ,0
Exp/Cntr=0.3,0.1

Type RM Length L Ch R = 1 ,22098   ,453,453,453
BEGIN DESCRIPTION:
Bear Creek 41.0
END DESCRIPTION:
XS GIS Cut Line= 3
      2188325.02     13792125.04        2188175.       13791825.
      2188124.98     13791724.96
#Sta/Elev= 30
  4668.4  854.52  4699.2  853.33  4721.6  851.38    4811   846.7  4833.4  844.99
  4855.7   841.5  4861.3  842.08  4878.1  841.06    4906  841.13  4936.8  839.54
  4950.7  840.11  4959.1  838.76  4981.5  839.54  4989.9  838.78  4995.5  839.39
  5001.1  837.53  5006.1  836.67  5006.6  836.17  5017.8  836.17  5018.3  836.67
  5026.2  839.15  5034.6  845.93  5040.2  848.68  5048.6  854.49    5057  859.44
  5062.6  858.34  5070.9  859.86  5101.7  859.84  5107.3  860.58  5115.7  860.66
#Mann= 3 ,-1 , 0
  4668.4     .12       0  5006.1     .05       0  5018.3     .12       0
Bank Sta=5006.1,5018.3
XS Rating Curve= 0 ,0
Exp/Cntr=0.3,0.1