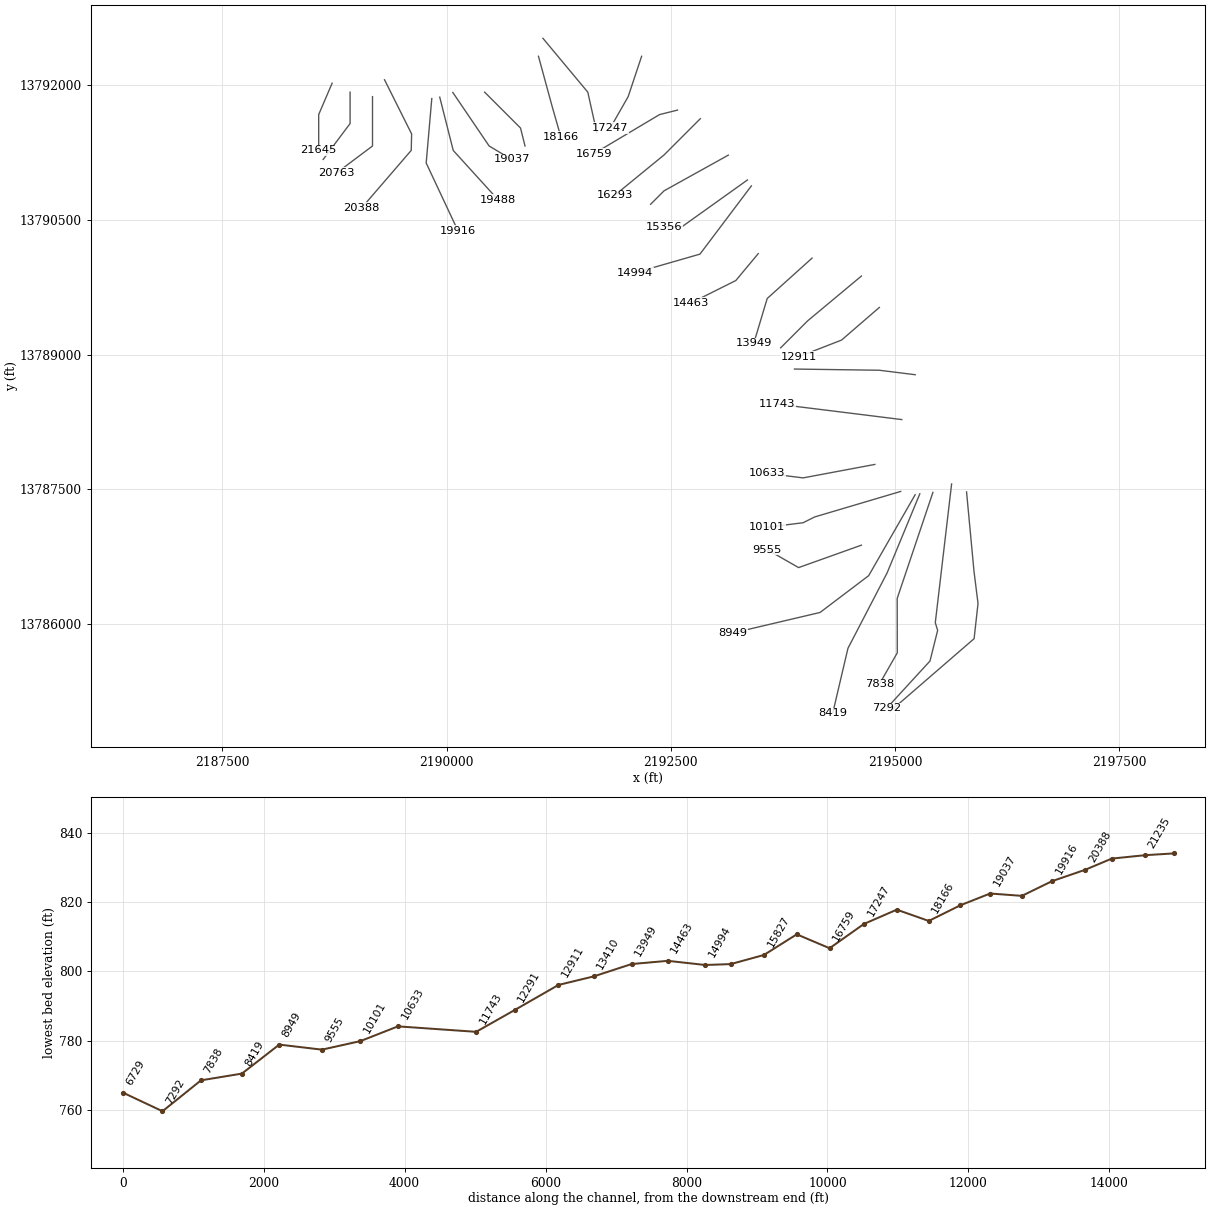
HEC-RAS study Bear Creek.prj: Bear Creek Base Level Engineering

--- Bear Creek.g01 (geometry) --- (continued)

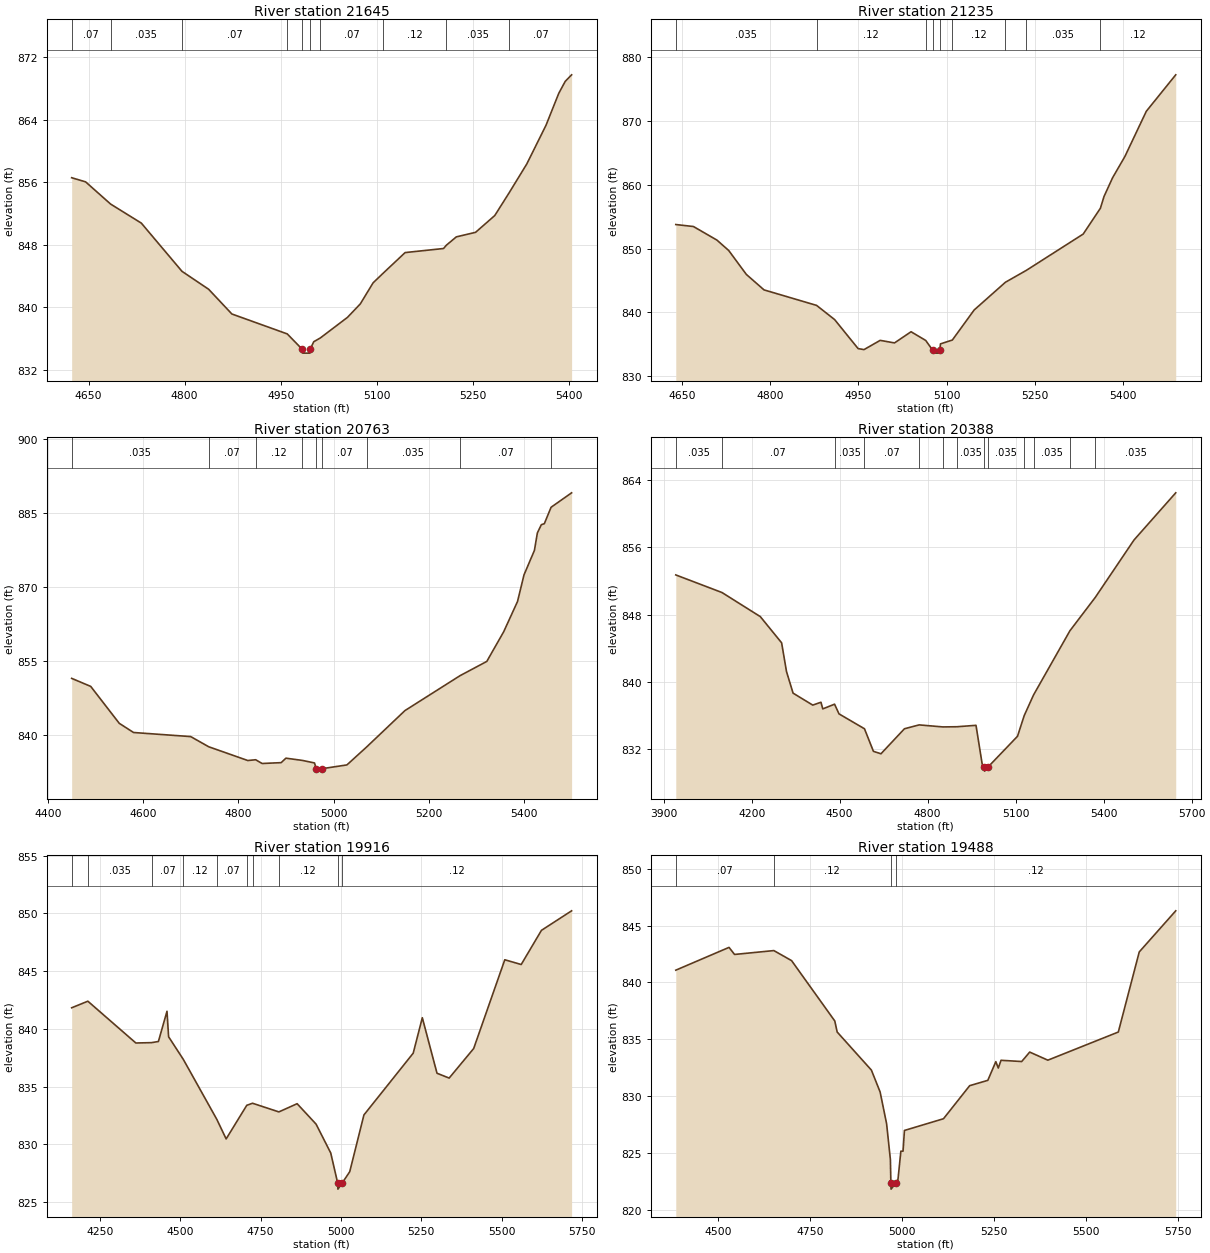
Type RM Length L Ch R = 1 ,21645   ,410,410,410
BEGIN DESCRIPTION:
Bear Creek 40.0
END DESCRIPTION:
XS GIS Cut Line= 3
        2188725.       13792025.        2188575.       13791675.
        2188575.     13791274.99
#Sta/Elev= 30
  4623.5  856.58  4645.3  856.05  4684.3  853.21  4732.3  850.77  4795.8   844.6
  4837.5   842.3  4873.7  839.14  4960.2  836.59  4983.5  834.63    4984  834.13
  4995.5  834.13    4996  834.63  5001.6  835.59    5012  836.08  5054.3  838.71
  5074.3  840.43  5094.3  843.13  5110.4  844.39  5144.3     847  5204.3  847.52
  5208.8  847.95  5224.3  849.01  5254.3  849.59  5284.3  851.74  5307.2  854.71
  5334.3  858.34  5364.3  863.29  5384.3  867.39  5394.3  868.91  5404.3  869.75
#Mann= 10 ,-1 , 0
  4623.5     .07       0  4684.3    .035       0  4795.8     .07       0
  4960.2     .12       0  4983.5     .05       0    4996     .12       0
    5012     .07       0  5110.4     .12       0  5208.8    .035       0
  5307.2     .07       0
Bank Sta=4983.5,4996
XS Rating Curve= 0 ,0
Exp/Cntr=0.3,0.1

Type RM Length L Ch R = 1 ,21235   ,472,472,472
BEGIN DESCRIPTION:
Bear Creek 39.0
END DESCRIPTION:
XS GIS Cut Line= 3
        2188925.     13791925.02        2188925.       13791575.
      2188625.01     13791175.01
#Sta/Elev= 30
  4639.7  853.76  4669.7  853.45  4709.7  851.32  4729.7  849.69  4759.7  845.94
  4789.7  843.52  4879.1  841.09  4909.7  838.87  4949.7  834.32  4959.7  834.16
  4987.2  835.61  5011.6  835.21  5039.7  836.96  5064.6   835.6  5076.2  834.11
  5076.7  833.61  5088.2  833.61  5088.7  834.11  5089.7  835.06  5109.9  835.66
    5147  840.37  5200.2  844.72  5235.7  846.58  5332.4  852.27  5361.6  856.31
  5367.8  858.16  5382.4   861.1  5403.3  864.43  5439.7  871.51  5489.7  877.22
#Mann= 9 ,-1 , 0
  4639.7    .035       0  4879.1     .12       0  5064.6     .07       0
  5076.2     .05       0  5088.7     .07       0  5109.9     .12       0
  5200.2     .07       0  5235.7    .035       0  5361.6     .12       0
Bank Sta=5076.2,5088.7
XS Rating Curve= 0 ,0
Exp/Cntr=0.3,0.1

Type RM Length L Ch R = 1 ,20763   ,375,375,375
BEGIN DESCRIPTION:
Bear Creek 38.0
END DESCRIPTION:
XS GIS Cut Line= 3
        2189175.     13791874.99        2189175.       13791325.
      2188774.99     13791024.99
#Sta/Elev= 30
    4450  851.46    4490  849.83    4550  842.33    4580  840.47    4700  839.64
    4738  837.57    4820  834.78  4836.4  834.94    4850  834.18    4890  834.35
    4900  835.26  4934.8   834.8    4960  834.29  4963.7  833.13  4964.2  832.63
  4976.2  833.13  5028.1  833.89  5069.7  837.55    5150  844.92  5265.6     852
  5321.9   854.9  5357.3  860.91  5386.4  867.06    5400  872.46  5421.9  877.43
  5428.1  880.98  5436.4  882.65  5442.7  882.85  5456.9  886.19    5500  889.12
#Mann= 9 ,-1 , 0
    4450    .035       0    4738     .07       0  4836.4     .12       0
  4934.8     .07       0  4963.7     .05       0  4976.2     .07       0
  5069.7    .035       0  5265.6     .07       0  5456.9     .12       0
Bank Sta=4963.7,4976.2
XS Rating Curve= 0 ,0
Exp/Cntr=0.3,0.1

Type RM Length L Ch R = 1 ,20388   ,472,472,472
BEGIN DESCRIPTION:
X18105
END DESCRIPTION:
XS GIS Cut Line= 4
      2189308.92     13792063.17      2189611.01     13791458.98
      2189606.67     13791275.82      2189054.59      13790635.2
#Sta/Elev= 30
  3941.4  852.71  4098.9  850.62  4229.5  847.76  4302.2  844.65  4318.9  841.23
  4341.3  838.67  4408.4  837.25  4436.3  837.59  4442.5   836.8  4482.7  837.36
  4497.8  836.21  4584.7  834.44  4615.2  831.76  4640.9  831.47  4720.9  834.44
  4771.1   834.9  4851.8  834.66  4899.7  834.68  4964.9  834.85    4986  830.24
  4993.7  829.91  4994.2  829.41  5006.3  829.91  5106.4  833.55  5129.1  835.99
    5161  838.45  5285.1  846.08  5371.9  850.06  5503.6  856.86  5645.8  862.46
#Mann= 13 ,-1 , 0
  3941.4    .035       0  4098.9     .07       0  4482.7    .035       0
  4584.7     .07       0  4771.1    .035       0  4851.8     .07       0
  4899.7    .035       0  4993.7    .035       0  5006.3    .035       0
  5129.1     .12       0    5161    .035       0  5285.1     .12       0
  5371.9    .035       0
Bank Sta=4993.7,5006.3
XS Rating Curve= 0 ,0
Exp/Cntr=0.3,0.1

Type RM Length L Ch R = 1 ,19916   ,428,428,428
BEGIN DESCRIPTION:
Bear Creek 37.0
END DESCRIPTION:
XS GIS Cut Line= 3
      2189835.83     13791853.91      2189773.34     13791135.19
      2190127.48     13790380.04
#Sta/Elev= 30
  4162.3  841.82  4212.7  842.39    4362  838.77  4410.8   838.8  4432.2   838.9
  4458.9  841.52  4463.9  839.31  4509.9  837.34    4614  832.15    4643  830.46
  4707.1  833.37  4725.1  833.55    4807   832.8  4863.8  833.51  4922.8  831.74
  4968.4  829.24  4990.2  826.61  4990.7  826.11  5003.3  826.61  5027.5  827.62
  5071.7  832.54    5225  837.89  5253.3  840.96    5299  836.15  5336.8  835.73
  5413.1  838.29  5509.9  845.98    5561  845.57    5624  848.53  5717.8  850.22
#Mann= 10 ,-1 , 0
  4162.3     .07       0  4212.7    .035       0  4410.8     .07       0
  4509.9     .12       0    4614     .07       0  4707.1     .12       0
  4725.1     .07       0    4807     .12       0  4990.2     .05       0
  5003.3     .12       0
Bank Sta=4990.2,5003.3
XS Rating Curve= 0 ,0
Exp/Cntr=0.3,0.1

Type RM Length L Ch R = 1 ,19488   ,451,451,451
BEGIN DESCRIPTION:
Bear Creek 36.0
END DESCRIPTION:
XS GIS Cut Line= 3
      2189924.38     13791869.58        2190075.       13791275.
      2190575.02     13790724.97
#Sta/Elev= 30
  4386.1  841.08  4530.6  843.08  4545.6  842.46  4652.2   842.8  4700.3  841.92
  4817.6  836.62  4824.1  835.65  4916.9  832.31  4940.6  830.39  4958.2   827.6
  4968.5  824.45  4969.8  822.36  4970.3  821.86  4982.9  822.36  4989.1  822.72
  4996.9  825.19  5002.8  825.19  5006.6  827.01  5112.6  828.04  5183.6  830.94
  5232.9  831.41  5254.6  833.05  5261.3  832.49  5268.7  833.17  5324.8  833.06
  5346.5  833.89  5395.8  833.18    5587  835.65  5643.8  842.68  5742.8  846.29
#Mann= 4 ,-1 , 0
  4386.1     .07       0  4652.2     .12       0  4969.8     .05       0
  4982.9     .12       0
Bank Sta=4969.8,4982.9
XS Rating Curve= 0 ,0
Exp/Cntr=0.3,0.1

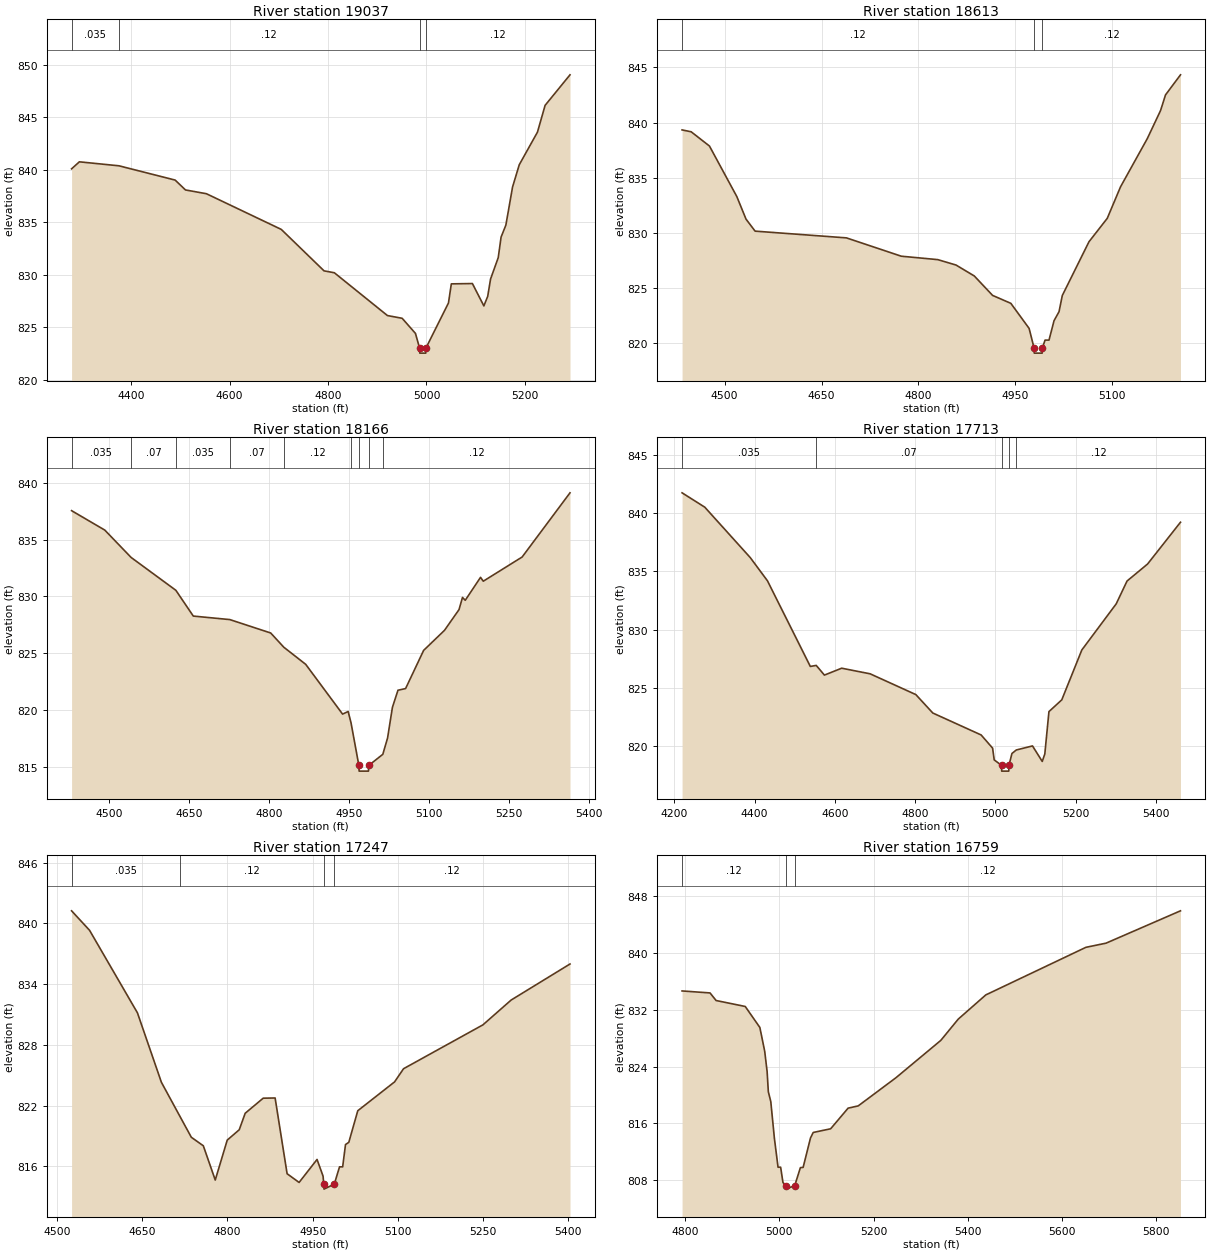
Type RM Length L Ch R = 1 ,19037   ,424,424,424
BEGIN DESCRIPTION:
Bear Creek 35.0
END DESCRIPTION:
XS GIS Cut Line= 3
      2190070.21     13791921.65        2190475.       13791325.
      2190725.04     13791174.98
#Sta/Elev= 30
    4279   840.1  4294.8  840.77  4375.3  840.39  4489.4  839.03  4510.4  838.09
  4552.9  837.73    4705  834.33  4791.9  830.38  4812.8   830.2  4920.7  826.12
  4950.6  825.86  4977.6  824.42  4985.9  823.04  4986.4  822.54  4998.6  822.54
  4999.1  823.04  5044.7  827.32  5050.5  829.14  5093.3  829.17  5116.6  827.04
  5124.4  827.95  5130.2   829.6  5145.8  831.64  5151.6   833.6  5161.3  834.74
  5174.9  838.37  5188.5  840.49  5225.5   843.6    5241  846.15  5291.6  849.06
#Mann= 4 ,-1 , 0
    4279    .035       0  4375.3     .12       0  4985.9     .05       0
  4999.1     .12       0
Bank Sta=4985.9,4999.1
XS Rating Curve= 0 ,0
Exp/Cntr=0.3,0.1

Type RM Length L Ch R = 1 ,18613   ,447,447,447
BEGIN DESCRIPTION:
Bear Creek 34.0
END DESCRIPTION:
XS GIS Cut Line= 3
      2190425.03     13791924.97        2190825.       13791525.
        2190875.       13791325.
#Sta/Elev= 30
  4434.1  839.34  4448.2  839.17  4476.5  837.88  4518.9   833.3  4533.1  831.26
  4547.2  830.17  4688.6  829.56  4773.5   827.9    4830  827.59  4858.3   827.1
  4886.6  826.11  4914.9  824.35  4943.2  823.63  4971.5  821.36    4979  819.62
  4979.5  819.12  4991.7  819.12  4992.2  819.62  4996.2   820.3  5002.3   820.3
  5010.1  822.06  5017.8  822.87  5022.9  824.34  5064.2  829.21  5092.5  831.33
  5113.1  834.19  5154.4  838.54    5175  841.09  5182.7  842.51  5205.9  844.33
#Mann= 3 ,-1 , 0
  4434.1     .12       0    4979     .05       0  4992.2     .12       0
Bank Sta=4979,4992.2
XS Rating Curve= 0 ,0
Exp/Cntr=0.3,0.1

Type RM Length L Ch R = 1 ,18166   ,453,453,453
BEGIN DESCRIPTION:
Bear Creek 33.0
END DESCRIPTION:
XS GIS Cut Line= 3
      2191024.99     13792325.02        2191175.       13791775.
        2191275.     13791425.02
#Sta/Elev= 30
  4429.9  837.54  4492.1  835.83  4541.5  833.42  4625.3  830.53    4658  828.26
  4726.5  827.95  4803.1  826.77  4827.6  825.52  4868.7  824.01  4937.8  819.63
  4948.2  819.86  4953.6  818.87  4968.3  815.11  4968.8  814.61  4986.3  814.61
  4986.8  815.11  5013.2  816.09  5022.1  817.53  5031.2  820.23  5041.6  821.73
  5055.9  821.88  5089.7  825.24  5128.7     827    5156  828.83  5162.5   829.9
  5167.7  829.65  5196.3  831.67  5201.5  831.33  5274.3  833.46    5364  839.11
#Mann= 9 ,-1 , 0
  4429.9    .035       0  4541.5     .07       0  4625.3    .035       0
  4726.5     .07       0  4827.6     .12       0  4953.6     .07       0
  4968.3     .05       0  4986.8     .07       0  5013.2     .12       0
Bank Sta=4968.3,4986.8
XS Rating Curve= 0 ,0
Exp/Cntr=0.3,0.1

Type RM Length L Ch R = 1 ,17713   ,466,466,466
BEGIN DESCRIPTION:
Bear Creek 32.0
END DESCRIPTION:
XS GIS Cut Line= 3
      2191075.01     13792524.99        2191575.       13791925.
        2191675.     13791474.98
#Sta/Elev= 30
  4219.5  841.72  4276.1  840.49  4389.4  836.17  4432.3  834.18  4539.1  826.84
  4553.8  826.93  4574.2   826.1  4617.2  826.69  4688.1  826.21    4802  824.43
  4844.3  822.85  4964.7  820.97  4993.3  819.84  4997.3  818.83  5015.5  818.37
    5016  817.87  5033.6  817.87  5034.1  818.37  5041.5  819.38  5052.3  819.68
  5092.7  820.03    5117   818.7  5123.4  819.34  5133.7  822.97  5165.7  823.98
  5215.6  828.25  5301.4  832.21  5328.3  834.16  5379.5  835.62  5461.5   839.2
#Mann= 5 ,-1 , 0
  4219.5    .035       0  4553.8     .07       0  5015.5     .05       0
  5034.1     .07       0  5052.3     .12       0
Bank Sta=5015.5,5034.1
XS Rating Curve= 0 ,0
Exp/Cntr=0.3,0.1

Type RM Length L Ch R = 1 ,17247   ,488,488,488
BEGIN DESCRIPTION:
Bear Creek 31.0
END DESCRIPTION:
XS GIS Cut Line= 3
      2192174.99     13792324.96        2192025.       13791875.
        2191825.     13791525.01
#Sta/Elev= 30
  4525.6  841.23  4557.2  839.31  4641.5  831.16  4683.7   824.3  4715.8  820.99
  4736.4  818.87  4757.5  818.03  4778.5  814.65  4799.6  818.59  4820.7  819.61
  4831.2  821.24  4862.9  822.73  4883.9  822.75    4905  815.27  4926.1  814.41
  4957.7  816.68  4968.3  815.03  4969.5  814.25    4970  813.75  4988.1  814.25
  4997.3  815.95  5002.8  815.95  5007.8  818.15  5013.6  818.37  5029.4  821.49
  5094.2  824.34    5110  825.64  5249.7  829.97  5299.4  832.42    5403  835.98
#Mann= 4 ,-1 , 0
  4525.6    .035       0  4715.8     .12       0  4969.5     .05       0
  4988.1     .12       0
Bank Sta=4969.5,4988.1
XS Rating Curve= 0 ,0
Exp/Cntr=0.3,0.1

Type RM Length L Ch R = 1 ,16759   ,466,466,466
BEGIN DESCRIPTION:
Bear Creek 30.0
END DESCRIPTION:
XS GIS Cut Line= 3
      2192575.03     13791725.01        2192375.       13791675.
      2191643.65     13791239.67
#Sta/Elev= 30
  4793.9  834.67  4853.2  834.39  4866.1  833.32  4927.9  832.48  4958.9  829.52
  4969.2  826.16  4974.3   823.3  4976.9  820.45  4982.1  819.07  4989.8  813.85
  4997.5  809.81    5003  809.81  5007.9  807.66  5013.9  807.22  5014.4  806.72
  5032.9  807.22  5044.9  809.75  5050.7  809.79  5066.3  813.93  5072.1  814.71
  5109.1  815.23  5146.1  818.14  5167.6  818.46  5247.4  822.42  5342.8   827.7
  5379.8   830.7  5438.2  834.11  5650.5  840.82  5693.3  841.41  5851.2  845.97
#Mann= 3 ,-1 , 0
  4793.9     .12       0  5013.9     .05       0  5032.9     .12       0
Bank Sta=5013.9,5032.9
XS Rating Curve= 0 ,0
Exp/Cntr=0.3,0.1

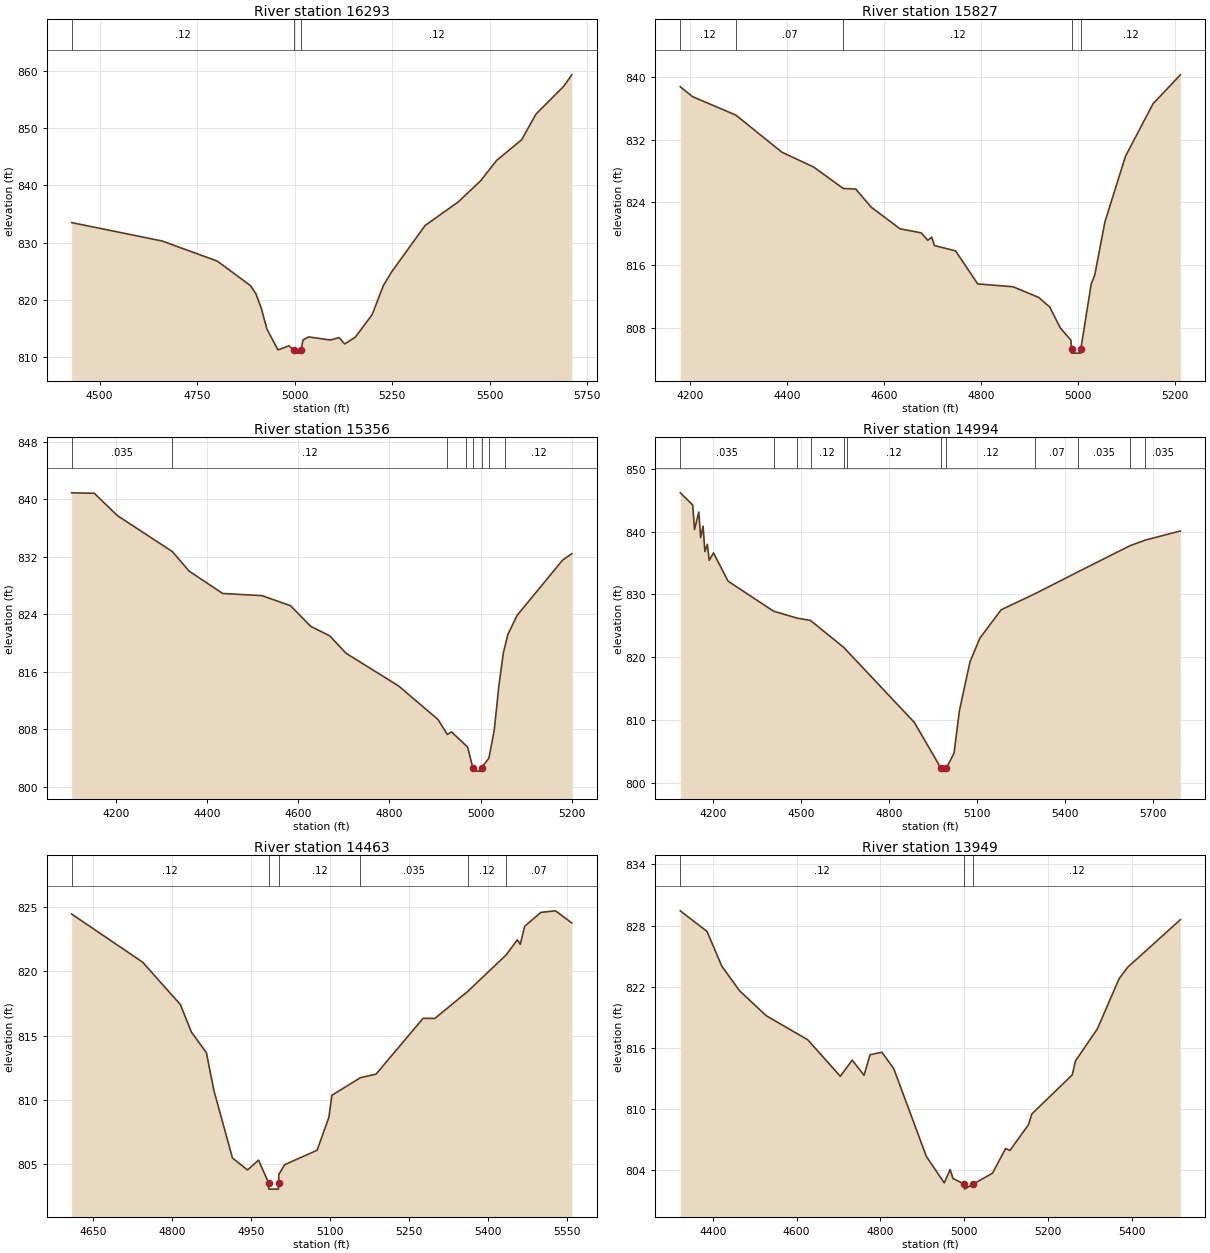
Type RM Length L Ch R = 1 ,16293   ,466,466,466
BEGIN DESCRIPTION:
Bear Creek 29.0
END DESCRIPTION:
XS GIS Cut Line= 4
      2192829.01     13791629.01        2192725.       13791525.
        2192425.       13791225.      2191874.99     13790774.99
#Sta/Elev= 30
  4428.2  833.52  4660.1  830.31  4801.6   826.8  4886.4  822.53  4900.6   821.1
  4914.7  818.48  4928.8  814.92  4957.1   811.3  4985.4  812.03  4997.2  811.24
  4997.7  810.74  5015.7  810.74  5016.2  811.24  5021.1  813.04  5035.4  813.57
  5091.4  813.03  5113.7  813.45    5128  812.34  5155.3  813.52  5198.4  817.46
  5227.1  822.52  5247.9  824.87  5334.1  833.01  5418.8  837.11  5476.2   840.8
  5517.8  844.39  5581.7  847.98  5618.3  852.45  5688.7  857.25  5710.2  859.31
#Mann= 3 ,-1 , 0
  4428.2     .12       0  4997.2     .05       0  5016.2     .12       0
Bank Sta=4997.2,5016.2
XS Rating Curve= 0 ,0
Exp/Cntr=0.3,0.1

Type RM Length L Ch R = 1 ,15827   ,471,471,471
BEGIN DESCRIPTION:
Bear Creek 28.0
END DESCRIPTION:
XS GIS Cut Line= 4
      2193141.32     13791222.96        2192875.       13791075.
        2192425.       13790825.      2192274.98     13790674.98
#Sta/Elev= 30
  4180.1  838.74  4205.6  837.47  4294.6  835.13  4389.8  830.39    4455  828.51
  4516.3  825.77    4542  825.69    4574  823.38  4633.5  820.62  4676.9  820.11
  4690.7  819.16  4698.7  819.56  4704.4  818.49  4747.9  817.81  4793.6   813.6
  4866.8  813.23  4919.5  811.87  4942.3  810.64  4964.1  807.97  4985.8  806.43
  4987.2  805.27  4987.7  804.77  5005.7  804.77  5006.2  805.27  5027.8  813.62
  5034.9  814.69  5056.1  821.53  5098.5  829.89  5155.1  836.56  5211.7  840.26
#Mann= 5 ,-1 , 0
  4180.1     .12       0  4294.6     .07       0  4516.3     .12       0
  4987.2     .05       0  5006.2     .12       0
Bank Sta=4987.2,5006.2
XS Rating Curve= 0 ,0
Exp/Cntr=0.3,0.1

Type RM Length L Ch R = 1 ,15356   ,362,362,362
BEGIN DESCRIPTION:
Bear Creek 27.0
END DESCRIPTION:
XS GIS Cut Line= 4
       2193354.4       13790946.        2192975.       13790675.
        2192625.       13790425.      2192424.96       13790425.
#Sta/Elev= 30
  4103.6  840.88  4153.2  840.82  4203.6  837.72  4324.6  832.69  4360.9  829.99
  4434.7  826.87  4520.7  826.57  4583.4  825.17  4627.6   822.3  4669.4  820.97
    4705  818.55  4820.5  813.99  4906.6  809.33  4927.2  807.24  4936.1  807.61
    4967  805.77  4971.7  805.46    4983  802.64  4983.5  802.14  5001.6  802.14
  5002.1  802.64  5018.2  803.93    5030  807.83    5040  813.96    5050  818.62
  5053.8   819.6    5060  821.19    5080  823.81    5180  831.53    5200  832.41
#Mann= 8 ,-1 , 0
  4103.6    .035       0  4324.6     .12       0  4927.2      .1       0
    4967     .12       0    4983     .05       0  5002.1     .12       0
  5018.2      .1       0  5053.8     .12       0
Bank Sta=4983,5002.1
XS Rating Curve= 0 ,0
Exp/Cntr=0.3,0.1

Type RM Length L Ch R = 1 ,14994   ,531,531,531
BEGIN DESCRIPTION:
Bear Creek 26.0
END DESCRIPTION:
XS GIS Cut Line= 3
      2193398.37     13790880.03      2192825.42     13790119.57
      2192101.44     13789911.23
#Sta/Elev= 30
  4087.2  846.16  4129.6  844.22  4135.8  840.32  4150.4   843.1  4156.7  839.03
    4165  840.85  4171.2  836.82  4179.5  837.96  4185.8  835.42  4200.4  836.61
  4250.3   832.1  4405.2  827.33  4486.7  826.21  4531.3  825.85    4644  821.59
  4657.4  820.93  4885.4  809.63  4975.7  802.38  4976.2  801.88  4994.8  802.38
  5020.7  804.74  5039.1   811.5  5075.1  819.27  5108.8  823.03  5181.3  827.55
  5297.5  830.12  5442.4  833.56  5622.4  837.78    5673  838.64  5792.7  840.09
#Mann= 12 ,-1 , 0
  4087.2    .035       0  4405.2     .12       0  4486.7    .035       0
  4531.3     .12       0    4644    .035       0  4657.4     .12       0
  4975.7     .05       0  4994.8     .12       0  5297.5     .07       0
  5442.4    .035       0  5622.4     .07       0    5673    .035       0
Bank Sta=4975.7,4994.8
XS Rating Curve= 0 ,0
Exp/Cntr=0.3,0.1

Type RM Length L Ch R = 1 ,14463   ,514,514,514
BEGIN DESCRIPTION:
Bear Creek 25.0
END DESCRIPTION:
XS GIS Cut Line= 3
      2193475.03     13790125.03        2193225.       13789825.
      2192724.97     13789574.99
#Sta/Elev= 30
  4609.1  824.45  4743.9  820.71  4815.5  817.42  4836.3  815.29  4864.9  813.68
  4879.2  810.74  4914.4   805.5    4943  804.57  4963.9  805.33  4982.9  803.58
  4983.4  803.08  5001.6  803.08  5002.1  803.58  5002.4  804.23  5013.6  804.98
  5075.1   806.1  5097.5  808.66  5103.1  810.37  5157.5  811.74  5186.9  812.01
  5276.4  816.35  5298.7  816.34  5361.1  818.44  5434.2  821.28  5455.3  822.45
  5460.8   822.1  5469.2   823.5    5500  824.58  5527.9   824.7  5558.7  823.76
#Mann= 6 ,-1 , 0
  4609.1     .12       0  4982.9     .05       0  5002.1     .12       0
  5157.5    .035       0  5361.1     .12       0  5434.2     .07       0
Bank Sta=4982.9,5002.1
XS Rating Curve= 0 ,0
Exp/Cntr=0.3,0.1

Type RM Length L Ch R = 1 ,13949   ,539,539,539
BEGIN DESCRIPTION:
Bear Creek 24.0
END DESCRIPTION:
XS GIS Cut Line= 3
      2194075.02     13790075.01        2193575.       13789625.
      2193425.01     13789125.02
#Sta/Elev= 30
    4322  829.44  4385.9  827.42  4421.1  824.02  4463.7   821.6  4527.2  819.16
  4626.6  816.79  4704.3  813.22  4732.7   814.8  4761.1  813.32  4775.3  815.33
  4803.7  815.57  4832.1  813.95  4909.9  805.35  4952.5  802.77  4966.7  804.07
  4973.4  803.19  5000.6  802.65  5001.1  802.15  5021.9  802.65  5067.8  803.71
  5099.1  806.13  5109.5  805.94  5153.9  808.48  5161.7  809.52  5258.3  813.35
  5266.2  814.73  5318.4  817.87  5370.6  822.81  5390.6   823.9  5516.7  828.58
#Mann= 3 ,-1 , 0
    4322     .12       0  5000.6     .05       0  5021.9     .12       0
Bank Sta=5000.6,5021.9
XS Rating Curve= 0 ,0
Exp/Cntr=0.3,0.1

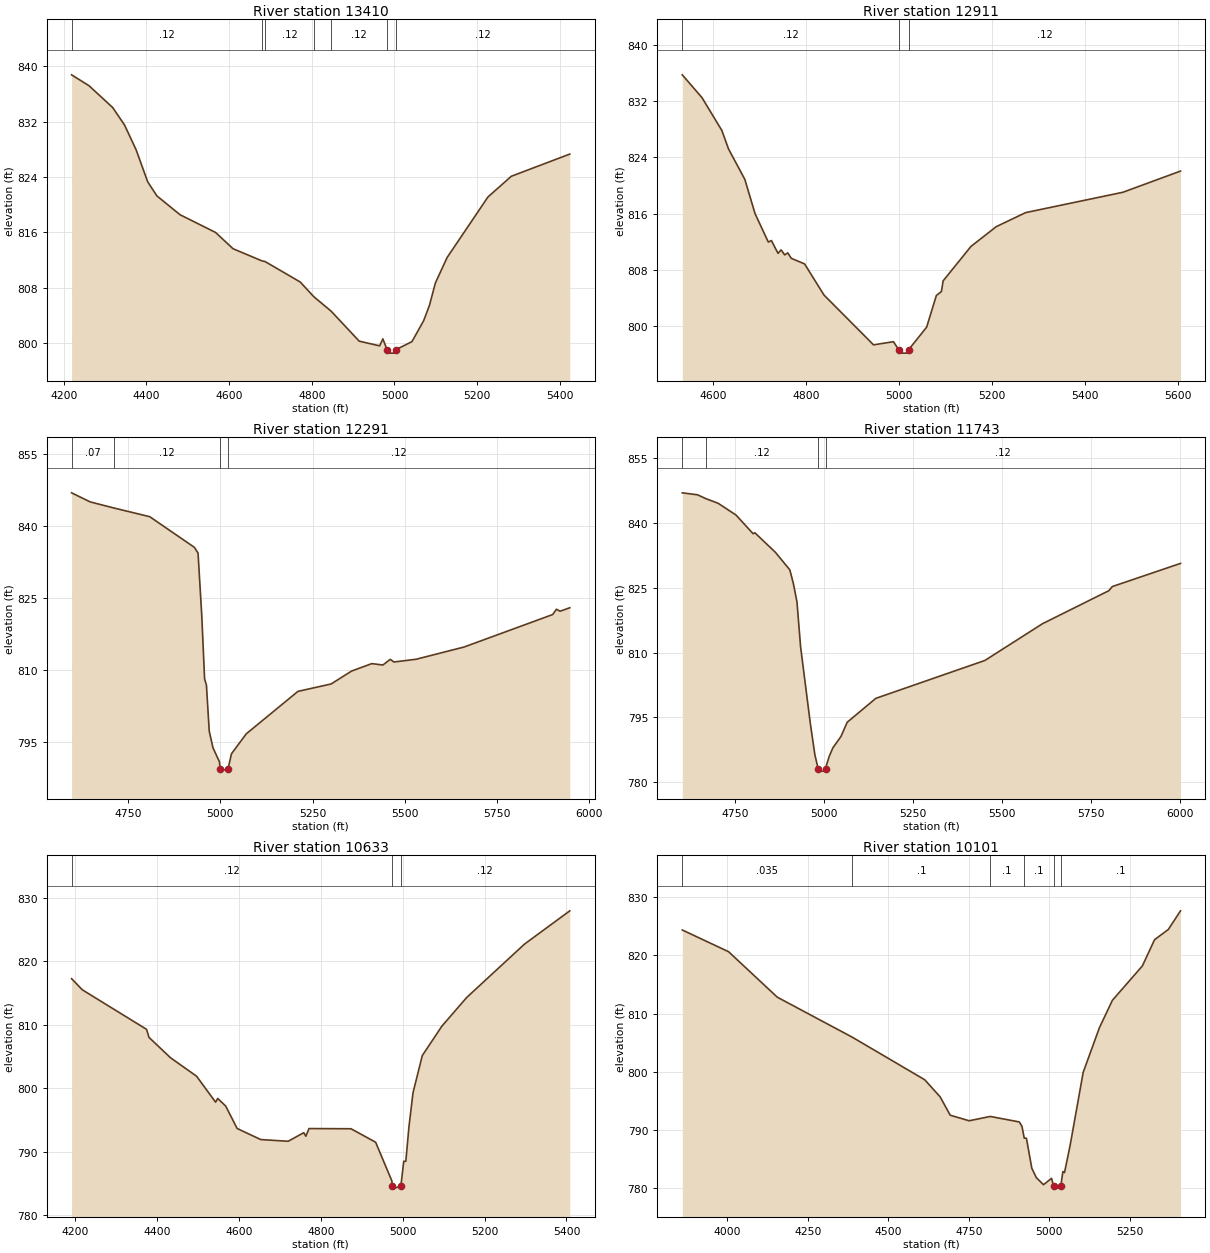
Type RM Length L Ch R = 1 ,13410   ,499,499,499
BEGIN DESCRIPTION:
Bear Creek 23.0
END DESCRIPTION:
XS GIS Cut Line= 3
      2194625.04     13789875.03        2194025.       13789375.
      2193725.03     13789075.03
#Sta/Elev= 30
  4218.9  838.74  4261.3  837.16  4318.5  834.01  4347.2  831.48  4375.2   827.9
  4403.1  823.29  4425.3  821.27  4481.2  818.55  4567.2  815.99  4609.5  813.64
  4679.7  811.88    4687  811.79  4772.2  808.83  4804.8  806.72  4846.6  804.64
  4914.7   800.3  4964.2  799.62    4972  800.63  4982.1  799.07  4982.6  798.57
    5003  798.57  5003.5  799.07  5042.4  800.23  5070.7  803.26  5084.8  805.49
    5099  808.69  5127.3  812.36  5226.2  821.11  5282.8   824.1  5424.2   827.3
#Mann= 7 ,-1 , 0
  4218.9     .12       0  4679.7     .07       0    4687     .12       0
  4804.8     .07       0  4846.6     .12       0  4982.1     .05       0
  5003.5     .12       0
Bank Sta=4982.1,5003.5
XS Rating Curve= 0 ,0
Exp/Cntr=0.3,0.1

Type RM Length L Ch R = 1 ,12911   ,620,620,620
BEGIN DESCRIPTION:
Bear Creek 22.0
END DESCRIPTION:
XS GIS Cut Line= 3
      2194825.01     13789525.01      2194403.55     13789161.24
      2193925.04     13788975.02
#Sta/Elev= 30
  4534.5  835.78  4576.8  832.53  4619.5  827.85  4633.8  825.22  4668.9  820.87
  4690.8     816  4719.3  811.94  4725.9  812.16  4740.2  810.33  4746.8  810.83
  4754.4  810.11  4761.1   810.4  4768.7  809.62  4797.2  808.83  4838.9  804.39
  4945.3  797.29  4988.1  797.74  4999.3  796.61  4999.8  796.11  5020.3  796.11
  5020.8  796.61  5059.4  799.81  5080.3  804.33  5091.2   804.9  5094.8  806.41
  5154.6  811.32    5209  814.14  5272.1  816.14    5481  819.04  5604.7  822.06
#Mann= 3 ,-1 , 0
  4534.5     .12       0  4999.3     .05       0  5020.8     .12       0
Bank Sta=4999.3,5020.8
XS Rating Curve= 0 ,0
Exp/Cntr=0.3,0.1

Type RM Length L Ch R = 1 ,12291   ,548,548,548
BEGIN DESCRIPTION:
Bear Creek 21.0
END DESCRIPTION:
XS GIS Cut Line= 3
        2195225.       13788775.        2194825.       13788825.
      2193878.71      13788838.3
#Sta/Elev= 30
  4597.3  846.88  4647.7  844.99  4712.9   843.7  4808.9  841.91  4929.9  835.52
  4939.9  834.32    4950  821.22  4957.6   808.1  4962.6  806.78  4970.2  797.18
  4980.3  793.74  4997.9   790.8  4999.6  789.37  5000.1  788.87  5021.2  789.37
  5030.4  792.48  5070.4  796.64  5210.4  805.49  5300.4  807.04  5355.8  809.73
  5410.5  811.28  5440.5  810.99  5460.5  812.17  5470.5  811.62  5530.5  812.19
  5660.5  814.74  5900.5  821.51  5910.5  822.61  5920.5   822.2  5946.8  822.93
#Mann= 4 ,-1 , 0
  4597.3     .07       0  4712.9     .12       0  4999.6     .05       0
  5021.2     .12       0
Bank Sta=4999.6,5021.2
XS Rating Curve= 0 ,0
Exp/Cntr=0.3,0.1

Type RM Length L Ch R = 1 ,11743   ,1110,1110,1110
BEGIN DESCRIPTION:
Bear Creek 20.0
END DESCRIPTION:
XS GIS Cut Line= 3
      2195075.04     13788274.99        2194675.       13788325.
      2193684.83     13788447.69
#Sta/Elev= 30
  4601.6  847.03  4644.5  846.57  4667.4   845.7  4702.4  844.61  4752.8  841.88
  4800.7  837.56  4805.7  837.77  4863.7  833.23    4904  829.18  4914.1  825.98
  4924.1  821.74  4934.2  811.42  4944.3  804.85  4961.9  793.45  4974.5  786.33
  4983.8  783.06  4984.3  782.56    5005  782.56  5005.5  783.06  5007.3  784.04
  5014.8  785.98  5024.9  787.94  5047.8  790.59  5065.2  793.87  5145.8  799.42
  5452.6   808.2  5614.5  816.71  5800.8  824.35  5810.9  825.32  6002.5  830.68
#Mann= 4 ,-1 , 0
  4601.6    .035       0  4667.4     .12       0  4983.8     .05       0
  5005.5     .12       0
Bank Sta=4983.8,5005.5
XS Rating Curve= 0 ,0
Exp/Cntr=0.3,0.1

Type RM Length L Ch R = 1 ,10633   ,532,532,532
BEGIN DESCRIPTION:
Bear Creek 19.0
END DESCRIPTION:
XS GIS Cut Line= 3
      2194775.04     13787775.01        2193975.       13787625.
        2193575.       13787675.
#Sta/Elev= 30
  4191.1  817.26  4217.4   815.5  4374.3  809.28  4380.2  808.02  4432.8  804.81
  4496.4  801.91    4543  797.82  4548.1  798.41  4567.6  797.21  4595.6  793.68
  4653.2  791.94  4720.2  791.67  4758.4  793.02  4763.4  792.47  4771.1  793.67
  4873.7  793.64  4933.9  791.52  4973.7  785.41  4973.8  784.64  4974.3  784.14
  4995.6  784.64  5002.5  788.52  5007.6  788.52  5015.2   793.9  5025.2  799.31
  5047.9  805.16  5095.8  809.79  5156.3  814.29  5297.3  822.68  5408.2  827.93
#Mann= 3 ,-1 , 0
  4191.1     .12       0  4973.8     .05       0  4995.6     .12       0
Bank Sta=4973.8,4995.6
XS Rating Curve= 0 ,0
Exp/Cntr=0.3,0.1

Type RM Length L Ch R = 1 ,10101   ,546,546,546
BEGIN DESCRIPTION:
Bear Creek 18.0
END DESCRIPTION:
XS GIS Cut Line= 4
      2195062.88     13787473.95      2194103.62     13787189.31
        2193975.       13787125.      2193575.01       13787075.
#Sta/Elev= 30
  3859.9  824.38  4003.7  820.65    4155  812.84  4387.9  805.97    4613  798.66
  4660.9  795.72  4692.2  792.57  4751.1  791.62  4816.4  792.36  4906.5  791.42
  4914.9  790.67    4922  788.64  4928.8  788.62  4945.6  783.46  4959.6  781.85
  4981.9  780.64  5006.8  781.73  5013.6  780.38  5014.1  779.88  5035.4  780.38
  5042.1   782.9  5047.1  782.72  5064.8  787.46  5105.1  799.93  5155.5  807.59
  5195.8   812.3    5289  818.21  5326.8  822.71  5369.6  824.47  5407.4  827.67
#Mann= 6 ,-1 , 0
  3859.9    .035       0  4387.9      .1       0  4816.4      .1       0
    4922      .1       0  5013.6     .05       0  5035.4      .1       0
Bank Sta=5013.6,5035.4
XS Rating Curve= 0 ,0
Exp/Cntr=0.3,0.1

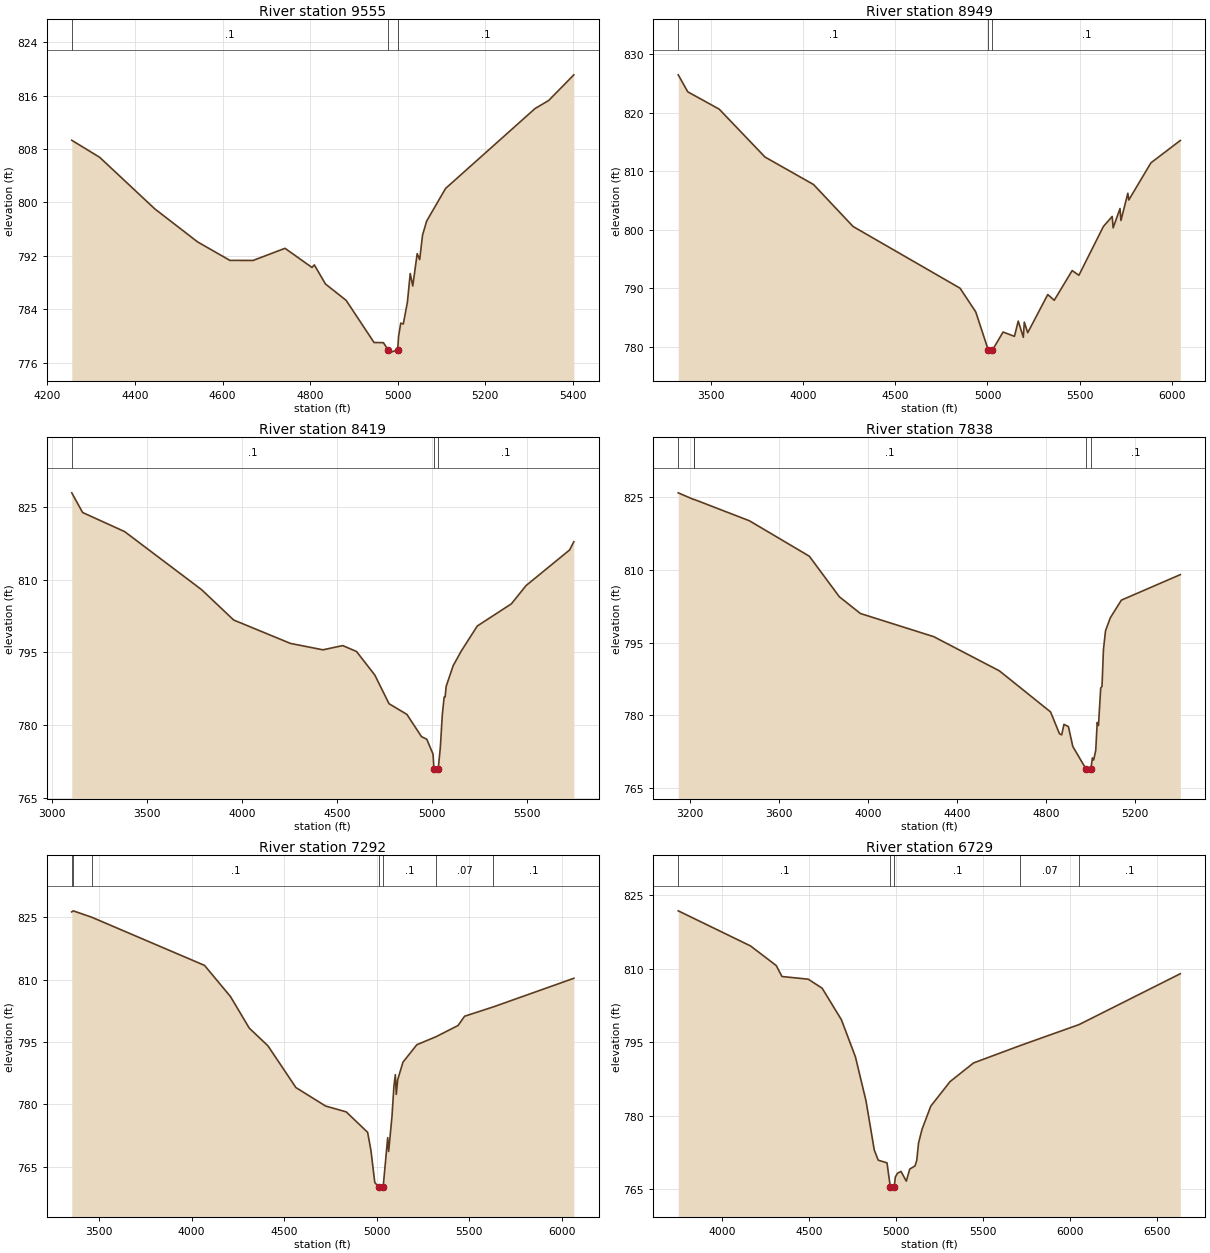
Type RM Length L Ch R = 1 ,9555    ,606,606,606
BEGIN DESCRIPTION:
Bear Creek 17.0
END DESCRIPTION:
XS GIS Cut Line= 3
      2194625.02     13786875.01        2193925.       13786625.
      2193575.03     13786824.98
#Sta/Elev= 30
  4255.7  809.31  4319.4  806.76  4445.3  799.03    4543  794.08  4616.8  791.31
  4669.8   791.3  4742.6  793.12  4804.2  790.25  4809.5  790.64    4835  787.77
  4882.2  785.32  4945.9     779  4967.2  778.98    4978  777.91  4978.5  777.41
  4999.9  777.91  5001.9  779.93  5006.9   781.9  5012.7  781.78  5022.1  785.06
  5028.5  789.34  5034.3  787.47  5044.4  792.32  5050.1  791.43  5056.6  795.09
    5066   797.2  5109.2  802.09  5313.6  814.07  5344.6  815.27  5402.1  819.12
#Mann= 3 ,-1 , 0
  4255.7      .1       0    4978     .05       0  4999.9      .1       0
Bank Sta=4978,4999.9
XS Rating Curve= 0 ,0
Exp/Cntr=0.3,0.1

Type RM Length L Ch R = 1 ,8949    ,530,530,530
BEGIN DESCRIPTION:
Bear Creek 16.0
END DESCRIPTION:
XS GIS Cut Line= 4
      2195224.33      13787437.5      2194705.92     13786534.91
      2194163.96     13786124.78      2193189.98     13785895.61
#Sta/Elev= 30
  3323.9  826.47  3375.7  823.56  3545.9   820.6  3794.1  812.41  4057.2  807.71
  4271.5  800.53  4851.1  789.98  4936.4  785.92  5004.5  779.37    5005  778.87
  5026.5  779.37  5084.4  782.48  5146.1  781.74  5166.6  784.35  5194.3  781.58
  5199.4  784.18    5218  782.36  5326.6  788.89  5361.8  787.91  5458.8  792.99
  5495.4  792.19  5628.3  800.54  5675.8  802.25    5681   800.3  5718.2   803.6
  5723.4  801.56  5760.6  806.22  5765.7  805.06  5885.8  811.42    6045  815.24
#Mann= 3 ,-1 , 0
  3323.9      .1       0  5004.5     .05       0  5026.5      .1       0
Bank Sta=5004.5,5026.5
XS Rating Curve= 0 ,0
Exp/Cntr=0.3,0.1

Type RM Length L Ch R = 1 ,8419    ,581,581,581
BEGIN DESCRIPTION:
Bear Creek 15.0
END DESCRIPTION:
XS GIS Cut Line= 4
      2195276.39     13787447.88      2194912.26     13786567.27
        2194475.       13785725.      2194304.61     13784999.88
#Sta/Elev= 30
  3102.6  827.91  3159.8  823.85  3381.3  819.91  3787.4  807.92    3956  801.67
  4255.5  796.84  4426.8  795.52  4531.3  796.39  4603.8  795.17  4700.3  790.31
  4775.1   784.4  4869.3   782.2  4946.4   777.6  4974.2  777.07  5007.1     774
  5011.8  770.99  5012.3  770.49  5034.5  770.99  5045.6  775.37  5055.9  782.07
  5065.6  785.76  5070.7  785.77  5076.4  787.99  5113.1  792.23  5155.5  795.24
  5240.3  800.43  5420.2  805.01  5497.6  808.78  5727.3  816.13  5749.4  817.82
#Mann= 3 ,-1 , 0
  3102.6      .1       0  5011.8     .05       0  5034.5      .1       0
Bank Sta=5011.8,5034.5
XS Rating Curve= 0 ,0
Exp/Cntr=0.3,0.1

Type RM Length L Ch R = 1 ,7838    ,546,546,546
BEGIN DESCRIPTION:
Bear Creek 14.0
END DESCRIPTION:
XS GIS Cut Line= 4
      2195422.22     13787463.49      2195023.94     13786281.25
        2195025.       13785675.      2194824.99     13785324.99
#Sta/Elev= 30
  3146.2  825.83  3215.6  824.46  3217.4  824.48  3466.4  820.07  3735.5  812.78
  3870.5  804.43    3965  800.99  4294.8  796.22    4590  789.18    4820  780.72
    4860  776.23    4870  776.01    4880  778.17    4900  777.71    4920   773.6
  4978.6  769.04  4979.1  768.54  5001.3  769.04  5007.9  771.26  5013.6  770.83
    5023  772.83  5029.5  778.55  5035.2  777.94  5045.3  785.64  5051.1  785.97
  5057.6  793.56  5066.9  797.44  5088.5  800.11  5138.2  803.74  5403.1  808.99
#Mann= 5 ,-1 , 0
  3146.2      .1       0  3215.6     .07       0  3217.4      .1       0
  4978.6     .05       0  5001.3      .1       0
Bank Sta=4978.6,5001.3
XS Rating Curve= 0 ,0
Exp/Cntr=0.3,0.1

Type RM Length L Ch R = 1 ,7292    ,563,563,563
BEGIN DESCRIPTION:
Bear Creek 13.0
END DESCRIPTION:
XS GIS Cut Line= 5
      2195630.57     13787557.25      2195448.69     13786010.53
        2195475.       13785925.      2195389.66     13785583.65
      2194907.86     13785058.64
#Sta/Elev= 30
  3353.4   826.3  3361.1  826.56  3460.6  825.03  4070.6  813.43  4210.5  805.93
  4312.2  798.33  4412.9  794.08  4563.9  784.04  4724.1   779.6  4835.8  778.19
  4951.2  773.27  4968.9  768.94  4989.8  761.18  5012.1  760.11  5012.6  759.61
  5034.9  760.11  5059.5  771.99  5064.7  768.68  5082.7  777.15    5093  784.35
  5100.8  787.15  5105.9   782.4  5113.6  785.97    5142  790.15  5216.7  794.34
  5321.1  796.29  5439.4  798.97  5474.6   801.2  5630.6  803.46  6064.7  810.33
#Mann= 7 ,-1 , 0
  3353.4    .035       0  3361.1     .07       0  3460.6      .1       0
  5012.1     .05       0  5034.9      .1       0  5321.1     .07       0
  5630.6      .1       0
Bank Sta=5012.1,5034.9
XS Rating Curve= 0 ,0
Exp/Cntr=0.3,0.1

Type RM Length L Ch R = 1 ,6729    ,551,551,551
BEGIN DESCRIPTION:
Bear Creek 12.0
END DESCRIPTION:
XS GIS Cut Line= 5
      2195797.24     13787468.72      2195880.14     13786583.92
        2195925.       13786225.      2195881.41     13785832.65
      2194943.09     13785020.84
#Sta/Elev= 30
  3749.6  821.85  4165.1  814.68    4313  810.67  4345.9  808.43  4496.6  807.89
  4576.9  806.04  4687.6   799.6  4768.2  792.01  4828.7  783.07  4876.5  772.98
  4899.2  770.91  4949.6  770.37  4968.4   765.5  4968.9     765  4991.2   765.5
  4997.5  767.46    5010  768.25  5030.2  768.62  5060.4  766.63  5080.5  769.11
  5110.7  769.74  5120.7  770.89  5130.8  774.41  5150.9  777.22  5201.2  781.95
  5311.9  786.96  5447.1  790.78  5716.2  794.34  6053.4  798.61  6635.5     809
#Mann= 5 ,-1 , 0
  3749.6      .1       0  4968.4     .05       0  4991.2      .1       0
  5716.2     .07       0  6053.4      .1       0
Bank Sta=4968.4,4991.2
XS Rating Curve= 0 ,0
Exp/Cntr=0.3,0.1