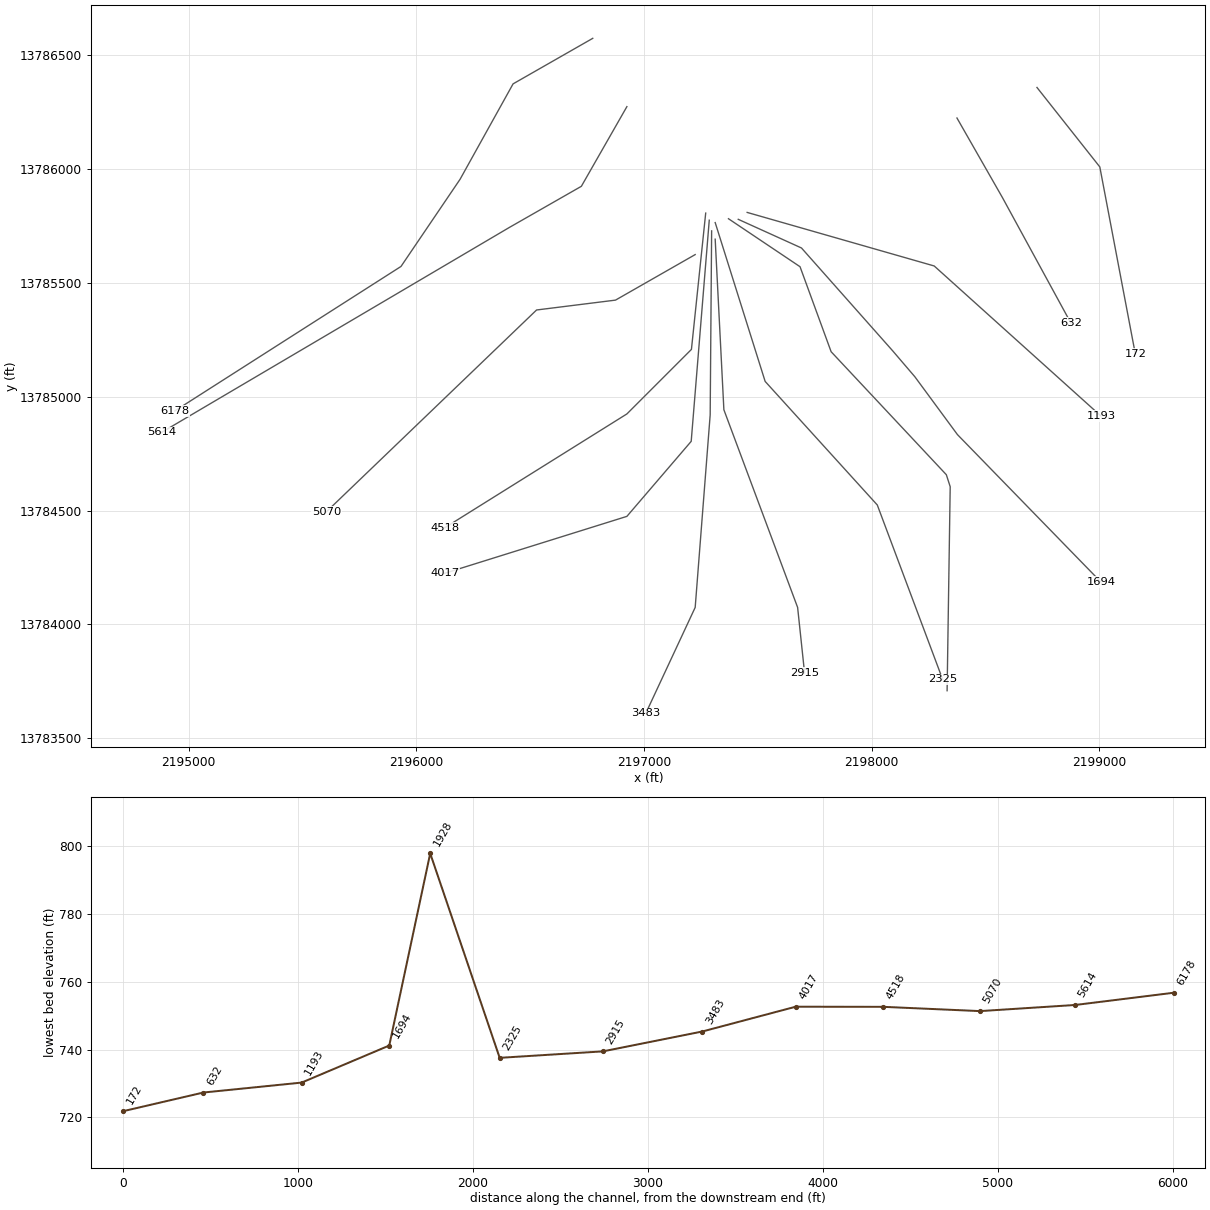
HEC-RAS study Bear Creek.prj: Bear Creek Base Level Engineering

--- Bear Creek.g01 (geometry) --- (continued)

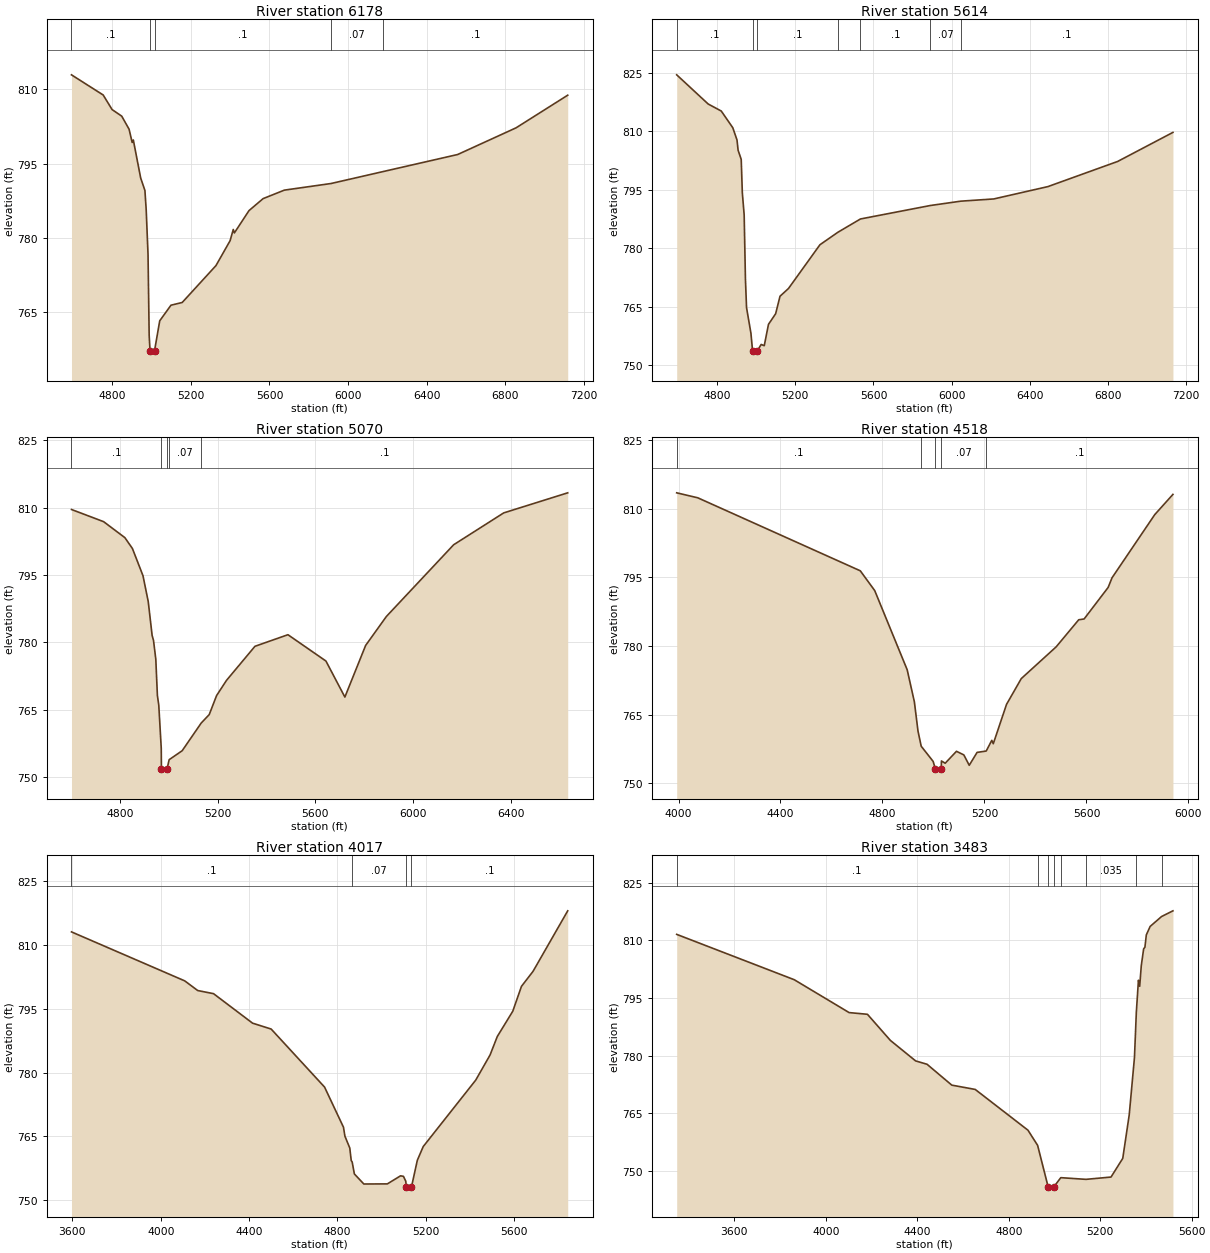
Type RM Length L Ch R = 1 ,6178    ,564,564,564
BEGIN DESCRIPTION:
Bear Creek 11.0
END DESCRIPTION:
XS GIS Cut Line= 5
      2196775.01     13786575.01        2196425.       13786375.
      2196192.18     13785955.92      2195932.65     13785572.91
      2194938.96     13784938.19
#Sta/Elev= 30
    4593  812.94  4754.3  808.87  4799.6  805.93  4848.6   804.6    4886  801.97
  4901.8  799.29  4907.6  799.79    4945  792.12  4966.6   789.6  4973.1  785.69
  4982.4  776.73  4988.2  760.38  4992.6  757.28  4993.1  756.78  5015.6  757.28
  5041.9   763.3  5099.1  766.45  5156.3     767  5327.9  774.44  5399.9  779.47
    5416  781.73  5421.7  781.04    5496  785.54  5567.9  787.96  5675.7  789.67
  5913.6  791.01  6179.6  793.43  6557.5  796.86  6854.4  802.24  7117.3  808.83
#Mann= 5 ,-1 , 0
    4593      .1       0  4992.6     .05       0  5015.6      .1       0
  5913.6     .07       0  6179.6      .1       0
Bank Sta=4992.6,5015.6
XS Rating Curve= 0 ,0
Exp/Cntr=0.3,0.1

Type RM Length L Ch R = 1 ,5614    ,544,544,544
BEGIN DESCRIPTION:
Bear Creek 10.0
END DESCRIPTION:
XS GIS Cut Line= 4
      2196924.99     13786274.98        2196725.       13785925.
      2196407.35     13785743.49      2194880.59     13784843.75
#Sta/Elev= 30
  4592.3  824.42  4753.5  816.95  4820.5  815.15  4879.5  810.88  4901.1  807.74
  4906.8  805.11  4922.7  802.76  4928.4  794.24  4937.8  788.55  4944.3   772.1
    4950   764.8  4972.4  758.27    4981  753.66  4981.5  753.16    5004  753.66
  5024.9  755.38  5040.7  755.07  5062.3  760.53    5099  763.25  5121.4  767.73
  5164.6   769.7  5325.8  780.91  5418.1  784.12  5533.3  787.51  5891.4  790.96
  6047.2  792.07  6216.1  792.64  6493.2   795.8  6850.4  802.24  7133.4  809.68
#Mann= 7 ,-1 , 0
  4592.3      .1       0    4981     .05       0    5004      .1       0
  5418.1     .07       0  5533.3      .1       0  5891.4     .07       0
  6047.2      .1       0
Bank Sta=4981,5004
XS Rating Curve= 0 ,0
Exp/Cntr=0.3,0.1

Type RM Length L Ch R = 1 ,5070    ,552,552,552
BEGIN DESCRIPTION:
Bear Creek 9.0
END DESCRIPTION:
XS GIS Cut Line= 4
      2197224.96     13785624.98        2196875.       13785425.
      2196528.18     13785381.65      2195604.51     13784494.77
#Sta/Elev= 30
  4601.1   809.6  4732.8  806.89  4819.9  803.33  4850.8  800.91    4894  794.87
  4915.6   789.1  4931.5  781.56  4937.2  780.44  4946.6  776.26  4953.1  768.19
  4958.8  766.02  4968.9  756.44  4969.6  751.85  4970.1  751.35  4992.7  751.85
  5001.3   753.9  5054.6  755.89  5132.8  762.07  5165.4  763.93  5195.6  768.17
    5236  771.54  5352.8  779.14  5487.9  781.72  5643.6  775.86  5721.2  767.84
  5806.2  779.33  5891.1  785.77  6166.9  801.75  6371.9  808.84  6634.2  813.31
#Mann= 5 ,-1 , 0
  4601.1      .1       0  4969.6     .05       0  4992.7      .1       0
  5001.3     .07       0  5132.8      .1       0
Bank Sta=4969.6,4992.7
XS Rating Curve= 0 ,0
Exp/Cntr=0.3,0.1

Type RM Length L Ch R = 1 ,4518    ,501,501,501
BEGIN DESCRIPTION:
Bear Creek 8.0
END DESCRIPTION:
XS GIS Cut Line= 4
      2197271.19     13785807.24      2197208.51     13785208.51
        2196925.       13784925.      2196125.04     13784425.02
#Sta/Elev= 30
  3992.9  813.53  4075.6  812.44    4713  796.46  4769.6  792.13  4896.9   774.8
  4925.1  767.78  4939.3  761.38  4951.9  758.06  4998.8  754.73  5007.2  753.11
  5007.7  752.61  5030.5  753.11  5031.2  754.83    5046  754.34  5090.2  756.95
  5119.1  756.16  5140.3  753.89    5171  756.71  5206.9  757.01  5228.7  759.35
  5234.6  758.61  5286.5  767.22  5344.3  772.86  5481.1  779.81  5569.6  785.74
  5590.8  785.92  5685.1  792.82  5700.4  794.94  5867.9  808.76  5939.2  813.19
#Mann= 5 ,-1 , 0
  3992.9      .1       0  4951.9     .07       0  5007.2     .05       0
  5030.5     .07       0  5206.9      .1       0
Bank Sta=5007.2,5030.5
XS Rating Curve= 0 ,0
Exp/Cntr=0.3,0.1

Type RM Length L Ch R = 1 ,4017    ,534,534,534
BEGIN DESCRIPTION:
Bear Creek 7.0
END DESCRIPTION:
XS GIS Cut Line= 4
      2197286.82     13785776.06       2197207.5     13784804.58
        2196925.       13784475.      2196125.05     13784225.01
#Sta/Elev= 30
    3596  812.99  4108.8   801.5  4167.7  799.23  4239.2   798.5  4415.9  791.58
  4500.1   790.2  4741.9  776.59  4827.5  767.18  4834.1  765.07  4856.1  762.29
  4862.7  759.34  4866.9  759.02  4876.9  756.21  4919.7  753.85  5026.3  753.88
    5086  755.77  5099.1  755.65  5109.6   754.5    5112  753.15  5112.5  752.65
  5135.4  753.15  5161.9  759.41  5188.7  762.64  5426.5  778.23  5491.4  784.13
  5523.9  788.44  5594.1  794.38  5633.4  800.21  5685.8  803.73  5842.9  817.93
#Mann= 4 ,-1 , 0
    3596      .1       0  4866.9     .07       0    5112     .05       0
  5135.4      .1       0
Bank Sta=5112,5135.4
XS Rating Curve= 0 ,0
Exp/Cntr=0.3,0.1

Type RM Length L Ch R = 1 ,3483    ,568,568,568
BEGIN DESCRIPTION:
Bear Creek 6.0
END DESCRIPTION:
XS GIS Cut Line= 4
      2197297.24     13785729.12      2197290.89     13784921.14
        2197225.       13784075.       2197007.9     13783609.55
#Sta/Elev= 30
  3347.9  811.56    3862  799.77    4102  791.22  4182.1  790.78  4282.4  783.99
  4392.8  778.66  4442.9  777.78    4551  772.36  4653.5  771.24  4884.2  760.64
  4926.4   756.7  4972.8  745.82  4973.3  745.32  4996.2  745.82  5027.7   748.3
  5137.8  747.86  5247.4  748.46  5298.7  753.31    5327  764.62  5349.9  779.52
  5358.1  791.29  5367.3  799.63  5372.8  798.06  5379.8  803.47  5390.1   807.8
  5395.6   808.2  5401.8  811.42  5418.5  813.62  5468.3  816.19  5518.2  817.68
#Mann= 8 ,-1 , 0
  3347.9      .1       0  4926.4    .035       0  4972.8    .035       0
  4996.2    .035       0  5027.7     .07       0  5137.8    .035       0
  5358.1      .1       0  5468.3     .07       0
Bank Sta=4972.8,4996.2
XS Rating Curve= 0 ,0
Exp/Cntr=0.3,0.1

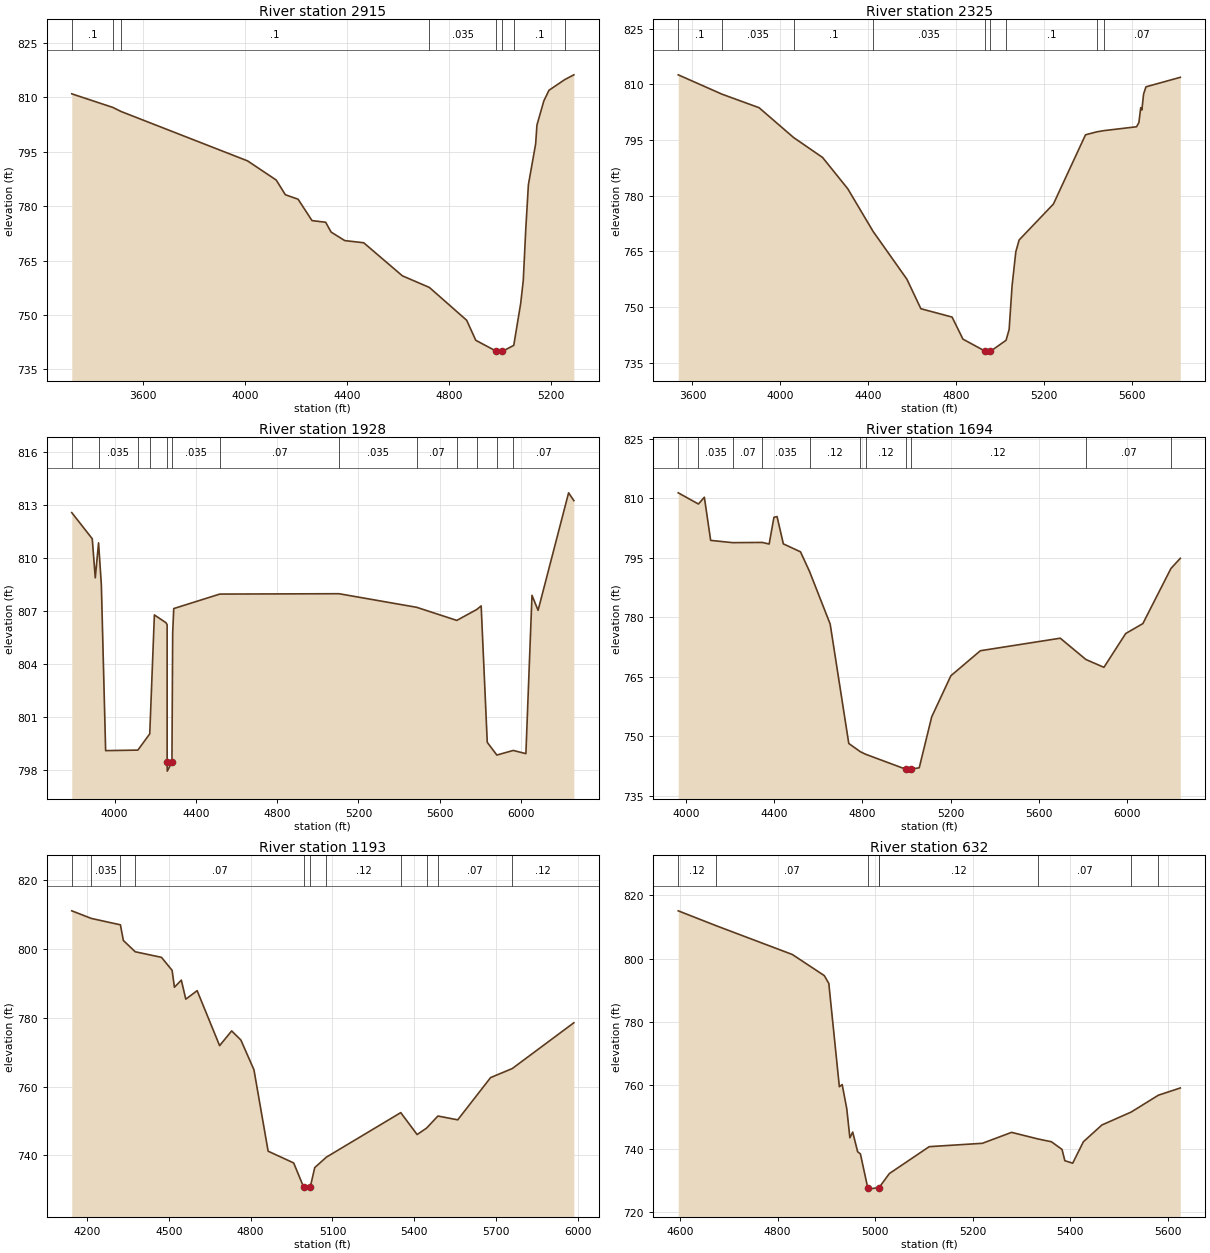
Type RM Length L Ch R = 1 ,2915    ,590,590,590
BEGIN DESCRIPTION:
Bear Creek 5.0
END DESCRIPTION:
XS GIS Cut Line= 4
      2197312.86     13785692.65      2197351.06     13784943.35
        2197675.       13784075.      2197705.43     13783788.09
#Sta/Elev= 30
  3322.9  810.99    3484  807.23  3516.1  806.11  4011.4  792.48  4123.4   787.2
  4159.1  783.15    4209  781.91  4263.5  776.01  4316.9  775.56  4338.2  772.85
  4391.6   770.5  4465.8   769.9  4617.4  760.77  4722.8  757.58  4868.9  748.52
  4904.6  742.99  4985.6  739.95  4986.1  739.45    5009  739.95  5053.3  741.59
  5080.4  753.17  5090.5   759.5  5100.5  773.94  5110.6  785.93    5139  797.19
    5144  802.36  5170.9     809    5191  811.96  5252.9  814.91  5288.5  816.23
#Mann= 8 ,-1 , 0
  3322.9      .1       0    3484    .035       0  3516.1      .1       0
  4722.8    .035       0  4985.6    .035       0    5009    .035       0
  5053.3      .1       0  5252.9    .035       0
Bank Sta=4985.6,5009
XS Rating Curve= 0 ,0
Exp/Cntr=0.3,0.1

Type RM Length L Ch R = 1 ,2325    ,397,397,397
BEGIN DESCRIPTION:
Bear Creek 4.0
END DESCRIPTION:
XS GIS Cut Line= 4
      2197312.87      13785765.6      2197532.33     13785067.87
        2198025.       13784525.      2198312.14     13783758.65
#Sta/Elev= 30
  3535.5  812.56  3734.7  807.34    3903   803.7  4059.8  795.67  4191.9  790.28
  4306.3  781.85  4421.6  770.35  4575.3  757.46  4638.8  749.51  4780.7  747.26
  4830.1  741.31  4931.9  738.04  4932.4  737.54  4955.3  738.04    5026     741
  5040.1  743.91  5053.4  755.65  5070.4  764.83  5085.5  768.04  5241.3  777.72
  5387.3  796.39    5438  797.18  5471.5  797.52  5619.4  798.56  5630.1   799.7
  5638.4   803.7  5643.7  803.09  5651.4  807.37  5662.1  809.32  5818.4  811.89
#Mann= 9 ,-1 , 0
  3535.5      .1       0  3734.7    .035       0  4059.8      .1       0
  4421.6    .035       0  4931.9    .035       0  4955.3    .035       0
    5026      .1       0    5438    .035       0  5471.5     .07       0
Bank Sta=4931.9,4955.3
XS Rating Curve= 0 ,0
Exp/Cntr=0.3,0.1

Type RM Length L Ch R = 1 ,1928    ,234,234,234
BEGIN DESCRIPTION:
Bear Creek 3.5
END DESCRIPTION:
XS GIS Cut Line= 6
      2197371.25     13785782.53      2197685.63     13785571.71
      2197822.18     13785198.29      2198328.28     13784658.03
       2198345.3     13784605.27       2198331.7     13783709.16
#Sta/Elev= 30
  3789.7  812.58  3890.5   811.1  3905.3  808.89  3921.5  810.87  3935.3  808.49
  3956.3  799.11  4114.9  799.14  4173.3  800.06  4196.1  806.79  4253.1  806.35
  4258.8  806.24  4258.9  798.45  4259.4  797.95  4282.4  798.45  4286.1  805.76
  4291.3  807.15    4518  807.97  5104.5  807.99  5486.8  807.22  5683.7  806.48
  5782.2   807.1  5803.6   807.3  5833.6  799.58  5880.7  798.86  5961.5  799.12
  6023.6  798.94  6053.6   807.9  6083.6  807.05  6233.7   813.7  6259.5  813.26
#Mann= 13 ,-1 , 0
  3789.7      .1       0  3921.5    .035       0  4114.9     .07       0
  4173.3    .035       0  4258.9     .05       0  4282.4    .035       0
    4518     .07       0  5104.5    .035       0  5486.8     .07       0
  5683.7    .035       0  5782.2     .07       0  5880.7    .035       0
  5961.5     .07       0
Bank Sta=4258.9,4282.4
XS Rating Curve= 0 ,0
Exp/Cntr=0.3,0.1

Type RM Length L Ch R = 1 ,1694    ,501,501,501
BEGIN DESCRIPTION:
Bear Creek 3.0
END DESCRIPTION:
XS GIS Cut Line= 6
      2197414.22     13785779.88      2197691.98     13785654.02
      2198091.83      13785203.1        2198190.     13785088.32
      2198377.03     13784834.33      2199007.09       13784187.
#Sta/Elev= 30
  3964.2   811.4  4055.7  808.58  4082.7  810.29  4111.3   799.4    4211  798.83
  4345.8  798.88  4376.6  798.48  4398.3  805.22  4412.5  805.41    4441  798.52
  4518.7  796.52  4559.7  791.58  4653.4  778.29  4737.8  748.16  4790.8  746.06
    4815  745.42  4995.7  741.68  4996.2  741.18  5019.2  741.68  5057.3  742.02
  5113.9  754.87  5200.8  765.24  5334.7  771.56  5697.1  774.72  5813.3  769.35
  5895.1  767.37  5993.9   775.9  6071.8  778.41    6199   792.3  6241.6  794.88
#Mann= 11 ,-1 , 0
  3964.2     .12       0  4055.7    .035       0    4211     .07       0
  4345.8    .035       0  4559.7     .12       0  4790.8     .07       0
    4815     .12       0  4995.7     .05       0  5019.2     .12       0
  5813.3     .07       0    6199     .12       0
Bank Sta=4995.7,5019.2
XS Rating Curve= 0 ,0
Exp/Cntr=0.3,0.1

Type RM Length L Ch R = 1 ,1193    ,561,561,561
BEGIN DESCRIPTION:
Bear Creek 2.0
END DESCRIPTION:
XS GIS Cut Line= 3
       2197453.3     13785810.26        2198275.       13785575.
      2199007.08     13784916.17
#Sta/Elev= 30
  4144.8  811.12  4216.5  808.91  4323.1  807.05  4333.8  802.51  4377.3  799.22
  4473.5   797.6  4512.4  793.83    4521  788.91  4546.2  790.98  4562.6  785.44
  4604.2  787.91  4686.5  771.93  4730.6  776.21  4764.4  773.57  4812.3  764.92
  4864.3  741.25  4957.9  737.83  4994.9  730.72  4995.4  730.22  5018.4  730.72
    5035  736.48  5077.8  739.52  5350.2  752.46  5410.2  746.08  5444.8  747.96
  5486.4  751.47    5559  750.36  5679.3  762.64  5758.8  765.27  5984.4  778.58
#Mann= 11 ,-1 , 0
  4144.8     .12       0  4216.5    .035       0  4323.1     .12       0
  4377.3     .07       0  4994.9     .05       0  5018.4     .07       0
  5077.8     .12       0  5350.2     .07       0  5444.8     .12       0
  5486.4     .07       0  5758.8     .12       0
Bank Sta=4994.9,5018.4
XS Rating Curve= 0 ,0
Exp/Cntr=0.3,0.1

Type RM Length L Ch R = 1 ,632     ,460,460,460
BEGIN DESCRIPTION:
Bear Creek 1.0
END DESCRIPTION:
XS GIS Cut Line= 3
      2198374.98     13786225.03        2198575.       13785875.
      2198874.98     13785325.04
#Sta/Elev= 30
  4596.4   815.1  4674.6  810.38  4830.4  801.32  4895.9  794.67  4905.2  792.18
  4926.8   759.6  4932.6  760.29    4942  752.67  4948.4   743.5  4954.2  745.29
  4964.3  739.09    4970   738.4  4984.9  727.79  4985.4  727.29  5008.5  727.79
  5008.8  727.89  5029.4  732.21  5111.1  740.69  5220.2  741.75    5280   745.2
  5334.2  743.12  5361.7  742.24  5383.5  739.81  5389.2  736.26  5405.3  735.47
  5427.2  742.23  5465.1  747.52  5525.1   751.6  5581.1  756.93    5626  759.21
#Mann= 8 ,-1 , 0
  4596.4     .12       0  4674.6     .07       0  4984.9     .05       0
  5008.5     .07       0  5008.8     .12       0  5334.2     .07       0
  5525.1     .12       0  5581.1     .07       0
Bank Sta=4984.9,5008.5
XS Rating Curve= 0 ,0
Exp/Cntr=0.3,0.1

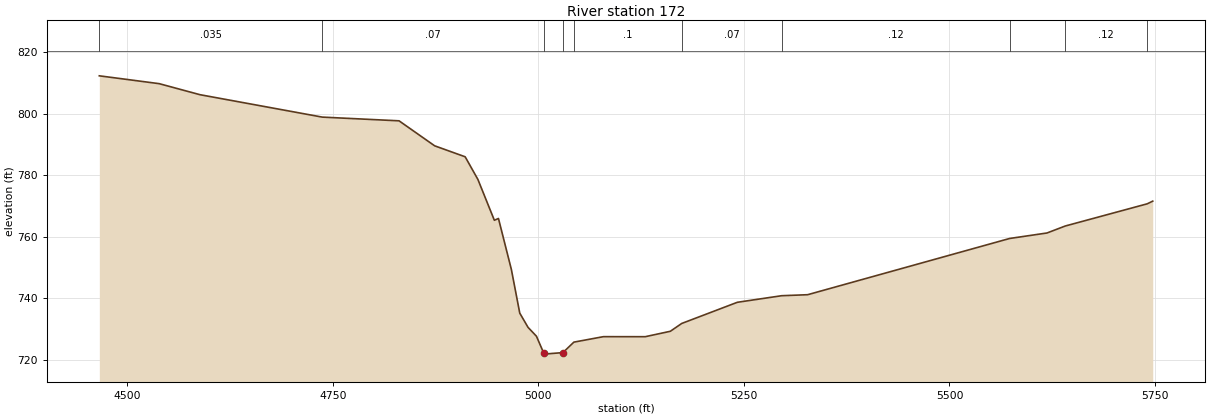
Type RM Length L Ch R = 1 ,172     ,0,0,0
BEGIN DESCRIPTION:
X18106
END DESCRIPTION:
XS GIS Cut Line= 3
      2198726.49     13786359.12       2199002.5     13786010.19
      2199158.49     13785188.67
#Sta/Elev= 30
  4466.1   812.3  4538.9  809.75  4588.5  806.16  4737.2  798.87  4830.6  797.66
  4873.9  789.53    4911  785.96  4926.5  778.59  4946.5  765.31  4951.5  765.89
  4967.2   749.3  4977.4   735.1  4987.5  730.46  4997.7  727.58  5006.3  722.26
  5006.8  721.76  5029.9  722.26  5043.2  725.66  5079.1  727.44    5130  727.43
  5160.5  729.19  5174.4  731.74    5242  738.62  5295.8  740.76  5327.5  741.09
  5573.1  759.38  5618.6  761.17  5640.8  763.44  5740.5  770.66  5747.2  771.53
#Mann= 10 ,-1 , 0
  4466.1    .035       0  4737.2     .07       0  5006.3     .05       0
  5029.9     .07       0  5043.2      .1       0  5174.4     .07       0
  5295.8     .12       0  5573.1     .07       0  5640.8     .12       0
  5740.5     .07       0
Bank Sta=5006.3,5029.9
XS Rating Curve= 0 ,0
Exp/Cntr=0.3,0.1

Chan Stop Cuts=-1
Use User Specified Reach Order=0
Composite Channel Slope=5