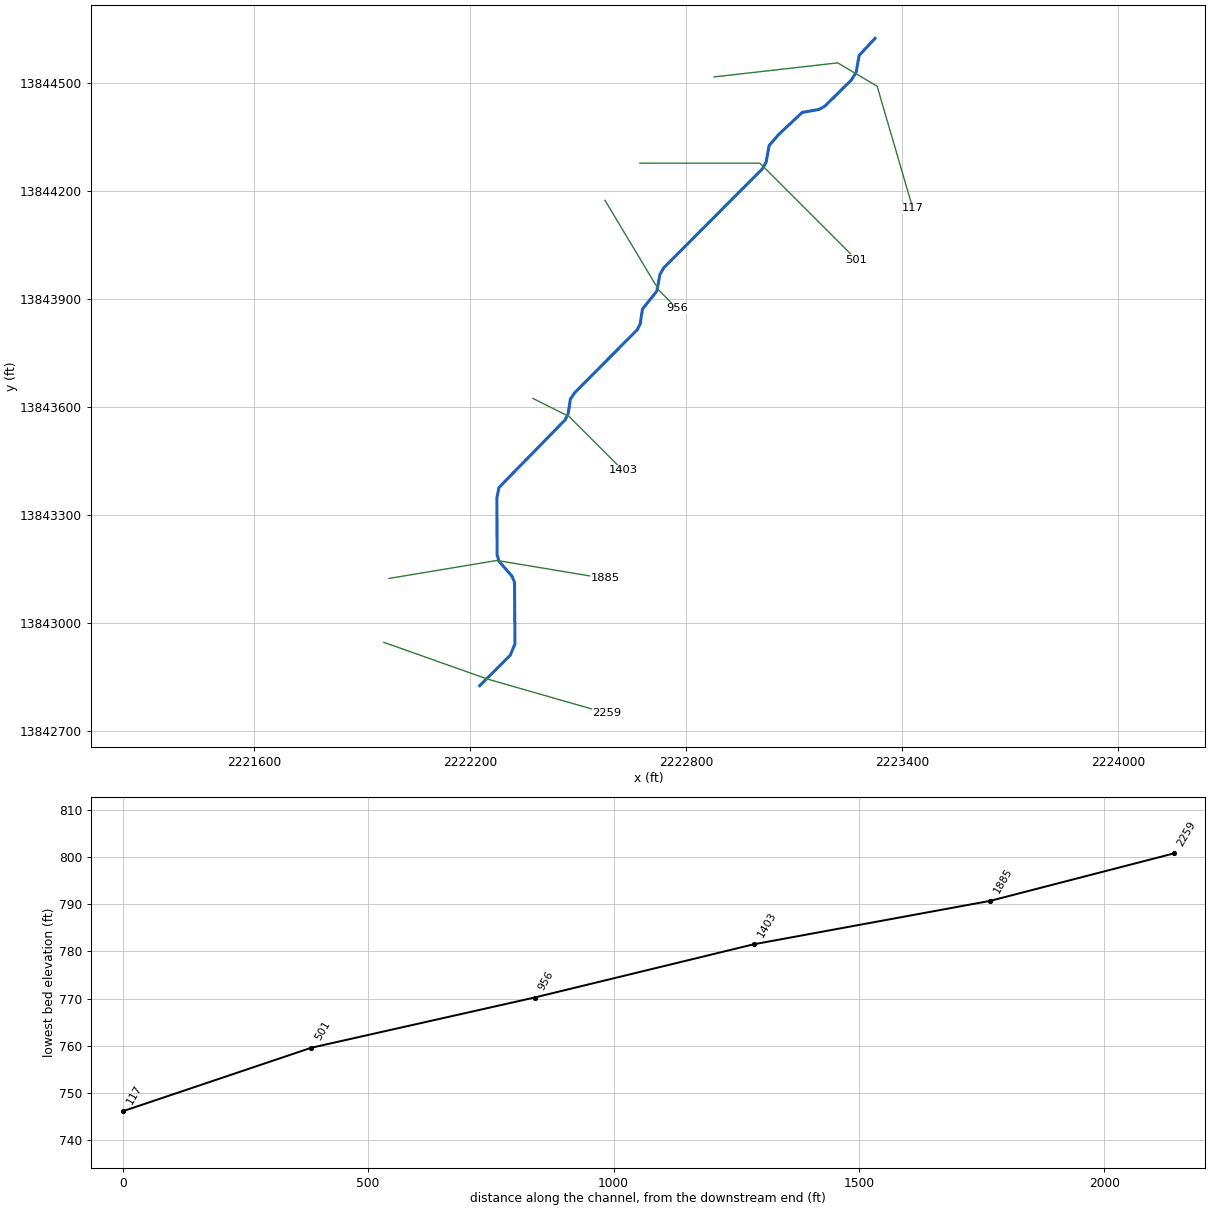
--- Bear Tributary 3.prj (project) ---

Proj Title=Bear Tributary 3 Base Level Engineering
Current Plan=p01
Default Exp/Contr=0.3,0.1
English Units
Geom File=g01
Flow File=f01
Plan File=p01
BEGIN DESCRIPTION:
Bear Tributary 3
END DESCRIPTION:

--- Bear Tributary 3.p01 (plan) ---

Plan Title=Multiple Run
Short Identifier=Multiple
Geom File=g01
Flow File=f01
Subcritical Flow
K Sum by GR= 0
Std Step Tol= 0.01
Critical Tol= 0.01
Num of Std Step Trials= 20
Max Error Tol= 0.3
Flow Tol Ratio= 0.001
Split Flow NTrial= 30
Split Flow Tol= 0.02
Split Flow Ratio= 0.02
Log Output Level= 0
Friction Slope Method= 1
Unsteady Friction Slope Method= 2
Unsteady Bridges Friction Slope Method= 1
Parabolic Critical Depth
Global Vel Dist=  1 , 1 , 1
Global Log Level= 0
CheckData=True
Encroach Param= -1, 0, 0, 0
BEGIN DESCRIPTION:
Multiple Run
END DESCRIPTION:

--- Bear Tributary 3.f01 (steady flow) ---

Flow Title=Multiple
Number of Profiles=7
Profile Names=10-year,25-year,50-year,1pct_min,100-year,1pct_plu,500-year
River Rch & RM= Bear Tributary 3,Reach-1,2259
     760    1266    1743    1166    2326    4642    4092
Boundary for River Rch & Prof#=Bear Tributary 3,Reach-1,1
Up Type=0
Dn Type=3
Dn Slope=0.005
Boundary for River Rch & Prof#=Bear Tributary 3,Reach-1,2
Up Type=0
Dn Type=3
Dn Slope=0.005
Boundary for River Rch & Prof#=Bear Tributary 3,Reach-1,3
Up Type=0
Dn Type=3
Dn Slope=0.005
Boundary for River Rch & Prof#=Bear Tributary 3,Reach-1,4
Up Type=0
Dn Type=3
Dn Slope=0.005
Boundary for River Rch & Prof#=Bear Tributary 3,Reach-1,5
Up Type=0
Dn Type=3
Dn Slope=0.005
Boundary for River Rch & Prof#=Bear Tributary 3,Reach-1,6
Up Type=0
Dn Type=3
Dn Slope=0.005
Boundary for River Rch & Prof#=Bear Tributary 3,Reach-1,7
Up Type=0
Dn Type=3
Dn Slope=0.005

--- Bear Tributary 3.g01 (geometry) ---

Geom Title=Existing Conditions

River Reach=Bear Tributary 3,Reach-1
Reach XY= 30
      2222227.31     13842827.31      2222311.73     13842911.64
      2222324.93     13842943.21      2222323.78     13843114.49
      2222316.86     13843131.06      2222280.75     13843172.67
      2222275.52     13843190.22      2222274.63     13843347.88
      2222280.46     13843377.45      2222464.22     13843565.32
      2222472.47     13843581.05      2222478.98     13843623.35
      2222491.65     13843641.67      2222664.24     13843815.32
      2222672.50     13843831.04      2222679.19     13843873.26
      2222718.90     13843922.81      2222727.61     13843969.37
      2222738.62     13843988.21      2223011.37     13844261.79
      2223022.46     13844281.05      2223030.85     13844327.30
      2223057.92     13844358.58      2223122.70     13844419.15
      2223168.96     13844427.53      2223184.70     13844435.77
      2223258.40     13844508.28      2223272.55     13844530.55
      2223280.71     13844577.35      2223325.00     13844625.00

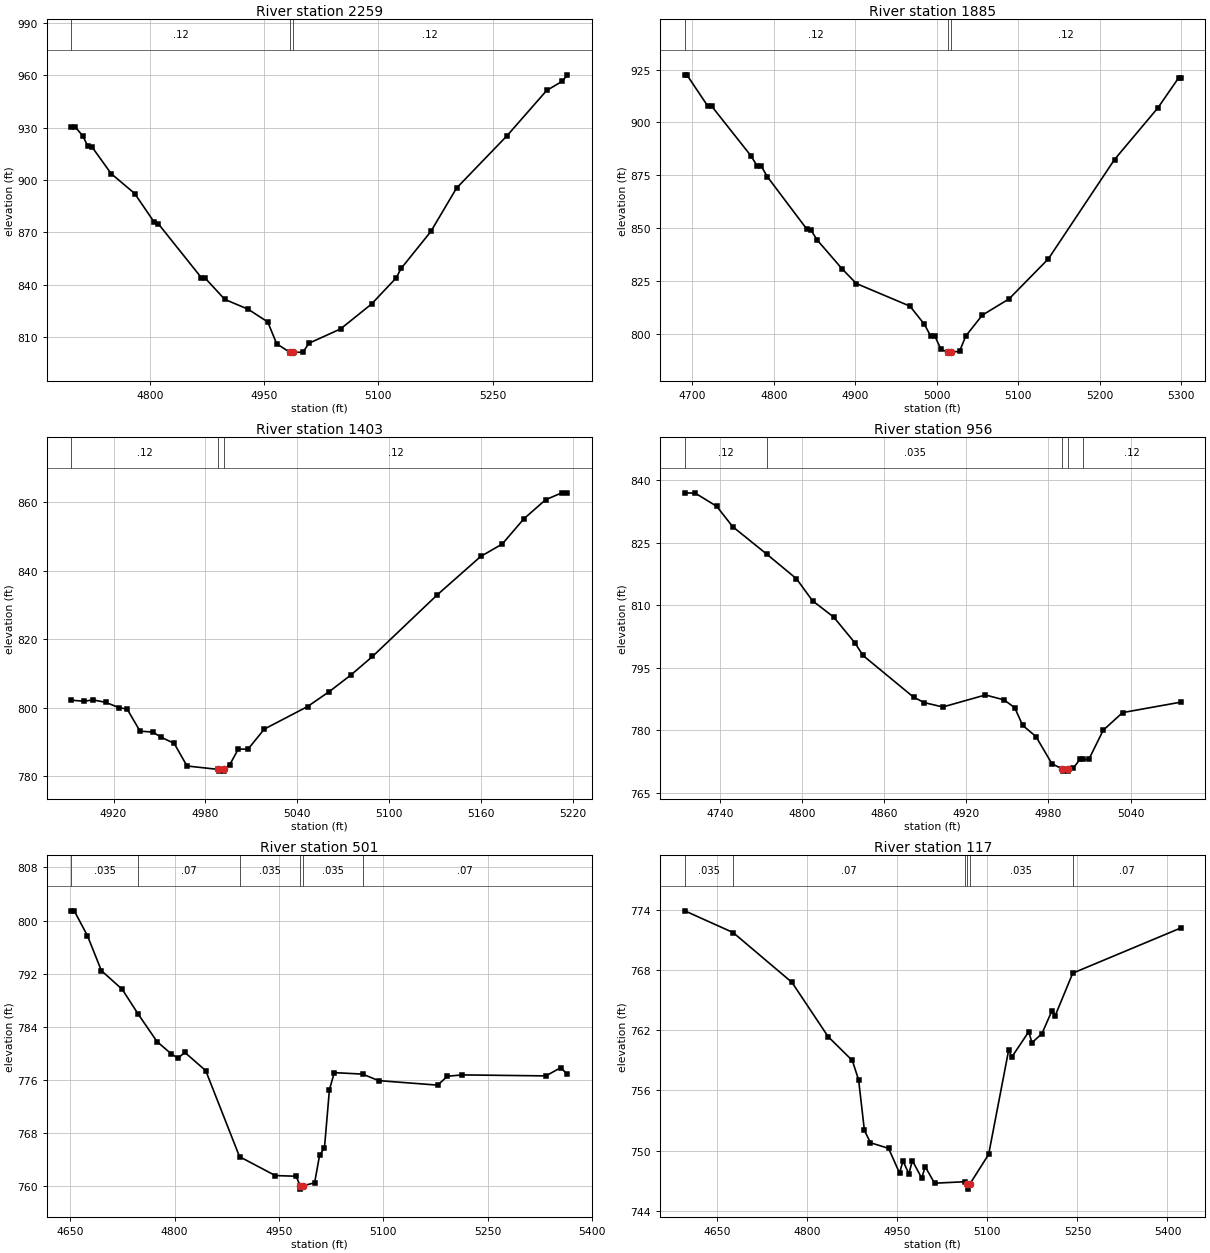
Type RM Length L Ch R = 1,2259,374,374,374
BEGIN DESCRIPTION:
X18172
END DESCRIPTION:
XS GIS Cut Line= 3
      2221961.07     13842947.50      2222247.51     13842845.94
      2222581.05     13842750.28
#Sta/Elev= 30
  4697.2  930.50  4701.9  930.50  4712.0  925.22  4718.5  919.55  4723.8  919.11
  4749.3  903.60  4780.2  892.19  4805.8  875.80  4811.1  874.92  4867.6  844.06
  4872.9  843.64  4898.4  831.56  4929.3  825.87  4954.9  818.60  4966.6  806.11
  4983.8  801.25  4984.0  800.75  4987.8  801.25  5001.1  801.26  5008.9  806.40
  5050.5  814.63  5091.1  828.88  5123.3  843.77  5130.0  849.28  5169.0  870.46
  5202.7  895.30  5269.0  925.32  5321.0  951.23  5341.8  956.61  5348.1  960.21
#Mann=3,-1,0
  4697.2    0.12       0  4983.8    0.05       0  4987.8    0.12       0
Bank Sta=4983.8,4987.8
Exp/Cntr=0.3,0.1

Type RM Length L Ch R = 1,1885,482,482,482
BEGIN DESCRIPTION:
Bear Tributary 3 4.0
END DESCRIPTION:
XS GIS Cut Line= 3
      2221975.00     13843125.00      2222275.00     13843175.00
      2222575.02     13843125.00
#Sta/Elev= 30
  4690.8  922.50  4693.3  922.50  4718.7  907.88  4723.8  907.65  4771.9  884.18
  4779.5  879.40  4784.6  879.25  4792.2  874.18  4840.3  849.53  4845.4  849.13
  4853.0  844.38  4883.4  830.78  4901.2  823.68  4967.1  812.94  4984.8  804.31
  4992.4  798.83  4997.5  798.83  5005.1  792.51  5013.2  791.21  5013.5  790.71
  5017.2  791.21  5027.9  791.56  5035.5  798.80  5055.8  808.69  5088.7  816.42
  5136.9  835.38  5218.0  882.40  5271.2  906.85  5296.5  920.98  5299.1  920.98
#Mann=3,-1,0
  4690.8    0.12       0  5013.2    0.05       0  5017.2    0.12       0
Bank Sta=5013.2,5017.2
Exp/Cntr=0.3,0.1

Type RM Length L Ch R = 1,1403,447,447,447
BEGIN DESCRIPTION:
Bear Tributary 3 3.0
END DESCRIPTION:
XS GIS Cut Line= 3
      2222374.97     13843625.02      2222475.00     13843575.00
      2222625.02     13843424.98
#Sta/Elev= 30
  4892.5  802.19  4900.9  801.88  4906.5  802.29  4914.9  801.57  4923.3  800.06
  4928.9  799.60  4937.3  793.16  4945.6  792.91  4951.2  791.37  4959.6  789.61
  4968.0  783.01  4988.4  782.01  4988.6  781.51  4992.1  781.51  4992.4  782.01
  4996.0  783.44  5001.5  787.93  5007.9  787.93  5018.5  793.76  5046.8  800.35
  5060.9  804.68  5075.0  809.51  5089.2  814.94  5131.6  832.95  5159.9  844.11
  5174.0  847.74  5188.2  855.13  5202.3  860.64  5212.9  862.67  5216.5  862.67
#Mann=3,-1,0
  4892.5    0.12       0  4988.4    0.05       0  4992.4    0.12       0
Bank Sta=4988.4,4992.4
Exp/Cntr=0.3,0.1

Type RM Length L Ch R = 1,956,455,455,455
BEGIN DESCRIPTION:
Bear Tributary 3 2.0
END DESCRIPTION:
XS GIS Cut Line= 3
      2222575.01     13844174.98      2222725.00     13843925.00
      2222774.98     13843875.02
#Sta/Elev= 30
  4714.4  836.99  4722.1  836.90  4737.7  833.76  4749.4  828.87  4774.4  822.25
  4796.0  816.37  4807.7  811.10  4823.2  807.18  4838.8  800.94  4844.6  797.97
  4881.5  787.98  4889.3  786.67  4902.9  785.62  4934.0  788.50  4947.6  787.32
  4955.4  785.45  4961.2  781.22  4970.9  778.53  4982.6  772.00  4990.3  770.73
  4990.6  770.23  4994.1  770.23  4994.3  770.73  4998.1  770.92  5003.0  773.02
  5005.0  773.02  5009.5  773.02  5020.1  780.06  5034.2  784.27  5076.6  786.77
#Mann=5,-1,0
  4714.4    0.12       0  4774.4   0.035       0  4990.3   0.035       0
  4994.3   0.035       0  5005.0    0.12       0
Bank Sta=4990.3,4994.3
Exp/Cntr=0.3,0.1

Type RM Length L Ch R = 1,501,384,384,384
BEGIN DESCRIPTION:
Bear Tributary 3 1.0
END DESCRIPTION:
XS GIS Cut Line= 3
      2222671.99     13844278.24      2223005.32     13844278.24
      2223273.57     13844009.98
#Sta/Elev= 30
  4651.7  801.47  4655.7  801.47  4674.7  797.72  4694.7  792.47  4724.7  789.65
  4747.8  785.90  4774.7  781.79  4794.7  779.99  4804.7  779.29  4814.7  780.16
  4844.7  777.42  4893.3  764.47  4944.7  761.63  4974.7  761.53  4980.4  760.09
  4980.6  759.59  4984.4  760.09  5001.2  760.54  5008.3  764.66  5015.4  765.84
  5022.5  774.56  5029.5  777.12  5070.1  776.90  5093.2  775.92  5178.0  775.24
  5192.2  776.58  5213.4  776.78  5333.6  776.63  5354.8  777.86  5364.4  776.90
#Mann=6,-1,0
  4651.7   0.035       0  4747.8    0.07       0  4893.3   0.035       0
  4980.4   0.035       0  4984.4   0.035       0  5070.1    0.07       0
Bank Sta=4980.4,4984.4
Exp/Cntr=0.3,0.1

Type RM Length L Ch R = 1,117,0,0,0
BEGIN DESCRIPTION:
X18171
END DESCRIPTION:
XS GIS Cut Line= 4
      2222877.69     13844517.82      2223221.47     13844556.88
      2223330.84     13844491.78      2223429.80     13844153.22
#Sta/Elev= 30
  4595.9  773.93  4676.4  771.76  4774.4  766.79  4834.7  761.37  4875.0  758.99
  4885.5  757.04  4895.1  752.02  4905.2  750.78  4935.4  750.22  4953.6  747.76
  4959.4  748.96  4969.2  747.68  4975.0  748.99  4990.6  747.25  4996.4  748.39
  5012.0  746.74  5062.6  746.89  5066.7  746.65  5066.9  746.15  5070.7  746.65
  5102.1  749.62  5135.5  760.05  5140.7  759.34  5169.0  761.87  5174.2  760.76
  5190.8  761.67  5207.6  763.96  5212.8  763.44  5242.2  767.71  5421.9  772.21
#Mann=6,-1,0
  4595.9   0.035       0  4676.4    0.07       0  5062.6   0.035       0
  5066.7    0.05       0  5070.7   0.035       0  5242.2    0.07       0
Bank Sta=5066.7,5070.7
Exp/Cntr=0.3,0.1

Chan Stop Cuts=-1