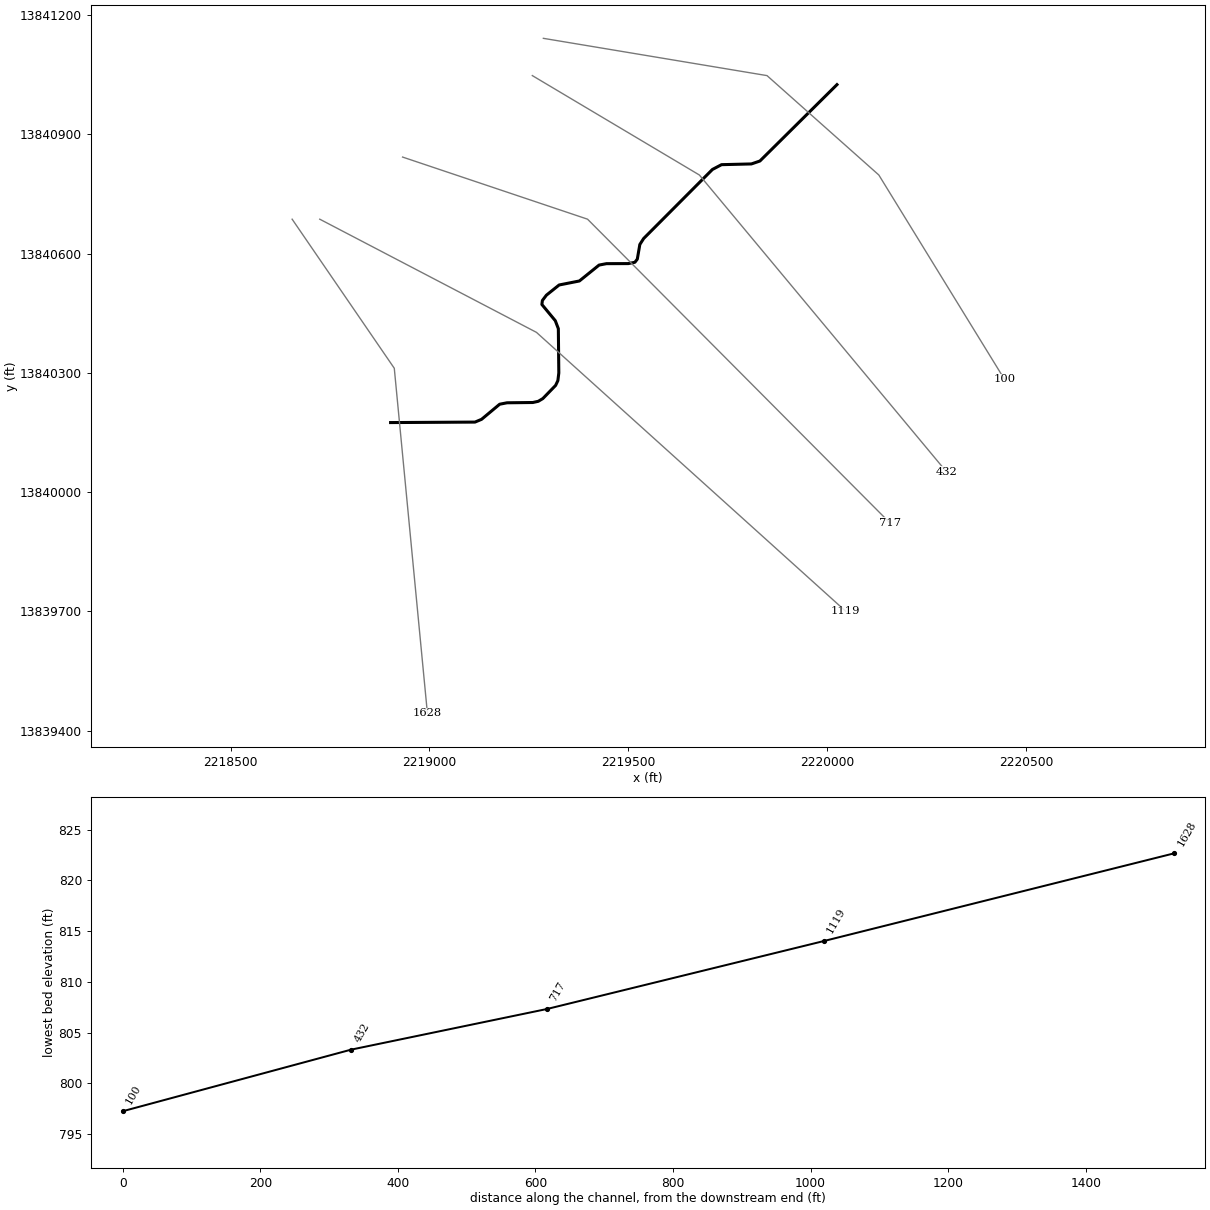
--- Bear Tributary 6.prj (project) ---

Proj Title=Bear Tributary 6 Base Level Engineering
Current Plan=p01
Default Exp/Contr=0.3,0.1
English Units
Geom File=g01
Flow File=f01
Plan File=p01
BEGIN DESCRIPTION:
Bear Tributary 6
END DESCRIPTION:

--- Bear Tributary 6.p01 (plan) ---

Plan Title=Multiple Run
Short Identifier=Multiple
Geom File=g01
Flow File=f01
Subcritical Flow
K Sum by GR= 0
Std Step Tol= 0.01
Critical Tol= 0.01
Num of Std Step Trials= 20
Max Error Tol= 0.3
Flow Tol Ratio= 0.001
Split Flow NTrial= 30
Split Flow Tol= 0.02
Split Flow Ratio= 0.02
Log Output Level= 0
Friction Slope Method= 1
Unsteady Friction Slope Method= 2
Unsteady Bridges Friction Slope Method= 1
Parabolic Critical Depth
Global Vel Dist=  1 , 1 , 1
Global Log Level= 0
CheckData=True
Encroach Param= -1, 0, 0, 0
BEGIN DESCRIPTION:
Multiple Run
END DESCRIPTION:

--- Bear Tributary 6.f01 (steady flow) ---

Flow Title=Multiple
Number of Profiles=7
Profile Names=10-year,25-year,50-year,1pct_min,100-year,1pct_plu,500-year
River Rch & RM= Bear Tributary 6,Reach-1,1628
    1111    1886    2626    1773    3537    7057    6344
Boundary for River Rch & Prof#=Bear Tributary 6,Reach-1,1
Up Type=0
Dn Type=3
Dn Slope=0.005
Boundary for River Rch & Prof#=Bear Tributary 6,Reach-1,2
Up Type=0
Dn Type=3
Dn Slope=0.005
Boundary for River Rch & Prof#=Bear Tributary 6,Reach-1,3
Up Type=0
Dn Type=3
Dn Slope=0.005
Boundary for River Rch & Prof#=Bear Tributary 6,Reach-1,4
Up Type=0
Dn Type=3
Dn Slope=0.005
Boundary for River Rch & Prof#=Bear Tributary 6,Reach-1,5
Up Type=0
Dn Type=3
Dn Slope=0.005
Boundary for River Rch & Prof#=Bear Tributary 6,Reach-1,6
Up Type=0
Dn Type=3
Dn Slope=0.005
Boundary for River Rch & Prof#=Bear Tributary 6,Reach-1,7
Up Type=0
Dn Type=3
Dn Slope=0.005

--- Bear Tributary 6.g01 (geometry) ---

Geom Title=Existing Conditions

River Reach=Bear Tributary 6,Reach-1
Reach XY= 30
      2218902.23     13840175.00      2219114.50     13840176.21
      2219131.06     13840183.14      2219176.60     13840221.14
      2219195.11     13840224.75      2219259.93     13840225.46
      2219273.75     13840228.51      2219285.16     13840235.36
      2219317.33     13840268.48      2219323.04     13840280.65
      2219325.36     13840299.79      2219324.18     13840411.14
      2219316.52     13840431.21      2219282.80     13840471.97
      2219284.01     13840482.02      2219294.13     13840495.42
      2219326.16     13840521.06      2219377.12     13840531.14
      2219426.65     13840571.14      2219445.25     13840574.70
      2219500.12     13840574.87      2219516.66     13840578.16
      2219522.78     13840586.05      2219529.15     13840622.92
      2219538.74     13840637.95      2219711.70     13840811.60
      2219734.64     13840823.68      2219809.78     13840825.53
      2219831.17     13840832.86      2220025.00     13841025.00

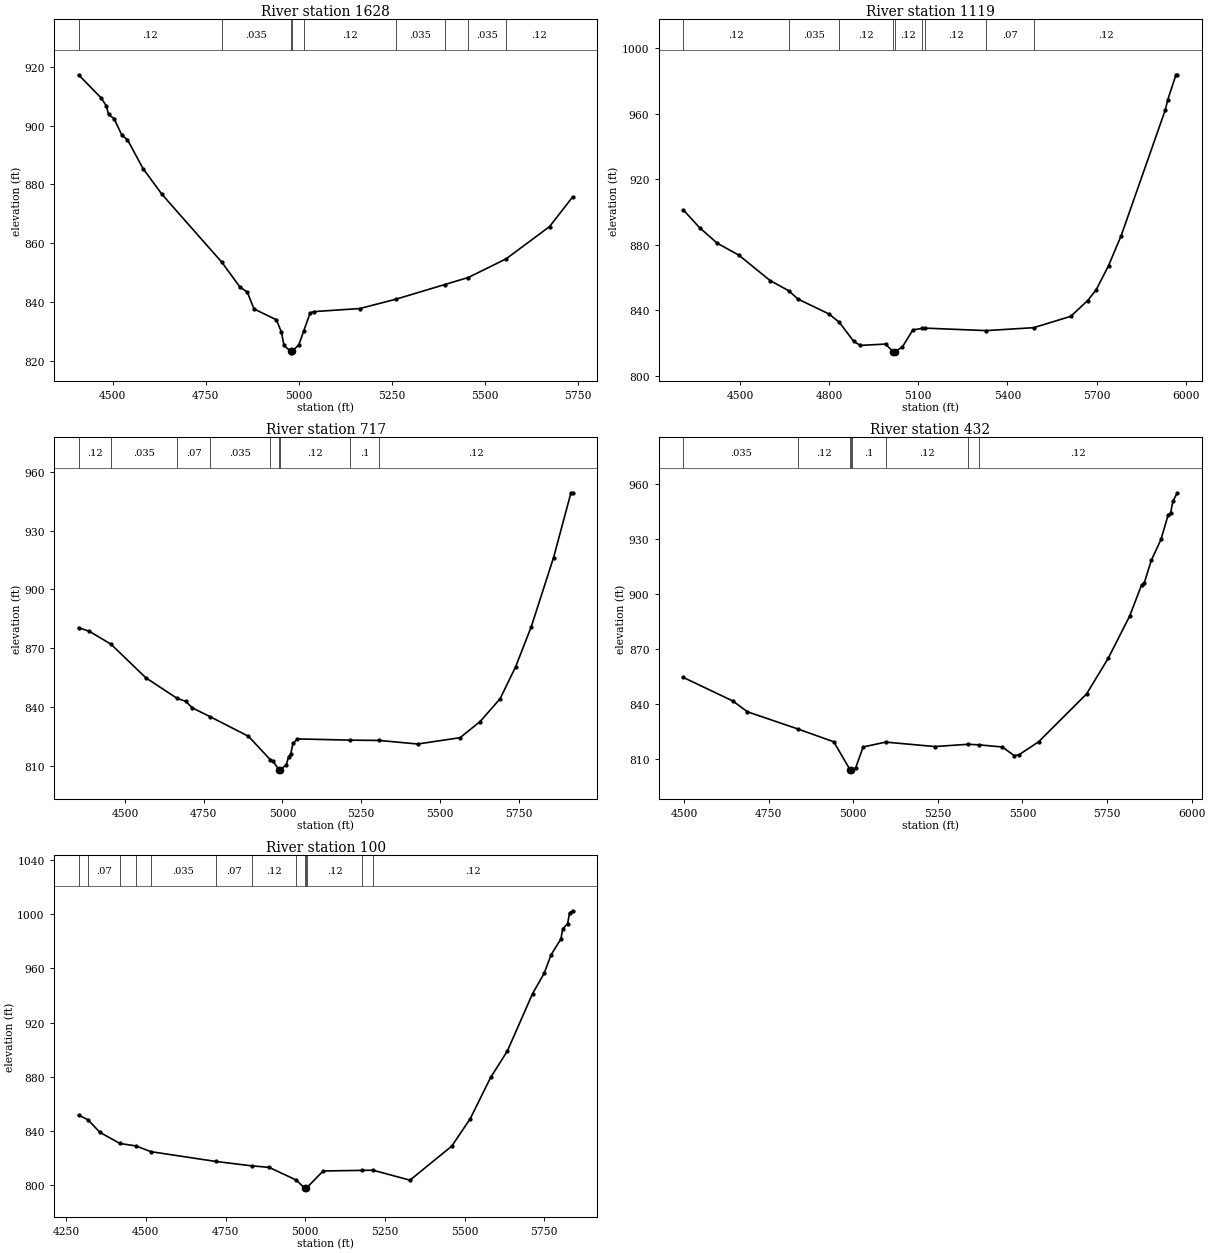
Type RM Length L Ch R = 1,1628,509,509,509
BEGIN DESCRIPTION:
X18177
END DESCRIPTION:
XS GIS Cut Line= 3
      2218654.59     13840686.58      2218911.53     13840311.58
      2218994.86     13839443.55
#Sta/Elev= 30
  4408.2  917.34  4467.8  909.59  4482.7  906.81  4488.7  903.82  4503.6  902.40
  4524.6  896.75  4539.5  895.23  4581.4  885.40  4632.2  876.63  4793.4  853.44
  4841.4  845.10  4861.4  843.30  4879.4  837.60  4939.7  833.90  4953.1  829.64
  4959.8  825.16  4977.9  823.16  4978.1  822.66  4981.9  823.16  5000.0  825.47
  5012.6  830.02  5030.1  836.25  5040.2  836.70  5163.2  837.74  5260.6  840.93
  5391.0  845.89  5454.7  848.31  5556.3  854.66  5673.1  865.66  5734.8  875.72
#Mann=9,-1,0
  4408.2    0.12       0  4793.4   0.035       0  4977.9   0.035       0
  4981.9   0.035       0  5012.6    0.12       0  5260.6   0.035       0
  5391.0    0.12       0  5454.7   0.035       0  5556.3    0.12       0
Bank Sta=4977.9,4981.9
Exp/Cntr=0.3,0.1

Type RM Length L Ch R = 1,1119,402,402,402
BEGIN DESCRIPTION:
X18176
END DESCRIPTION:
XS GIS Cut Line= 3
      2218724.07     13840686.56      2219269.17     13840401.86
      2220046.95     13839700.47
#Sta/Elev= 30
  4309.3  901.22  4363.9  890.36  4423.2  880.92  4496.4  873.57  4601.2  858.12
  4663.9  851.90  4695.1  846.81  4799.9  837.69  4834.5  832.55  4882.6  821.02
  4904.7  818.56  4989.7  819.37  5016.1  814.52  5016.4  814.02  5020.1  814.52
  5046.5  817.66  5081.7  828.02  5113.0  828.93  5122.2  829.10  5328.7  827.58
  5488.0  829.37  5613.0  836.29  5669.8  845.93  5698.2  852.40  5740.1  867.25
  5782.7  885.59  5931.4  962.41  5938.9  968.19  5966.9  983.63  5971.6  983.63
#Mann=9,-1,0
  4309.3    0.12       0  4663.9   0.035       0  4834.5    0.12       0
  5016.1    0.05       0  5020.1    0.12       0  5113.0     0.1       0
  5122.2    0.12       0  5328.7    0.07       0  5488.0    0.12       0
Bank Sta=5016.1,5020.1
Exp/Cntr=0.3,0.1

Type RM Length L Ch R = 1,717,285,285,285
BEGIN DESCRIPTION:
X18175
END DESCRIPTION:
XS GIS Cut Line= 3
      2218932.39     13840842.82      2219397.64     13840686.58
      2220158.03     13839922.72
#Sta/Elev= 30
  4352.7  880.47  4387.1  878.60  4455.4  872.06  4566.4  854.87  4665.4  844.38
  4693.0  842.84  4714.1  839.48  4770.4  835.00  4892.2  824.98  4961.5  813.02
  4970.0  812.30  4989.2  807.83  4989.5  807.33  4993.2  807.83  5012.5  810.48
  5019.5  814.46  5026.6  816.09  5033.7  821.44  5047.8  823.64  5213.7  823.02
  5307.4  822.86  5429.6  821.04  5564.0  824.26  5627.6  832.48  5691.3  844.20
  5740.8  860.61  5790.3  881.04  5861.0  916.32  5916.2  949.39  5921.3  949.39
#Mann=9,-1,0
  4352.7    0.12       0  4455.4   0.035       0  4665.4    0.07       0
  4770.4   0.035       0  4961.5    0.12       0  4989.2    0.05       0
  4993.2    0.12       0  5213.7     0.1       0  5307.4    0.12       0
Bank Sta=4989.2,4993.2
Exp/Cntr=0.3,0.1

Type RM Length L Ch R = 1,432,332,332,332
BEGIN DESCRIPTION:
X18174
END DESCRIPTION:
XS GIS Cut Line= 3
      2219258.73     13841047.71      2219678.89     13840797.69
      2220300.03     13840051.64
#Sta/Elev= 30
  4498.1  854.36  4644.6  841.46  4687.5  835.58  4837.7  826.11  4942.6  819.19
  4990.9  803.82  4991.1  803.32  4994.9  803.82  4996.1  803.85  5007.2  804.92
  5029.4  816.38  5096.2  819.02  5241.5  816.59  5339.7  817.84  5372.8  817.51
  5440.7  816.35  5475.9  811.61  5490.2  812.16  5547.5  819.14  5689.4  845.30
  5753.2  864.72  5816.9  887.89  5852.1  904.91  5859.9  905.95  5880.7  918.25
  5909.4  929.75  5930.2  942.92  5938.0  944.33  5944.5  950.65  5957.8  955.25
#Mann=8,-1,0
  4498.1   0.035       0  4837.7    0.12       0  4990.9    0.05       0
  4994.9    0.12       0  4996.1     0.1       0  5096.2    0.12       0
  5339.7     0.1       0  5372.8    0.12       0
Bank Sta=4990.9,4994.9
Exp/Cntr=0.3,0.1

Type RM Length L Ch R = 1,100,0,0,0
BEGIN DESCRIPTION:
X18173
END DESCRIPTION:
XS GIS Cut Line= 4
      2219286.53     13841141.44      2219849.03     13841047.69
      2220130.28     13840797.69      2220446.25     13840283.82
#Sta/Elev= 30
  4289.0  851.69  4318.4  848.28  4356.0  838.95  4418.8  830.74  4469.4  828.91
  4515.6  824.71  4719.9  817.46  4831.6  814.24  4886.6  813.11  4971.4  803.80
  4998.3  797.75  4998.6  797.25  5002.3  797.75  5006.0  798.32  5056.4  810.45
  5179.0  810.87  5213.0  811.00  5328.6  803.65  5460.0  828.83  5518.0  849.16
  5581.8  879.51  5634.0  898.91  5713.2  941.33  5749.9  956.49  5771.2  969.97
  5802.1  981.72  5807.9  989.10  5823.3  993.09  5829.2 1000.96  5838.8 1002.55
#Mann=13,-1,0
  4289.0   0.035       0  4318.4    0.07       0  4418.8   0.035       0
  4469.4    0.07       0  4515.6   0.035       0  4719.9    0.07       0
  4831.6    0.12       0  4971.4    0.07       0  4998.3    0.05       0
  5002.3    0.07       0  5006.0    0.12       0  5179.0     0.1       0
  5213.0    0.12       0
Bank Sta=4998.3,5002.3
Exp/Cntr=0.3,0.1

Chan Stop Cuts=-1