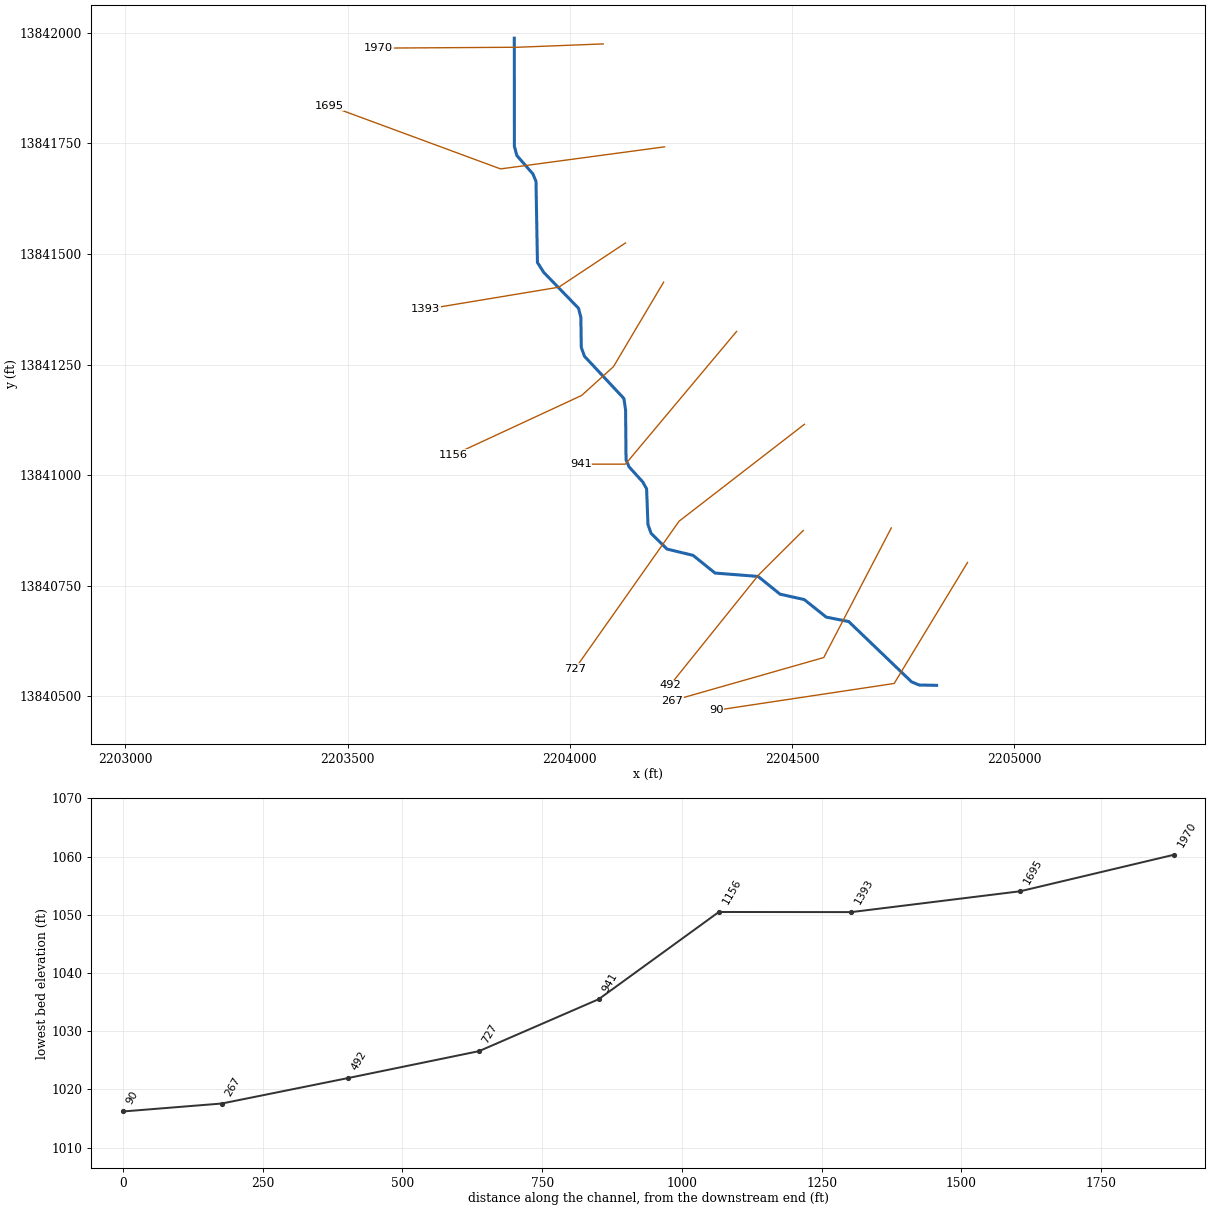
--- Bear Tributary 9.prj (project) ---

Proj Title=Bear Tributary 9 Base Level Engineering
Current Plan=p01
Default Exp/Contr=0.3,0.1
English Units
Geom File=g01
Flow File=f01
Plan File=p01
BEGIN DESCRIPTION:
Bear Tributary 9
END DESCRIPTION:

--- Bear Tributary 9.p01 (plan) ---

Plan Title=Multiple Run
Short Identifier=Multiple
Geom File=g01
Flow File=f01
Subcritical Flow
K Sum by GR= 0
Std Step Tol= 0.01
Critical Tol= 0.01
Num of Std Step Trials= 20
Max Error Tol= 0.3
Flow Tol Ratio= 0.001
Split Flow NTrial= 30
Split Flow Tol= 0.02
Split Flow Ratio= 0.02
Log Output Level= 0
Friction Slope Method= 1
Unsteady Friction Slope Method= 2
Unsteady Bridges Friction Slope Method= 1
Parabolic Critical Depth
Global Vel Dist=  1 , 1 , 1
Global Log Level= 0
CheckData=True
Encroach Param= -1, 0, 0, 0
BEGIN DESCRIPTION:
Multiple Run
END DESCRIPTION:

--- Bear Tributary 9.f01 (steady flow) ---

Flow Title=Multiple
Number of Profiles=7
Profile Names=10-year,25-year,50-year,1pct_min,100-year,1pct_plu,500-year
River Rch & RM= Bear Tributary 9,Reach-1,1970
     996    1679    2324    1560    3112    6209    5519
Boundary for River Rch & Prof#=Bear Tributary 9,Reach-1,1
Up Type=0
Dn Type=3
Dn Slope=0.005
Boundary for River Rch & Prof#=Bear Tributary 9,Reach-1,2
Up Type=0
Dn Type=3
Dn Slope=0.005
Boundary for River Rch & Prof#=Bear Tributary 9,Reach-1,3
Up Type=0
Dn Type=3
Dn Slope=0.005
Boundary for River Rch & Prof#=Bear Tributary 9,Reach-1,4
Up Type=0
Dn Type=3
Dn Slope=0.005
Boundary for River Rch & Prof#=Bear Tributary 9,Reach-1,5
Up Type=0
Dn Type=3
Dn Slope=0.005
Boundary for River Rch & Prof#=Bear Tributary 9,Reach-1,6
Up Type=0
Dn Type=3
Dn Slope=0.005
Boundary for River Rch & Prof#=Bear Tributary 9,Reach-1,7
Up Type=0
Dn Type=3
Dn Slope=0.005

--- Bear Tributary 9.g01 (geometry) ---

Geom Title=Existing Conditions

River Reach=Bear Tributary 9,Reach-1
Reach XY= 30
      2203875.00     13841987.94      2203875.21     13841743.27
      2203880.75     13841722.67      2203916.86     13841681.06
      2203923.78     13841664.49      2203927.07     13841480.86
      2203941.47     13841458.25      2204019.46     13841377.42
      2204024.74     13841356.71      2204025.68     13841288.92
      2204032.88     13841268.84      2204121.44     13841173.53
      2204125.34     13841147.87      2204126.39     13841034.67
      2204133.14     13841018.94      2204164.10     13840984.63
      2204172.64     13840969.02      2204175.61     13840888.78
      2204182.74     13840868.54      2204218.62     13840833.00
      2204277.15     13840818.85      2204326.58     13840778.82
      2204423.42     13840771.17      2204472.82     13840731.12
      2204527.20     13840718.92      2204576.74     13840679.19
      2204627.30     13840669.17      2204768.79     13840532.76
      2204785.76     13840525.75      2204825.00     13840525.00

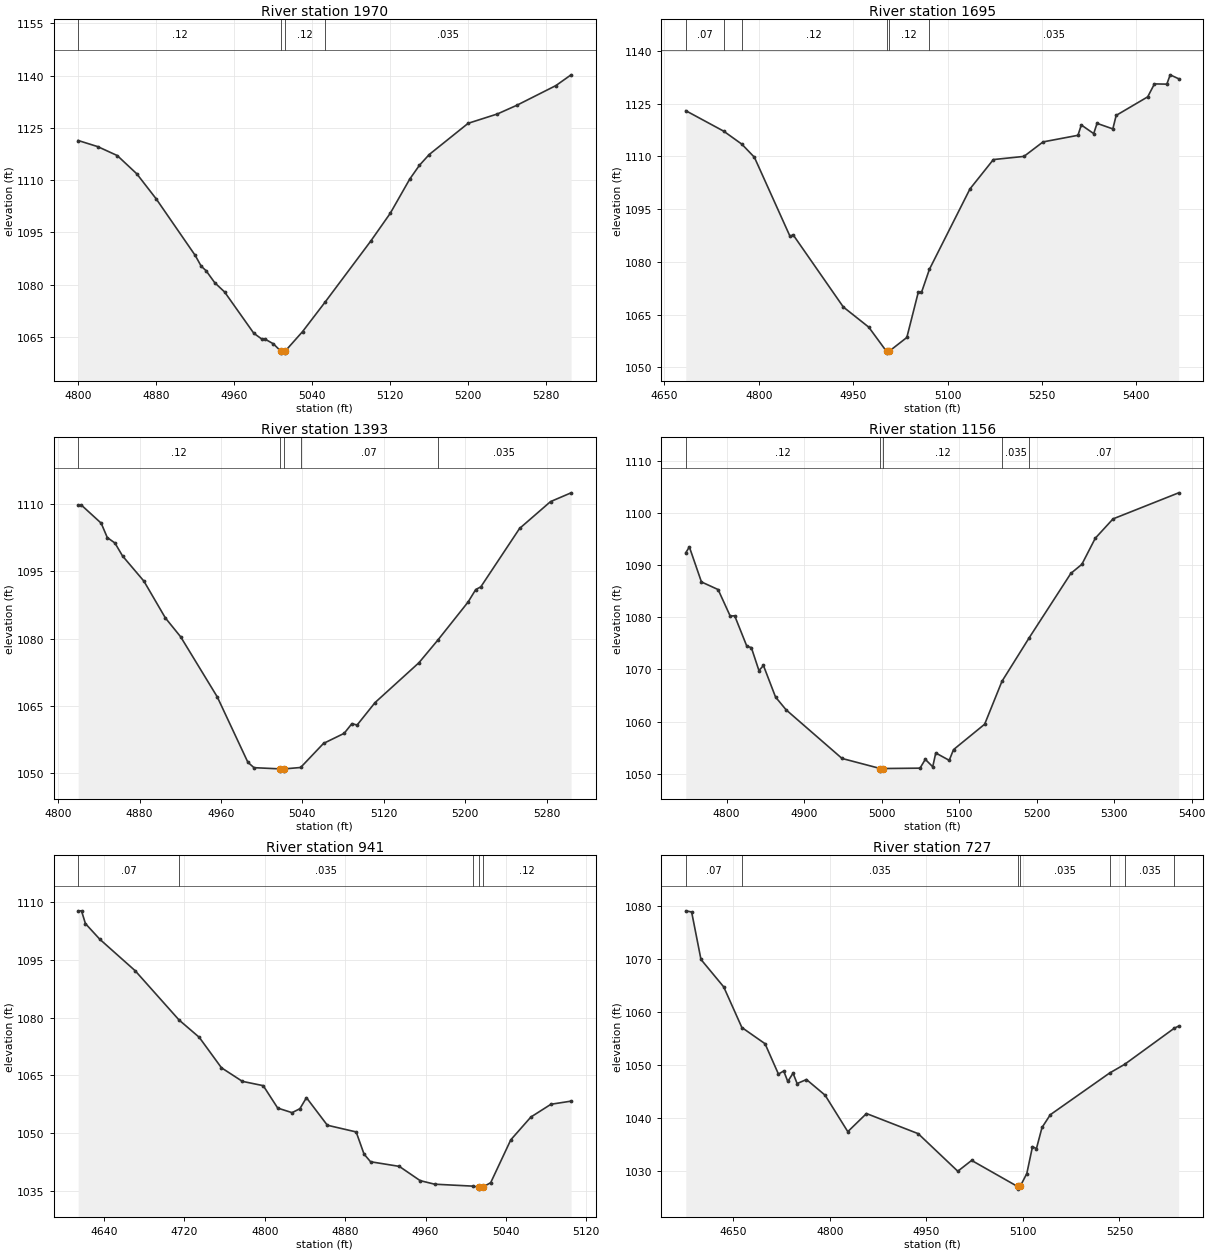
Type RM Length L Ch R = 1,1970,275,275,275
BEGIN DESCRIPTION:
Bear Tributary 9 4.0
END DESCRIPTION:
XS GIS Cut Line= 3
      2204075.05     13841975.00      2203883.58     13841967.47
      2203569.40     13841965.48
#Sta/Elev= 30
  4799.8 1121.35  4819.9 1119.59  4839.9 1117.03  4859.9 1111.80  4879.9 1104.58
  4919.9 1088.36  4926.0 1085.29  4931.0 1083.99  4940.0 1080.51  4950.0 1077.89
  4980.0 1066.03  4988.2 1064.36  4991.4 1064.36  5000.0 1063.01  5008.0 1060.82
  5008.2 1060.32  5011.7 1060.32  5012.0 1060.82  5030.0 1066.48  5052.9 1074.86
  5100.0 1092.47  5120.0 1100.44  5140.0 1110.26  5150.0 1114.24  5160.0 1117.32
  5200.0 1126.29  5230.0 1128.97  5250.0 1131.47  5290.0 1137.11  5305.6 1140.20
#Mann=4,-1,0
  4799.8    0.12       0  5008.0    0.05       0  5012.0    0.12       0
  5052.9   0.035       0
Bank Sta=5008,5012
Exp/Cntr=0.3,0.1

Type RM Length L Ch R = 1,1695,302,302,302
BEGIN DESCRIPTION:
X18182
END DESCRIPTION:
XS GIS Cut Line= 3
      2204213.03     13841742.34      2203844.13     13841692.43
      2203458.92     13841835.26
#Sta/Elev= 30
  4684.1 1123.00  4744.2 1117.19  4773.1 1113.49  4793.1 1109.76  4849.7 1087.27
  4854.7 1087.69  4934.4 1067.17  4974.8 1061.44  5003.0 1054.55  5003.3 1054.05
  5007.0 1054.55  5035.3 1058.50  5053.4 1071.31  5058.6 1071.31  5071.2 1077.90
  5135.6 1100.75  5172.8 1109.10  5221.4 1110.00  5251.7 1114.12  5307.2 1116.00
  5312.5 1118.94  5332.2 1116.48  5337.5 1119.40  5362.6 1117.82  5367.9 1121.66
  5418.0 1126.94  5428.7 1130.62  5448.4 1130.55  5453.7 1133.20  5467.2 1132.08
#Mann=6,-1,0
  4684.1    0.07       0  4744.2   0.035       0  4773.1    0.12       0
  5003.0    0.05       0  5007.0    0.12       0  5071.2   0.035       0
Bank Sta=5003,5007
Exp/Cntr=0.3,0.1

Type RM Length L Ch R = 1,1393,237,237,237
BEGIN DESCRIPTION:
Bear Tributary 9 3.0
END DESCRIPTION:
XS GIS Cut Line= 3
      2204125.02     13841525.02      2203975.00     13841425.00
      2203675.04     13841375.01
#Sta/Elev= 30
  4819.7 1109.83  4822.7 1109.83  4842.3 1105.77  4848.3 1102.56  4855.8 1101.35
  4863.3 1098.46  4884.3 1092.84  4905.4 1084.63  4920.4 1080.43  4956.4 1067.02
  4986.5 1052.43  4992.5 1051.24  5018.3 1050.97  5018.5 1050.47  5022.0 1050.47
  5022.3 1050.97  5038.3 1051.28  5060.8 1056.65  5081.1 1058.90  5088.7 1061.06
  5093.8 1060.75  5111.5 1065.77  5154.6 1074.65  5173.1 1079.68  5202.8 1088.16
  5210.4 1090.97  5215.4 1091.57  5253.5 1104.60  5283.9 1110.58  5304.1 1112.54
#Mann=5,-1,0
  4819.7    0.12       0  5018.3    0.05       0  5022.3    0.12       0
  5038.3    0.07       0  5173.1   0.035       0
Bank Sta=5018.3,5022.3
Exp/Cntr=0.3,0.1

Type RM Length L Ch R = 1,1156,215,215,215
BEGIN DESCRIPTION:
X18181
END DESCRIPTION:
XS GIS Cut Line= 4
      2204210.91     13841436.39      2204098.04     13841245.38
      2204026.42     13841180.27      2203738.88     13841046.23
#Sta/Elev= 30
  4747.4 1092.37  4752.0 1093.49  4767.6 1086.77  4789.1 1085.31  4804.7 1080.23
  4810.5 1080.28  4826.2 1074.43  4832.0 1074.18  4841.8 1069.77  4847.6 1070.75
  4863.2 1064.70  4876.8 1062.25  4949.0 1052.92  4998.3 1050.99  4998.6 1050.49
  5002.3 1050.99  5049.6 1051.06  5056.4 1052.75  5066.0 1051.33  5069.9 1053.97
  5087.3 1052.56  5092.8 1054.61  5133.0 1059.49  5155.3 1067.71  5190.3 1076.03
  5244.2 1088.41  5258.4 1090.15  5275.7 1095.15  5298.6 1098.86  5383.3 1103.86
#Mann=5,-1,0
  4747.4    0.12       0  4998.3    0.05       0  5002.3    0.12       0
  5155.3   0.035       0  5190.3    0.07       0
Bank Sta=4998.3,5002.3
Exp/Cntr=0.3,0.1

Type RM Length L Ch R = 1,941,214,214,214
BEGIN DESCRIPTION:
Bear Tributary 9 2.0
END DESCRIPTION:
XS GIS Cut Line= 3
      2204375.03     13841325.04      2204125.00     13841025.00
      2204024.96     13841025.00
#Sta/Elev= 30
  4614.2 1107.67  4617.5 1107.67  4621.4 1104.36  4635.7 1100.30  4670.9 1092.14
  4714.6 1079.36  4734.7 1074.87  4756.8 1066.97  4777.6 1063.45  4798.4 1062.33
  4812.8 1056.52  4827.1 1055.33  4834.9 1056.36  4841.4 1059.22  4862.2 1052.07
  4890.9 1050.33  4898.7 1044.60  4905.2 1042.60  4933.8 1041.40  4954.6 1037.70
  4969.0 1036.78  5007.5 1036.27  5012.8 1036.00  5013.0 1035.50  5016.8 1036.00
  5024.8 1037.18  5044.8 1048.29  5064.8 1054.20  5084.8 1057.51  5104.8 1058.32
#Mann=5,-1,0
  4614.2    0.07       0  4714.6   0.035       0  5007.5    0.12       0
  5012.8   0.035       0  5016.8    0.12       0
Bank Sta=5012.8,5016.8
Exp/Cntr=0.3,0.1

Type RM Length L Ch R = 1,727,235,235,235
BEGIN DESCRIPTION:
X18180
END DESCRIPTION:
XS GIS Cut Line= 3
      2204527.71     13841115.16      2204245.61     13840895.98
      2204011.25     13840561.81
#Sta/Elev= 30
  4576.5 1079.12  4585.6 1078.90  4600.1 1069.94  4635.4 1064.76  4663.6 1057.09
  4699.6 1054.03  4720.4 1048.30  4728.6 1048.88  4734.9 1046.90  4743.1 1048.47
  4749.4 1046.51  4763.9 1047.27  4792.8 1044.32  4828.1 1037.43  4857.1 1040.85
  4937.4 1037.05  4998.9 1029.96  5020.4 1032.00  5091.7 1027.08  5092.0 1026.58
  5095.7 1027.08  5106.1 1029.53  5114.9 1034.61  5121.0 1034.22  5129.7 1038.22
  5142.6 1040.63  5234.8 1048.51  5257.9 1050.13  5335.1 1056.96  5341.9 1057.36
#Mann=7,-1,0
  4576.5    0.07       0  4663.6   0.035       0  5091.7   0.035       0
  5095.7   0.035       0  5234.8    0.07       0  5257.9   0.035       0
  5335.1    0.07       0
Bank Sta=5091.7,5095.7
Exp/Cntr=0.3,0.1

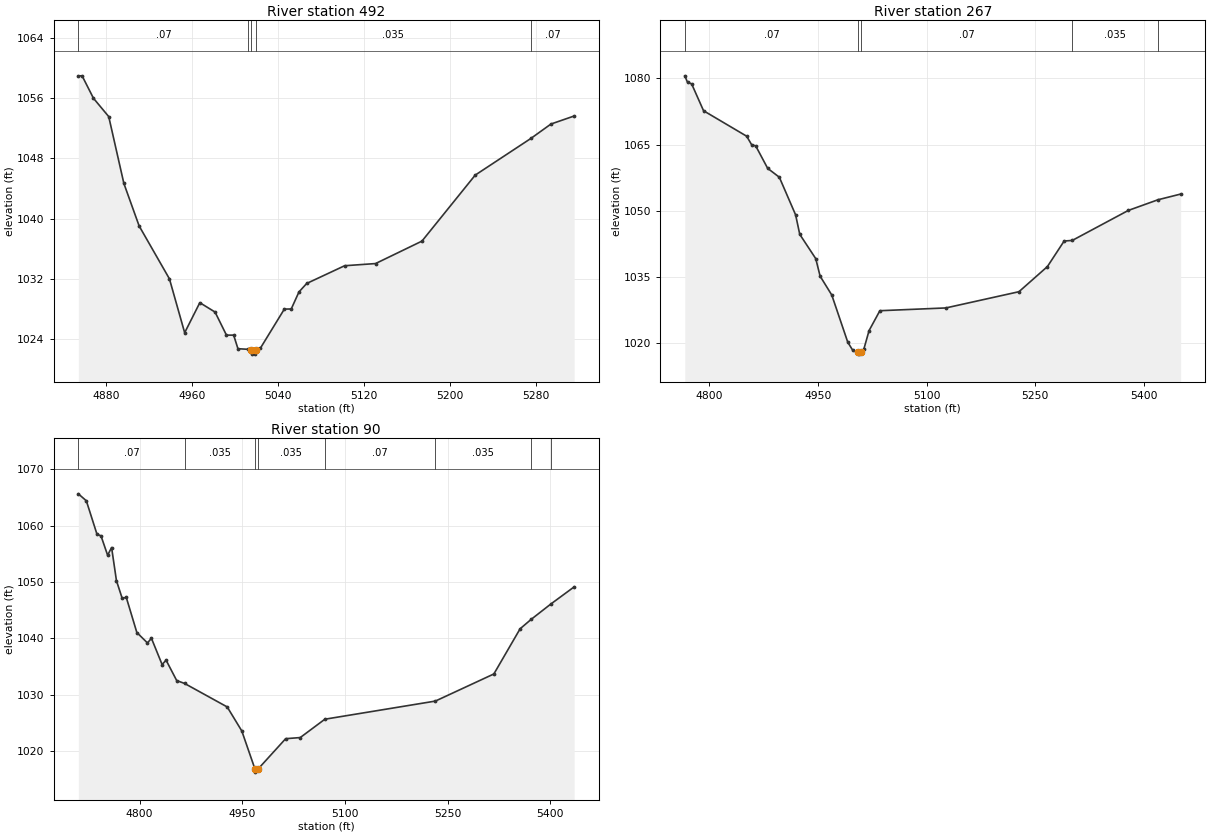
Type RM Length L Ch R = 1,492,225,225,225
BEGIN DESCRIPTION:
Bear Tributary 9 1.0
END DESCRIPTION:
XS GIS Cut Line= 3
      2204524.99     13840874.99      2204425.00     13840775.00
      2204224.98     13840524.97
#Sta/Elev= 30
  4854.2 1059.00  4857.7 1059.00  4868.3 1056.01  4882.5 1053.57  4896.6 1044.67
  4910.8 1039.01  4939.0 1031.97  4953.2 1024.79  4967.3 1028.79  4981.5 1027.54
  4992.1 1024.47  4998.8 1024.47  5002.8 1022.66  5012.6 1022.58  5015.2 1022.44
  5015.5 1021.94  5019.0 1021.94  5019.2 1022.44  5023.6 1022.71  5046.0 1027.94
  5052.4 1027.95  5059.6 1030.22  5066.8 1031.35  5102.1 1033.71  5130.9 1034.00
  5174.1 1036.99  5223.7 1045.78  5275.5 1050.66  5294.2 1052.58  5315.8 1053.65
#Mann=5,-1,0
  4854.2    0.07       0  5012.6   0.035       0  5015.2    0.05       0
  5019.2   0.035       0  5275.5    0.07       0
Bank Sta=5015.2,5019.2
Exp/Cntr=0.3,0.1

Type RM Length L Ch R = 1,267,177,177,177
BEGIN DESCRIPTION:
X18179
END DESCRIPTION:
XS GIS Cut Line= 3
      2204723.05     13840880.82      2204571.13     13840587.82
      2204230.39     13840490.16
#Sta/Elev= 30
  4766.2 1080.54  4770.0 1079.06  4775.6 1078.73  4792.1 1072.64  4851.6 1066.88
  4858.5 1064.95  4864.1 1064.69  4880.6 1059.61  4896.7 1057.60  4919.2 1049.08
  4924.9 1044.68  4947.0 1039.18  4953.0 1035.22  4969.1 1030.95  4991.2 1020.27
  4998.0 1018.46  5005.7 1018.08  5006.0 1017.58  5009.7 1018.08  5013.4 1018.72
  5020.6 1022.91  5035.5 1027.40  5126.6 1028.03  5227.5 1031.70  5266.8 1037.39
  5289.9 1043.17  5301.1 1043.30  5378.5 1050.09  5419.4 1052.50  5450.7 1053.79
#Mann=5,-1,0
  4766.2    0.07       0  5005.7    0.05       0  5009.7    0.07       0
  5301.1   0.035       0  5419.4    0.07       0
Bank Sta=5005.7,5009.7
Exp/Cntr=0.3,0.1

Type RM Length L Ch R = 1,90,0,0,0
BEGIN DESCRIPTION:
X18178
END DESCRIPTION:
XS GIS Cut Line= 3
      2204894.48     13840802.67      2204729.55     13840529.23
      2204329.04     13840468.61
#Sta/Elev= 30
  4710.4 1065.65  4722.1 1064.41  4737.7 1058.45  4743.5 1058.19  4753.2 1054.74
  4759.0 1056.11  4766.1 1050.22  4774.5 1047.07  4780.4 1047.27  4795.9 1041.01
  4811.4 1039.16  4817.2 1039.99  4832.8 1035.32  4838.6 1036.10  4854.1 1032.48
  4865.7 1031.96  4927.9 1027.79  4949.2 1023.53  4968.6 1016.71  4968.9 1016.21
  4972.6 1016.71  5013.3 1022.15  5034.6 1022.35  5070.6 1025.61  5232.0 1028.83
  5317.5 1033.65  5355.8 1041.67  5371.8 1043.33  5400.8 1046.08  5434.8 1049.12
#Mann=8,-1,0
  4710.4    0.07       0  4865.7   0.035       0  4968.6   0.035       0
  4972.6   0.035       0  5070.6    0.07       0  5232.0   0.035       0
  5371.8    0.07       0  5400.8   0.035       0
Bank Sta=4968.6,4972.6
Exp/Cntr=0.3,0.1

Chan Stop Cuts=-1