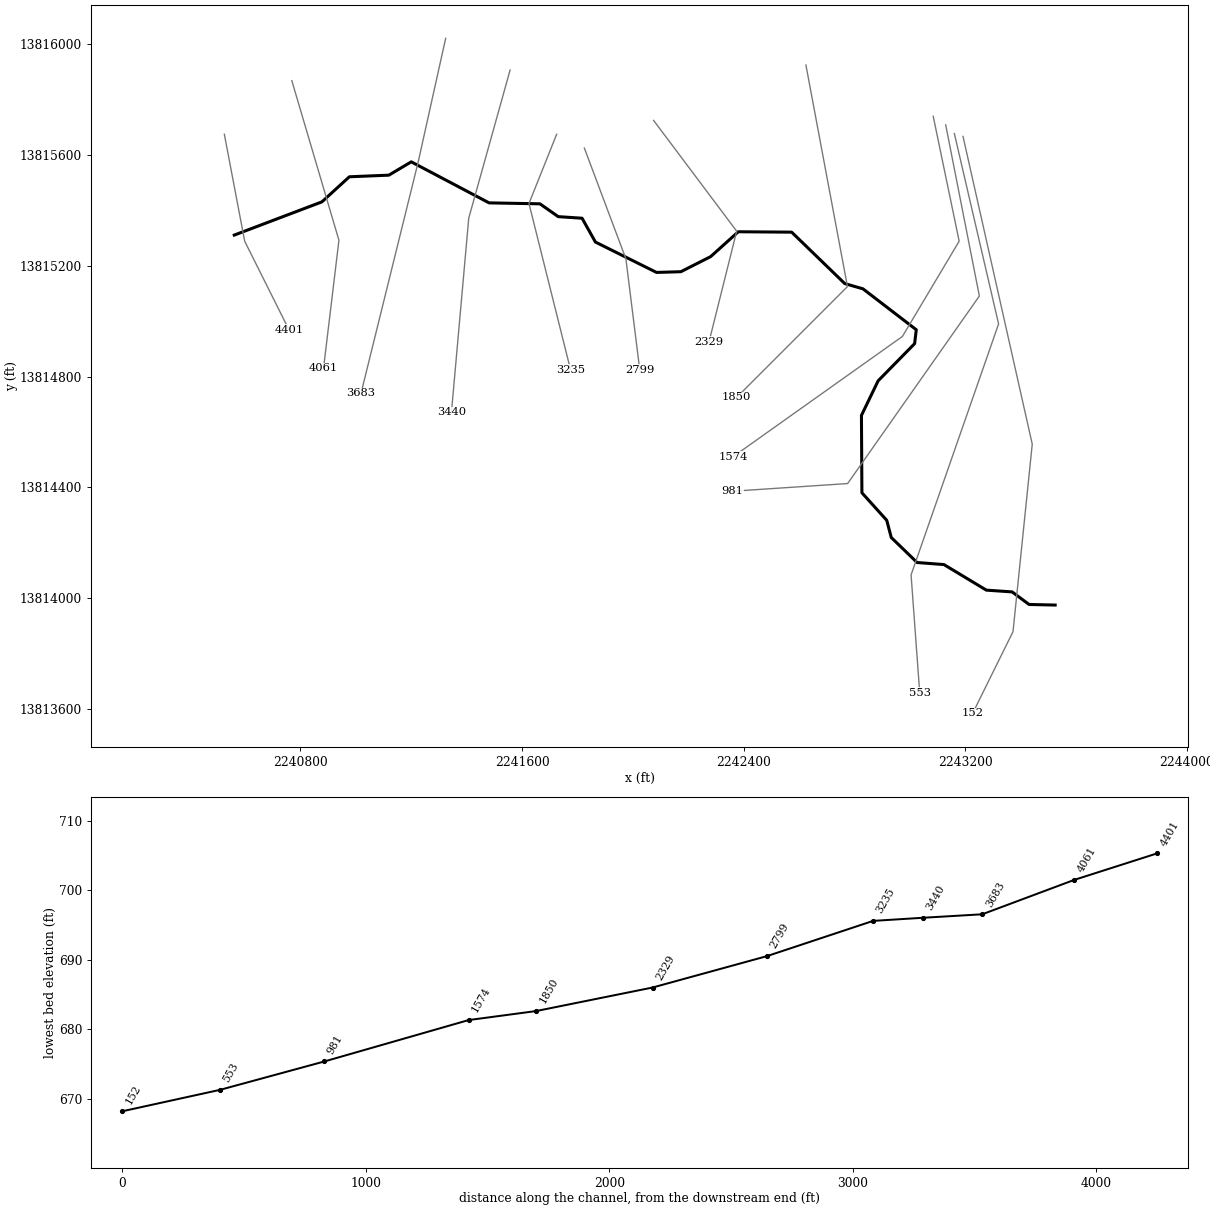
--- Blieders Creek Tributary 1.prj (project) ---

Proj Title=Blieders Creek Tributary 1 Base Level Engineering
Current Plan=p01
Default Exp/Contr=0.3,0.1
English Units
Geom File=g01
Flow File=f01
Plan File=p01
BEGIN DESCRIPTION:
Blieders Creek Tributary 1
END DESCRIPTION:

--- Blieders Creek Tributary 1.p01 (plan) ---

Plan Title=Multiple Run
Short Identifier=Multiple
Geom File=g01
Flow File=f01
Subcritical Flow
K Sum by GR= 0
Std Step Tol= 0.01
Critical Tol= 0.01
Num of Std Step Trials= 20
Max Error Tol= 0.3
Flow Tol Ratio= 0.001
Split Flow NTrial= 30
Split Flow Tol= 0.02
Split Flow Ratio= 0.02
Log Output Level= 0
Friction Slope Method= 1
Unsteady Friction Slope Method= 2
Unsteady Bridges Friction Slope Method= 1
Parabolic Critical Depth
Global Vel Dist=  1 , 1 , 1
Global Log Level= 0
CheckData=True
Encroach Param= -1, 0, 0, 0
BEGIN DESCRIPTION:
Multiple Run
END DESCRIPTION:

--- Blieders Creek Tributary 1.f01 (steady flow) ---

Flow Title=Multiple
Number of Profiles=7
Profile Names=10-year,25-year,50-year,1pct_min,100-year,1pct_plu,500-year
River Rch & RM= Blieders Creek T,Reach-1,4401
    1095    1840    2541    1698    3389    6761    5965
Boundary for River Rch & Prof#=Blieders Creek T,Reach-1,1
Up Type=0
Dn Type=3
Dn Slope=0.005
Boundary for River Rch & Prof#=Blieders Creek T,Reach-1,2
Up Type=0
Dn Type=3
Dn Slope=0.005
Boundary for River Rch & Prof#=Blieders Creek T,Reach-1,3
Up Type=0
Dn Type=3
Dn Slope=0.005
Boundary for River Rch & Prof#=Blieders Creek T,Reach-1,4
Up Type=0
Dn Type=3
Dn Slope=0.005
Boundary for River Rch & Prof#=Blieders Creek T,Reach-1,5
Up Type=0
Dn Type=3
Dn Slope=0.005
Boundary for River Rch & Prof#=Blieders Creek T,Reach-1,6
Up Type=0
Dn Type=3
Dn Slope=0.005
Boundary for River Rch & Prof#=Blieders Creek T,Reach-1,7
Up Type=0
Dn Type=3
Dn Slope=0.005

--- Blieders Creek Tributary 1.g01 (geometry) ---

Geom Title=Existing Conditions

River Reach=Blieders Creek T,Reach-1
Reach XY= 30
      2240560.90     13815310.90      2240877.29     13815430.85
      2240976.47     13815521.45      2241119.07     13815527.30
      2241200.00     13815575.41      2241480.93     13815427.24
      2241664.50     13815423.78      2241730.66     13815377.51
      2241816.65     13815371.81      2241865.02     13815285.69
      2242085.54     13815176.08      2242173.42     13815178.67
      2242281.05     13815233.16      2242380.86     13815322.94
      2242573.54     13815321.47      2242765.32     13815135.78
      2242831.04     13815116.82      2243023.50     13814969.13
      2243017.55     13814918.97      2242885.76     13814784.68
      2242825.51     13814659.79      2242827.18     13814380.45
      2242916.82     13814281.04      2242933.15     13814218.93
      2243026.48     13814128.61      2243123.41     13814121.17
      2243276.58     13814028.83      2243369.44     13814022.55
      2243430.87     13813977.10      2243525.00     13813975.00

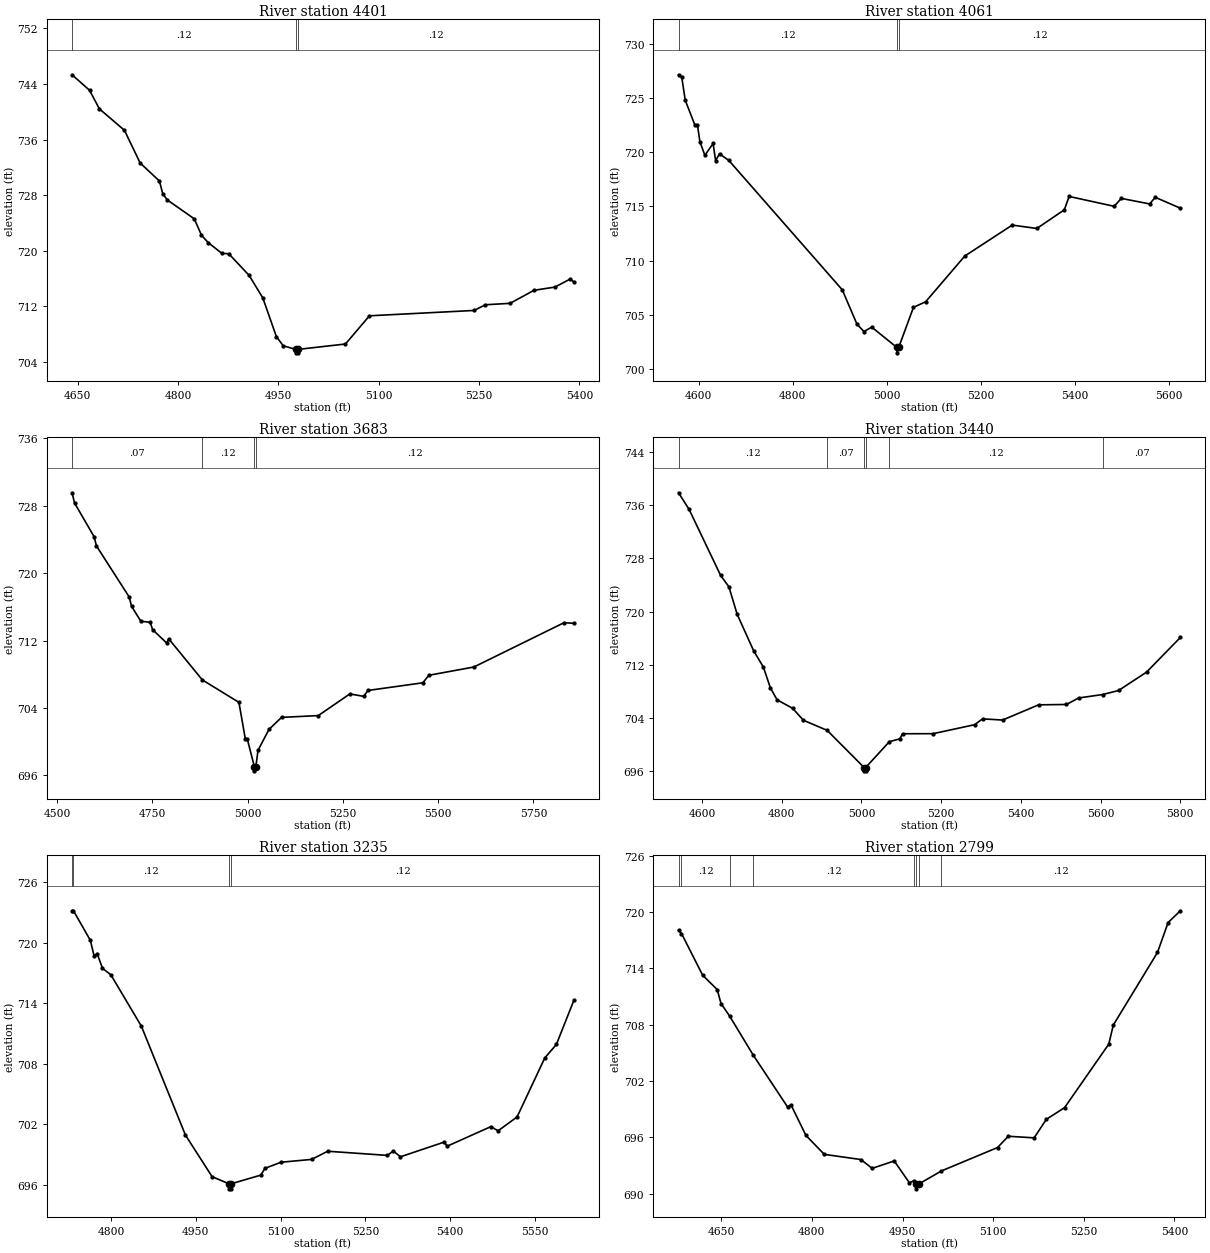
Type RM Length L Ch R = 1,4401,340,340,340
BEGIN DESCRIPTION:
Blieders Creek Tributary 1 7.0
END DESCRIPTION:
XS GIS Cut Line= 3
      2240524.99     13815675.03      2240598.50     13815288.74
      2240758.06     13814969.63
#Sta/Elev= 30
  4641.8  745.32  4667.9  743.09  4682.6  740.42  4720.1  737.33  4743.6  732.62
  4772.3  730.04  4777.4  728.19  4784.3  727.30  4824.5  724.59  4835.2  722.24
  4845.4  721.16  4865.8  719.62  4876.0  719.57  4906.5  716.45  4926.9  713.21
  4947.2  707.64  4957.4  706.33  4975.8  705.81  4976.0  705.31  4979.5  705.31
  4979.8  705.81  5050.4  706.58  5086.3  710.64  5242.8  711.41  5259.6  712.23
  5296.4  712.43  5332.3  714.31  5363.4  714.77  5385.8  715.90  5391.8  715.55
#Mann=3,-1,0
  4641.8    0.12       0  4975.8    0.05       0  4979.8    0.12       0
Bank Sta=4975.8,4979.8
Exp/Cntr=0.3,0.1

Type RM Length L Ch R = 1,4061,378,378,378
BEGIN DESCRIPTION:
X18287
END DESCRIPTION:
XS GIS Cut Line= 3
      2240768.65     13815868.57      2240938.78     13815292.21
      2240883.22     13814830.39
#Sta/Elev= 30
  4557.2  727.12  4564.0  726.92  4571.4  724.78  4592.1  722.47  4597.4  722.48
  4602.6  720.96  4613.1  719.70  4630.7  720.79  4635.9  719.21  4644.3  719.84
  4664.0  719.23  4905.0  707.31  4936.3  704.14  4951.2  703.46  4967.6  703.87
  5021.0  702.00  5021.3  701.50  5025.0  702.00  5056.3  705.69  5082.3  706.21
  5165.4  710.42  5266.1  713.27  5318.5  712.96  5376.9  714.68  5387.0  715.91
  5482.8  715.00  5497.8  715.73  5558.2  715.22  5570.0  715.83  5623.3  714.83
#Mann=3,-1,0
  4557.2    0.12       0  5021.0    0.05       0  5025.0    0.12       0
Bank Sta=5021,5025
Exp/Cntr=0.3,0.1

Type RM Length L Ch R = 1,3683,243,243,243
BEGIN DESCRIPTION:
Blieders Creek Tributary 1 6.0
END DESCRIPTION:
XS GIS Cut Line= 3
      2241324.19     13816021.35      2241225.00     13815575.00
      2241018.65     13814740.16
#Sta/Elev= 30
  4538.9  729.52  4545.4  728.31  4596.6  724.32  4603.0  723.21  4688.8  717.17
  4695.2  716.05  4719.6  714.28  4743.9  714.17  4750.3  713.29  4787.4  711.70
  4792.5  712.21  4880.9  707.33  4976.9  704.67  4993.6  700.35  4998.7  700.35
  5017.4  697.05  5017.7  696.55  5021.4  697.05  5027.0  698.98  5055.7  701.46
  5088.8  702.89  5185.2  703.10  5268.1  705.67  5304.4  705.38  5315.5  706.08
  5459.7  706.99  5475.3  707.88  5593.6  708.86  5830.5  714.12  5856.1  714.04
#Mann=4,-1,0
  4538.9    0.07       0  4880.9    0.12       0  5017.4    0.05       0
  5021.4    0.12       0
Bank Sta=5017.4,5021.4
Exp/Cntr=0.3,0.1

Type RM Length L Ch R = 1,3440,205,205,205
BEGIN DESCRIPTION:
X18286
END DESCRIPTION:
XS GIS Cut Line= 3
      2241556.84     13815906.79      2241407.53     13815372.07
      2241345.04     13814670.72
#Sta/Elev= 30
  4541.0  737.88  4567.6  735.37  4646.7  725.44  4667.4  723.74  4688.2  719.59
  4729.7  714.09  4754.0  711.65  4771.3  708.57  4788.2  706.74  4827.5  705.45
  4854.3  703.66  4914.0  702.14  5006.7  696.55  5007.0  696.05  5010.5  696.05
  5010.7  696.55  5070.1  700.44  5096.2  700.86  5103.3  701.63  5179.8  701.64
  5284.0  702.99  5304.1  703.87  5354.3  703.69  5444.6  705.98  5514.4  706.03
  5545.0  707.01  5605.6  707.53  5645.4  708.14  5715.7  710.91  5800.3  716.11
#Mann=6,-1,0
  4541.0    0.12       0  4914.0    0.07       0  5006.7    0.05       0
  5010.7    0.07       0  5070.1    0.12       0  5605.6    0.07       0
Bank Sta=5006.7,5010.7
Exp/Cntr=0.3,0.1

Type RM Length L Ch R = 1,3235,436,436,436
BEGIN DESCRIPTION:
Blieders Creek Tributary 1 5.0
END DESCRIPTION:
XS GIS Cut Line= 3
      2241724.99     13815674.98      2241625.00     13815425.00
      2241775.00     13814825.00
#Sta/Elev= 30
  4731.2  723.19  4733.7  723.19  4763.5  720.26  4770.2  718.70  4775.6  718.95
  4785.0  717.48  4799.8  716.84  4853.7  711.75  4931.8  700.93  4978.9  696.81
  5008.7  696.10  5009.0  695.60  5012.5  695.60  5012.7  696.10  5064.9  696.96
  5072.6  697.64  5100.9  698.24  5155.0  698.52  5183.4  699.33  5289.0  698.92
  5299.4  699.35  5312.2  698.78  5389.5  700.24  5394.7  699.83  5472.0  701.77
  5484.9  701.36  5518.4  702.73  5567.4  708.58  5588.0  709.93  5618.9  714.30
#Mann=4,-1,0
  4731.2    0.07       0  4733.7    0.12       0  5008.7    0.05       0
  5012.7    0.12       0
Bank Sta=5008.7,5012.7
Exp/Cntr=0.3,0.1

Type RM Length L Ch R = 1,2799,470,470,470
BEGIN DESCRIPTION:
Blieders Creek Tributary 1 4.0
END DESCRIPTION:
XS GIS Cut Line= 3
      2241825.01     13815624.96      2241975.00     13815225.00
      2242025.00     13814824.97
#Sta/Elev= 30
  4579.4  718.04  4584.3  717.72  4619.4  713.27  4643.4  711.75  4649.7  710.26
  4663.9  708.93  4703.1  704.76  4760.0  699.23  4765.4  699.48  4790.3  696.21
  4820.6  694.20  4881.1  693.65  4899.8  692.71  4936.3  693.50  4961.2  691.19
  4968.7  691.37  4972.5  691.03  4972.7  690.53  4976.6  691.03  5014.5  692.44
  5107.3  694.93  5125.0  696.13  5167.8  695.96  5188.0  697.93  5218.2  699.18
  5291.3  705.94  5298.8  707.97  5371.9  715.70  5389.5  718.89  5409.7  720.14
#Mann=8,-1,0
  4579.4    0.07       0  4584.3    0.12       0  4663.9    0.07       0
  4703.1    0.12       0  4968.7    0.07       0  4972.5    0.05       0
  4976.6    0.07       0  5014.5    0.12       0
Bank Sta=4972.5,4976.6
Exp/Cntr=0.3,0.1

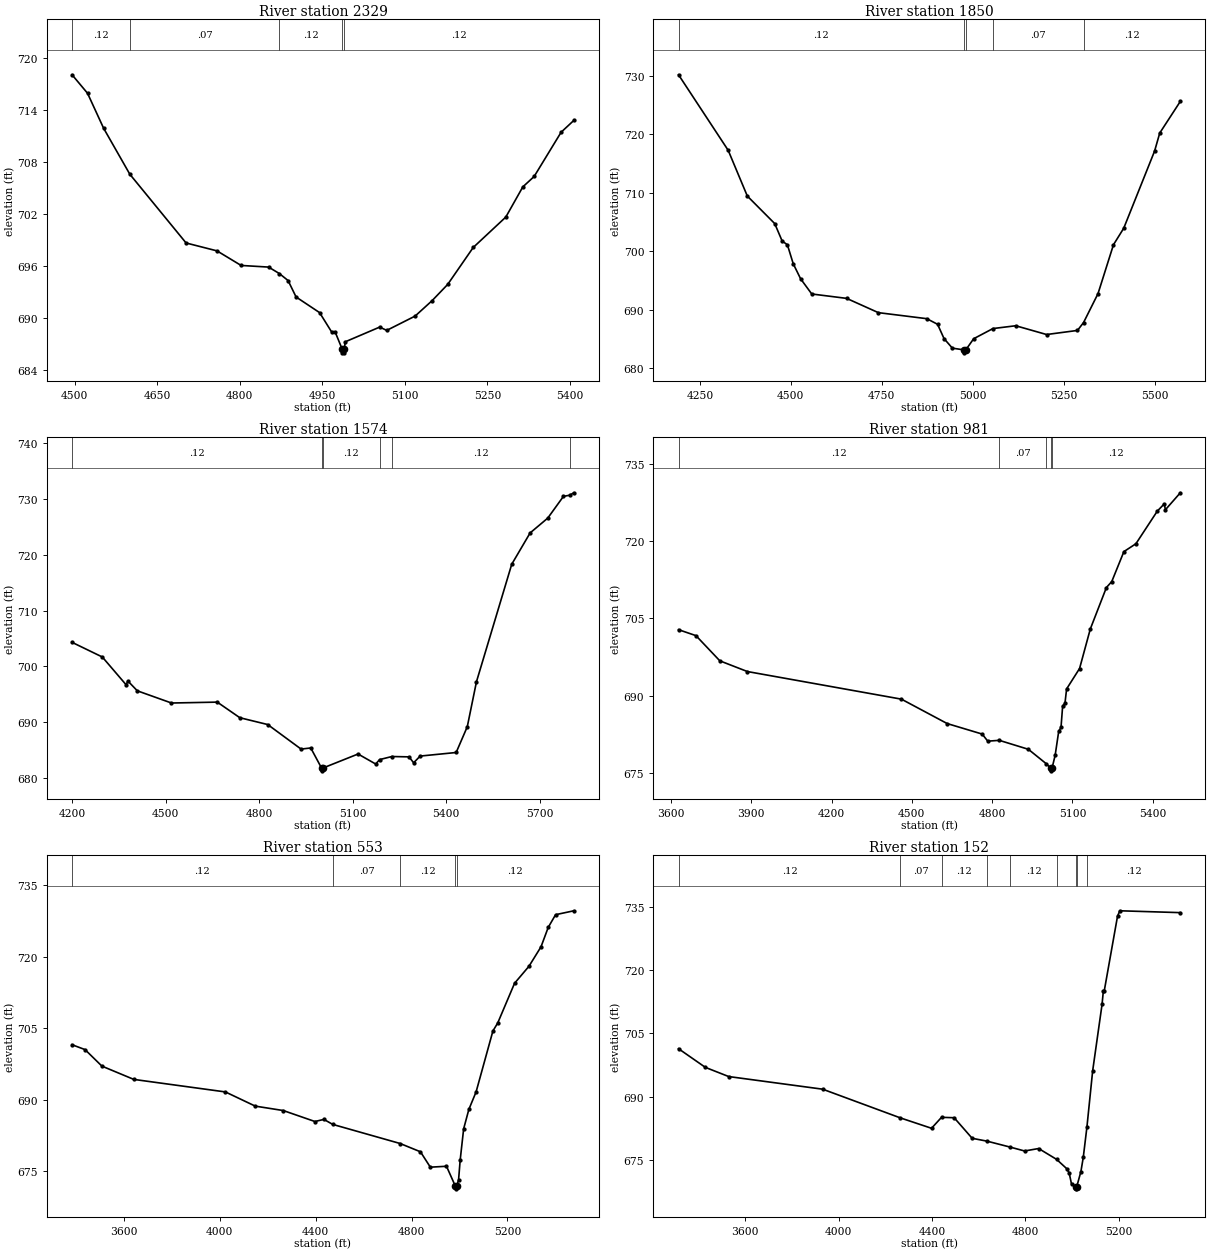
Type RM Length L Ch R = 1,2329,479,479,479
BEGIN DESCRIPTION:
Blieders Creek Tributary 1 3.0
END DESCRIPTION:
XS GIS Cut Line= 3
      2242075.01     13815724.99      2242375.00     13815325.00
      2242275.00     13814924.99
#Sta/Elev= 30
  4495.0  718.08  4523.1  715.95  4552.3  711.92  4600.0  706.61  4702.3  698.68
  4758.5  697.77  4802.3  696.09  4852.3  695.90  4871.7  695.16  4887.7  694.35
  4902.3  692.45  4945.0  690.65  4966.9  688.42  4973.1  688.45  4985.6  686.51
  4985.9  686.01  4989.5  686.01  4989.8  686.51  4991.9  687.29  5054.3  688.98
  5067.1  688.60  5118.7  690.25  5149.6  692.03  5177.9  693.90  5224.3  698.16
  5283.6  701.67  5314.5  705.15  5335.1  706.35  5384.1  711.45  5407.3  712.82
#Mann=5,-1,0
  4495.0    0.12       0  4600.0    0.07       0  4871.7    0.12       0
  4985.6    0.05       0  4989.8    0.12       0
Bank Sta=4985.6,4989.8
Exp/Cntr=0.3,0.1

Type RM Length L Ch R = 1,1850,276,276,276
BEGIN DESCRIPTION:
Blieders Creek Tributary 1 2.0
END DESCRIPTION:
XS GIS Cut Line= 3
      2242625.00     13815924.98      2242775.00     13815125.00
      2242375.00     13814725.00
#Sta/Elev= 30
  4191.4  730.15  4327.9  717.24  4380.5  709.42  4455.9  704.71  4476.3  701.73
  4490.7  701.09  4506.8  697.84  4527.1  695.27  4557.7  692.68  4653.5  691.93
  4740.8  689.49  4873.9  688.46  4903.6  687.50  4921.4  685.05  4944.3  683.42
  4976.9  683.12  4977.2  682.62  4981.1  683.12  5002.8  685.03  5055.8  686.77
  5118.5  687.25  5203.3  685.75  5288.2  686.45  5304.9  687.79  5344.7  692.74
  5387.2  701.10  5415.4  703.92  5500.3  717.12  5514.4  720.19  5571.0  725.60
#Mann=5,-1,0
  4191.4    0.12       0  4976.9    0.05       0  4981.1    0.12       0
  5055.8    0.07       0  5304.9    0.12       0
Bank Sta=4976.9,4981.1
Exp/Cntr=0.3,0.1

Type RM Length L Ch R = 1,1574,593,593,593
BEGIN DESCRIPTION:
X18285
END DESCRIPTION:
XS GIS Cut Line= 4
      2243084.63     13815740.08      2243178.37     13815288.74
      2242973.50     13814944.99      2242362.39     13814510.96
#Sta/Elev= 30
  4199.2  704.31  4296.3  701.69  4373.0  696.70  4378.1  697.41  4408.7  695.64
  4518.3  693.46  4665.3  693.62  4737.7  690.83  4827.2  689.61  4934.3  685.22
  4965.4  685.42  5000.0  681.83  5000.3  681.33  5004.3  681.83  5117.2  684.34
  5173.8  682.55  5186.3  683.34  5225.7  683.89  5280.8  683.83  5295.6  682.77
  5316.5  683.97  5432.1  684.61  5467.8  689.22  5497.3  697.27  5610.5  718.28
  5669.5  723.88  5726.1  726.53  5776.5  730.42  5796.1  730.62  5809.9  731.06
#Mann=6,-1,0
  4199.2    0.12       0  5000.0    0.05       0  5004.3    0.12       0
  5186.3    0.07       0  5225.7    0.12       0  5796.1    0.07       0
Bank Sta=5000,5004.3
Exp/Cntr=0.3,0.1

Type RM Length L Ch R = 1,981,428,428,428
BEGIN DESCRIPTION:
X18284
END DESCRIPTION:
XS GIS Cut Line= 4
      2243129.75     13815708.91      2243251.28     13815090.82
      2242775.59     13814413.74      2242359.42     13814386.00
#Sta/Elev= 30
  3628.4  702.82  3693.5  701.66  3782.7  696.76  3885.5  694.68  4461.0  689.31
  4632.1  684.56  4762.7  682.52  4783.6  681.14  4826.6  681.30  4935.2  679.56
  5001.2  676.79  5019.3  675.87  5019.6  675.37  5023.6  675.87  5035.4  678.42
  5048.5  683.03  5057.2  683.83  5063.3  687.97  5072.0  688.53  5078.1  691.30
  5126.5  695.27  5166.6  702.95  5226.7  711.01  5246.8  712.18  5292.1  718.00
  5337.0  719.53  5417.1  725.89  5442.4  727.25  5447.5  726.16  5502.9  729.44
#Mann=5,-1,0
  3628.4    0.12       0  4826.6    0.07       0  5001.2    0.12       0
  5019.3    0.05       0  5023.6    0.12       0
Bank Sta=5019.3,5023.6
Exp/Cntr=0.3,0.1

Type RM Length L Ch R = 1,553,401,401,401
BEGIN DESCRIPTION:
X18283
END DESCRIPTION:
XS GIS Cut Line= 4
      2243161.01     13815677.59      2243320.73     13814990.13
      2243004.75     13814083.88      2243035.88     13813658.45
#Sta/Elev= 30
  3384.7  701.55  3438.7  700.53  3509.1  697.06  3642.1  694.27  4023.9  691.64
  4148.5  688.66  4265.4  687.73  4397.1  685.43  4434.8  685.87  4471.5  684.82
  4752.5  680.81  4837.2  679.07  4878.4  675.84  4945.8  676.03  4983.3  671.79
  4983.6  671.29  4987.7  671.79  4996.1  673.15  5002.7  677.27  5017.3  683.89
  5039.0  687.97  5069.2  691.65  5139.3  704.44  5159.4  706.12  5229.6  714.46
  5289.7  718.03  5339.9  722.12  5370.0  726.20  5400.6  728.86  5476.8  729.68
#Mann=5,-1,0
  3384.7    0.12       0  4471.5    0.07       0  4752.5    0.12       0
  4983.3    0.05       0  4987.7    0.12       0
Bank Sta=4983.3,4987.7
Exp/Cntr=0.3,0.1

Type RM Length L Ch R = 1,152,0,0,0
BEGIN DESCRIPTION:
Blieders Creek Tributary 1 1.0
END DESCRIPTION:
XS GIS Cut Line= 4
      2243192.26     13815667.17      2243442.25     13814556.10
      2243372.81     13813879.02      2243226.97     13813583.87
#Sta/Elev= 30
  3314.8  701.37  3429.8  696.95  3529.7  694.78  3932.0  691.79  4264.6  685.00
  4398.1  682.54  4440.9  685.13  4495.0  685.04  4572.1  680.17  4636.1  679.49
  4735.3  678.08  4796.5  677.17  4856.9  677.75  4933.8  675.18  4977.5  672.96
  4987.5  671.98  4997.6  669.33  5015.4  668.71  5015.8  668.21  5019.9  668.71
  5037.8  672.31  5047.9  675.65  5063.6  682.86  5088.1  696.13  5128.3  711.84
  5133.8  714.98  5137.5  714.98  5194.5  732.70  5204.2  734.01  5463.5  733.57
#Mann=9,-1,0
  3314.8    0.12       0  4264.6    0.07       0  4440.9    0.12       0
  4636.1    0.07       0  4735.3    0.12       0  4933.8     0.1       0
  5015.4    0.05       0  5019.9     0.1       0  5063.6    0.12       0
Bank Sta=5015.4,5019.9
Exp/Cntr=0.3,0.1

Chan Stop Cuts=-1