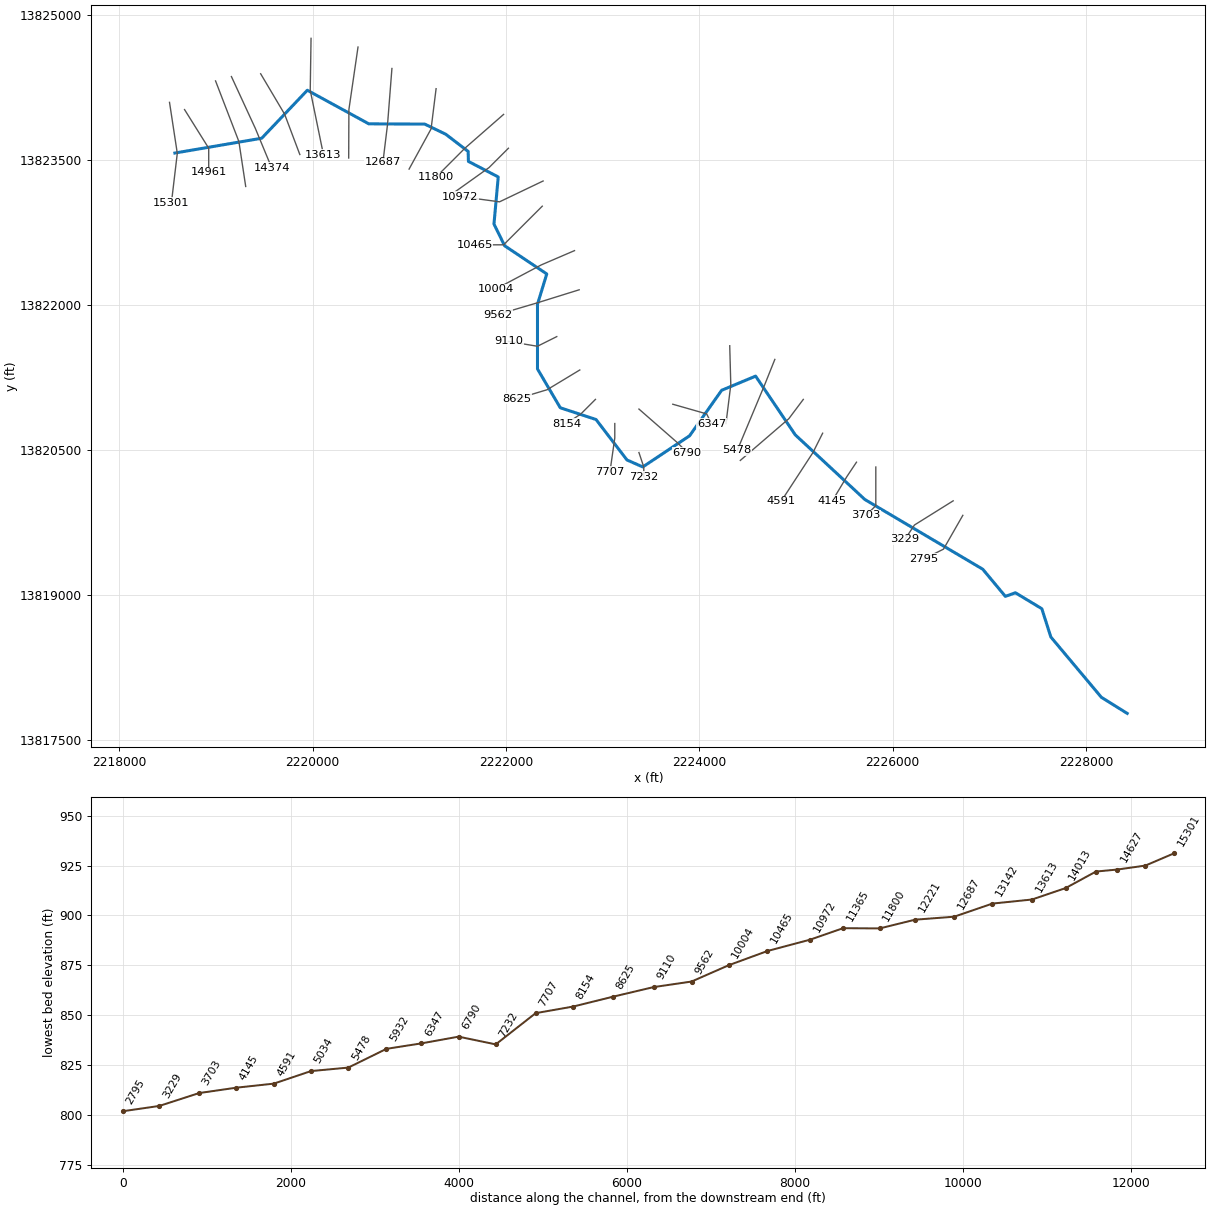
--- Blieders Creek Tributary 11.prj (project) ---

Proj Title=Blieders Creek Tributary 11 Base Level Engineering
Current Plan=p01
Default Exp/Contr=0.3,0.1
English Units
Geom File=g01
Flow File=f01
Plan File=p01
BEGIN DESCRIPTION:
Blieders Creek Tributary 11
END DESCRIPTION:

--- Blieders Creek Tributary 11.p01 (plan) ---

Plan Title=Multiple Run
Short Identifier=Multiple
Geom File=g01
Flow File=f01
Subcritical Flow
K Sum by GR= 0
Std Step Tol= 0.01
Critical Tol= 0.01
Num of Std Step Trials= 20
Max Error Tol= 0.3
Flow Tol Ratio= 0.001
Split Flow NTrial= 30
Split Flow Tol= 0.02
Split Flow Ratio= 0.02
Log Output Level= 0
Friction Slope Method= 1
Unsteady Friction Slope Method= 2
Unsteady Bridges Friction Slope Method= 1
Parabolic Critical Depth
Global Vel Dist=  1 , 1 , 1
Global Log Level= 0
CheckData=True
Encroach Param= -1, 0, 0, 0
BEGIN DESCRIPTION:
Multiple Run
END DESCRIPTION:

--- Blieders Creek Tributary 11.f01 (steady flow) ---

Flow Title=Multiple
Number of Profiles=7
Profile Names=10-year,25-year,50-year,1pct_min,100-year,1pct_plu,500-year
River Rch & RM= Blieders Creek T,Reach-1,15301
    1317    2245    3132    2115    4220    8420    7580
River Rch & RM= Blieders Creek T,Reach-1,13613
    1704    2932    4113    2789    5565   11105   10090
River Rch & RM= Blieders Creek T,Reach-1,8625
    2002    3459    4866    3306    6596   13161   12005
Boundary for River Rch & Prof#=Blieders Creek T,Reach-1,1
Up Type=0
Dn Type=3
Dn Slope=0.005
Boundary for River Rch & Prof#=Blieders Creek T,Reach-1,2
Up Type=0
Dn Type=3
Dn Slope=0.005
Boundary for River Rch & Prof#=Blieders Creek T,Reach-1,3
Up Type=0
Dn Type=3
Dn Slope=0.005
Boundary for River Rch & Prof#=Blieders Creek T,Reach-1,4
Up Type=0
Dn Type=3
Dn Slope=0.005
Boundary for River Rch & Prof#=Blieders Creek T,Reach-1,5
Up Type=0
Dn Type=3
Dn Slope=0.005
Boundary for River Rch & Prof#=Blieders Creek T,Reach-1,6
Up Type=0
Dn Type=3
Dn Slope=0.005
Boundary for River Rch & Prof#=Blieders Creek T,Reach-1,7
Up Type=0
Dn Type=3
Dn Slope=0.005

--- Blieders Creek Tributary 11.g01 (geometry) ---

Geom Title=Existing Conditions

River Reach=Blieders Creek T,Reach-1
Reach XY= 30
      2218575.00     13823575.00      2219473.50     13823728.46
      2219944.99     13824225.06      2220580.93     13823877.24
      2221159.79     13823874.49      2221377.29     13823769.15
      2221608.62     13823591.70      2221611.00     13823488.61
      2221919.54     13823327.45      2221875.50     13822840.21
      2221985.76     13822615.30      2222421.48     13822323.54
      2222325.51     13822009.79      2222325.52     13821340.22
      2222561.35     13820938.26      2222931.06     13820816.86
      2223251.15     13820398.06      2223414.52     13820325.93
      2223898.52     13820647.99      2224230.62     13821119.38
      2224581.73     13821265.85      2224991.64     13820658.32
      2225711.79     13819988.63      2226931.17     13819267.14
      2227164.92     13818986.11      2227268.95     13819023.34
      2227541.79     13818858.56      2227635.48     13818565.20
      2228157.92     13817941.42      2228425.00     13817775.00

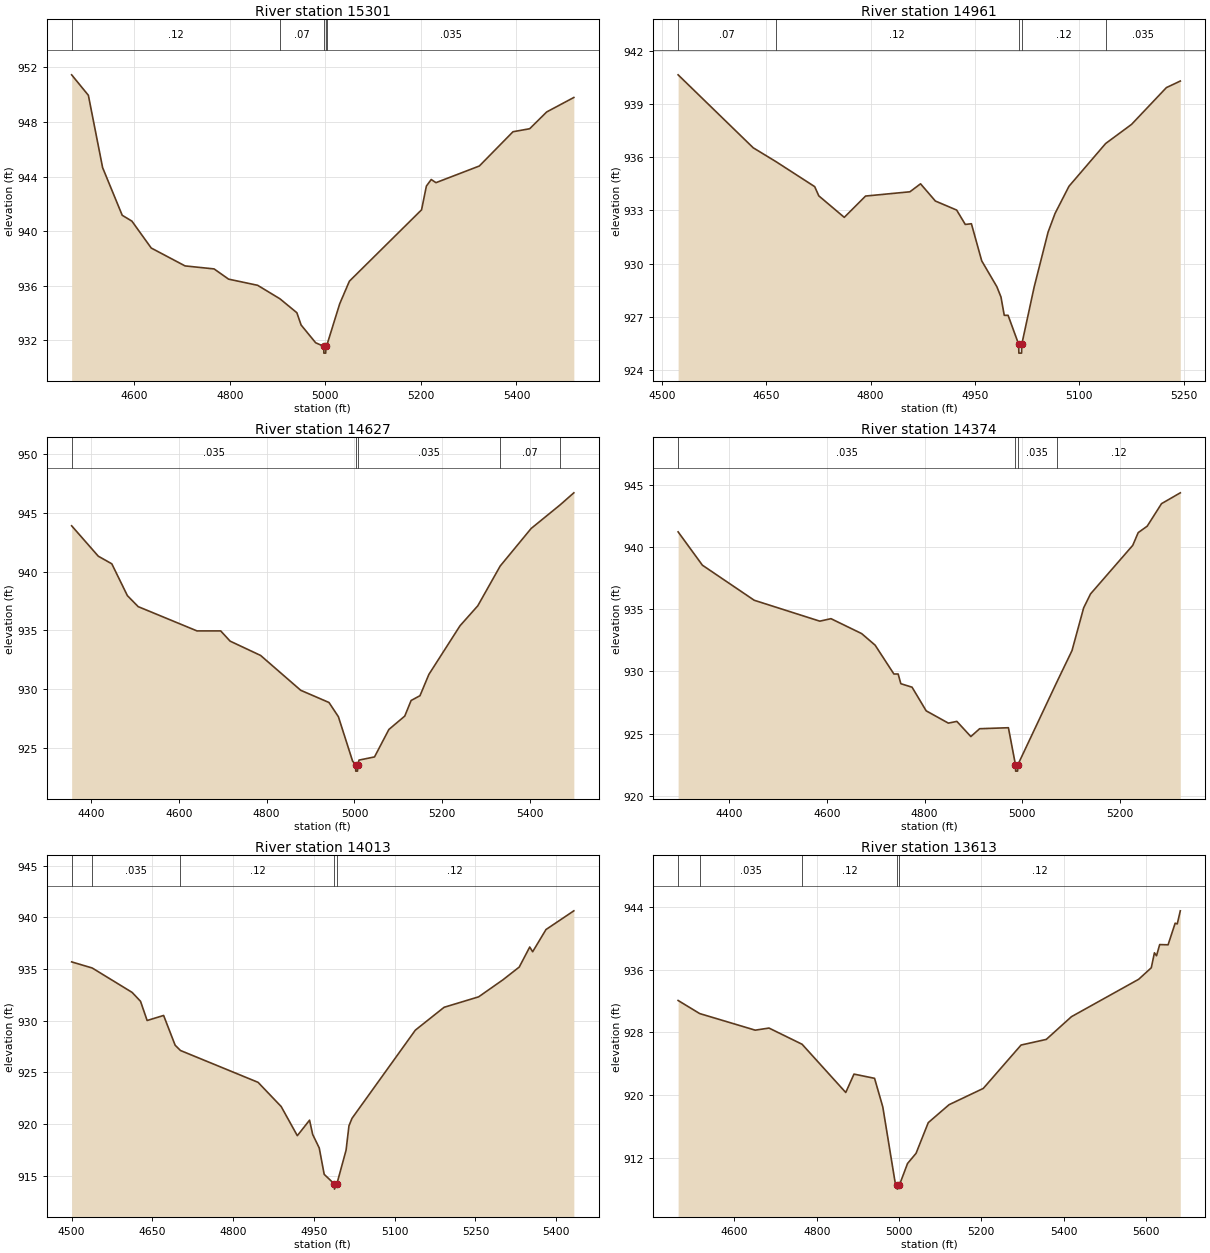
Type RM Length L Ch R = 1,15301,340,340,340
BEGIN DESCRIPTION:
X18291
END DESCRIPTION:
XS GIS Cut Line= 3
      2218519.57     13824099.63      2218600.01     13823571.96
      2218539.05     13823058.64
#Sta/Elev= 30
  4469.3  951.46  4504.3  949.96  4534.1  944.66  4575.1  941.17  4595.4  940.74
  4635.8  938.77  4706.6  937.46  4767.3  937.24  4797.7  936.49  4858.4  936.04
  4905.1  935.05  4940.5  934.03  4949.4  933.13  4979.8  931.83  4996.7  931.57
  4997.0  931.07  5000.9  931.07  5001.2  931.57  5004.2  931.76  5030.2  934.69
  5050.4  936.34  5201.4  941.57  5211.5  943.31  5221.6  943.79  5231.6  943.56
  5322.3  944.78  5392.7  947.29  5427.6  947.51  5463.2  948.74  5520.0  949.80
#Mann=5,-1,0
  4469.3    0.12       0  4905.1    0.07       0  4996.7    0.05       0
  5001.2    0.07       0  5004.2   0.035       0
Bank Sta=4996.7,5001.2
Exp/Cntr=0.3,0.1

Type RM Length L Ch R = 1,14961,334,334,334
BEGIN DESCRIPTION:
Blieders Creek Tributary 11 31.0
END DESCRIPTION:
XS GIS Cut Line= 3
      2218675.02     13824024.96      2218925.00     13823625.00
      2218925.00     13823374.96
#Sta/Elev= 30
  4523.3  940.64  4631.2  936.53  4663.9  935.75  4719.6  934.34  4725.5  933.82
  4762.1  932.61  4792.7  933.81  4856.4  934.05  4871.7  934.50  4893.0  933.53
  4923.6  933.02  4936.0  932.21  4944.8  932.25  4959.6  930.16  4981.4  928.70
  4987.3  928.12  4992.0  927.09  4997.5  927.09  5012.7  925.46  5013.0  924.96
  5016.9  924.96  5017.2  925.46  5035.0  928.69  5055.0  931.78  5065.0  932.83
  5085.0  934.36  5137.7  936.77  5175.0  937.85  5225.0  939.92  5245.0  940.29
#Mann=5,-1,0
  4523.3    0.07       0  4663.9    0.12       0  5012.7    0.05       0
  5017.2    0.12       0  5137.7   0.035       0
Bank Sta=5012.7,5017.2
Exp/Cntr=0.3,0.1

Type RM Length L Ch R = 1,14627,253,253,253
BEGIN DESCRIPTION:
X18290
END DESCRIPTION:
XS GIS Cut Line= 3
      2218995.75     13824321.56      2219237.03     13823694.21
      2219307.63     13823228.88
#Sta/Elev= 30
  4356.4  943.90  4417.0  941.31  4447.8  940.66  4483.2  937.95  4507.8  937.01
  4641.7  934.94  4695.6  934.94  4717.0  934.07  4786.4  932.85  4877.7  929.88
  4942.0  928.84  4963.4  927.63  4995.6  923.86  5002.6  923.49  5002.9  922.99
  5006.9  922.99  5007.3  923.49  5010.3  923.93  5045.6  924.20  5078.3  926.54
  5114.4  927.68  5128.9  929.01  5149.1  929.42  5169.3  931.23  5240.2  935.38
  5280.6  937.08  5331.6  940.47  5402.0  943.67  5467.6  945.67  5499.2  946.71
#Mann=5,-1,0
  4356.4   0.035       0  5002.6   0.035       0  5007.3   0.035       0
  5331.6    0.07       0  5467.6   0.035       0
Bank Sta=5002.6,5007.3
Exp/Cntr=0.3,0.1

Type RM Length L Ch R = 1,14374,361,361,361
BEGIN DESCRIPTION:
Blieders Creek Tributary 11 30.0
END DESCRIPTION:
XS GIS Cut Line= 3
      2219159.80     13824366.67      2219407.55     13823829.34
      2219574.99     13823425.04
#Sta/Elev= 30
  4294.9  941.22  4344.7  938.54  4450.9  935.72  4585.3  934.04  4608.2  934.24
  4671.1  933.04  4698.7  932.11  4737.2  929.79  4745.9  929.79  4751.4  929.01
  4774.4  928.73  4803.3  926.83  4848.8  925.84  4866.2  925.98  4894.9  924.76
  4912.9  925.39  4971.9  925.47  4986.4  922.48  4986.7  921.98  4990.7  921.98
  4991.1  922.48  5071.6  929.18  5102.2  931.67  5126.1  935.11  5140.2  936.23
  5226.8  940.14  5237.9  941.16  5256.4  941.68  5285.7  943.49  5324.2  944.36
#Mann=4,-1,0
  4294.9   0.035       0  4986.4   0.035       0  4991.1   0.035       0
  5071.6    0.12       0
Bank Sta=4986.4,4991.1
Exp/Cntr=0.3,0.1

Type RM Length L Ch R = 1,14013,400,400,400
BEGIN DESCRIPTION:
Blieders Creek Tributary 11 29.0
END DESCRIPTION:
XS GIS Cut Line= 3
      2219462.22     13824395.63      2219709.97     13823977.34
      2219867.43     13823559.58
#Sta/Elev= 30
  4500.2  935.69  4538.4  935.10  4612.5  932.74  4628.1  931.88  4640.4  930.02
  4671.0  930.51  4692.4  927.63  4702.3  927.12  4846.4  924.04  4889.3  921.70
  4919.3  918.88  4942.0  920.38  4947.8  919.00  4960.0  917.69  4969.2  915.14
  4988.0  914.21  4988.3  913.71  4992.7  914.21  5009.8  917.47  5015.2  919.84
  5020.9  920.56  5138.5  929.09  5191.9  931.30  5256.0  932.31  5301.2  933.96
  5331.4  935.19  5350.9  937.13  5356.3  936.67  5381.1  938.82  5432.8  940.63
#Mann=5,-1,0
  4500.2    0.07       0  4538.4   0.035       0  4702.3    0.12       0
  4988.0    0.05       0  4992.7    0.12       0
Bank Sta=4988,4992.7
Exp/Cntr=0.3,0.1

Type RM Length L Ch R = 1,13613,471,471,471
BEGIN DESCRIPTION:
Blieders Creek Tributary 11 28.0
END DESCRIPTION:
XS GIS Cut Line= 3
      2219983.44     13824762.34      2219975.00     13824225.00
      2220112.13     13823555.92
#Sta/Elev= 30
  4463.1  932.07  4515.5  930.40  4650.5  928.28  4683.9  928.55  4764.4  926.48
  4870.5  920.32  4890.5  922.67  4940.5  922.13  4960.5  918.48  4990.5  908.83
  4995.4  908.48  4995.8  907.98  5000.7  908.48  5020.6  911.25  5041.3  912.55
  5071.0  916.47  5121.5  918.76  5204.7  920.84  5296.5  926.38  5357.8  927.10
  5418.9  930.00  5582.4  934.78  5613.0  936.25  5620.6  938.16  5625.7  937.78
  5633.4  939.21  5653.8  939.18  5671.0  941.94  5676.1  941.85  5683.5  943.52
#Mann=5,-1,0
  4463.1    0.12       0  4515.5   0.035       0  4764.4    0.12       0
  4995.4    0.05       0  5000.7    0.12       0
Bank Sta=4995.4,5000.7
Exp/Cntr=0.3,0.1

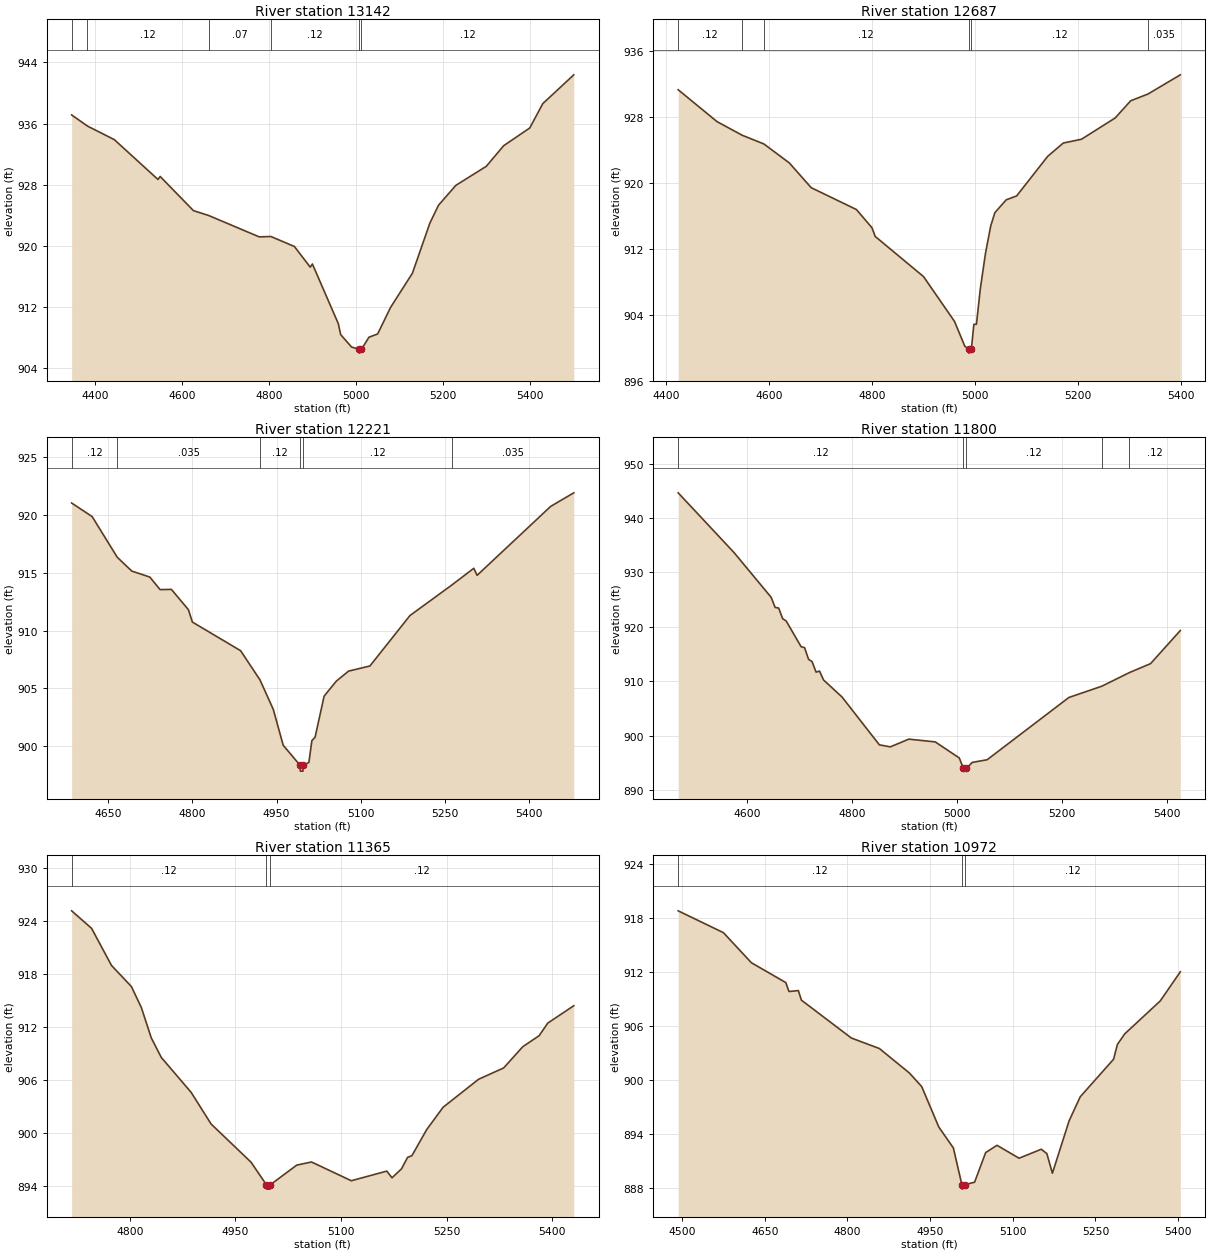
Type RM Length L Ch R = 1,13142,455,455,455
BEGIN DESCRIPTION:
Blieders Creek Tributary 11 27.0
END DESCRIPTION:
XS GIS Cut Line= 3
      2220469.25     13824672.23      2220375.00     13824025.00
      2220372.74     13823523.66
#Sta/Elev= 30
  4346.2  937.13  4382.6  935.67  4444.5  933.89  4544.8  928.68  4549.9  929.07
  4626.4  924.60  4661.1  923.97  4777.9  921.16  4804.8  921.21  4858.8  919.90
  4895.2  917.20  4900.2  917.61  4959.8  909.80  4965.2  908.37  4990.2  906.74
  5007.6  906.44  5008.0  905.94  5013.0  906.44  5030.3  908.02  5050.3  908.45
  5080.3  911.95  5130.3  916.40  5170.3  922.94  5190.3  925.30  5230.3  927.91
  5300.3  930.40  5340.3  933.10  5400.3  935.42  5430.3  938.61  5501.6  942.38
#Mann=6,-1,0
  4346.2    0.07       0  4382.6    0.12       0  4661.1    0.07       0
  4804.8    0.12       0  5007.6    0.05       0  5013.0    0.12       0
Bank Sta=5007.6,5013
Exp/Cntr=0.3,0.1

Type RM Length L Ch R = 1,12687,466,466,466
BEGIN DESCRIPTION:
Blieders Creek Tributary 11 26.0
END DESCRIPTION:
XS GIS Cut Line= 3
      2220819.94     13824450.24      2220775.00     13823875.00
      2220726.72     13823479.32
#Sta/Elev= 30
  4423.0  931.34  4498.5  927.47  4547.6  925.81  4589.5  924.76  4638.9  922.46
  4681.5  919.45  4769.3  916.80  4799.4  914.60  4805.9  913.53  4899.7  908.66
  4959.9  903.22  4979.9  900.21  4987.3  899.87  4987.7  899.37  4992.7  899.87
  4997.5  902.87  5002.5  902.87  5010.1  907.21  5020.1  911.49  5030.2  914.80
  5038.3  916.42  5060.4  917.98  5080.6  918.45  5141.0  923.26  5171.2  924.87
  5206.5  925.33  5272.0  927.91  5302.2  930.00  5335.8  930.82  5398.6  933.15
#Mann=6,-1,0
  4423.0    0.12       0  4547.6    0.07       0  4589.5    0.12       0
  4987.3    0.05       0  4992.7    0.12       0  5335.8   0.035       0
Bank Sta=4987.3,4992.7
Exp/Cntr=0.3,0.1

Type RM Length L Ch R = 1,12221,421,421,421
BEGIN DESCRIPTION:
Blieders Creek Tributary 11 25.0
END DESCRIPTION:
XS GIS Cut Line= 3
      2221276.80     13824241.18      2221225.00     13823825.00
      2220997.48     13823408.94
#Sta/Elev= 30
  4585.4  921.00  4621.9  919.83  4666.6  916.32  4692.4  915.13  4724.6  914.61
  4742.8  913.53  4762.9  913.55  4793.2  911.80  4800.3  910.73  4886.1  908.26
  4920.6  905.74  4944.3  903.19  4961.9  900.10  4992.0  898.37  4992.4  897.87
  4997.0  897.87  4997.5  898.37  5007.6  898.62  5012.9  900.50  5018.6  900.79
  5034.7  904.34  5056.5  905.64  5078.3  906.50  5116.2  906.94  5187.4  911.29
  5261.5  913.91  5301.1  915.37  5306.9  914.76  5437.9  920.71  5479.0  921.88
#Mann=6,-1,0
  4585.4    0.12       0  4666.6   0.035       0  4920.6    0.12       0
  4992.0    0.05       0  4997.5    0.12       0  5261.5   0.035       0
Bank Sta=4992,4997.5
Exp/Cntr=0.3,0.1

Type RM Length L Ch R = 1,11800,435,435,435
BEGIN DESCRIPTION:
Blieders Creek Tributary 11 24.0
END DESCRIPTION:
XS GIS Cut Line= 3
      2221975.03     13823975.02      2221575.00     13823625.00
      2221275.01     13823325.01
#Sta/Elev= 30
  4469.0  944.63  4575.3  933.66  4646.0  925.43  4653.6  923.57  4660.3  923.46
  4667.9  921.50  4674.5  921.10  4703.0  916.36  4709.6  916.19  4717.2  914.04
  4723.9  913.62  4731.5  911.69  4738.1  911.88  4745.7  910.25  4780.8  907.13
  4852.0  898.33  4872.9  897.96  4908.0  899.38  4958.3  898.87  5004.1  895.92
  5011.9  894.00  5012.4  893.50  5017.4  894.00  5028.8  895.10  5057.1  895.59
  5212.7  907.03  5275.6  909.11  5328.0  911.61  5368.2  913.25  5424.8  919.33
#Mann=5,-1,0
  4469.0    0.12       0  5011.9    0.05       0  5017.4    0.12       0
  5275.6   0.035       0  5328.0    0.12       0
Bank Sta=5011.9,5017.4
Exp/Cntr=0.3,0.1

Type RM Length L Ch R = 1,11365,393,393,393
BEGIN DESCRIPTION:
Blieders Creek Tributary 11 23.0
END DESCRIPTION:
XS GIS Cut Line= 3
      2222025.00     13823625.00      2221825.00     13823425.00
      2221474.97     13823174.98
#Sta/Elev= 30
  4717.5  925.11  4745.8  923.13  4774.1  918.93  4802.4  916.54  4816.5  914.16
  4830.6  910.73  4844.8  908.52  4887.2  904.57  4915.5  900.99  4972.1  896.68
  4994.0  894.12  4994.4  893.62  4999.2  893.62  4999.7  894.12  5037.2  896.34
  5058.1  896.69  5114.6  894.57  5165.0  895.66  5172.4  894.90  5185.9  895.92
  5194.5  897.21  5200.7  897.41  5221.6  900.35  5244.9  902.88  5295.3  906.05
  5330.9  907.33  5358.0  909.73  5381.3  910.98  5393.6  912.41  5430.5  914.37
#Mann=3,-1,0
  4717.5    0.12       0  4994.0    0.05       0  4999.7    0.12       0
Bank Sta=4994,4999.7
Exp/Cntr=0.3,0.1

Type RM Length L Ch R = 1,10972,507,507,507
BEGIN DESCRIPTION:
Blieders Creek Tributary 11 22.0
END DESCRIPTION:
XS GIS Cut Line= 3
      2222383.59     13823285.64      2221933.13     13823070.06
      2221525.00     13823125.00
#Sta/Elev= 30
  4492.9  918.84  4575.0  916.41  4625.8  913.06  4688.3  910.85  4693.9  909.86
  4711.0  909.96  4716.5  908.90  4807.2  904.68  4858.1  903.51  4912.6  900.78
  4934.8  899.28  4965.9  894.77  4992.3  892.44  5007.7  888.36  5008.2  887.86
  5013.4  888.36  5030.8  888.63  5050.9  891.93  5071.5  892.74  5111.5  891.30
  5151.8  892.30  5161.9  891.82  5172.0  889.63  5202.3  895.46  5222.5  898.14
  5283.0  902.32  5289.9  903.96  5303.2  905.14  5367.7  908.81  5404.1  912.05
#Mann=3,-1,0
  4492.9    0.12       0  5007.7    0.05       0  5013.4    0.12       0
Bank Sta=5007.7,5013.4
Exp/Cntr=0.3,0.1

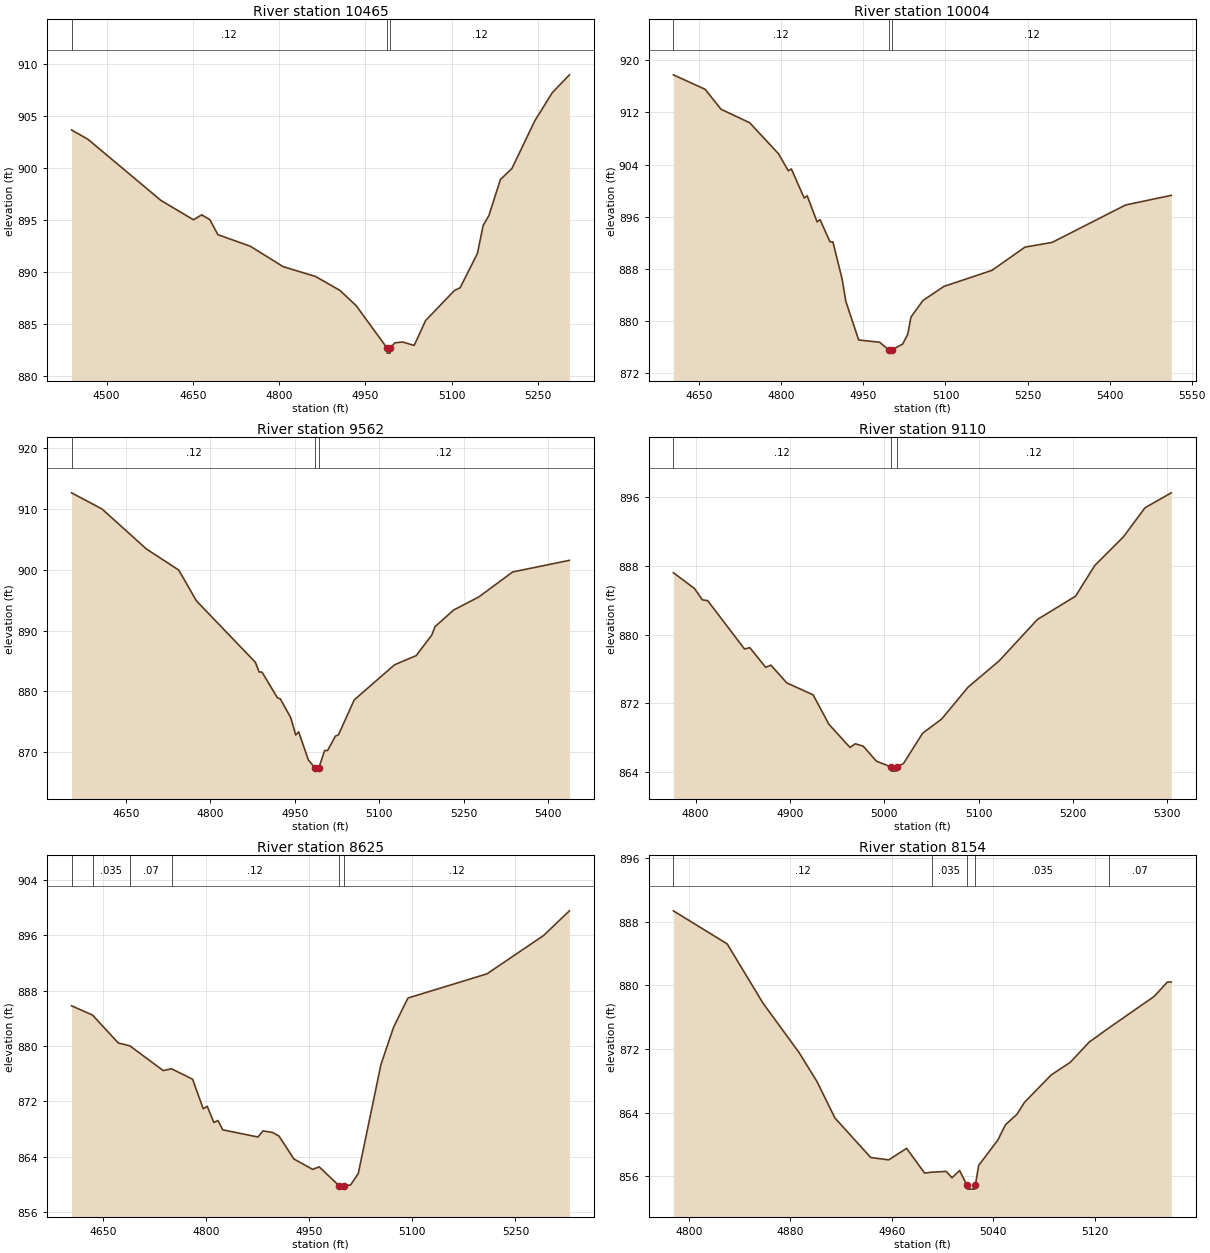
Type RM Length L Ch R = 1,10465,461,461,461
BEGIN DESCRIPTION:
Blieders Creek Tributary 11 21.0
END DESCRIPTION:
XS GIS Cut Line= 3
      2222374.99     13823024.99      2221975.00     13822625.00
      2221674.96     13822625.00
#Sta/Elev= 30
  4439.1  903.65  4467.4  902.76  4594.6  896.87  4651.2  895.01  4665.4  895.49
  4679.5  895.03  4693.6  893.58  4750.2  892.46  4806.8  890.51  4863.3  889.56
  4905.8  888.22  4934.1  886.75  4987.6  882.69  4988.1  882.19  4993.1  882.19
  4993.6  882.69  5001.2  883.18  5014.8  883.26  5034.8  882.93  5054.8  885.33
  5104.8  888.21  5114.8  888.48  5144.8  891.77  5154.8  894.47  5164.8  895.42
  5184.8  898.88  5204.8  899.94  5244.8  904.55  5274.8  907.22  5304.8  908.95
#Mann=3,-1,0
  4439.1    0.12       0  4987.6    0.05       0  4993.6    0.12       0
Bank Sta=4987.6,4993.6
Exp/Cntr=0.3,0.1

Type RM Length L Ch R = 1,10004,442,442,442
BEGIN DESCRIPTION:
Blieders Creek Tributary 11 20.0
END DESCRIPTION:
XS GIS Cut Line= 3
      2222708.50     13822564.94      2222364.25     13822416.94
      2221891.32     13822166.00
#Sta/Elev= 30
  4602.6  917.78  4660.6  915.56  4689.6  912.50  4742.1  910.42  4794.6  905.68
  4812.7  903.05  4818.2  903.34  4841.7  898.87  4847.2  899.21  4865.3  895.20
  4870.7  895.55  4888.8  892.16  4894.2  892.14  4911.2  886.37  4917.8  883.02
  4941.3  877.08  4979.7  876.73  4996.1  875.56  4996.6  875.06  5002.2  875.56
  5021.7  876.45  5031.1  877.96  5036.8  880.58  5058.8  883.14  5097.1  885.30
  5185.0  887.77  5245.3  891.33  5295.0  892.06  5429.3  897.80  5512.7  899.28
#Mann=3,-1,0
  4602.6    0.12       0  4996.1    0.05       0  5002.2    0.12       0
Bank Sta=4996.1,5002.2
Exp/Cntr=0.3,0.1

Type RM Length L Ch R = 1,9562,452,452,452
BEGIN DESCRIPTION:
Blieders Creek Tributary 11 19.0
END DESCRIPTION:
XS GIS Cut Line= 3
      2222756.74     13822159.55      2222325.00     13822025.00
      2221910.64     13821902.19
#Sta/Elev= 30
  4553.4  912.65  4607.6  909.99  4686.2  903.43  4743.8  899.95  4775.2  894.89
  4879.9  884.79  4886.6  883.19  4891.8  883.17  4919.1  878.94  4924.3  878.76
  4942.8  875.68  4951.6  872.84  4956.8  873.35  4974.2  868.71  4986.3  867.39
  4986.8  866.89  4992.5  867.39  5003.0  870.28  5008.2  870.28  5022.2  872.66
  5027.5  872.85  5055.5  878.60  5127.2  884.38  5165.6  885.88  5193.4  889.28
  5198.9  890.63  5232.1  893.38  5276.8  895.53  5337.0  899.64  5437.8  901.55
#Mann=3,-1,0
  4553.4    0.12       0  4986.3    0.05       0  4992.5    0.12       0
Bank Sta=4986.3,4992.5
Exp/Cntr=0.3,0.1

Type RM Length L Ch R = 1,9110,485,485,485
BEGIN DESCRIPTION:
Blieders Creek Tributary 11 18.0
END DESCRIPTION:
XS GIS Cut Line= 3
      2222524.98     13821674.99      2222325.00     13821575.00
      2222025.02     13821625.00
#Sta/Elev= 30
  4776.4  887.23  4798.7  885.40  4807.1  884.07  4812.7  883.98  4851.8  878.34
  4857.4  878.50  4874.2  876.21  4879.8  876.46  4896.6  874.39  4924.5  873.00
  4941.3  869.56  4963.6  866.87  4969.2  867.30  4977.6  867.02  4991.6  865.27
  5007.0  864.61  5007.5  864.11  5012.8  864.11  5013.3  864.61  5020.3  864.99
  5040.5  868.52  5060.8  870.19  5088.7  873.89  5121.6  876.95  5162.2  881.78
  5202.7  884.50  5223.0  888.07  5253.4  891.41  5276.2  894.79  5304.1  896.54
#Mann=3,-1,0
  4776.4    0.12       0  5007.0    0.05       0  5013.3    0.12       0
Bank Sta=5007,5013.3
Exp/Cntr=0.3,0.1

Type RM Length L Ch R = 1,8625,471,471,471
BEGIN DESCRIPTION:
Blieders Creek Tributary 11 17.0
END DESCRIPTION:
XS GIS Cut Line= 3
      2222763.20     13821329.50      2222425.00     13821125.00
      2222110.06     13821030.28
#Sta/Elev= 30
  4604.5  885.80  4635.0  884.46  4672.5  880.42  4689.3  880.01  4737.8  876.43
  4749.9  876.69  4780.5  875.18  4796.0  870.91  4801.8  871.26  4811.5  868.92
  4817.4  869.21  4824.4  867.86  4875.6  866.82  4882.9  867.71  4896.9  867.47
  4906.2  866.96  4927.9  863.64  4955.1  862.14  4964.7  862.50  4993.5  859.78
  4994.0  859.28  5000.1  859.78  5010.2  859.87  5021.5  861.53  5054.5  877.31
  5072.8  882.69  5093.7  886.92  5208.6  890.42  5290.9  895.96  5328.6  899.54
#Mann=6,-1,0
  4604.5    0.07       0  4635.0   0.035       0  4689.3    0.07       0
  4749.9    0.12       0  4993.5    0.05       0  5000.1    0.12       0
Bank Sta=4993.5,5000.1
Exp/Cntr=0.3,0.1

Type RM Length L Ch R = 1,8154,447,447,447
BEGIN DESCRIPTION:
Blieders Creek Tributary 11 16.0
END DESCRIPTION:
XS GIS Cut Line= 3
      2222924.98     13821024.98      2222775.00     13820875.00
      2222624.99     13820774.99
#Sta/Elev= 30
  4787.9  889.37  4830.3  885.21  4858.6  877.74  4886.9  871.56  4901.0  867.92
  4915.2  863.32  4943.4  858.35  4957.6  858.05  4971.7  859.50  4985.9  856.39
  4991.6  856.50  5003.0  856.60  5007.5  855.80  5013.5  856.71  5019.2  854.87
  5019.7  854.37  5025.4  854.37  5025.9  854.87  5028.5  857.35  5043.6  860.54
  5049.6  862.46  5058.6  863.77  5064.6  865.28  5085.6  868.72  5100.7  870.32
  5115.7  872.87  5131.2  874.65  5166.8  878.60  5177.3  880.42  5180.3  880.42
#Mann=5,-1,0
  4787.9    0.12       0  4991.6   0.035       0  5019.2   0.035       0
  5025.9   0.035       0  5131.2    0.07       0
Bank Sta=5019.2,5025.9
Exp/Cntr=0.3,0.1

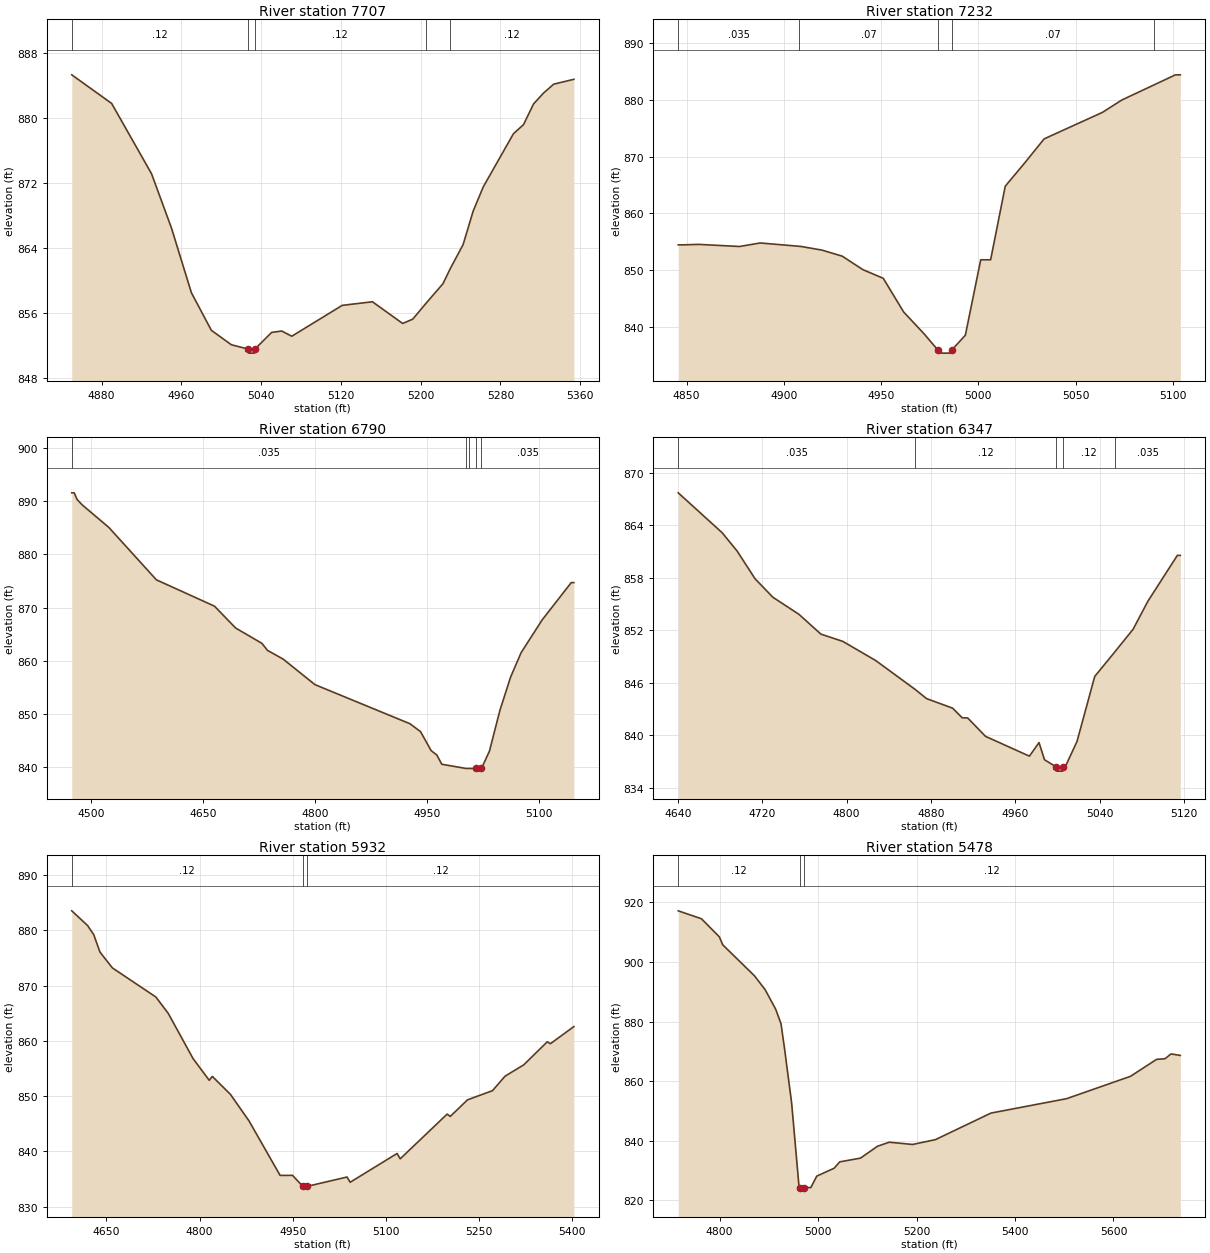
Type RM Length L Ch R = 1,7707,475,475,475
BEGIN DESCRIPTION:
Blieders Creek Tributary 11 15.0
END DESCRIPTION:
XS GIS Cut Line= 3
      2223125.00     13820775.04      2223125.00     13820625.00
      2223075.00     13820274.99
#Sta/Elev= 30
  4850.0  885.31  4890.0  881.79  4930.0  873.14  4950.0  866.46  4970.0  858.49
  4990.0  853.87  5010.1  852.09  5026.9  851.56  5027.4  851.06  5033.2  851.06
  5033.7  851.56  5050.5  853.61  5060.6  853.78  5070.7  853.14  5121.3  856.94
  5151.6  857.38  5181.9  854.71  5192.0  855.24  5204.9  857.13  5222.3  859.60
  5229.7  861.47  5242.5  864.41  5252.6  868.53  5262.7  871.51  5293.0  878.06
  5303.1  879.18  5313.2  881.73  5323.3  883.08  5333.4  884.16  5353.6  884.76
#Mann=5,-1,0
  4850.0    0.12       0  5026.9    0.05       0  5033.7    0.12       0
  5204.9    0.07       0  5229.7    0.12       0
Bank Sta=5026.9,5033.7
Exp/Cntr=0.3,0.1

Type RM Length L Ch R = 1,7232,442,442,442
BEGIN DESCRIPTION:
Blieders Creek Tributary 11 14.0
END DESCRIPTION:
XS GIS Cut Line= 3
      2223375.01     13820474.98      2223425.00     13820325.00
      2223425.00     13820225.00
#Sta/Elev= 29
  4845.7  854.47  4848.3  854.47  4856.2  854.55  4877.3  854.18  4887.8  854.80
  4907.7  854.22  4908.9  854.18  4919.5  853.55  4930.0  852.48  4940.6  850.11
  4951.1  848.58  4961.6  842.65  4972.2  838.77  4979.3  835.92  4979.8  835.42
  4985.7  835.42  4986.2  835.92  4993.3  838.57  5001.2  851.84  5003.8  851.84
  5006.3  851.84  5013.8  864.78  5023.8  868.88  5033.8  873.11  5063.8  877.78
  5073.8  879.96  5090.3  882.61  5101.3  884.38  5103.8  884.38
#Mann=5,-1,0
  4845.7   0.035       0  4907.7    0.07       0  4979.3    0.05       0
  4986.2    0.07       0  5090.3    0.12       0
Bank Sta=4979.3,4986.2
Exp/Cntr=0.3,0.1

Type RM Length L Ch R = 1,6790,443,443,443
BEGIN DESCRIPTION:
Blieders Creek Tributary 11 13.0
END DESCRIPTION:
XS GIS Cut Line= 3
      2223375.01     13820924.99      2223775.00     13820575.00
      2223874.99     13820475.01
#Sta/Elev= 30
  4473.7  891.53  4477.0  891.53  4480.8  890.29  4487.5  889.29  4523.5  885.02
  4587.1  875.20  4664.9  870.26  4693.4  866.15  4728.5  863.28  4736.1  861.95
  4757.0  860.32  4799.7  855.52  4926.9  848.19  4941.1  846.71  4955.4  843.13
  4963.0  842.31  4969.6  840.58  5002.1  839.79  5005.5  839.79  5015.9  839.79
  5016.4  839.29  5022.3  839.29  5022.8  839.79  5033.5  843.05  5047.6  850.74
  5061.8  856.93  5075.9  861.52  5104.2  867.69  5143.1  874.68  5146.6  874.68
#Mann=5,-1,0
  4473.7   0.035       0  5002.1    0.07       0  5005.5   0.035       0
  5015.9   0.035       0  5022.8   0.035       0
Bank Sta=5015.9,5022.8
Exp/Cntr=0.3,0.1

Type RM Length L Ch R = 1,6347,415,415,415
BEGIN DESCRIPTION:
Blieders Creek Tributary 11 12.0
END DESCRIPTION:
XS GIS Cut Line= 3
      2223725.03     13820974.99      2224075.00     13820875.00
      2224125.01     13820774.98
#Sta/Elev= 30
  4640.4  867.69  4682.0  863.14  4696.3  861.03  4713.2  857.88  4730.1  855.77
  4754.8  853.82  4775.6  851.56  4796.4  850.73  4827.6  848.54  4864.9  845.25
  4875.7  844.20  4900.4  843.11  4909.5  842.01  4914.7  841.99  4931.6  839.89
  4973.2  837.63  4982.3  839.18  4987.5  837.22  4998.3  836.42  4998.8  835.92
  5004.7  835.92  5005.2  836.42  5007.2  836.42  5018.3  839.31  5035.1  846.73
  5054.6  849.60  5071.5  852.12  5085.4  855.30  5113.4  860.55  5116.2  860.55
#Mann=5,-1,0
  4640.4   0.035       0  4864.9    0.12       0  4998.3    0.05       0
  5005.2    0.12       0  5054.6   0.035       0
Bank Sta=4998.3,5005.2
Exp/Cntr=0.3,0.1

Type RM Length L Ch R = 1,5932,454,454,454
BEGIN DESCRIPTION:
Blieders Creek Tributary 11 11.0
END DESCRIPTION:
XS GIS Cut Line= 3
      2224313.93     13821580.43      2224325.00     13821175.00
      2224275.00     13820774.99
#Sta/Elev= 30
  4594.2  883.53  4619.6  880.88  4629.6  879.22  4639.6  876.07  4659.7  873.20
  4729.7  867.94  4749.7  864.96  4789.7  856.78  4815.6  852.88  4820.6  853.58
  4849.7  850.34  4879.7  845.53  4929.8  835.67  4949.8  835.68  4966.3  833.69
  4966.8  833.19  4973.3  833.69  5037.6  835.38  5042.6  834.43  5118.2  839.64
  5123.2  838.67  5198.8  846.76  5203.9  846.34  5231.6  849.34  5271.9  851.00
  5292.0  853.61  5322.3  855.68  5360.1  859.84  5365.1  859.49  5402.9  862.59
#Mann=3,-1,0
  4594.2    0.12       0  4966.3    0.05       0  4973.3    0.12       0
Bank Sta=4966.3,4973.3
Exp/Cntr=0.3,0.1

Type RM Length L Ch R = 1,5478,444,444,444
BEGIN DESCRIPTION:
Blieders Creek Tributary 11 10.0
END DESCRIPTION:
XS GIS Cut Line= 3
      2224780.44     13821438.87      2224675.00     13821175.00
      2224391.15     13820496.22
#Sta/Elev= 30
  4715.9  917.15  4763.1  914.49  4799.4  908.43  4806.2  905.77  4870.8  895.35
  4892.4  890.72  4913.9  884.13  4924.7  879.28  4931.4  871.46  4946.2  852.82
  4961.0  825.13  4964.2  824.30  4964.7  823.80  4971.3  824.30  4985.2  824.33
  4997.4  828.17  5032.6  830.81  5043.9  832.94  5086.1  834.20  5120.7  838.18
  5144.5  839.54  5192.1  838.78  5238.5  840.41  5351.2  849.31  5504.8  854.14
  5634.6  861.64  5687.6  867.33  5704.6  867.53  5716.9  869.14  5735.8  868.65
#Mann=3,-1,0
  4715.9    0.12       0  4964.2    0.05       0  4971.3    0.12       0
Bank Sta=4964.2,4971.3
Exp/Cntr=0.3,0.1

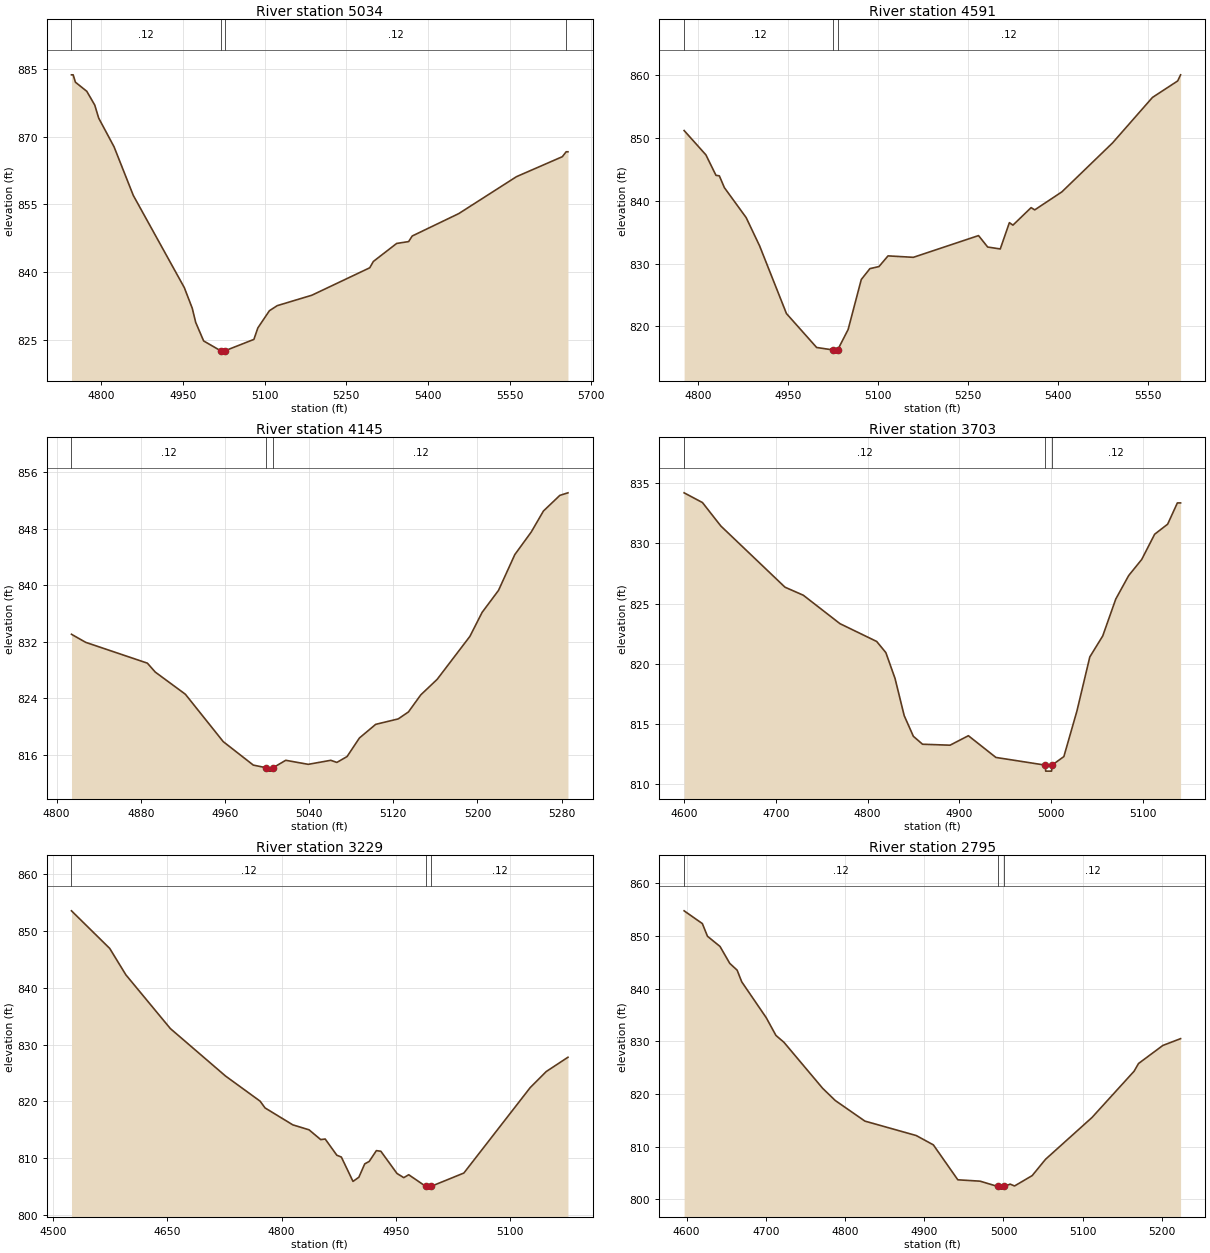
Type RM Length L Ch R = 1,5034,443,443,443
BEGIN DESCRIPTION:
Blieders Creek Tributary 11 9.0
END DESCRIPTION:
XS GIS Cut Line= 3
      2225074.97     13821024.96      2224925.00     13820825.00
      2224423.34     13820393.28
#Sta/Elev= 30
  4745.2  883.68  4748.3  883.68  4752.4  882.05  4773.3  880.03  4787.9  876.99
  4795.2  874.09  4823.3  867.76  4858.7  856.98  4952.4  836.56  4967.0  831.99
  4973.3  828.86  4987.9  824.75  5019.5  822.55  5020.0  822.05  5026.7  822.55
  5080.2  825.09  5087.5  827.64  5108.7  831.44  5123.0  832.56  5186.6  834.87
  5293.0  840.95  5299.6  842.35  5342.4  846.34  5364.4  846.75  5371.0  847.99
  5456.5  852.95  5562.5  861.13  5646.7  865.55  5653.7  866.64  5657.0  866.64
#Mann=4,-1,0
  4745.2    0.12       0  5019.5    0.05       0  5026.7    0.12       0
  5653.7    0.07       0
Bank Sta=5019.5,5026.7
Exp/Cntr=0.3,0.1

Type RM Length L Ch R = 1,4591,446,446,446
BEGIN DESCRIPTION:
Blieders Creek Tributary 11 8.0
END DESCRIPTION:
XS GIS Cut Line= 3
      2225274.99     13820674.98      2225175.00     13820475.00
      2224845.26     13819969.30
#Sta/Elev= 30
  4776.4  851.19  4812.7  847.32  4829.5  844.06  4835.1  843.98  4843.5  842.10
  4879.8  837.33  4902.2  832.83  4946.9  822.06  4997.2  816.66  5025.0  816.26
  5025.5  815.76  5032.2  816.26  5049.7  819.52  5071.6  827.48  5086.0  829.21
  5101.1  829.54  5116.2  831.24  5158.4  831.01  5267.0  834.47  5282.2  832.65
  5303.2  832.34  5318.4  836.53  5324.3  836.13  5354.6  838.92  5360.6  838.56
  5405.9  841.43  5490.3  849.22  5556.8  856.46  5598.9  859.09  5603.7  860.06
#Mann=3,-1,0
  4776.4    0.12       0  5025.0    0.05       0  5032.2    0.12       0
Bank Sta=5025,5032.2
Exp/Cntr=0.3,0.1

Type RM Length L Ch R = 1,4145,442,442,442
BEGIN DESCRIPTION:
Blieders Creek Tributary 11 7.0
END DESCRIPTION:
XS GIS Cut Line= 3
      2225625.01     13820375.02      2225525.00     13820225.00
      2225375.02     13819975.04
#Sta/Elev= 30
  4814.2  833.07  4827.7  831.93  4886.3  828.99  4893.8  827.73  4922.4  824.60
  4958.4  817.90  4987.0  814.58  4998.6  814.23  4999.1  813.73  5005.5  813.73
  5006.0  814.23  5017.8  815.26  5039.2  814.69  5060.6  815.26  5066.4  814.96
  5076.1  815.79  5087.8  818.41  5103.3  820.34  5124.7  821.11  5134.4  822.09
  5146.1  824.50  5161.7  826.70  5192.8  832.77  5204.4  836.16  5220.0  839.27
  5235.5  844.33  5251.1  847.52  5262.7  850.49  5278.3  852.70  5286.0  853.06
#Mann=3,-1,0
  4814.2    0.12       0  4998.6    0.05       0  5006.0    0.12       0
Bank Sta=4998.6,5006
Exp/Cntr=0.3,0.1

Type RM Length L Ch R = 1,3703,474,474,474
BEGIN DESCRIPTION:
Blieders Creek Tributary 11 6.0
END DESCRIPTION:
XS GIS Cut Line= 3
      2225825.00     13820324.98      2225825.00     13819925.00
      2225725.00     13819825.00
#Sta/Elev= 30
  4600.0  834.22  4620.0  833.41  4640.0  831.46  4710.0  826.36  4730.0  825.69
  4770.0  823.32  4810.0  821.84  4820.0  820.91  4830.0  818.76  4840.0  815.66
  4850.0  813.94  4860.0  813.28  4890.0  813.20  4910.0  813.99  4940.0  812.18
  4993.8  811.54  4994.3  811.04  5000.7  811.04  5001.2  811.54  5014.1  812.25
  5028.3  816.03  5042.4  820.55  5056.5  822.30  5070.7  825.37  5084.8  827.33
  5099.0  828.67  5113.1  830.77  5127.3  831.61  5137.9  833.38  5141.4  833.38
#Mann=3,-1,0
  4600.0    0.12       0  4993.8    0.05       0  5001.2    0.12       0
Bank Sta=4993.8,5001.2
Exp/Cntr=0.3,0.1

Type RM Length L Ch R = 1,3229,434,434,434
BEGIN DESCRIPTION:
Blieders Creek Tributary 11 5.0
END DESCRIPTION:
XS GIS Cut Line= 3
      2226625.04     13819975.02      2226225.00     13819725.00
      2226125.01     13819575.02
#Sta/Elev= 30
  4524.0  853.53  4574.2  846.92  4595.4  842.28  4653.8  832.83  4726.3  824.48
  4771.7  820.06  4778.2  818.87  4814.7  815.89  4836.0  815.02  4851.3  813.30
  4857.2  813.40  4872.5  810.55  4878.4  810.23  4893.7  805.95  4901.4  806.68
  4909.1  809.03  4915.0  809.46  4924.4  811.36  4930.3  811.25  4951.5  807.34
  4960.4  806.61  4966.9  807.12  4989.1  805.09  4989.6  804.59  4996.0  804.59
  4996.5  805.09  5039.3  807.42  5126.4  822.44  5147.5  825.27  5176.0  827.78
#Mann=3,-1,0
  4524.0    0.12       0  4989.1    0.05       0  4996.5    0.12       0
Bank Sta=4989.1,4996.5
Exp/Cntr=0.3,0.1

Type RM Length L Ch R = 1,2795,466,466,466
BEGIN DESCRIPTION:
Blieders Creek Tributary 11 4.0
END DESCRIPTION:
XS GIS Cut Line= 3
      2226724.99     13819824.98      2226525.00     13819475.00
      2226325.00     13819375.00
#Sta/Elev= 30
  4596.9  854.76  4619.9  852.34  4626.4  849.93  4642.2  848.00  4654.5  844.79
  4663.8  843.50  4669.6  841.29  4700.5  834.49  4712.8  831.11  4722.9  829.81
  4771.8  821.07  4787.6  818.77  4825.1  814.85  4889.9  812.11  4911.5  810.34
  4942.4  803.71  4970.5  803.45  4992.9  802.44  4993.4  801.94  5000.8  801.94
  5001.3  802.44  5008.4  802.89  5014.0  802.54  5036.3  804.51  5053.1  807.60
  5111.8  815.54  5164.9  824.32  5170.5  825.78  5201.2  829.21  5223.6  830.50
#Mann=3,-1,0
  4596.9    0.12       0  4992.9    0.05       0  5001.3    0.12       0
Bank Sta=4992.9,5001.3
Exp/Cntr=0.3,0.1