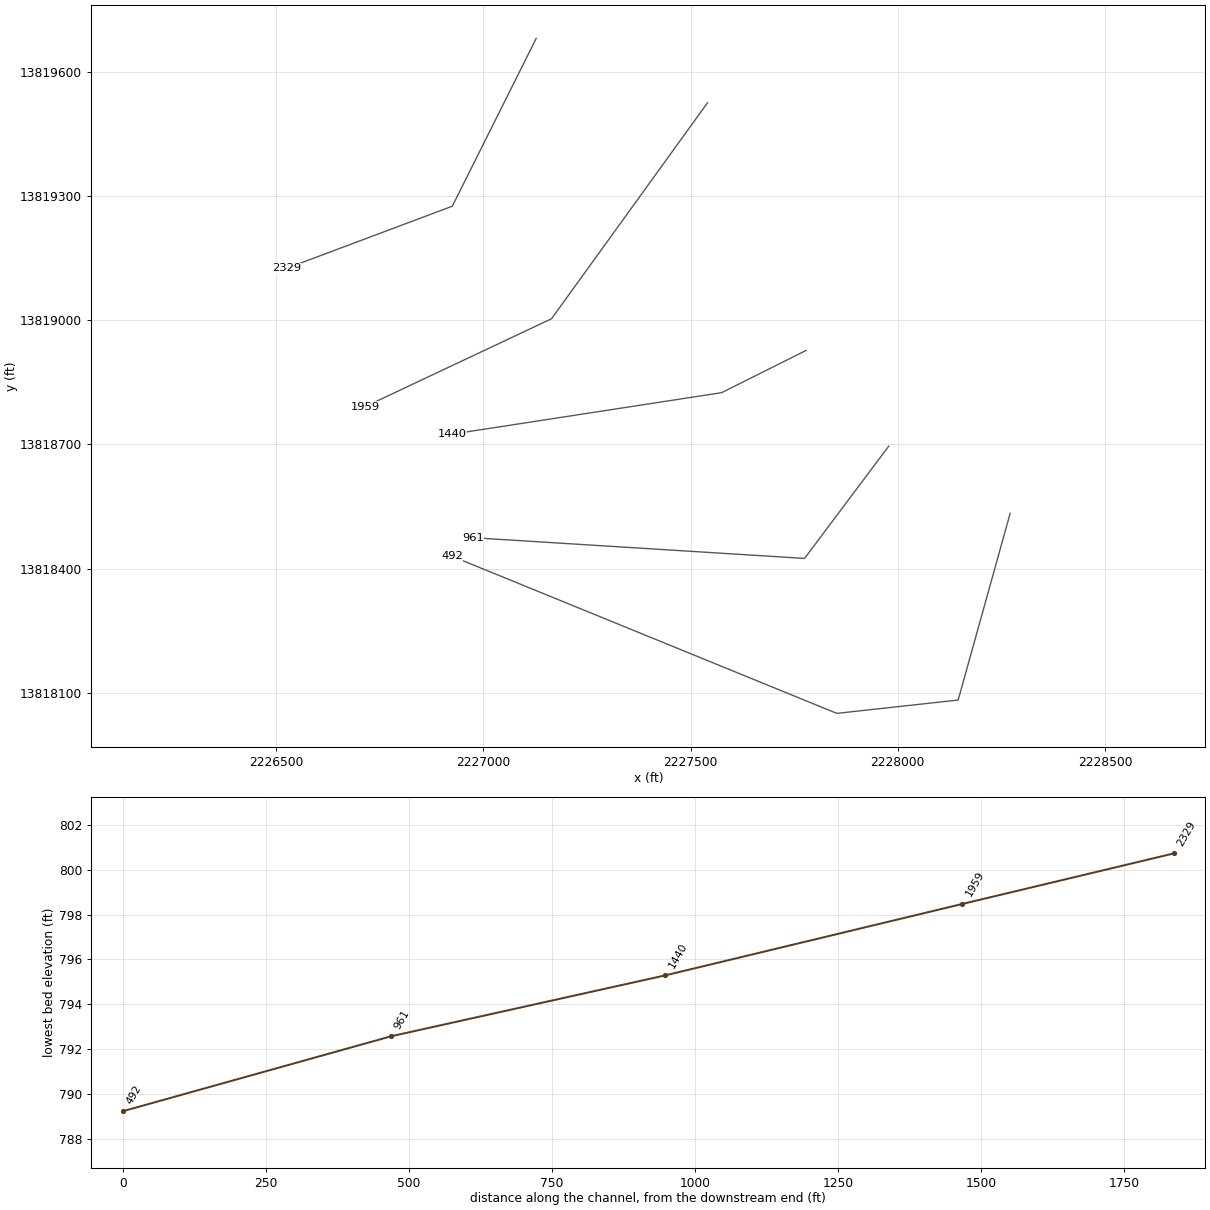
HEC-RAS study Blieders Creek Tributary 11.prj: Blieders Creek Tributary 11 Base Level Engineering

--- Blieders Creek Tributary 11.g01 (geometry) --- (continued)

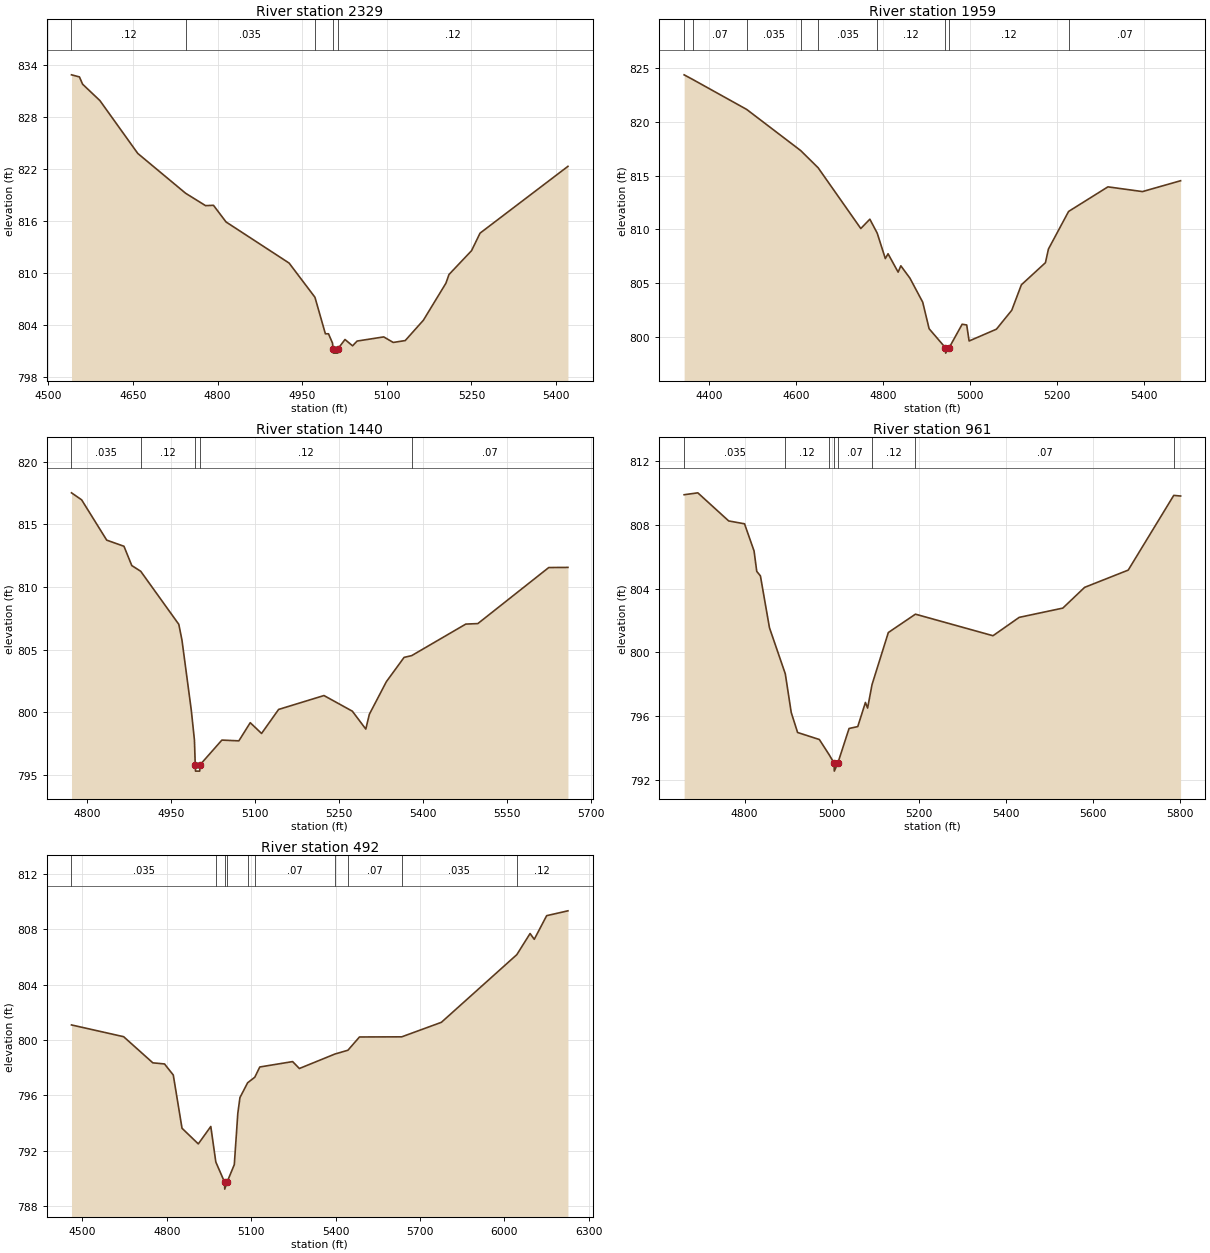
Type RM Length L Ch R = 1,2329,370,370,370
BEGIN DESCRIPTION:
Blieders Creek Tributary 11 3.0
END DESCRIPTION:
XS GIS Cut Line= 4
      2227127.54     13819680.08      2227025.00     13819475.00
      2226925.00     13819275.00      2226525.00     13819125.00
#Sta/Elev= 30
  4540.9  832.82  4555.0  832.58  4560.6  831.74  4591.3  829.85  4658.4  823.76
  4743.2  819.17  4778.6  817.74  4792.6  817.78  4814.9  815.86  4926.7  811.12
  4972.5  807.18  4991.0  802.97  4996.5  802.97  5003.6  801.90  5004.7  801.24
  5005.2  800.74  5012.7  800.74  5013.2  801.24  5025.8  802.31  5039.2  801.58
  5047.2  802.13  5094.4  802.61  5111.3  801.97  5132.6  802.19  5164.7  804.53
  5204.7  808.80  5210.1  809.80  5250.1  812.55  5265.2  814.57  5421.0  822.27
#Mann=5,-1,0
  4540.9    0.12       0  4743.2   0.035       0  4972.5    0.12       0
  5004.7    0.05       0  5013.2    0.12       0
Bank Sta=5004.7,5013.2
Exp/Cntr=0.3,0.1

Type RM Length L Ch R = 1,1959,519,519,519
BEGIN DESCRIPTION:
X18289
END DESCRIPTION:
XS GIS Cut Line= 3
      2227540.91     13819524.62      2227164.46     13819003.39
      2226714.07     13818791.06
#Sta/Elev= 30
  4342.9  824.39  4362.6  823.96  4486.6  821.17  4610.7  817.34  4650.8  815.74
  4748.9  810.08  4769.7  810.95  4786.6  809.65  4805.3  807.28  4811.5  807.73
  4834.7  806.02  4840.9  806.61  4861.8  805.46  4891.2  803.22  4905.9  800.75
  4943.4  798.98  4943.9  798.48  4951.9  798.98  4981.8  801.17  4992.3  801.10
  4997.8  799.61  5060.6  800.71  5095.8  802.47  5117.9  804.84  5173.2  806.90
  5180.1  808.17  5226.4  811.67  5316.8  813.96  5396.2  813.52  5483.8  814.53
#Mann=9,-1,0
  4342.9    0.12       0  4362.6    0.07       0  4486.6   0.035       0
  4610.7    0.12       0  4650.8   0.035       0  4786.6    0.12       0
  4943.4    0.05       0  4951.9    0.12       0  5226.4    0.07       0
Bank Sta=4943.4,4951.9
Exp/Cntr=0.3,0.1

Type RM Length L Ch R = 1,1440,479,479,479
BEGIN DESCRIPTION:
Blieders Creek Tributary 11 2.0
END DESCRIPTION:
XS GIS Cut Line= 4
      2227778.67     13818926.84      2227675.00     13818875.00
      2227575.00     13818825.00      2226924.96     13818724.99
#Sta/Elev= 30
  4772.8  817.53  4790.9  816.97  4835.6  813.75  4866.4  813.26  4880.3  811.72
  4896.3  811.26  4964.2  807.02  4969.8  805.77  4986.5  800.15  4992.1  797.76
  4993.5  795.79  4994.0  795.29  5001.5  795.29  5002.0  795.79  5041.0  797.77
  5071.3  797.71  5091.6  799.16  5111.8  798.30  5142.2  800.22  5223.1  801.33
  5273.7  800.08  5297.7  798.65  5304.0  799.83  5334.4  802.44  5366.0  804.38
  5379.5  804.52  5476.0  807.04  5497.5  807.08  5624.0  811.56  5658.2  811.57
#Mann=5,-1,0
  4772.8   0.035       0  4896.3    0.12       0  4993.5    0.05       0
  5002.0    0.12       0  5379.5    0.07       0
Bank Sta=4993.5,5002
Exp/Cntr=0.3,0.1

Type RM Length L Ch R = 1,961,469,469,469
BEGIN DESCRIPTION:
Blieders Creek Tributary 11 1.0
END DESCRIPTION:
XS GIS Cut Line= 4
      2227978.23     13818695.98      2227925.00     13818625.00
      2227775.00     13818425.00      2226974.98     13818475.00
#Sta/Elev= 30
  4661.3  809.88  4692.7  810.00  4763.6  808.24  4800.0  808.06  4821.9  806.36
  4828.1  805.08  4836.5  804.80  4857.3  801.55  4893.7  798.66  4907.3  796.24
  4921.9  794.99  4971.9  794.55  4994.8  793.58  5005.7  793.07  5006.2  792.57
  5014.3  793.07  5040.1  795.24  5060.1  795.36  5077.7  796.87  5082.7  796.52
  5092.9  797.99  5130.3  801.25  5192.6  802.40  5370.7  801.05  5430.9  802.20
  5531.1  802.78  5581.2  804.08  5681.3  805.16  5785.9  809.84  5801.6  809.80
#Mann=8,-1,0
  4661.3   0.035       0  4893.7    0.12       0  4994.8    0.07       0
  5005.7    0.05       0  5014.3    0.07       0  5092.9    0.12       0
  5192.6    0.07       0  5785.9    0.12       0
Bank Sta=5005.7,5014.3
Exp/Cntr=0.3,0.1

Type RM Length L Ch R = 1,492,0,0,0
BEGIN DESCRIPTION:
X18288
END DESCRIPTION:
XS GIS Cut Line= 4
      2228271.23     13818533.70      2228145.74     13818083.24
      2227852.97     13818051.07      2226924.06     13818430.34
#Sta/Elev= 30
  4461.1  801.09  4646.6  800.24  4750.4  798.35  4791.9  798.27  4823.1  797.47
  4854.2  793.62  4912.1  792.49  4956.5  793.75  4974.4  791.18  5005.6  789.72
  5006.1  789.22  5014.2  789.72  5040.1  790.99  5052.6  794.70  5060.2  795.84
  5087.5  796.91  5113.0  797.31  5130.7  798.05  5247.5  798.44  5271.5  797.94
  5398.3  798.99  5444.1  799.26  5485.3  800.22  5635.6  800.23  5776.6  801.28
  6044.7  806.17  6092.0  807.70  6106.8  807.28  6150.9  808.99  6226.6  809.34
#Mann=10,-1,0
  4461.1   0.035       0  4974.4    0.07       0  5005.6    0.05       0
  5014.2    0.07       0  5087.5    0.12       0  5113.0    0.07       0
  5398.3   0.035       0  5444.1    0.07       0  5635.6   0.035       0
  6044.7    0.12       0
Bank Sta=5005.6,5014.2
Exp/Cntr=0.3,0.1

Chan Stop Cuts=-1