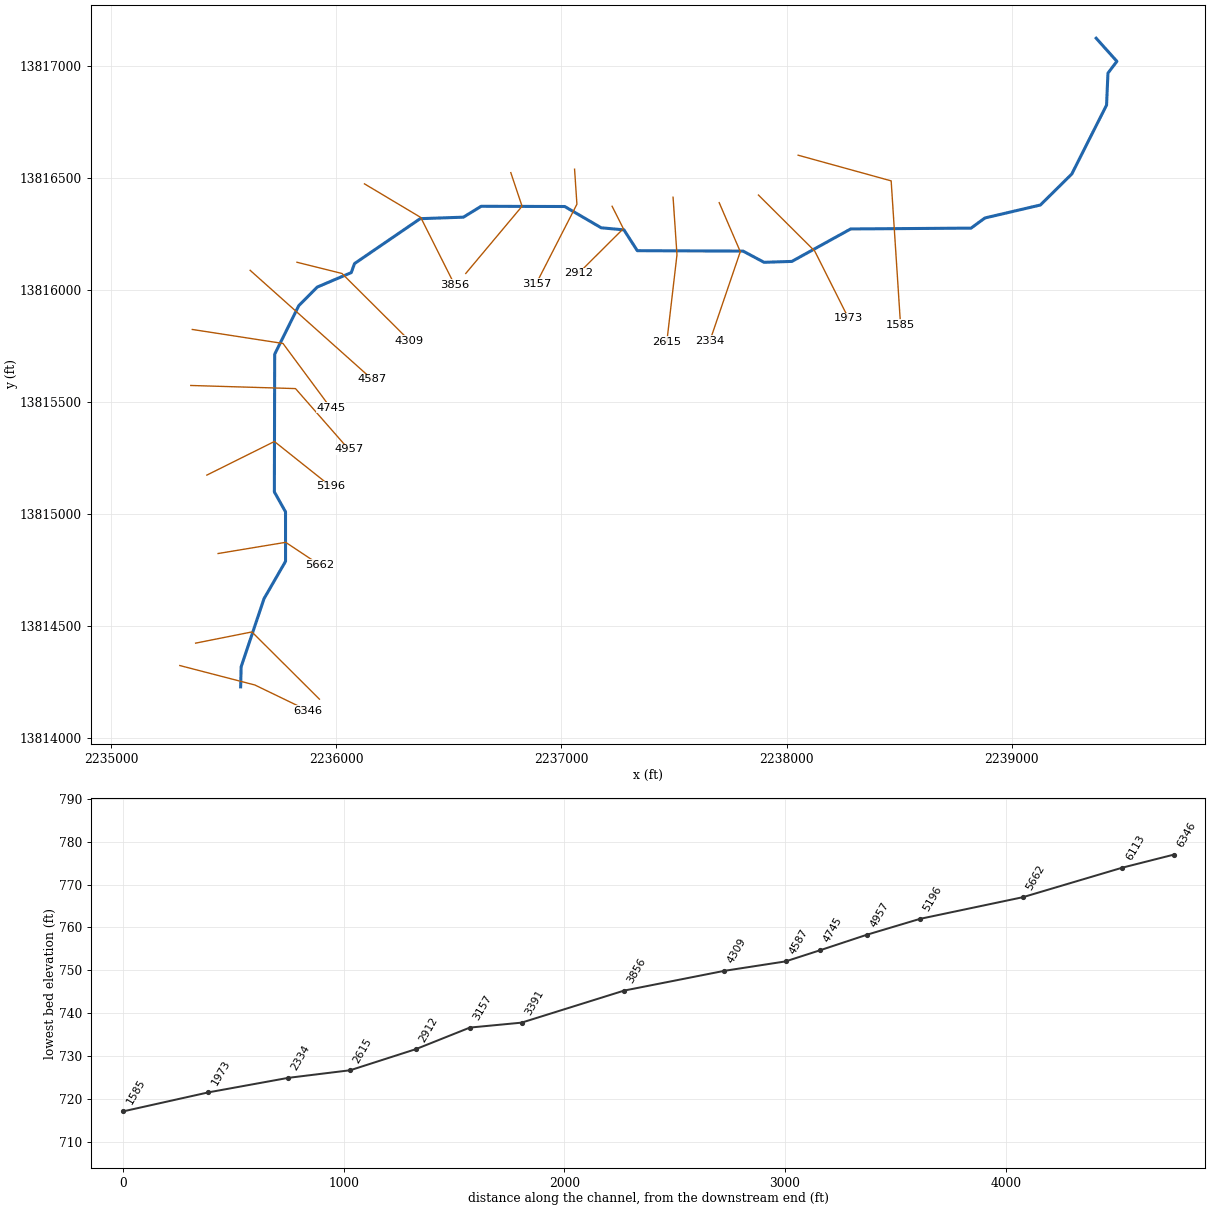
--- Blieders Creek Tributary 3.prj (project) ---

Proj Title=Blieders Creek Tributary 3 Base Level Engineering
Current Plan=p01
Default Exp/Contr=0.3,0.1
English Units
Geom File=g01
Flow File=f01
Plan File=p01
BEGIN DESCRIPTION:
Blieders Creek Tributary 3
END DESCRIPTION:

--- Blieders Creek Tributary 3.p01 (plan) ---

Plan Title=Multiple Run
Short Identifier=Multiple
Geom File=g01
Flow File=f01
Subcritical Flow
K Sum by GR= 0
Std Step Tol= 0.01
Critical Tol= 0.01
Num of Std Step Trials= 20
Max Error Tol= 0.3
Flow Tol Ratio= 0.001
Split Flow NTrial= 30
Split Flow Tol= 0.02
Split Flow Ratio= 0.02
Log Output Level= 0
Friction Slope Method= 1
Unsteady Friction Slope Method= 2
Unsteady Bridges Friction Slope Method= 1
Parabolic Critical Depth
Global Vel Dist=  1 , 1 , 1
Global Log Level= 0
CheckData=True
Encroach Param= -1, 0, 0, 0
BEGIN DESCRIPTION:
Multiple Run
END DESCRIPTION:

--- Blieders Creek Tributary 3.f01 (steady flow) ---

Flow Title=Multiple
Number of Profiles=7
Profile Names=10-year,25-year,50-year,1pct_min,100-year,1pct_plu,500-year
River Rch & RM= Blieders Creek T,Reach-1,6346
     665    1085    1470     965    1926    3843    3270
Boundary for River Rch & Prof#=Blieders Creek T,Reach-1,1
Up Type=0
Dn Type=3
Dn Slope=0.005
Boundary for River Rch & Prof#=Blieders Creek T,Reach-1,2
Up Type=0
Dn Type=3
Dn Slope=0.005
Boundary for River Rch & Prof#=Blieders Creek T,Reach-1,3
Up Type=0
Dn Type=3
Dn Slope=0.005
Boundary for River Rch & Prof#=Blieders Creek T,Reach-1,4
Up Type=0
Dn Type=3
Dn Slope=0.005
Boundary for River Rch & Prof#=Blieders Creek T,Reach-1,5
Up Type=0
Dn Type=3
Dn Slope=0.005
Boundary for River Rch & Prof#=Blieders Creek T,Reach-1,6
Up Type=0
Dn Type=3
Dn Slope=0.005
Boundary for River Rch & Prof#=Blieders Creek T,Reach-1,7
Up Type=0
Dn Type=3
Dn Slope=0.005

--- Blieders Creek Tributary 3.g01 (geometry) ---

Geom Title=Existing Conditions

River Reach=Blieders Creek T,Reach-1
Reach XY= 30
      2235575.00     13814229.87      2235577.21     13814319.54
      2235678.83     13814623.42      2235774.49     13814790.21
      2235774.32     13815011.08      2235724.80     13815099.92
      2235726.20     13815714.50      2235833.13     13815931.07
      2235915.30     13816014.24      2236066.38     13816078.84
      2236080.77     13816119.01      2236372.55     13816319.53
      2236564.49     13816326.22      2236643.27     13816374.79
      2237014.50     13816373.80      2237176.59     13816278.83
      2237277.66     13816269.54      2237336.83     13816176.64
      2237806.73     13816174.79      2237899.93     13816124.77
      2238023.44     13816128.74      2238284.65     13816273.64
      2238819.47     13816277.38      2238880.98     13816322.64
      2239127.43     13816380.52      2239266.86     13816518.94
      2239421.24     13816826.56      2239427.47     13816969.15
      2239467.19     13817021.79      2239375.00     13817125.00

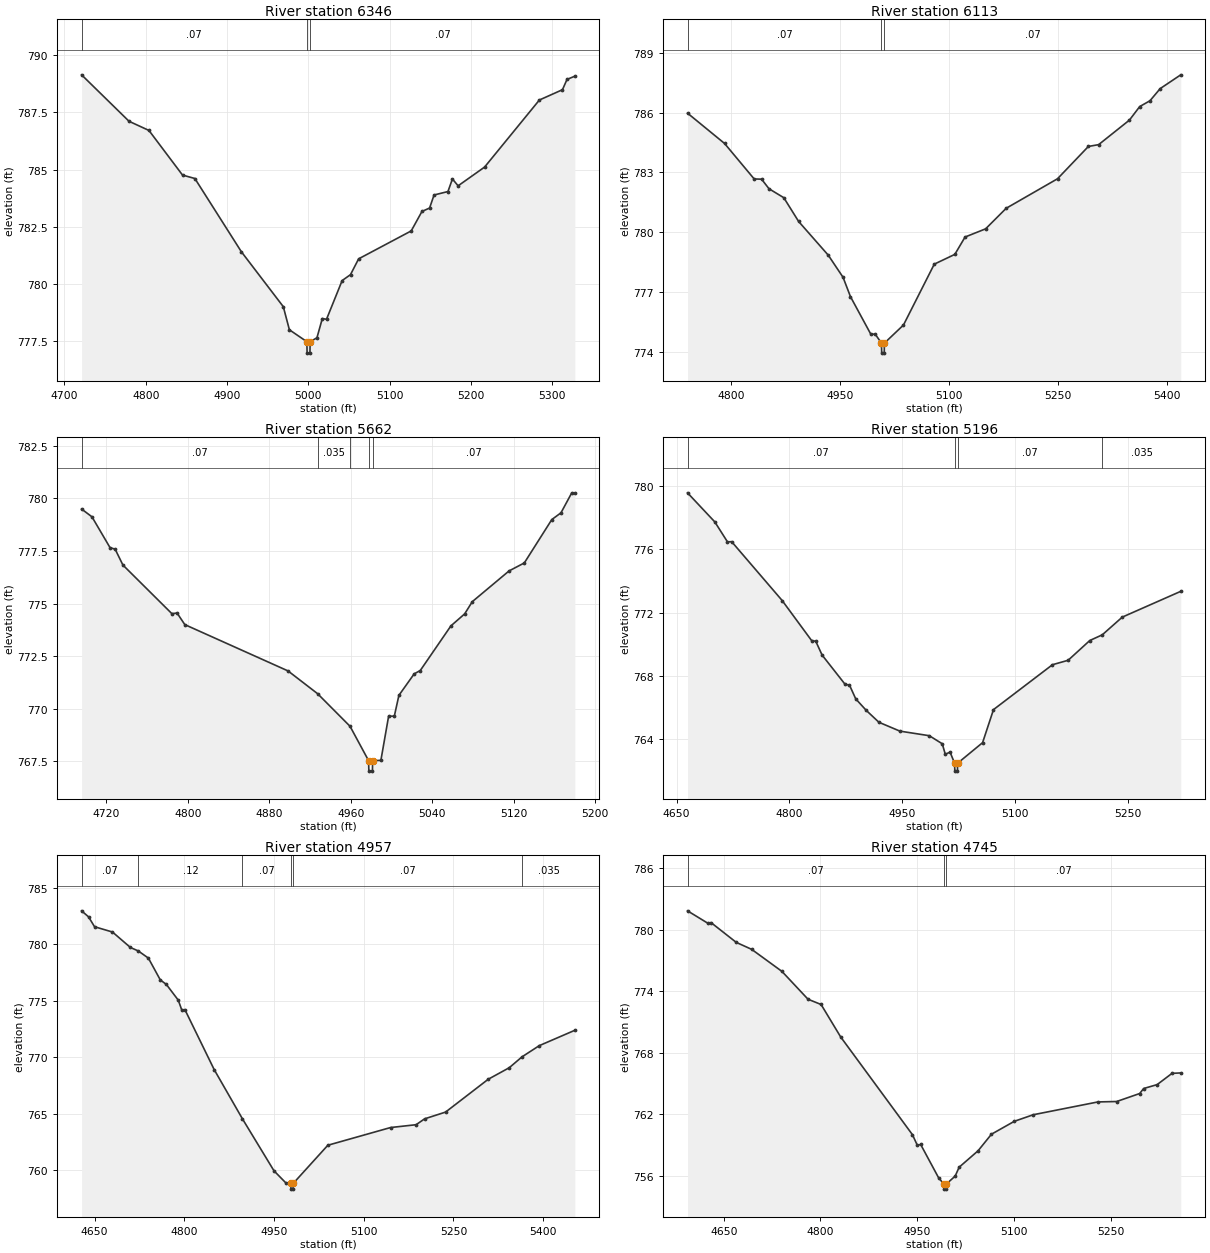
Type RM Length L Ch R = 1,6346,233,233,233
BEGIN DESCRIPTION:
X18295
END DESCRIPTION:
XS GIS Cut Line= 3
      2235304.78     13814325.04      2235638.11     13814238.23
      2235874.23     13814123.65
#Sta/Elev= 30
  4721.1  789.14  4779.5  787.11  4804.0  786.71  4845.3  784.76  4860.5  784.61
  4917.7  781.41  4969.3  779.01  4976.8  778.00  4998.3  777.48  4998.6  776.98
  5002.1  776.98  5002.3  777.48  5010.7  777.65  5017.3  778.49  5022.5  778.46
  5041.7  780.15  5052.0  780.41  5062.0  781.10  5126.7  782.32  5139.9  783.17
  5149.3  783.32  5154.8  783.89  5171.9  784.04  5177.4  784.59  5184.4  784.29
  5217.0  785.11  5284.4  788.04  5312.8  788.49  5318.4  788.94  5328.0  789.08
#Mann=3,-1,0
  4721.1    0.07       0  4998.3    0.05       0  5002.3    0.07       0
Bank Sta=4998.3,5002.3
Exp/Cntr=0.3,0.1

Type RM Length L Ch R = 1,6113,451,451,451
BEGIN DESCRIPTION:
Blieders Creek Tributary 3 13.0
END DESCRIPTION:
XS GIS Cut Line= 3
      2235374.99     13814425.00      2235625.00     13814475.00
      2235924.98     13814175.02
#Sta/Elev= 30
  4740.4  785.97  4791.4  784.45  4832.2  782.67  4842.4  782.66  4852.6  782.18
  4873.0  781.73  4893.4  780.54  4934.2  778.85  4954.6  777.74  4964.8  776.77
  4992.8  774.89  4998.9  774.89  5007.5  774.44  5007.8  773.94  5011.3  773.94
  5011.5  774.44  5037.8  775.35  5080.2  778.40  5108.5  778.89  5122.6  779.76
  5150.9  780.17  5179.2  781.20  5249.9  782.68  5292.4  784.30  5306.5  784.39
  5348.9  785.62  5363.1  786.30  5377.2  786.59  5391.3  787.20  5419.6  787.89
#Mann=3,-1,0
  4740.4    0.07       0  5007.5    0.05       0  5011.5    0.07       0
Bank Sta=5007.5,5011.5
Exp/Cntr=0.3,0.1

Type RM Length L Ch R = 1,5662,466,466,466
BEGIN DESCRIPTION:
Blieders Creek Tributary 3 12.0
END DESCRIPTION:
XS GIS Cut Line= 3
      2235474.96     13814824.99      2235775.00     13814875.00
      2235925.04     13814774.98
#Sta/Elev= 30
  4695.7  779.49  4705.9  779.12  4723.6  777.66  4728.7  777.58  4736.3  776.83
  4784.4  774.52  4789.5  774.55  4797.1  774.00  4898.5  771.80  4927.5  770.72
  4959.4  769.17  4977.6  767.54  4977.9  767.04  4981.4  767.04  4981.6  767.54
  4989.7  767.55  4997.3  769.65  5002.9  769.65  5007.4  770.64  5022.4  771.66
  5028.4  771.82  5058.5  773.94  5072.0  774.51  5079.5  775.09  5115.6  776.55
  5130.6  776.93  5157.6  778.99  5166.6  779.31  5177.2  780.26  5180.2  780.26
#Mann=5,-1,0
  4695.7    0.07       0  4927.5   0.035       0  4959.4    0.07       0
  4977.6    0.05       0  4981.6    0.07       0
Bank Sta=4977.6,4981.6
Exp/Cntr=0.3,0.1

Type RM Length L Ch R = 1,5196,239,239,239
BEGIN DESCRIPTION:
Blieders Creek Tributary 3 11.0
END DESCRIPTION:
XS GIS Cut Line= 3
      2235424.99     13815175.00      2235725.00     13815325.00
      2235975.02     13815124.98
#Sta/Elev= 30
  4664.6  779.58  4700.9  777.74  4717.7  776.48  4723.3  776.49  4790.4  772.77
  4829.5  770.24  4835.1  770.19  4843.5  769.32  4874.2  767.46  4879.8  767.43
  4888.2  766.55  4902.2  765.82  4919.0  765.07  4946.9  764.51  4986.0  764.22
  5003.2  763.71  5007.2  763.05  5013.6  763.18  5019.6  762.48  5019.9  761.98
  5023.4  761.98  5023.6  762.48  5056.8  763.78  5071.3  765.87  5149.7  768.71
  5170.5  768.99  5199.3  770.24  5215.9  770.60  5242.5  771.72  5320.2  773.35
#Mann=4,-1,0
  4664.6    0.07       0  5019.6    0.05       0  5023.6    0.07       0
  5215.9   0.035       0
Bank Sta=5019.6,5023.6
Exp/Cntr=0.3,0.1

Type RM Length L Ch R = 1,4957,212,212,212
BEGIN DESCRIPTION:
X18296
END DESCRIPTION:
XS GIS Cut Line= 3
      2235353.36     13815575.04      2235818.67     13815561.15
      2236054.76     13815290.34
#Sta/Elev= 30
  4628.2  782.97  4639.8  782.44  4649.9  781.56  4679.9  781.09  4709.9  779.72
  4723.1  779.41  4739.9  778.78  4759.9  776.84  4769.9  776.45  4789.9  775.05
  4796.0  774.14  4801.0  774.21  4849.9  768.90  4897.2  764.53  4950.0  759.92
  4970.0  758.84  4978.0  758.80  4978.3  758.30  4981.8  758.30  4982.0  758.80
  5040.0  762.19  5144.9  763.76  5187.6  764.01  5201.8  764.53  5236.9  765.13
  5308.2  768.04  5343.3  769.06  5364.8  770.03  5393.6  771.02  5453.0  772.38
#Mann=6,-1,0
  4628.2    0.07       0  4723.1    0.12       0  4897.2    0.07       0
  4978.0    0.05       0  4982.0    0.07       0  5364.8   0.035       0
Bank Sta=4978,4982
Exp/Cntr=0.3,0.1

Type RM Length L Ch R = 1,4745,158,158,158
BEGIN DESCRIPTION:
Blieders Creek Tributary 3 10.0
END DESCRIPTION:
XS GIS Cut Line= 3
      2235360.33     13815825.04      2235763.11     13815762.54
      2235975.01     13815474.98
#Sta/Elev= 30
  4593.9  781.84  4625.4  780.63  4630.4  780.69  4669.5  778.76  4693.4  778.08
  4740.3  775.93  4780.8  773.21  4801.0  772.70  4831.4  769.53  4942.7  759.99
  4950.3  758.95  4955.4  759.04  4983.2  755.79  4991.3  755.18  4991.5  754.68
  4995.0  754.68  4995.3  755.18  5008.9  755.95  5015.1  756.82  5044.4  758.42
  5065.2  760.04  5100.7  761.30  5130.0  761.94  5230.3  763.19  5259.3  763.23
  5295.0  764.01  5301.2  764.50  5322.1  764.88  5345.2  765.98  5358.7  766.02
#Mann=3,-1,0
  4593.9    0.07       0  4991.3    0.05       0  4995.3    0.07       0
Bank Sta=4991.3,4995.3
Exp/Cntr=0.3,0.1

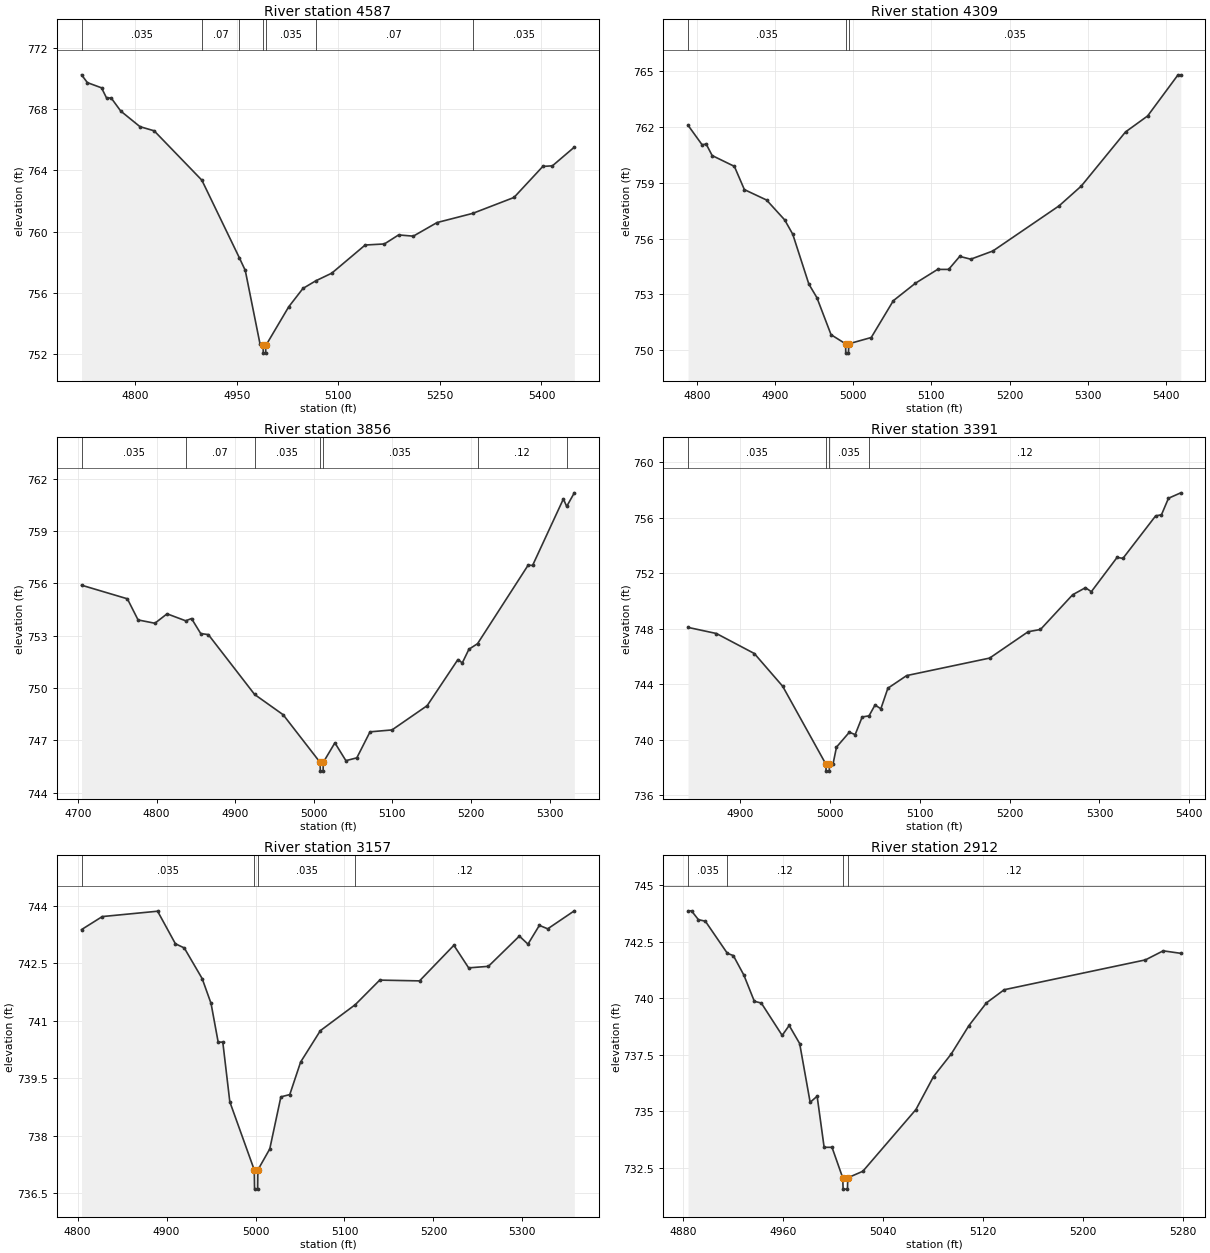
Type RM Length L Ch R = 1,4587,278,278,278
BEGIN DESCRIPTION:
X18297
END DESCRIPTION:
XS GIS Cut Line= 2
      2235617.25     13816088.95      2236158.91     13815602.85
#Sta/Elev= 30
  4720.7  770.25  4729.3  769.74  4750.2  769.40  4757.7  768.73  4764.4  768.74
  4778.6  767.88  4807.0  766.86  4827.9  766.59  4898.4  763.36  4953.6  758.30
  4962.5  757.46  4984.2  752.67  4988.9  752.55  4989.1  752.05  4992.6  752.05
  4992.9  752.55  5026.7  755.08  5047.7  756.28  5066.7  756.78  5090.3  757.28
  5139.6  759.12  5168.0  759.19  5189.0  759.78  5210.7  759.70  5245.8  760.59
  5298.5  761.19  5359.4  762.23  5402.0  764.26  5416.2  764.30  5448.5  765.52
#Mann=7,-1,0
  4720.7   0.035       0  4898.4    0.07       0  4953.6   0.035       0
  4988.9   0.035       0  4992.9   0.035       0  5066.7    0.07       0
  5298.5   0.035       0
Bank Sta=4988.9,4992.9
Exp/Cntr=0.3,0.1

Type RM Length L Ch R = 1,4309,453,453,453
BEGIN DESCRIPTION:
Blieders Creek Tributary 3 9.0
END DESCRIPTION:
XS GIS Cut Line= 3
      2235825.01     13816125.00      2236025.00     13816075.00
      2236324.99     13815775.01
#Sta/Elev= 30
  4788.6  762.09  4806.6  761.04  4811.8  761.08  4819.5  760.46  4847.9  759.88
  4860.7  758.63  4889.1  758.07  4912.3  757.00  4922.6  756.23  4943.2  753.55
  4953.5  752.82  4971.6  750.83  4990.2  750.34  4990.4  749.84  4993.9  749.84
  4994.2  750.34  5023.0  750.68  5051.3  752.66  5079.6  753.60  5107.9  754.34
  5122.0  754.34  5136.2  755.04  5150.3  754.89  5178.6  755.33  5263.4  757.76
  5291.7  758.82  5348.3  761.73  5376.6  762.59  5415.5  764.80  5419.0  764.80
#Mann=3,-1,0
  4788.6   0.035       0  4990.2   0.035       0  4994.2   0.035       0
Bank Sta=4990.2,4994.2
Exp/Cntr=0.3,0.1

Type RM Length L Ch R = 1,3856,465,465,465
BEGIN DESCRIPTION:
Blieders Creek Tributary 3 8.0
END DESCRIPTION:
XS GIS Cut Line= 3
      2236125.01     13816474.99      2236375.00     13816325.00
      2236524.98     13816025.04
#Sta/Elev= 30
  4704.6  755.89  4762.9  755.11  4776.5  753.90  4797.9  753.71  4813.4  754.25
  4837.1  753.85  4844.5  753.98  4856.2  753.12  4865.9  753.06  4924.8  749.63
  4961.1  748.47  5008.1  745.74  5008.4  745.24  5011.9  745.24  5012.1  745.74
  5026.9  746.86  5040.9  745.84  5054.8  746.00  5071.6  747.49  5099.6  747.60
  5144.3  748.99  5183.4  751.63  5189.0  751.44  5197.4  752.22  5208.4  752.54
  5272.8  757.04  5278.4  757.02  5317.6  760.83  5321.8  760.40  5331.5  761.18
#Mann=7,-1,0
  4704.6   0.035       0  4837.1    0.07       0  4924.8   0.035       0
  5008.1   0.035       0  5012.1   0.035       0  5208.4    0.12       0
  5321.8    0.07       0
Bank Sta=5008.1,5012.1
Exp/Cntr=0.3,0.1

Type RM Length L Ch R = 1,3391,234,234,234
BEGIN DESCRIPTION:
Blieders Creek Tributary 3 7.0
END DESCRIPTION:
XS GIS Cut Line= 3
      2236775.00     13816524.99      2236825.00     13816375.00
      2236575.01     13816075.01
#Sta/Elev= 30
  4841.9  748.10  4873.5  747.66  4915.7  746.22  4947.3  743.86  4995.4  738.25
  4995.6  737.75  4999.1  737.75  4999.4  738.25  5003.3  738.25  5007.2  739.48
  5021.5  740.55  5028.0  740.38  5035.8  741.65  5043.4  741.73  5050.1  742.51
  5056.6  742.24  5064.4  743.72  5085.3  744.63  5177.7  745.89  5220.6  747.79
  5234.3  747.95  5270.1  750.45  5284.4  750.96  5290.9  750.67  5319.6  753.14
  5326.1  753.07  5362.5  756.13  5369.0  756.21  5376.8  757.40  5390.5  757.79
#Mann=4,-1,0
  4841.9   0.035       0  4995.4   0.035       0  4999.4   0.035       0
  5043.4    0.12       0
Bank Sta=4995.4,4999.4
Exp/Cntr=0.3,0.1

Type RM Length L Ch R = 1,3157,245,245,245
BEGIN DESCRIPTION:
X18294
END DESCRIPTION:
XS GIS Cut Line= 3
      2237058.25     13816540.27      2237068.67     13816384.07
      2236888.15     13816029.98
#Sta/Elev= 30
  4804.4  743.38  4827.7  743.72  4889.9  743.86  4909.9  743.01  4919.9  742.90
  4940.0  742.10  4950.0  741.45  4958.0  740.44  4963.2  740.44  4971.1  738.88
  4998.6  737.10  4998.9  736.60  5002.4  736.60  5002.6  737.10  5016.0  737.65
  5028.5  739.01  5038.5  739.07  5050.7  739.92  5072.9  740.74  5112.2  741.42
  5139.6  742.06  5184.4  742.04  5223.0  742.97  5239.6  742.38  5261.8  742.42
  5296.6  743.21  5306.3  743.00  5319.1  743.49  5328.5  743.40  5358.4  743.87
#Mann=4,-1,0
  4804.4   0.035       0  4998.6   0.035       0  5002.6   0.035       0
  5112.2    0.12       0
Bank Sta=4998.6,5002.6
Exp/Cntr=0.3,0.1

Type RM Length L Ch R = 1,2912,297,297,297
BEGIN DESCRIPTION:
Blieders Creek Tributary 3 6.0
END DESCRIPTION:
XS GIS Cut Line= 3
      2237225.02     13816374.96      2237275.00     13816275.00
      2237075.00     13816075.00
#Sta/Elev= 30
  4884.0  743.87  4886.8  743.87  4892.3  743.48  4897.9  743.41  4915.5  741.99
  4920.3  741.89  4928.7  741.03  4937.1  739.87  4942.7  739.79  4959.4  738.36
  4965.0  738.80  4973.4  738.00  4981.8  735.40  4987.4  735.67  4993.0  733.41
  4999.3  733.41  5007.9  732.06  5008.2  731.56  5011.7  731.56  5011.9  732.06
  5024.0  732.35  5066.5  735.08  5080.6  736.54  5094.8  737.54  5108.9  738.79
  5123.0  739.80  5137.2  740.38  5250.3  741.70  5264.5  742.10  5278.6  741.99
#Mann=4,-1,0
  4884.0   0.035       0  4915.5    0.12       0  5007.9    0.05       0
  5011.9    0.12       0
Bank Sta=5007.9,5011.9
Exp/Cntr=0.3,0.1

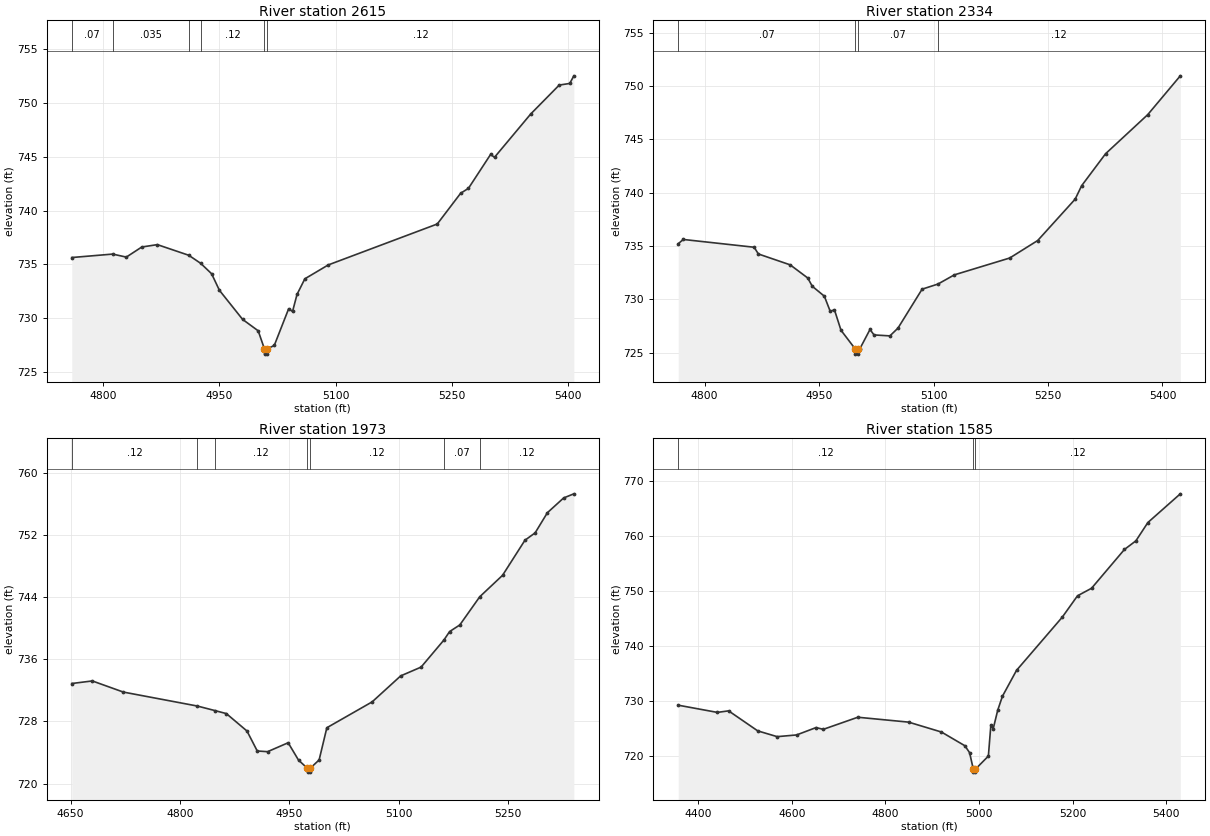
Type RM Length L Ch R = 1,2615,281,281,281
BEGIN DESCRIPTION:
X18293
END DESCRIPTION:
XS GIS Cut Line= 3
      2237495.75     13816415.32      2237513.11     13816158.37
      2237468.00     13815769.71
#Sta/Elev= 30
  4759.1  735.63  4811.9  735.95  4829.6  735.67  4849.6  736.61  4869.7  736.83
  4910.3  735.84  4925.7  735.09  4939.8  734.12  4949.9  732.58  4979.9  729.87
  5000.0  728.81  5008.0  727.14  5008.2  726.64  5011.7  726.64  5012.0  727.14
  5020.8  727.45  5039.4  730.87  5044.4  730.61  5050.2  732.20  5060.3  733.65
  5090.5  734.94  5231.4  738.75  5261.6  741.61  5271.7  742.07  5300.3  745.22
  5305.4  744.96  5352.2  748.99  5389.0  751.68  5402.6  751.83  5407.9  752.54
#Mann=6,-1,0
  4759.1    0.07       0  4811.9   0.035       0  4910.3    0.07       0
  4925.7    0.12       0  5008.0    0.05       0  5012.0    0.12       0
Bank Sta=5008,5012
Exp/Cntr=0.3,0.1

Type RM Length L Ch R = 1,2334,361,361,361
BEGIN DESCRIPTION:
Blieders Creek Tributary 3 5.0
END DESCRIPTION:
XS GIS Cut Line= 3
      2237700.61     13816391.02      2237794.36     13816172.26
      2237659.48     13815774.52
#Sta/Elev= 30
  4765.4  735.21  4772.0  735.61  4864.9  734.88  4870.4  734.25  4912.1  733.23
  4935.1  732.00  4941.1  731.22  4956.9  730.29  4964.6  728.87  4970.1  729.02
  4978.7  727.10  4997.2  725.36  4997.4  724.86  5000.9  724.86  5001.2  725.36
  5003.4  725.36  5016.7  727.17  5022.0  726.66  5042.8  726.57  5053.4  727.30
  5085.0  730.95  5105.8  731.43  5127.2  732.29  5199.8  733.87  5236.5  735.51
  5285.6  739.39  5294.1  740.65  5325.5  743.65  5380.7  747.31  5423.4  750.95
#Mann=4,-1,0
  4765.4    0.07       0  4997.2    0.05       0  5001.2    0.07       0
  5105.8    0.12       0
Bank Sta=4997.2,5001.2
Exp/Cntr=0.3,0.1

Type RM Length L Ch R = 1,1973,388,388,388
BEGIN DESCRIPTION:
Blieders Creek Tributary 3 4.0
END DESCRIPTION:
XS GIS Cut Line= 3
      2237875.03     13816424.97      2238125.00     13816175.00
      2238274.99     13815875.02
#Sta/Elev= 30
  4651.5  732.88  4679.7  733.21  4722.2  731.78  4823.9  729.98  4847.8  729.40
  4863.6  729.01  4891.9  726.77  4906.0  724.20  4920.2  724.11  4948.4  725.26
  4962.6  723.03  4974.7  721.98  4975.0  721.48  4978.5  721.48  4978.7  721.98
  4990.9  723.05  5001.5  727.19  5063.7  730.52  5102.8  733.86  5130.8  734.99
  5162.1  738.47  5169.9  739.56  5183.9  740.41  5211.3  744.04  5242.6  746.80
  5273.3  751.31  5287.3  752.26  5304.1  754.85  5326.4  756.75  5340.4  757.28
#Mann=7,-1,0
  4651.5    0.12       0  4823.9    0.07       0  4847.8    0.12       0
  4974.7    0.05       0  4978.7    0.12       0  5162.1    0.07       0
  5211.3    0.12       0
Bank Sta=4974.7,4978.7
Exp/Cntr=0.3,0.1

Type RM Length L Ch R = 1,1585,0,0,0
BEGIN DESCRIPTION:
X18292
END DESCRIPTION:
XS GIS Cut Line= 3
      2238051.35     13816602.80      2238464.50     13816488.23
      2238506.17     13815845.82
#Sta/Elev= 30
  4357.6  729.19  4441.1  727.88  4465.2  728.16  4527.4  724.52  4568.9  723.47
  4610.4  723.78  4652.0  725.12  4667.5  724.80  4741.2  727.00  4849.7  726.11
  4919.9  724.31  4970.0  721.81  4980.0  720.55  4988.0  717.52  4988.3  717.02
  4991.8  717.02  4992.0  717.52  5020.1  719.94  5025.4  725.55  5030.4  724.89
  5040.1  728.29  5050.1  730.81  5080.2  735.52  5177.8  745.18  5210.5  749.08
  5240.5  750.45  5310.7  757.50  5335.2  759.07  5360.8  762.40  5430.1  767.62
#Mann=3,-1,0
  4357.6    0.12       0  4988.0    0.05       0  4992.0    0.12       0
Bank Sta=4988,4992
Exp/Cntr=0.3,0.1

Chan Stop Cuts=-1