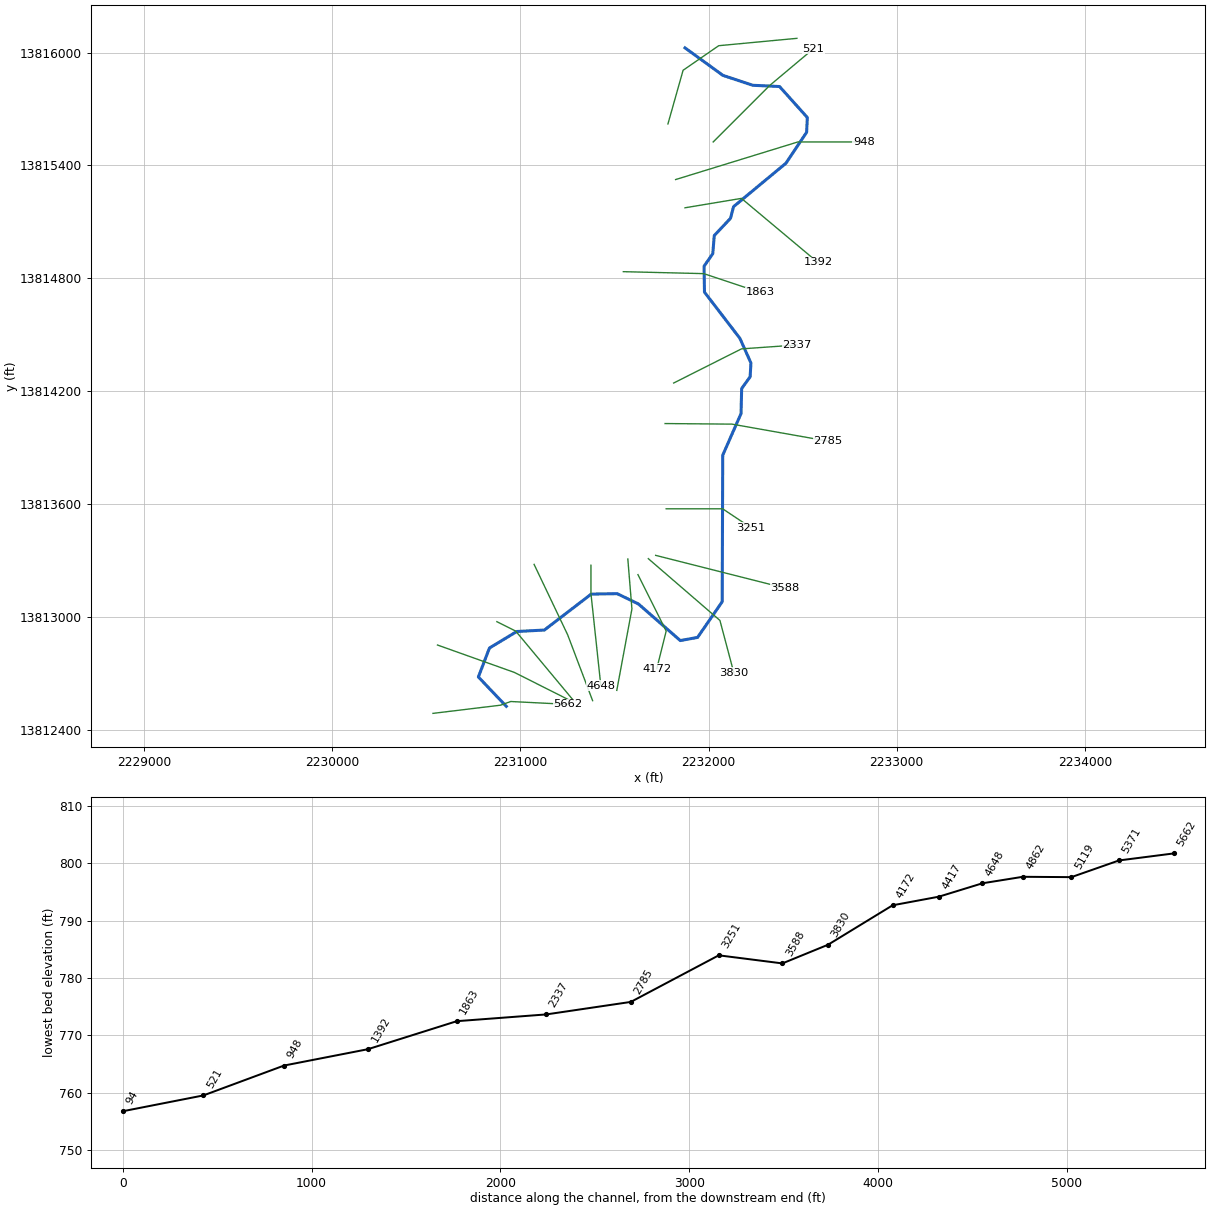
--- Blieders Creek Tributary 6.prj (project) ---

Proj Title=Blieders Creek Tributary 6 Base Level Engineering
Current Plan=p01
Default Exp/Contr=0.3,0.1
English Units
Geom File=g01
Flow File=f01
Plan File=p01
BEGIN DESCRIPTION:
Blieders Creek Tributary 6
END DESCRIPTION:

--- Blieders Creek Tributary 6.p01 (plan) ---

Plan Title=Multiple Run
Short Identifier=Multiple
Geom File=g01
Flow File=f01
Subcritical Flow
K Sum by GR= 0
Std Step Tol= 0.01
Critical Tol= 0.01
Num of Std Step Trials= 20
Max Error Tol= 0.3
Flow Tol Ratio= 0.001
Split Flow NTrial= 30
Split Flow Tol= 0.02
Split Flow Ratio= 0.02
Log Output Level= 0
Friction Slope Method= 1
Unsteady Friction Slope Method= 2
Unsteady Bridges Friction Slope Method= 1
Parabolic Critical Depth
Global Vel Dist=  1 , 1 , 1
Global Log Level= 0
CheckData=True
Encroach Param= -1, 0, 0, 0
BEGIN DESCRIPTION:
Multiple Run
END DESCRIPTION:

--- Blieders Creek Tributary 6.f01 (steady flow) ---

Flow Title=Multiple
Number of Profiles=7
Profile Names=10-year,25-year,50-year,1pct_min,100-year,1pct_plu,500-year
River Rch & RM= Blieders Creek T,Reach-1,5662
     905    1496    2043    1351    2696    5378    4643
River Rch & RM= Blieders Creek T,Reach-1,3588
    1143    1913    2634    1753    3498    6980    6111
Boundary for River Rch & Prof#=Blieders Creek T,Reach-1,1
Up Type=0
Dn Type=3
Dn Slope=0.005
Boundary for River Rch & Prof#=Blieders Creek T,Reach-1,2
Up Type=0
Dn Type=3
Dn Slope=0.005
Boundary for River Rch & Prof#=Blieders Creek T,Reach-1,3
Up Type=0
Dn Type=3
Dn Slope=0.005
Boundary for River Rch & Prof#=Blieders Creek T,Reach-1,4
Up Type=0
Dn Type=3
Dn Slope=0.005
Boundary for River Rch & Prof#=Blieders Creek T,Reach-1,5
Up Type=0
Dn Type=3
Dn Slope=0.005
Boundary for River Rch & Prof#=Blieders Creek T,Reach-1,6
Up Type=0
Dn Type=3
Dn Slope=0.005
Boundary for River Rch & Prof#=Blieders Creek T,Reach-1,7
Up Type=0
Dn Type=3
Dn Slope=0.005

--- Blieders Creek Tributary 6.g01 (geometry) ---

Geom Title=Existing Conditions

River Reach=Blieders Creek T,Reach-1
Reach XY= 30
      2230925.00     13812525.00      2230776.61     13812681.03
      2230835.63     13812835.00      2230980.93     13812922.75
      2231127.44     13812930.48      2231376.47     13813121.46
      2231514.50     13813123.81      2231627.30     13813069.17
      2231849.97     13812874.49      2231941.79     13812891.39
      2232072.76     13813080.93      2232075.52     13813859.78
      2232172.73     13814080.94      2232176.23     13814214.49
      2232221.30     13814276.60      2232225.41     13814350.00
      2232166.84     13814481.05      2231978.54     13814726.47
      2231976.20     13814864.49      2232022.64     13814930.98
      2232030.54     13815027.42      2232116.82     13815118.96
      2232133.16     13815181.05      2232411.38     13815411.76
      2232521.53     13815576.50      2232525.22     13815654.95
      2232377.45     13815819.53      2232235.51     13815826.23
      2232076.58     13815878.82      2231875.00     13816025.00

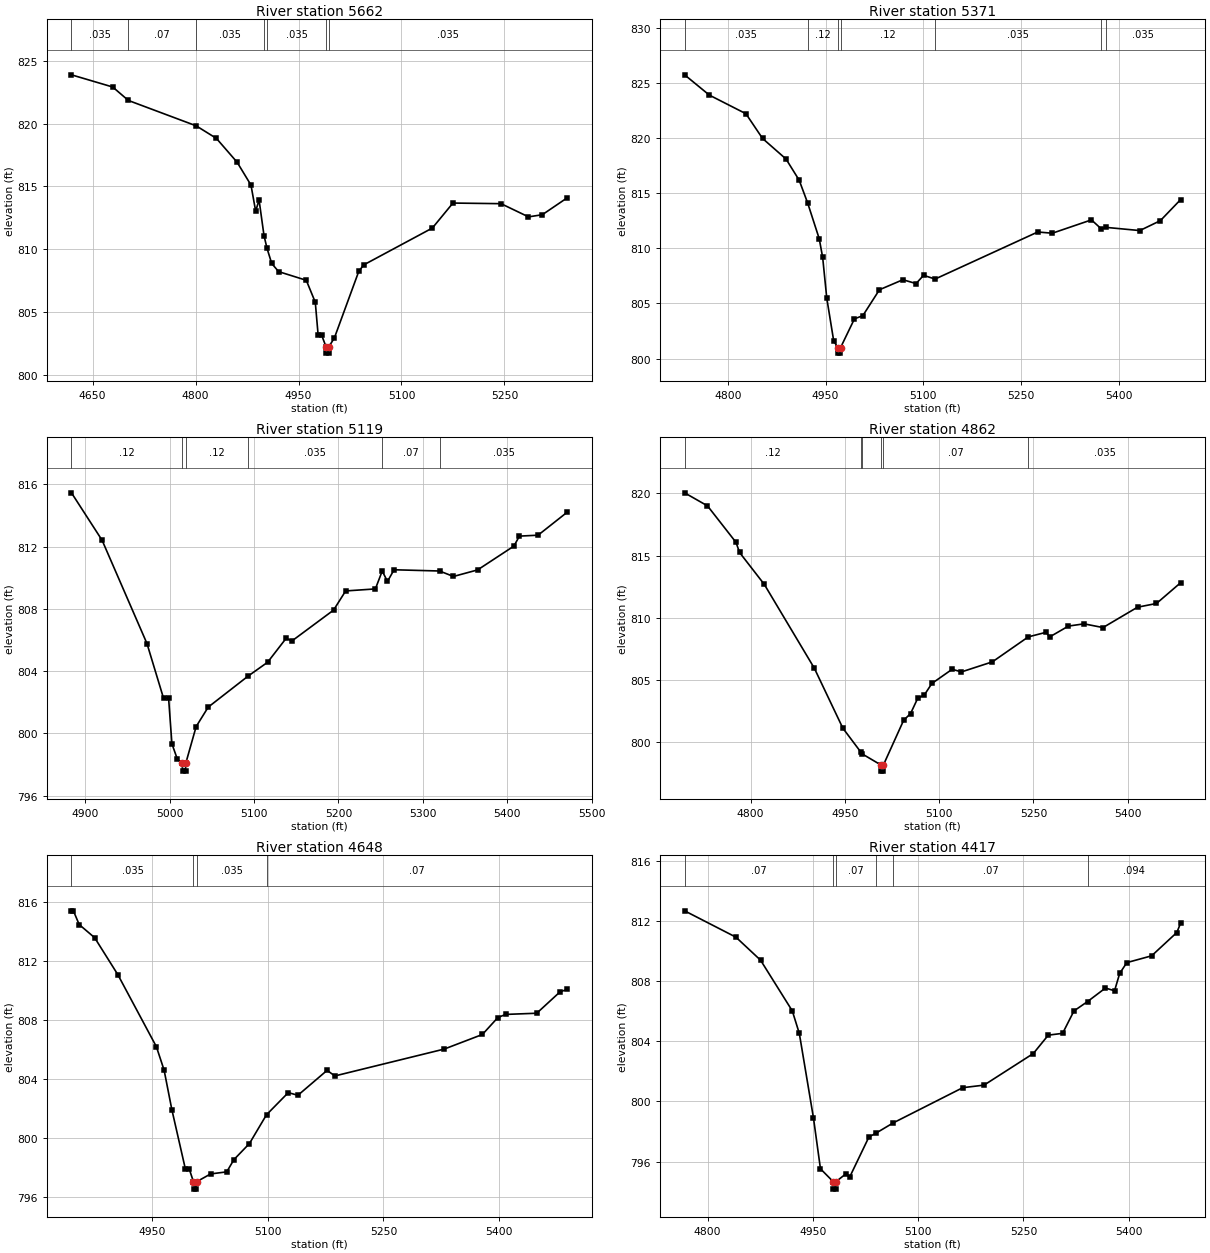
Type RM Length L Ch R = 1,5662,291,291,291
BEGIN DESCRIPTION:
X18302
END DESCRIPTION:
XS GIS Cut Line= 4
      2230535.32     13812487.49      2230894.34     13812531.01
      2230948.74     13812550.59      2231251.70     13812535.44
#Sta/Elev= 30
  4619.1  823.88  4679.2  822.91  4702.0  821.84  4800.8  819.82  4830.3  818.82
  4860.5  816.92  4880.7  815.10  4887.5  813.03  4892.5  813.91  4899.7  811.07
  4904.1  810.06  4910.9  808.86  4921.0  808.21  4961.3  807.52  4974.4  805.77
  4978.6  803.13  4983.8  803.13  4990.1  802.22  4990.3  801.72  4993.8  801.72
  4994.1  802.22  5002.3  802.94  5037.7  808.22  5044.8  808.74  5145.0  811.68
  5175.0  813.67  5245.1  813.62  5285.1  812.57  5305.2  812.74  5341.9  814.10
#Mann=7,-1,0
  4619.1   0.035       0  4702.0    0.07       0  4800.8   0.035       0
  4899.7    0.12       0  4904.1   0.035       0  4990.1   0.035       0
  4994.1   0.035       0
Bank Sta=4990.1,4994.1
Exp/Cntr=0.3,0.1

Type RM Length L Ch R = 1,5371,252,252,252
BEGIN DESCRIPTION:
X18301
END DESCRIPTION:
XS GIS Cut Line= 3
      2230559.24     13812850.88      2230968.32     13812705.09
      2231261.00     13812557.67
#Sta/Elev= 30
  4733.4  825.74  4771.4  823.90  4827.6  822.21  4853.1  819.97  4889.2  818.10
  4909.4  816.18  4922.5  814.10  4940.2  810.87  4945.5  809.17  4951.8  805.47
  4962.5  801.58  4969.0  800.99  4969.3  800.49  4972.8  800.49  4973.0  800.99
  4994.3  803.60  5007.2  803.89  5032.7  806.24  5068.8  807.15  5089.0  806.80
  5100.5  807.55  5118.2  807.21  5275.9  811.48  5298.3  811.37  5358.4  812.58
  5373.4  811.77  5380.7  811.90  5432.7  811.61  5464.3  812.51  5495.4  814.42
#Mann=7,-1,0
  4733.4   0.035       0  4922.5    0.12       0  4969.0    0.05       0
  4973.0    0.12       0  5118.2   0.035       0  5373.4    0.07       0
  5380.7   0.035       0
Bank Sta=4969,4973
Exp/Cntr=0.3,0.1

Type RM Length L Ch R = 1,5119,257,257,257
BEGIN DESCRIPTION:
Blieders Creek Tributary 6 11.0
END DESCRIPTION:
XS GIS Cut Line= 3
      2230875.04     13812974.98      2230975.00     13812925.00
      2231279.22     13812559.63
#Sta/Elev= 30
  4883.9  815.45  4920.2  812.40  4973.3  805.77  4992.9  802.26  4998.9  802.26
  5002.8  799.34  5009.3  798.34  5015.1  798.08  5015.4  797.58  5018.9  797.58
  5019.2  798.08  5031.5  800.44  5045.8  801.69  5093.2  803.69  5116.1  804.57
  5138.2  806.12  5144.7  805.93  5194.2  807.92  5208.5  809.15  5243.7  809.28
  5251.8  810.43  5258.0  809.76  5265.8  810.51  5319.7  810.43  5336.1  810.08
  5364.7  810.50  5407.7  812.03  5414.2  812.67  5436.3  812.73  5471.1  814.22
#Mann=6,-1,0
  4883.9    0.12       0  5015.1    0.05       0  5019.2    0.12       0
  5093.2   0.035       0  5251.8    0.07       0  5319.7   0.035       0
Bank Sta=5015.1,5019.2
Exp/Cntr=0.3,0.1

Type RM Length L Ch R = 1,4862,214,214,214
BEGIN DESCRIPTION:
X18300
END DESCRIPTION:
XS GIS Cut Line= 3
      2231072.76     13813279.59      2231251.21     13812905.28
      2231383.94     13812554.95
#Sta/Elev= 30
  4695.0  820.05  4731.4  819.00  4776.8  816.06  4782.4  815.25  4821.9  812.67
  4901.4  805.93  4946.8  801.10  4975.0  799.20  4977.8  799.02  5007.3  798.14
  5007.5  797.64  5011.1  797.64  5011.4  798.14  5043.5  801.73  5054.6  802.28
  5065.8  803.49  5076.7  803.79  5088.5  804.70  5120.7  805.84  5135.6  805.63
  5184.8  806.44  5241.9  808.45  5270.3  808.82  5275.7  808.44  5305.8  809.32
  5330.6  809.50  5360.8  809.20  5415.7  810.84  5445.9  811.14  5484.3  812.81
#Mann=6,-1,0
  4695.0    0.12       0  4975.0   0.035       0  4977.8    0.07       0
  5007.3    0.05       0  5011.4    0.07       0  5241.9   0.035       0
Bank Sta=5007.3,5011.4
Exp/Cntr=0.3,0.1

Type RM Length L Ch R = 1,4648,231,231,231
BEGIN DESCRIPTION:
Blieders Creek Tributary 6 10.0
END DESCRIPTION:
XS GIS Cut Line= 3
      2231375.00     13813275.03      2231375.00     13813125.00
      2231427.47     13812635.43
#Sta/Elev= 30
  4845.9  815.37  4848.4  815.37  4855.9  814.44  4875.9  813.55  4905.9  811.05
  4955.9  806.16  4965.9  804.57  4975.9  801.90  4993.4  797.88  4998.4  797.88
  5003.9  797.01  5004.2  796.51  5007.8  796.51  5008.0  797.01  5026.1  797.54
  5047.0  797.68  5056.3  798.51  5076.4  799.60  5098.5  801.55  5126.7  803.05
  5139.2  802.87  5177.0  804.56  5187.0  804.18  5328.6  806.00  5378.1  806.99
  5398.2  808.14  5408.3  808.35  5448.5  808.43  5478.7  809.88  5488.3  810.05
#Mann=4,-1,0
  4845.9   0.035       0  5003.9   0.035       0  5008.0   0.035       0
  5098.5    0.07       0
Bank Sta=5003.9,5008
Exp/Cntr=0.3,0.1

Type RM Length L Ch R = 1,4417,245,245,245
BEGIN DESCRIPTION:
X18303
END DESCRIPTION:
XS GIS Cut Line= 3
      2231571.08     13813307.89      2231592.84     13813042.37
      2231512.40     13812609.69
#Sta/Elev= 30
  4767.4  812.66  4840.5  810.91  4875.6  809.38  4920.8  806.01  4930.8  804.51
  4950.9  798.91  4960.9  795.52  4979.0  794.67  4979.2  794.17  4982.8  794.17
  4983.1  794.67  4997.5  795.20  5002.5  794.97  5030.0  797.64  5039.3  797.87
  5064.5  798.57  5163.6  800.91  5193.9  801.08  5264.1  803.18  5285.4  804.40
  5305.8  804.52  5322.0  806.01  5341.3  806.63  5366.8  807.53  5379.8  807.35
  5387.1  808.50  5397.3  809.22  5432.6  809.67  5468.5  811.22  5473.9  811.84
#Mann=6,-1,0
  4767.4    0.07       0  4979.0    0.05       0  4983.1    0.07       0
  5039.3   0.035       0  5064.5    0.07       0  5341.3   0.094       0
Bank Sta=4979,4983.1
Exp/Cntr=0.3,0.1

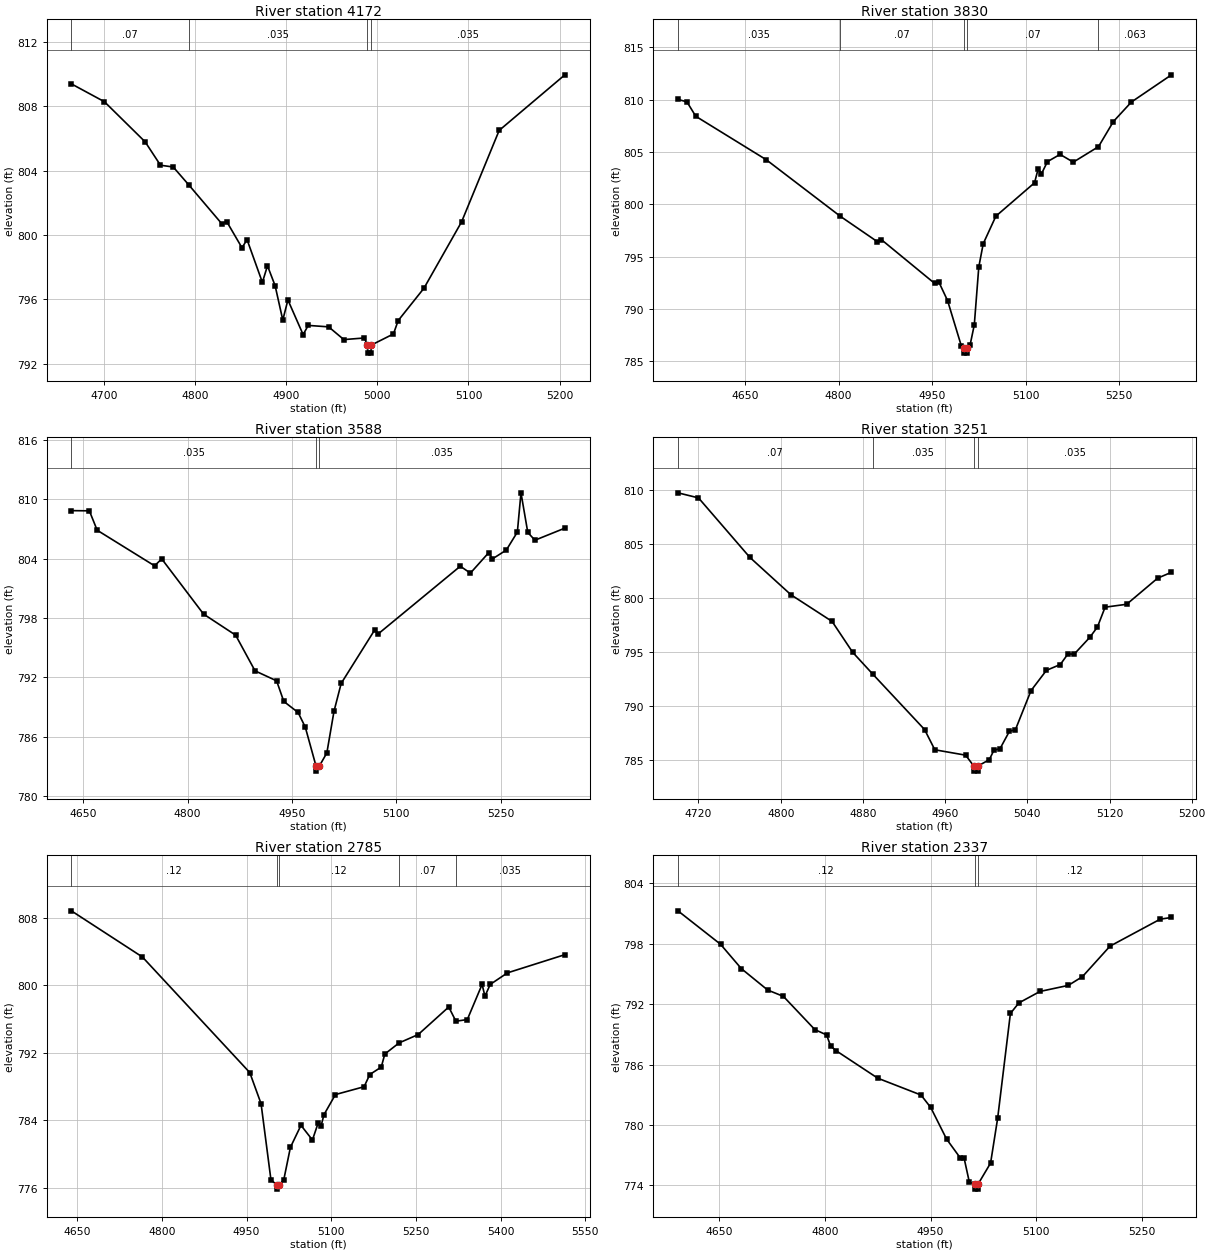
Type RM Length L Ch R = 1,4172,342,342,342
BEGIN DESCRIPTION:
Blieders Creek Tributary 6 9.0
END DESCRIPTION:
XS GIS Cut Line= 3
      2231625.01     13813224.98      2231775.00     13812925.00
      2231725.01     13812725.04
#Sta/Elev= 30
  4664.3  809.38  4700.6  808.27  4745.3  805.78  4762.1  804.33  4776.1  804.22
  4793.6  803.08  4829.2  800.71  4834.8  800.83  4851.5  799.21  4857.1  799.71
  4873.9  797.06  4879.5  798.09  4887.9  796.85  4896.3  794.72  4901.9  795.97
  4918.6  793.82  4924.2  794.39  4946.6  794.30  4963.3  793.51  4985.7  793.61
  4989.2  793.17  4989.5  792.67  4993.1  792.67  4993.4  793.17  5017.7  793.86
  5022.9  794.69  5051.2  796.70  5092.5  800.82  5133.7  806.49  5205.8  809.94
#Mann=4,-1,0
  4664.3    0.07       0  4793.6   0.035       0  4989.2   0.035       0
  4993.4   0.035       0
Bank Sta=4989.2,4993.4
Exp/Cntr=0.3,0.1

Type RM Length L Ch R = 1,3830,242,242,242
BEGIN DESCRIPTION:
Blieders Creek Tributary 6 8.0
END DESCRIPTION:
XS GIS Cut Line= 3
      2231679.87     13813310.03      2232060.69     13812981.44
      2232134.68     13812702.89
#Sta/Elev= 30
  4542.5  810.02  4556.9  809.79  4571.1  808.41  4684.1  804.26  4802.8  798.86
  4861.8  796.45  4868.4  796.64  4954.0  792.45  4960.6  792.60  4974.8  790.80
  4996.8  786.48  5001.3  786.29  5001.6  785.79  5005.2  785.79  5005.5  786.29
  5011.0  786.61  5017.6  788.49  5024.8  794.02  5031.9  796.24  5052.2  798.87
  5114.2  802.06  5120.1  803.42  5125.2  802.91  5134.9  804.08  5155.1  804.77
  5176.3  804.03  5216.7  805.51  5240.6  807.91  5269.4  809.77  5333.7  812.37
#Mann=5,-1,0
  4542.5   0.035       0  4802.8    0.07       0  5001.3    0.05       0
  5005.5    0.07       0  5216.7   0.063       0
Bank Sta=5001.3,5005.5
Exp/Cntr=0.3,0.1

Type RM Length L Ch R = 1,3588,337,337,337
BEGIN DESCRIPTION:
X18299
END DESCRIPTION:
XS GIS Cut Line= 2
      2231719.05     13813327.43      2232406.66     13813153.35
#Sta/Elev= 30
  4632.8  808.87  4658.7  808.85  4669.9  806.89  4752.4  803.29  4762.7  803.99
  4822.8  798.41  4868.9  796.28  4896.8  792.67  4927.8  791.66  4938.1  789.58
  4958.7  788.46  4969.0  786.98  4984.5  783.03  4984.8  782.53  4989.1  783.03
  5000.0  784.37  5010.3  788.59  5020.6  791.40  5068.8  796.81  5073.9  796.41
  5191.8  803.25  5206.3  802.55  5232.8  804.63  5238.0  803.99  5257.9  804.88
  5273.8  806.70  5279.0  810.67  5288.8  806.66  5299.1  805.88  5342.1  807.10
#Mann=3,-1,0
  4632.8   0.035       0  4984.5   0.035       0  4989.1   0.035       0
Bank Sta=4984.5,4989.1
Exp/Cntr=0.3,0.1

Type RM Length L Ch R = 1,3251,466,466,466
BEGIN DESCRIPTION:
Blieders Creek Tributary 6 7.0
END DESCRIPTION:
XS GIS Cut Line= 3
      2231775.00     13813575.00      2232075.00     13813575.00
      2232225.02     13813474.99
#Sta/Elev= 30
  4700.0  809.76  4720.0  809.29  4770.0  803.77  4810.0  800.30  4850.0  797.83
  4870.0  794.97  4889.4  792.96  4940.0  787.80  4950.0  785.92  4980.0  785.42
  4987.7  784.44  4988.0  783.94  4992.0  783.94  4992.4  784.44  5003.0  785.00
  5007.5  785.88  5013.5  786.03  5022.5  787.62  5028.5  787.80  5043.6  791.41
  5058.6  793.29  5072.1  793.83  5079.6  794.82  5085.6  794.79  5100.7  796.34
  5108.2  797.30  5115.7  799.15  5136.7  799.42  5166.8  801.84  5180.3  802.39
#Mann=4,-1,0
  4700.0    0.07       0  4889.4   0.035       0  4987.7   0.035       0
  4992.4   0.035       0
Bank Sta=4987.7,4992.4
Exp/Cntr=0.3,0.1

Type RM Length L Ch R = 1,2785,448,448,448
BEGIN DESCRIPTION:
Blieders Creek Tributary 6 6.0
END DESCRIPTION:
XS GIS Cut Line= 3
      2231769.06     13814028.11      2232125.00     13814025.00
      2232635.18     13813934.54
#Sta/Elev= 30
  4639.7  808.83  4765.6  803.35  4955.7  789.64  4975.7  785.95  4993.2  776.92
  5003.5  776.31  5003.8  775.81  5008.2  776.31  5016.0  776.94  5027.7  780.77
  5046.4  783.38  5066.7  781.64  5076.7  783.63  5081.8  783.25  5087.1  784.64
  5107.4  787.03  5158.2  787.96  5168.3  789.41  5188.6  790.29  5194.9  791.84
  5220.2  793.16  5254.0  794.15  5308.1  797.42  5320.8  795.73  5341.0  795.93
  5367.2  800.10  5372.2  798.70  5381.6  800.10  5412.1  801.47  5513.8  803.63
#Mann=5,-1,0
  4639.7    0.12       0  5003.5    0.05       0  5008.2    0.12       0
  5220.2    0.07       0  5320.8   0.035       0
Bank Sta=5003.5,5008.2
Exp/Cntr=0.3,0.1

Type RM Length L Ch R = 1,2337,474,474,474
BEGIN DESCRIPTION:
Blieders Creek Tributary 6 5.0
END DESCRIPTION:
XS GIS Cut Line= 3
      2231814.75     13814243.52      2232175.00     13814425.00
      2232470.99     13814445.84
#Sta/Elev= 30
  4591.7  801.28  4652.1  797.96  4681.6  795.54  4719.0  793.41  4741.3  792.78
  4785.9  789.48  4802.6  788.95  4808.2  787.86  4815.9  787.39  4875.2  784.65
  4936.5  782.98  4950.3  781.74  4972.7  778.61  4992.3  776.72  4997.6  776.72
  5005.1  774.31  5012.7  774.13  5013.1  773.63  5017.2  773.63  5017.5  774.13
  5035.2  776.22  5045.2  780.66  5063.3  791.08  5075.3  792.13  5105.3  793.27
  5145.4  793.87  5165.5  794.74  5204.6  797.77  5275.8  800.45  5291.8  800.62
#Mann=3,-1,0
  4591.7    0.12       0  5012.7    0.05       0  5017.5    0.12       0
Bank Sta=5012.7,5017.5
Exp/Cntr=0.3,0.1

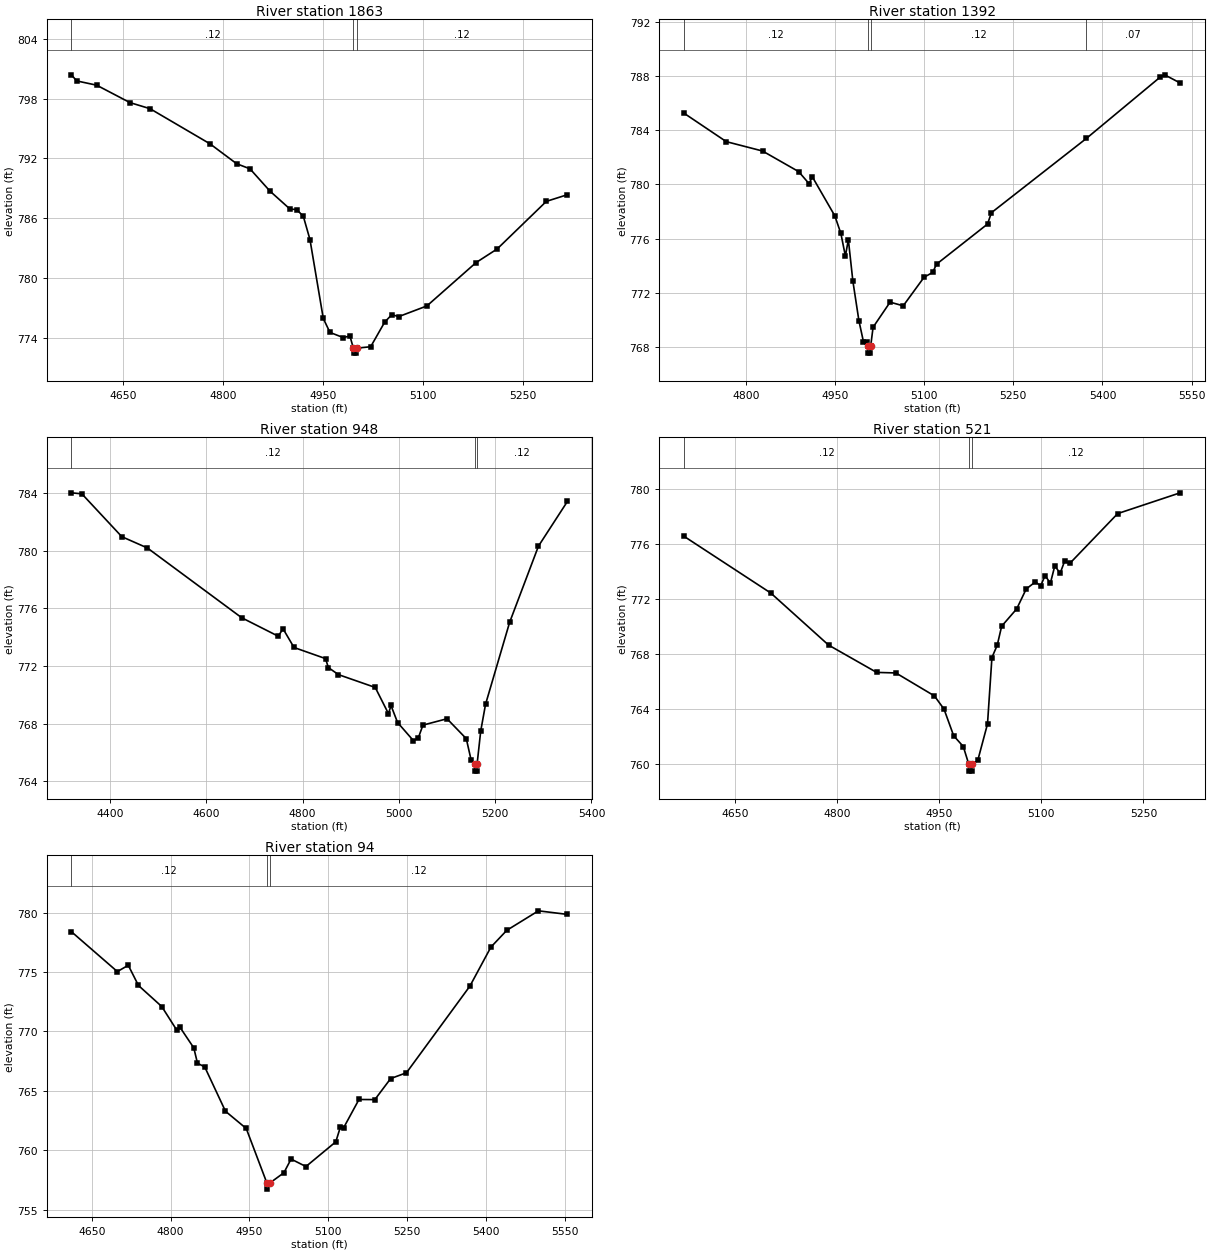
Type RM Length L Ch R = 1,1863,471,471,471
BEGIN DESCRIPTION:
Blieders Creek Tributary 6 4.0
END DESCRIPTION:
XS GIS Cut Line= 3
      2231547.18     13814835.42      2231975.00     13814825.00
      2232275.02     13814724.99
#Sta/Elev= 30
  4572.5  800.40  4580.3  799.79  4610.3  799.36  4660.3  797.61  4690.4  797.00
  4780.4  793.47  4820.4  791.47  4840.4  790.96  4870.4  788.72  4900.4  786.92
  4910.4  786.87  4920.4  786.20  4930.4  783.86  4950.4  775.93  4960.4  774.53
  4980.4  774.01  4990.4  774.17  4995.5  772.95  4995.8  772.45  5000.0  772.45
  5000.4  772.95  5021.5  773.09  5042.6  775.57  5053.2  776.31  5063.7  776.12
  5105.9  777.19  5179.6  781.54  5211.3  782.91  5285.1  787.69  5316.7  788.36
#Mann=3,-1,0
  4572.5    0.12       0  4995.5    0.05       0  5000.4    0.12       0
Bank Sta=4995.5,5000.4
Exp/Cntr=0.3,0.1

Type RM Length L Ch R = 1,1392,444,444,444
BEGIN DESCRIPTION:
Blieders Creek Tributary 6 3.0
END DESCRIPTION:
XS GIS Cut Line= 3
      2231875.02     13815175.00      2232175.00     13815225.00
      2232581.43     13814884.55
#Sta/Elev= 30
  4696.3  785.25  4767.2  783.16  4828.1  782.47  4888.9  780.95  4906.6  780.05
  4911.7  780.58  4949.7  777.69  4959.9  776.39  4967.5  774.72  4972.5  775.93
  4980.1  772.87  4990.3  769.94  4997.9  768.40  5003.7  768.40  5005.1  768.06
  5005.5  767.56  5009.7  767.56  5010.0  768.06  5014.1  769.47  5042.7  771.32
  5064.8  771.05  5099.9  773.16  5114.3  773.51  5120.8  774.12  5206.6  777.08
  5213.2  777.92  5373.0  783.40  5496.8  787.91  5504.6  788.09  5530.6  787.49
#Mann=4,-1,0
  4696.3    0.12       0  5005.1    0.05       0  5010.0    0.12       0
  5373.0    0.07       0
Bank Sta=5005.1,5010
Exp/Cntr=0.3,0.1

Type RM Length L Ch R = 1,948,427,427,427
BEGIN DESCRIPTION:
Blieders Creek Tributary 6 2.0
END DESCRIPTION:
XS GIS Cut Line= 3
      2231825.02     13815325.01      2232475.00     13815525.00
      2232825.05     13815525.00
#Sta/Elev= 30
  4319.9  784.00  4341.5  783.93  4424.5  780.96  4477.5  780.18  4673.6  775.34
  4749.5  774.06  4759.3  774.58  4782.2  773.28  4847.6  772.51  4853.5  771.89
  4874.4  771.40  4950.9  770.51  4978.4  768.69  4983.6  769.26  4997.3  768.08
  5030.0  766.83  5040.0  766.98  5050.0  767.90  5100.0  768.34  5140.0  766.96
  5150.0  765.49  5157.5  765.21  5157.9  764.71  5162.1  764.71  5162.5  765.21
  5170.0  767.49  5180.0  769.34  5230.0  775.02  5290.0  780.31  5350.0  783.40
#Mann=3,-1,0
  4319.9    0.12       0  5157.5    0.05       0  5162.5    0.12       0
Bank Sta=5157.5,5162.5
Exp/Cntr=0.3,0.1

Type RM Length L Ch R = 1,521,427,427,427
BEGIN DESCRIPTION:
Blieders Creek Tributary 6 1.0
END DESCRIPTION:
XS GIS Cut Line= 3
      2232025.01     13815525.01      2232325.00     13815825.00
      2232558.22     13816020.70
#Sta/Elev= 30
  4575.2  776.57  4702.5  772.45  4787.3  768.67  4858.0  766.68  4886.3  766.64
  4942.9  764.97  4957.0  764.01  4971.2  762.07  4985.3  761.29  4993.4  760.00
  4993.8  759.50  4998.1  759.50  4998.5  760.00  5006.6  760.28  5020.9  762.93
  5027.4  767.76  5035.2  768.66  5041.7  770.04  5063.8  771.30  5077.8  772.75
  5091.2  773.26  5099.0  772.98  5105.5  773.72  5113.3  773.17  5119.8  774.43
  5127.6  773.89  5134.1  774.75  5141.9  774.61  5212.2  778.23  5303.9  779.74
#Mann=3,-1,0
  4575.2    0.12       0  4993.4    0.05       0  4998.5    0.12       0
Bank Sta=4993.4,4998.5
Exp/Cntr=0.3,0.1

Type RM Length L Ch R = 1,94,0,0,0
BEGIN DESCRIPTION:
X18298
END DESCRIPTION:
XS GIS Cut Line= 4
      2231784.33     13815620.95      2231864.85     13815906.02
      2232054.16     13816036.59      2232469.82     13816075.76
#Sta/Elev= 30
  4611.4  778.39  4698.7  775.04  4719.5  775.57  4738.9  773.87  4783.2  772.10
  4812.0  770.10  4817.2  770.40  4844.2  768.62  4851.2  767.33  4865.0  767.02
  4904.5  763.29  4944.0  761.84  4983.4  757.24  4983.8  756.74  4988.5  757.24
  5015.7  758.12  5029.3  759.27  5057.6  758.64  5114.4  760.72  5123.2  761.97
  5129.3  761.90  5158.5  764.28  5188.7  764.27  5218.8  766.04  5248.9  766.53
  5369.5  773.81  5409.6  777.10  5439.8  778.51  5500.0  780.15  5555.1  779.85
#Mann=3,-1,0
  4611.4    0.12       0  4983.4    0.05       0  4988.5    0.12       0
Bank Sta=4983.4,4988.5
Exp/Cntr=0.3,0.1

Chan Stop Cuts=-1