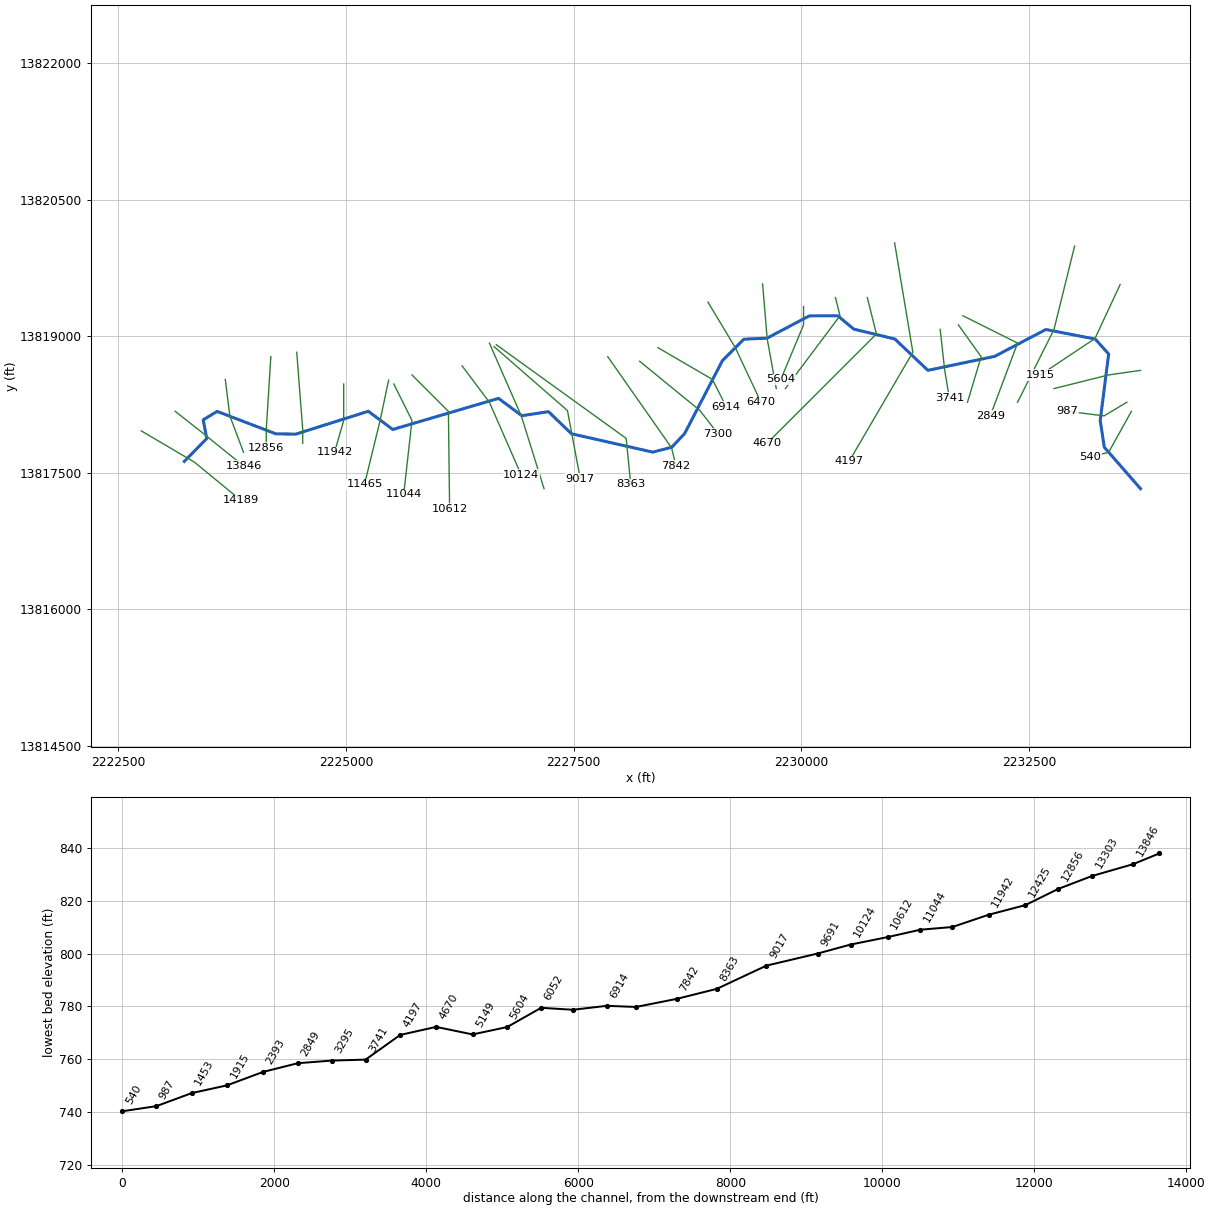
--- Blieders Creek Tributary 9.prj (project) ---

Proj Title=Blieders Creek Tributary 9 Base Level Engineering
Current Plan=p01
Default Exp/Contr=0.3,0.1
English Units
Geom File=g01
Flow File=f01
Plan File=p01
Y Axis Title=Elevation
X Axis Title(PF)=Main Channel Distance
X Axis Title(XS)=Station
BEGIN DESCRIPTION:
Blieders Creek Tributary 9
END DESCRIPTION:
DSS Export Rating Curves= 0
DSS Export Rating Curve Sorted= 0
DSS Export Volume Flow Curves= 0
DXF OffsetX= 0
DXF OffsetY= 0
DXF ScaleX= 1
DXF ScaleY= 10

--- Blieders Creek Tributary 9.p01 (plan) ---

Plan Title=Multiple Run
Short Identifier=Multiple
Geom File=g01
Flow File=f01
Subcritical Flow
K Sum by GR= 0
Std Step Tol= 0.01
Critical Tol= 0.01
Num of Std Step Trials= 20
Max Error Tol= 0.3
Flow Tol Ratio= 0.001
Split Flow NTrial= 30
Split Flow Tol= 0.02
Split Flow Ratio= 0.02
Log Output Level= 0
Friction Slope Method= 1
Unsteady Friction Slope Method= 2
Unsteady Bridges Friction Slope Method= 1
Parabolic Critical Depth
Global Vel Dist=  1 , 1 , 1
Global Log Level= 0
CheckData=True
Encroach Param= -1, 0, 0, 0
BEGIN DESCRIPTION:
Multiple Run
END DESCRIPTION:

--- Blieders Creek Tributary 9.f01 (steady flow) ---

Flow Title=Multiple
Number of Profiles=7
Profile Names=10-year,25-year,50-year,1pct_min,100-year,1pct_plu,500-year
River Rch & RM= Blieders Creek T,Reach-1,14189
    1051    1769    2446    1638    3269    6522    5777
River Rch & RM= Blieders Creek T,Reach-1,13303
    1542    2640    3692    2496    4980    9936    8972
River Rch & RM= Blieders Creek T,Reach-1,9017
    1608    2757    3859    2611    5209   10393    9398
River Rch & RM= Blieders Creek T,Reach-1,7842
    3205    5651    8059    5541   11055   22058   20612
River Rch & RM= Blieders Creek T,Reach-1,2393
    3404    6008    8575    5899   11769   23483   21967
Boundary for River Rch & Prof#=Blieders Creek T,Reach-1,1
Up Type=0
Dn Type=3
Dn Slope=0.005
Boundary for River Rch & Prof#=Blieders Creek T,Reach-1,2
Up Type=0
Dn Type=3
Dn Slope=0.005
Boundary for River Rch & Prof#=Blieders Creek T,Reach-1,3
Up Type=0
Dn Type=3
Dn Slope=0.005
Boundary for River Rch & Prof#=Blieders Creek T,Reach-1,4
Up Type=0
Dn Type=3
Dn Slope=0.005
Boundary for River Rch & Prof#=Blieders Creek T,Reach-1,5
Up Type=0
Dn Type=3
Dn Slope=0.005
Boundary for River Rch & Prof#=Blieders Creek T,Reach-1,6
Up Type=0
Dn Type=3
Dn Slope=0.005
Boundary for River Rch & Prof#=Blieders Creek T,Reach-1,7
Up Type=0
Dn Type=3
Dn Slope=0.005

--- Blieders Creek Tributary 9.g01 (geometry) ---

Geom Title=Existing Conditions
Program Version=4.10

River Reach=Blieders Creek T,Reach-1
Reach XY= 30
        2223225.       13817625.      2223471.63     13817876.28
      2223432.36     13818081.34      2223585.68     13818174.25
      2224230.93     13817927.24      2224450.09     13817924.79
      2225245.16     13818175.47      2225514.29     13817975.72
      2226675.01     13818317.47      2226930.89     13818126.96
      2227223.53     13818171.47      2227476.47     13817928.54
      2228369.17     13817726.77      2228577.48     13817780.43
      2228719.02     13817930.77      2229133.14     13818731.06
      2229368.95      13818967.5      2229623.41     13818978.82
      2230086.83     13819223.36      2230400.12      13819225.3
      2230576.46     13819078.54      2231027.44     13818969.52
      2231390.03     13818625.33      2232123.44     13818778.76
      2232685.44     13819073.94      2233227.43     13818969.48
      2233375.04     13818805.02      2233282.56       13818075.
      2233327.06     13817780.86        2233725.       13817325.

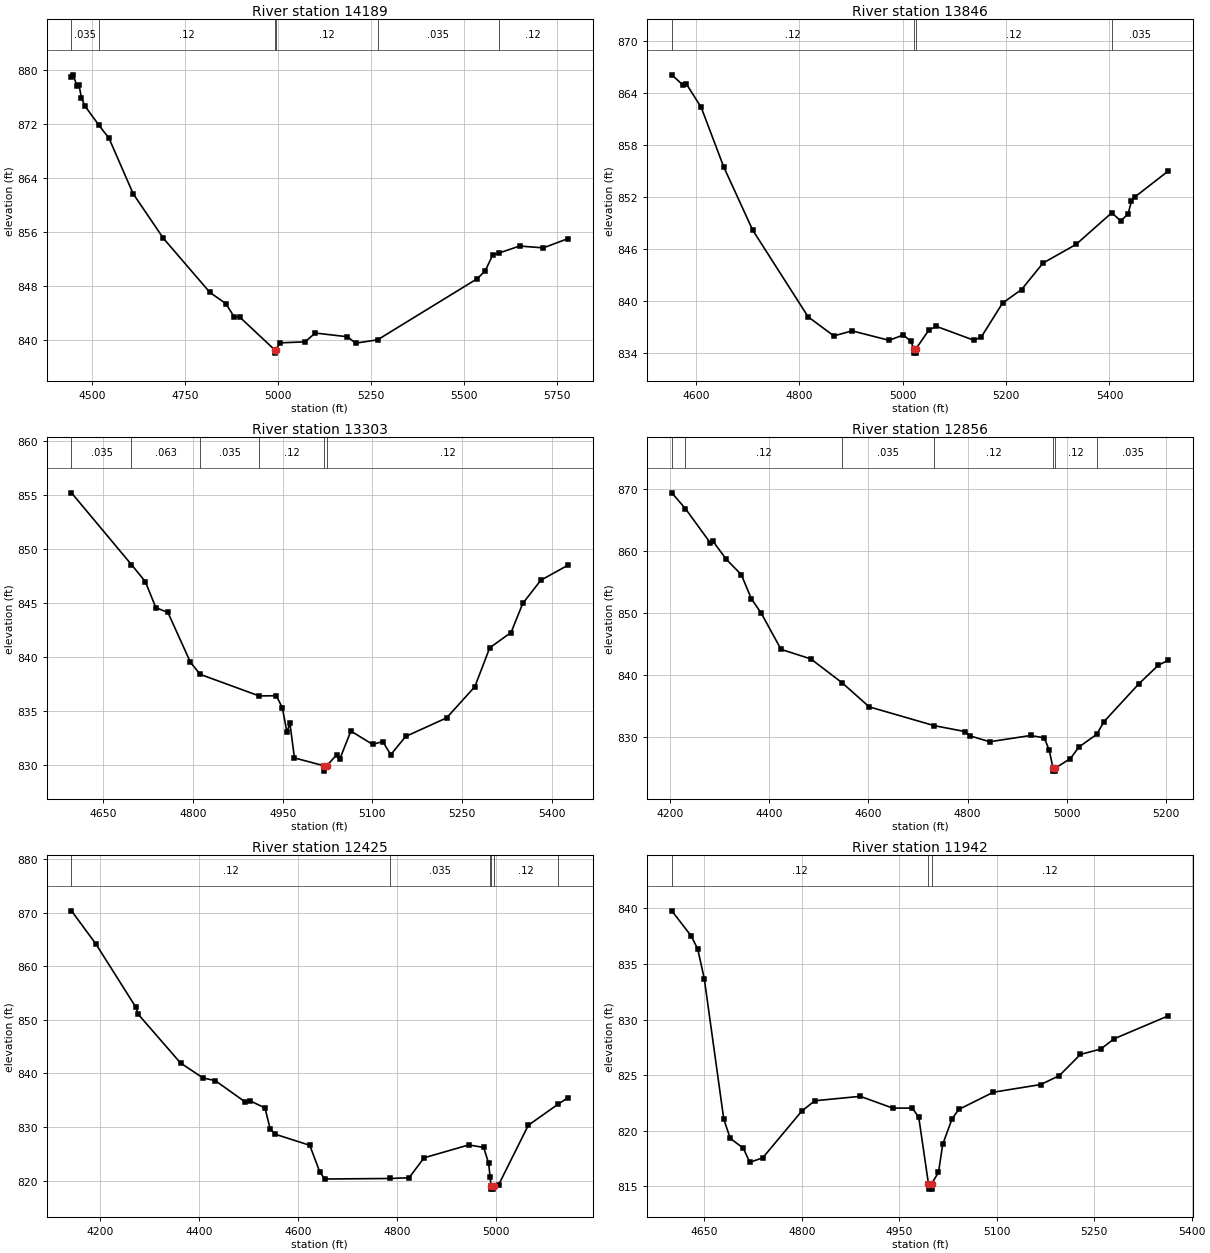
Type RM Length L Ch R = 1 ,14189   ,343,343,343
BEGIN DESCRIPTION:
X18304
END DESCRIPTION:
XS GIS Cut Line= 3
      2222752.13      13817960.3      2223335.09     13817617.14
      2223843.33      13817199.8
#Sta/Elev= 30
  4444.4  878.94  4449.3  879.27  4459.1  877.54  4464.9  877.72  4470.9  875.88
  4480.6  874.64  4518.3  871.78    4545  869.89  4610.2  861.63  4691.4  855.02
  4816.4     847  4859.3  845.34  4880.8  843.43  4896.4  843.35  4990.1   838.5
  4990.4     838  4994.1   838.5  5004.7  839.52  5072.2  839.68  5099.4  840.98
  5185.7  840.43  5207.9  839.48  5266.8  839.97  5534.8  849.04  5555.9  850.19
  5576.7  852.58  5592.5  852.83  5648.5  853.88  5712.3  853.61  5778.5  854.98
#Mann= 6 ,-1 , 0
  4444.4    .035       0  4518.3     .12       0  4990.1     .05       0
  4994.1     .12       0  5266.8    .035       0  5592.5     .12       0
Bank Sta=4990.1,4994.1
XS Rating Curve= 0 ,0
Exp/Cntr=0.3,0.1

Type RM Length L Ch R = 1 ,13846   ,543,543,543
BEGIN DESCRIPTION:
Blieders Creek Tributary 9 27.0
END DESCRIPTION:
XS GIS Cut Line= 3
      2223125.01     13818174.99      2223413.64     13817947.88
      2223875.02     13817574.98
#Sta/Elev= 30
  4553.3  866.09    4575   864.9  4581.3  865.05  4610.2  862.33  4653.6  855.48
  4709.6  848.18  4817.1  838.14  4866.8  835.94  4902.1  836.52  4973.7  835.43
  5001.3  836.05  5015.7  835.31  5021.6  834.45  5021.9  833.95  5025.5  833.95
  5025.7  834.45  5050.9  836.64  5065.3  837.04  5137.2  835.45  5151.6  835.77
  5193.2  839.73  5229.9  841.29  5271.5  844.35  5335.5  846.51  5404.5  850.16
  5421.8  849.21  5436.2  850.04  5442.6  851.53  5449.5     852  5513.8  854.98
#Mann= 4 ,-1 , 0
  4553.3     .12       0  5021.6     .05       0  5025.7     .12       0
  5404.5    .035       0
Bank Sta=5021.6,5025.7
XS Rating Curve= 0 ,0
Exp/Cntr=0.3,0.1

Type RM Length L Ch R = 1 ,13303   ,447,447,447
BEGIN DESCRIPTION:
Blieders Creek Tributary 9 26.0
END DESCRIPTION:
XS GIS Cut Line= 3
        2223675.     13818524.99        2223725.       13818125.
        2223875.       13817725.
#Sta/Elev= 30
  4596.9   855.2  4697.1  848.56  4720.3  846.99    4738  844.57  4758.1  844.13
  4795.9  839.51    4812   838.4  4910.8   836.4  4939.5  836.42  4949.6  835.29
  4957.2  833.05  4962.2  833.87  4969.8  830.66  5018.9  829.94  5019.3  829.44
  5023.9  829.94  5040.1  830.94  5045.4  830.52  5064.1  833.15  5100.6  831.91
  5117.5  832.18  5130.8  830.96  5155.8  832.65  5224.3  834.37  5271.5  837.26
  5296.4  840.86    5332  842.27  5351.6  844.96  5381.8  847.11  5427.2   848.5
#Mann= 6 ,-1 , 0
  4596.9    .035       0  4697.1    .063       0    4812    .035       0
  4910.8     .12       0  5018.9     .05       0  5023.9     .12       0
Bank Sta=5018.9,5023.9
XS Rating Curve= 0 ,0
Exp/Cntr=0.3,0.1

Type RM Length L Ch R = 1 ,12856   ,431,431,431
BEGIN DESCRIPTION:
Blieders Creek Tributary 9 25.0
END DESCRIPTION:
XS GIS Cut Line= 3
        2224175.       13818775.        2224125.       13817975.
        2224125.     13817774.96
#Sta/Elev= 30
  4203.3  869.34  4230.6  866.81    4281  861.28    4286  861.58  4313.5  858.61
  4343.6  856.16  4363.6  852.31  4383.7  849.96  4423.7  844.13  4483.8  842.59
  4546.9  838.75  4601.6  834.87  4732.9  831.84  4794.5   830.9  4804.5  830.21
  4844.6  829.25  4927.2  830.26  4954.8  829.88  4964.8  827.88  4972.3  825.02
  4972.7  824.52    4977  824.52  4977.3  825.02  5007.4  826.54  5024.9  828.42
  5060.5  830.44  5074.9  832.46  5144.9  838.53  5184.9  841.58  5204.9  842.37
#Mann= 7 ,-1 , 0
  4203.3    .035       0  4230.6     .12       0  4546.9    .035       0
  4732.9     .12       0  4972.3     .05       0  4977.3     .12       0
  5060.5    .035       0
Bank Sta=4972.3,4977.3
XS Rating Curve= 0 ,0
Exp/Cntr=0.3,0.1

Type RM Length L Ch R = 1 ,12425   ,483,483,483
BEGIN DESCRIPTION:
Blieders Creek Tributary 9 24.0
END DESCRIPTION:
XS GIS Cut Line= 3
      2224459.62     13818824.34        2224525.       13817975.
        2224525.     13817824.96
#Sta/Elev= 30
  4143.1   870.4  4192.6  864.17  4272.8  852.41  4278.1  851.03  4363.1  841.97
  4408.4  839.17  4433.3  838.66  4493.5  834.69  4503.5  834.89  4533.6  833.56
  4543.8  829.72  4553.7  828.66  4623.9  826.59  4643.9  821.67    4654  820.28
  4786.5  820.38  4824.5  820.52  4854.5  824.24  4944.8  826.65  4974.9  826.18
  4984.9  823.23  4987.9  820.63  4989.9  818.89  4990.3  818.39  4994.6  818.39
  4994.9  818.89    5005  819.18    5065  830.33  5125.8  834.31    5145  835.48
#Mann= 6 ,-1 , 0
  4143.1     .12       0  4786.5    .035       0  4987.9     .12       0
  4989.9     .05       0  4994.9     .12       0  5125.8     .07       0
Bank Sta=4989.9,4994.9
XS Rating Curve= 0 ,0
Exp/Cntr=0.3,0.1

Type RM Length L Ch R = 1 ,11942   ,477,477,477
BEGIN DESCRIPTION:
Blieders Creek Tributary 9 23.0
END DESCRIPTION:
XS GIS Cut Line= 3
        2224975.     13818474.97        2224975.       13818075.
      2224874.99     13817724.97
#Sta/Elev= 30
    4600  839.79    4630  837.52    4640  836.33    4650  833.68    4680  821.04
    4690  819.31    4710  818.44    4720  817.16    4740  817.57    4800  821.77
    4820   822.7    4890   823.1    4940  822.04    4970  822.04    4980  821.23
  4994.9  815.25  4995.3  814.75  4999.7  814.75    5000  815.25  5010.4  816.26
  5016.9  818.78  5031.2  821.06  5041.6  821.92  5094.9  823.47  5167.7  824.16
  5196.3  824.96  5228.8  826.87    5260  827.35  5280.8  828.28    5364  830.34
#Mann= 3 ,-1 , 0
    4600     .12       0  4994.9     .05       0    5000     .12       0
Bank Sta=4994.9,5000
XS Rating Curve= 0 ,0
Exp/Cntr=0.3,0.1

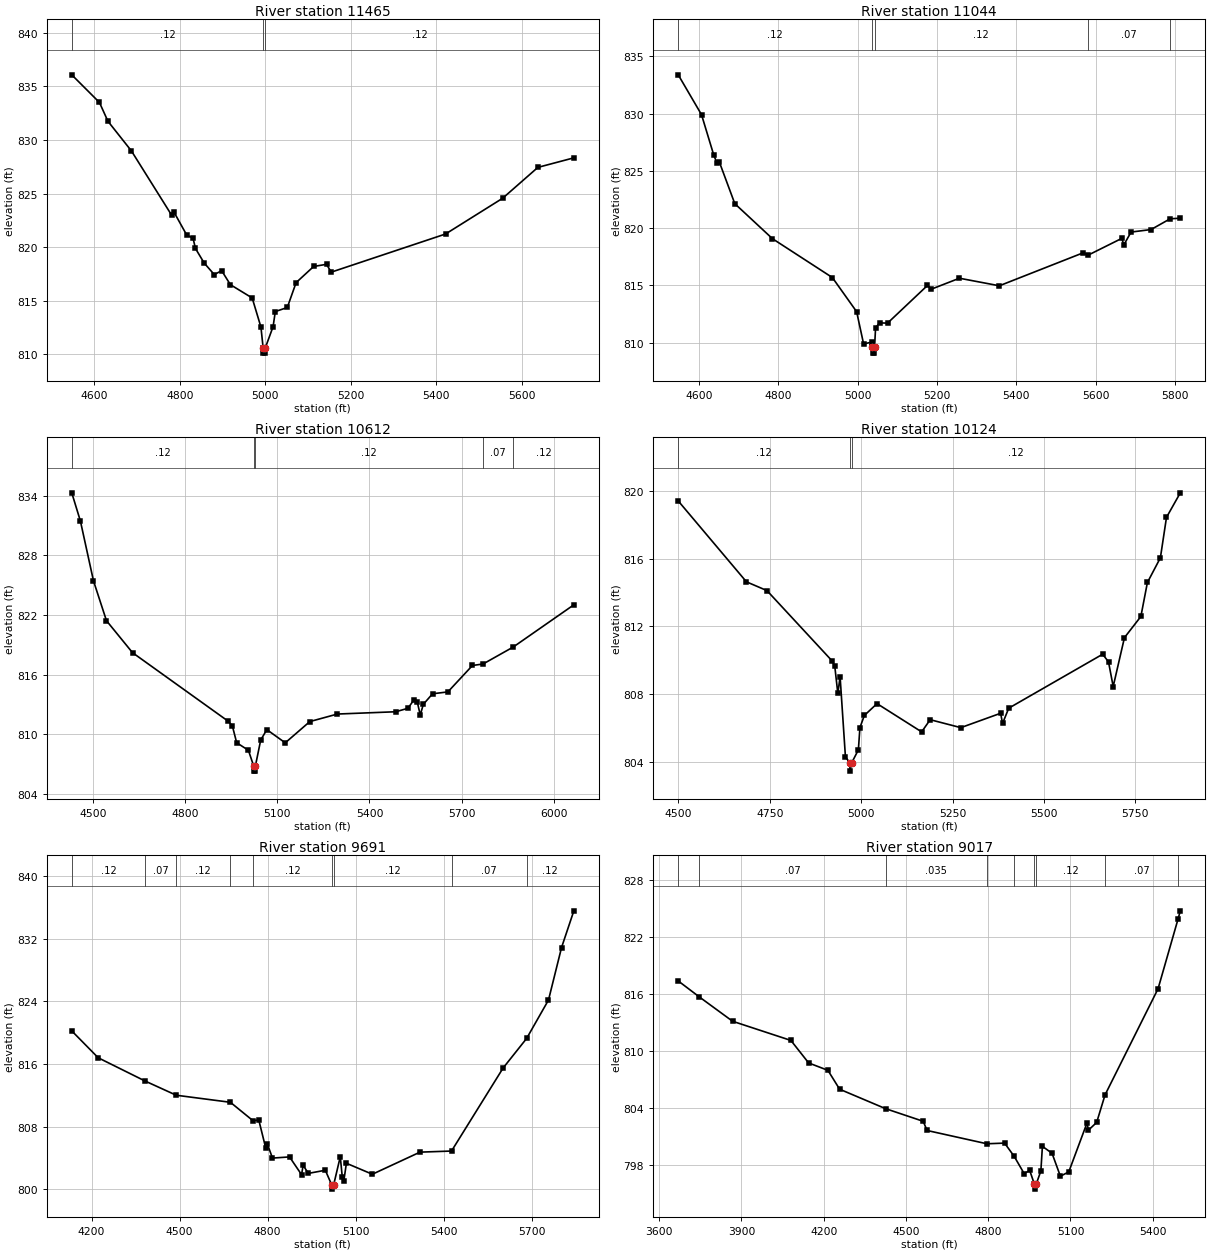
Type RM Length L Ch R = 1 ,11465   ,421,421,421
BEGIN DESCRIPTION:
Blieders Creek Tributary 9 22.0
END DESCRIPTION:
XS GIS Cut Line= 3
      2225468.38     13818518.38        2225375.       13818075.
      2225203.79     13817373.19
#Sta/Elev= 30
  4546.9  836.08  4611.7   833.5  4631.5  831.75  4686.5  828.98    4781  822.96
  4786.1  823.27  4816.1  821.12  4830.8  820.83  4836.5  819.87  4856.9  818.51
  4880.6  817.43  4897.8   817.8  4918.3  816.49  4969.3  815.25  4989.8  812.53
  4994.9   810.6  4995.3   810.1  4999.7   810.1  5000.1   810.6  5018.3  812.58
  5023.4  813.98  5051.5  814.36  5072.1  816.68  5113.2  818.19  5143.3  818.39
  5154.4  817.66    5422  821.22  5555.8  824.56  5638.2  827.44  5722.4  828.33
#Mann= 3 ,-1 , 0
  4546.9     .12       0  4994.9     .05       0  5000.1     .12       0
Bank Sta=4994.9,5000.1
XS Rating Curve= 0 ,0
Exp/Cntr=0.3,0.1

Type RM Length L Ch R = 1 ,11044   ,432,432,432
BEGIN DESCRIPTION:
Blieders Creek Tributary 9 21.0
END DESCRIPTION:
XS GIS Cut Line= 3
        2225525.     13818475.01        2225725.       13818075.
      2225633.77     13817261.62
#Sta/Elev= 30
  4547.9  833.38  4606.6   829.9  4637.3  826.39  4645.7  825.65  4651.3  825.79
  4690.5  822.13  4785.5  819.07  4936.4  815.68  4997.6   812.7  5015.2  809.88
  5035.2  810.04  5037.5  809.58  5037.9  809.08  5042.4  809.08  5042.8  809.58
  5045.4   811.3  5055.5  811.72  5075.6   811.7  5176.2  814.99  5186.3  814.67
  5256.8  815.62  5357.4  814.96  5568.7  817.84  5580.9  817.63  5666.1   819.1
  5671.2  818.53  5689.4  819.65  5739.8  819.87    5788  820.81  5813.6  820.86
#Mann= 5 ,-1 , 0
  4547.9     .12       0  5037.5     .05       0  5042.8     .12       0
  5580.9     .07       0    5788    .035       0
Bank Sta=5037.5,5042.8
XS Rating Curve= 0 ,0
Exp/Cntr=0.3,0.1

Type RM Length L Ch R = 1 ,10612   ,488,488,488
BEGIN DESCRIPTION:
Blieders Creek Tributary 9 20.0
END DESCRIPTION:
XS GIS Cut Line= 3
      2225725.03     13818574.97        2226125.       13818175.
      2226138.15     13817104.53
#Sta/Elev= 30
  4429.8   834.3    4458  831.45  4500.5  825.44  4542.9  821.42  4627.8   818.2
  4938.9  811.31    4953  810.84  4967.2  809.13  5005.4  808.37  5022.8  806.77
  5023.2  806.27  5027.7  806.27  5028.1  806.77  5045.5   809.4  5065.5  810.45
  5125.5  809.12  5205.5  811.26  5295.5  812.02  5485.5  812.25  5525.5   812.6
  5545.5  813.48  5555.5  813.27  5565.5  811.92  5575.5     813  5605.5  814.06
  5655.5  814.25  5735.5  816.91  5770.1  817.06  5868.5  818.77    6066  823.02
#Mann= 5 ,-1 , 0
  4429.8     .12       0  5022.8     .05       0  5028.1     .12       0
  5770.1     .07       0  5868.5     .12       0
Bank Sta=5022.8,5028.1
XS Rating Curve= 0 ,0
Exp/Cntr=0.3,0.1

Type RM Length L Ch R = 1 ,10124   ,433,433,433
BEGIN DESCRIPTION:
Blieders Creek Tributary 9 19.0
END DESCRIPTION:
XS GIS Cut Line= 3
      2226274.98     13818675.02        2226575.       13818275.
      2226924.98     13817475.04
#Sta/Elev= 30
  4499.6  819.41  4686.1  814.63  4742.3  814.11  4921.5  809.93  4927.8  809.63
  4936.1  808.03  4942.3  809.02  4956.9  804.28  4968.8  803.94  4969.3  803.44
  4974.2  803.94  4992.3   804.7  4996.5  806.01  5008.6  806.73  5043.3  807.43
  5165.3  805.76  5188.7  806.48  5272.5  806.01  5381.3  806.86  5386.7  806.26
  5403.5  807.16  5660.4  810.35  5676.4   809.9  5689.2  808.44    5720  811.33
  5764.9  812.58  5782.8  814.59  5818.3  816.05    5835  818.44  5872.8  819.89
#Mann= 3 ,-1 , 0
  4499.6     .12       0  4968.8     .05       0  4974.2     .12       0
Bank Sta=4968.8,4974.2
XS Rating Curve= 0 ,0
Exp/Cntr=0.3,0.1

Type RM Length L Ch R = 1 ,9691    ,674,674,674
BEGIN DESCRIPTION:
Blieders Creek Tributary 9 18.0
END DESCRIPTION:
XS GIS Cut Line= 3
      2226574.99     13818925.03        2226925.       13818125.
        2227175.       13817325.
#Sta/Elev= 30
  4132.6  820.23  4222.7   816.8  4382.7  813.83  4488.8  812.02  4673.3  811.12
  4750.7  808.76    4770  808.87  4793.4  805.33  4798.8  805.84  4816.8     804
  4874.9  804.15  4915.8  801.89  4921.3  803.07  4939.2  802.05  4996.9  802.45
  5019.1  800.54  5019.6  800.04    5025  800.54  5047.8  804.17  5054.6  801.62
  5059.8  801.07  5068.7  803.34  5157.2  801.94  5319.6  804.76    5427   804.9
    5603   815.5  5683.1  819.27  5757.6  824.17  5802.1  830.87    5844  835.55
#Mann= 9 ,-1 , 0
  4132.6     .12       0  4382.7     .07       0  4488.8     .12       0
  4673.3     .07       0  4750.7     .12       0  5019.1     .05       0
    5025     .12       0    5427     .07       0  5683.1     .12       0
Bank Sta=5019.1,5025
XS Rating Curve= 0 ,0
Exp/Cntr=0.3,0.1

Type RM Length L Ch R = 1 ,9017    ,654,654,654
BEGIN DESCRIPTION:
X18305
END DESCRIPTION:
XS GIS Cut Line= 3
      2226626.01     13818886.36      2227432.19     13818183.54
      2227572.75     13817435.25
#Sta/Elev= 30
  3669.7   817.4  3746.9  815.71    3868  813.15  4080.6  811.13  4145.2  808.76
  4215.5  807.98  4258.2  805.99  4425.8  803.94  4562.9  802.61  4577.2  801.64
  4795.3  800.24  4859.8  800.31  4894.9  798.91  4931.1   797.1  4951.4  797.43
  4968.7  795.96  4969.2  795.46  4974.8  795.96  4992.1  797.38  4997.7  799.97
  5032.8  799.24  5063.3  796.82  5093.9  797.28  5160.4  802.44  5165.4  801.67
  5195.6  802.49  5226.1  805.39  5419.5  816.58  5492.3  823.92  5500.6  824.79
#Mann= 9 ,-1 , 0
  3669.7     .12       0  3746.9     .07       0  4425.8    .035       0
  4795.3     .07       0  4894.9     .12       0  4968.7     .05       0
  4974.8     .12       0  5226.1     .07       0  5492.3    .035       0
Bank Sta=4968.7,4974.8
XS Rating Curve= 0 ,0
Exp/Cntr=0.3,0.1

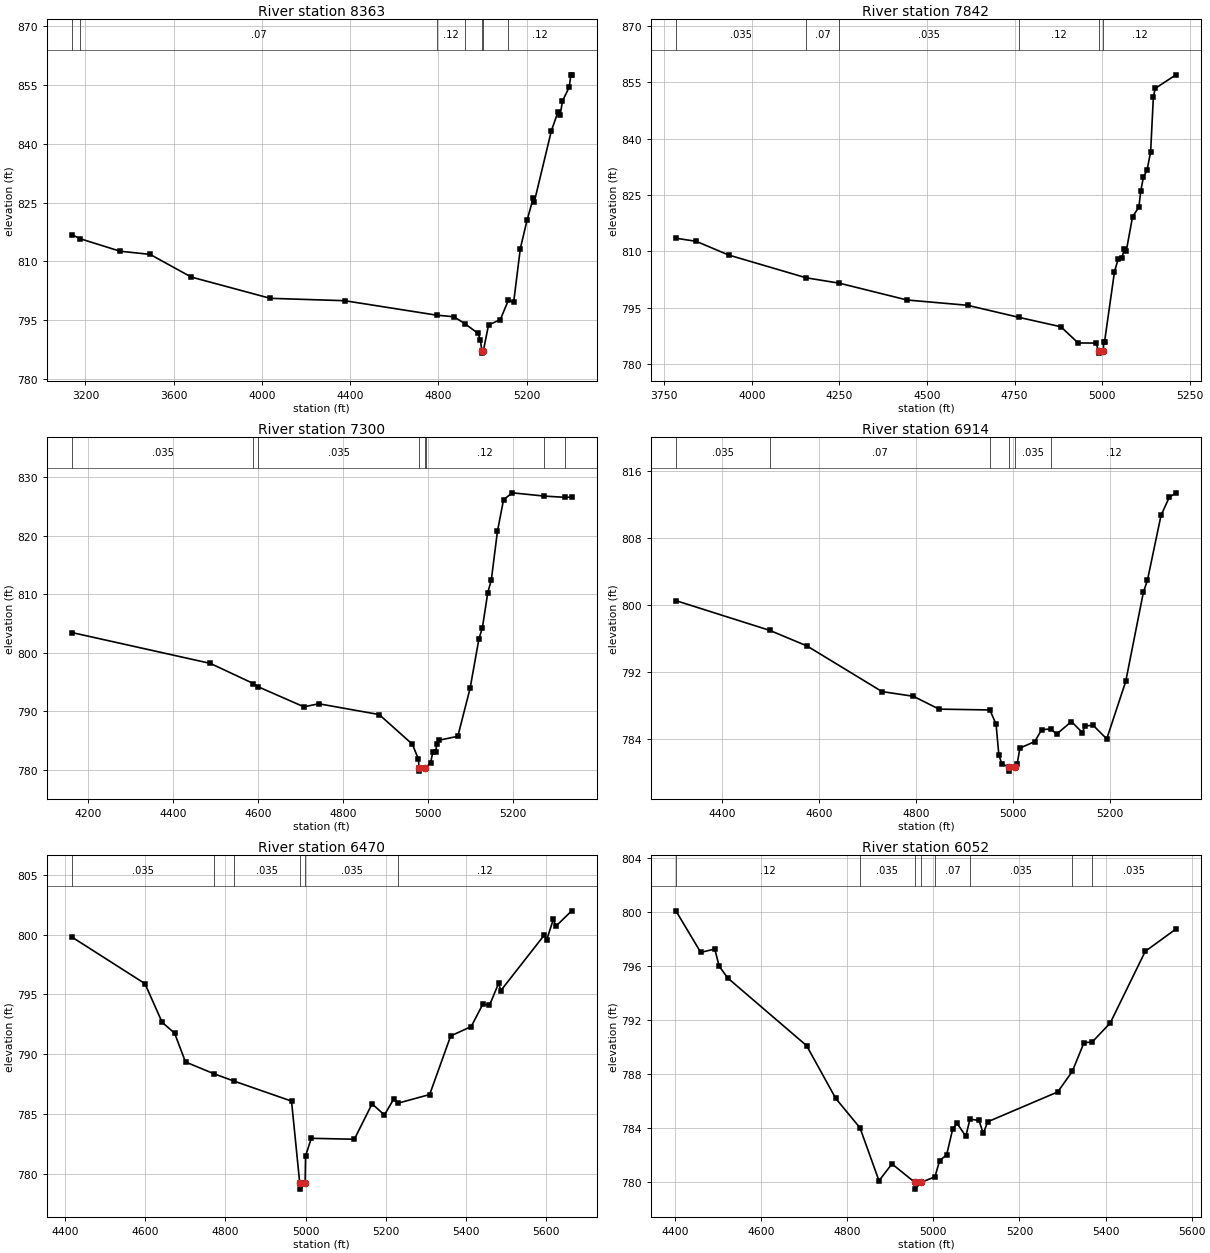
Type RM Length L Ch R = 1 ,8363    ,521,521,521
BEGIN DESCRIPTION:
X18306
END DESCRIPTION:
XS GIS Cut Line= 3
       2226650.8     13818907.04      2228077.14      13817877.6
      2228126.74     13817373.26
#Sta/Elev= 30
  3137.9  816.84  3177.3  815.77  3356.9  812.61  3493.1   811.8  3679.6  806.03
  4037.8  800.61  4375.2     800  4791.6  796.32  4869.6  795.92  4922.4  794.05
  4979.9  791.65    4990  789.93  4996.9  787.15  4997.4  786.65  5003.1  787.15
  5026.7   793.8  5080.4   795.2  5116.9  800.16  5140.7  799.61  5170.8  813.26
    5201  820.43  5229.4  826.11  5234.4  825.23  5311.5  843.26  5341.7  848.12
  5351.7  847.35  5361.8  850.85  5391.9  854.31  5400.3  857.53  5403.7  857.53
#Mann= 7 ,-1 , 0
  3137.9     .12       0  3177.3     .07       0  4791.6     .12       0
  4922.4    .035       0  4996.9    .035       0  5003.1    .035       0
  5116.9     .12       0
Bank Sta=4996.9,5003.1
XS Rating Curve= 0 ,0
Exp/Cntr=0.3,0.1

Type RM Length L Ch R = 1 ,7842    ,542,542,542
BEGIN DESCRIPTION:
Blieders Creek Tributary 9 17.0
END DESCRIPTION:
XS GIS Cut Line= 3
      2227875.02     13818774.98        2228575.       13817775.
        2228625.     13817574.98
#Sta/Elev= 30
  3783.3  813.49  3841.3  812.67  3933.7  809.02  4155.1  802.95  4250.1  801.51
  4442.9  797.04  4615.5  795.63  4763.3  792.39  4881.9  789.91  4931.1  785.59
  4981.7  785.58    4990  783.39  4990.5  782.89    5003  783.39  5003.9  785.95
  5006.5  785.95  5034.8  804.59  5045.2  807.91  5055.5  808.18  5063.2  810.71
  5068.3  810.03  5086.4  819.24  5104.4  821.75  5109.6     826  5117.3  829.75
  5127.6  831.61  5137.9   836.5  5145.7  851.02  5150.8  853.38  5210.1  857.01
#Mann= 6 ,-1 , 0
  3783.3    .035       0  4155.1     .07       0  4250.1    .035       0
  4763.3     .12       0    4990     .05       0    5003     .12       0
Bank Sta=4990,5003
XS Rating Curve= 0 ,0
Exp/Cntr=0.3,0.1

Type RM Length L Ch R = 1 ,7300    ,386,386,386
BEGIN DESCRIPTION:
Blieders Creek Tributary 9 16.0
END DESCRIPTION:
XS GIS Cut Line= 3
      2228224.98     13818725.02      2228887.46     13818183.54
      2229084.81     13817928.63
#Sta/Elev= 30
  4160.9  803.48  4487.6   798.2  4589.2  794.75  4599.8  794.22    4708  790.78
  4743.1   791.3  4885.3  789.46  4963.5  784.39  4977.9  781.82  4979.3  780.29
  4979.8  779.79  4992.3  780.29  4994.7  780.36  5006.6  781.23  5011.7  783.07
  5018.6  783.07  5020.8  784.36  5027.3  785.09  5070.6  785.74  5099.6  793.97
  5120.4  802.42  5128.5  804.29  5141.2  810.31  5149.4   812.4  5163.9  820.75
  5178.4   826.2  5199.2  827.35  5274.5  826.79  5323.4  826.58  5338.9  826.63
#Mann= 8 ,-1 , 0
  4160.9    .035       0  4589.2     .07       0  4599.8    .035       0
  4979.3     .05       0  4992.3    .035       0  4994.7     .12       0
  5274.5    .035       0  5323.4     .12       0
Bank Sta=4979.3,4992.3
XS Rating Curve= 0 ,0
Exp/Cntr=0.3,0.1

Type RM Length L Ch R = 1 ,6914    ,444,444,444
BEGIN DESCRIPTION:
Blieders Creek Tributary 9 15.0
END DESCRIPTION:
XS GIS Cut Line= 3
        2228425.       13818875.        2229025.       13818525.
      2229174.98     13818225.03
#Sta/Elev= 30
  4305.4  800.54    4499  796.99  4575.4  795.14    4730   789.7  4794.5  789.14
  4847.5  787.61  4952.2  787.51  4964.9  785.82  4970.7  782.12  4976.9  781.09
  4990.6  780.72  4991.1  780.22  5003.7  780.72  5008.4  781.07    5014  782.97
  5044.7  783.74  5058.7  785.16    5078  785.25  5089.5  784.62  5120.2  786.13
  5142.6  784.81  5148.2  785.61  5164.9  785.68  5192.9  784.06    5232  790.92
  5268.4  801.55  5276.7  802.97  5304.7   810.7  5321.5  812.84  5335.4  813.39
#Mann= 6 ,-1 , 0
  4305.4    .035       0    4499     .07       0  4952.2    .035       0
  4990.6    .035       0  5003.7    .035       0    5078     .12       0
Bank Sta=4990.6,5003.7
XS Rating Curve= 0 ,0
Exp/Cntr=0.3,0.1

Type RM Length L Ch R = 1 ,6470    ,418,418,418
BEGIN DESCRIPTION:
Blieders Creek Tributary 9 14.0
END DESCRIPTION:
XS GIS Cut Line= 3
      2228974.99     13819375.02        2229275.       13818875.
      2229557.21     13818274.52
#Sta/Elev= 30
  4416.9  799.81  4599.6   795.9  4642.4  792.67  4673.5  791.76  4700.7  789.35
  4771.4  788.37    4821  787.76    4965  786.08  4985.5  779.22    4986  778.72
  4998.9  779.22    5000  781.49  5014.2  782.97  5121.6  782.89  5165.8  785.85
  5196.6  784.92  5219.4  786.23  5230.9  785.91  5309.4  786.63  5361.8  791.53
  5412.9  792.31    5442  794.19  5458.5  794.09  5481.3  795.93  5486.8  795.32
  5595.3  799.97  5600.9  799.54  5618.1  801.31  5623.7  800.69  5663.5  801.99
#Mann= 6 ,-1 , 0
  4416.9    .035       0  4771.4     .07       0    4821    .035       0
  4985.5    .035       0  4998.9    .035       0  5230.9     .12       0
Bank Sta=4985.5,4998.9
XS Rating Curve= 0 ,0
Exp/Cntr=0.3,0.1

Type RM Length L Ch R = 1 ,6052    ,448,448,448
BEGIN DESCRIPTION:
Blieders Creek Tributary 9 13.0
END DESCRIPTION:
XS GIS Cut Line= 3
        2229575.     13819574.96        2229625.       13818975.
      2229725.01     13818424.96
#Sta/Elev= 30
  4402.4  800.09  4460.1  797.01  4492.7  797.26  4502.7     796  4522.8  795.11
  4705.9   790.1  4773.6  786.19  4829.9  784.01    4874  780.09  4904.1  781.34
  4957.3  779.97  4957.8  779.47  4971.4  779.97    5004  780.38  5014.6  781.57
  5031.1  782.02  5045.1  783.91  5055.3  784.35  5075.6  783.38  5085.2  784.65
  5106.1  784.56  5116.2   783.6  5126.4  784.46    5289  786.67  5322.8  788.19
    5350  790.32  5369.1  790.37    5411  791.78  5492.3  797.09  5563.5  798.74
#Mann= 8 ,-1 , 0
  4402.4     .12       0  4829.9    .035       0  4957.3    .035       0
  4971.4    .035       0    5004     .07       0  5085.2    .035       0
  5322.8     .07       0  5369.1    .035       0
Bank Sta=4957.3,4971.4
XS Rating Curve= 0 ,0
Exp/Cntr=0.3,0.1

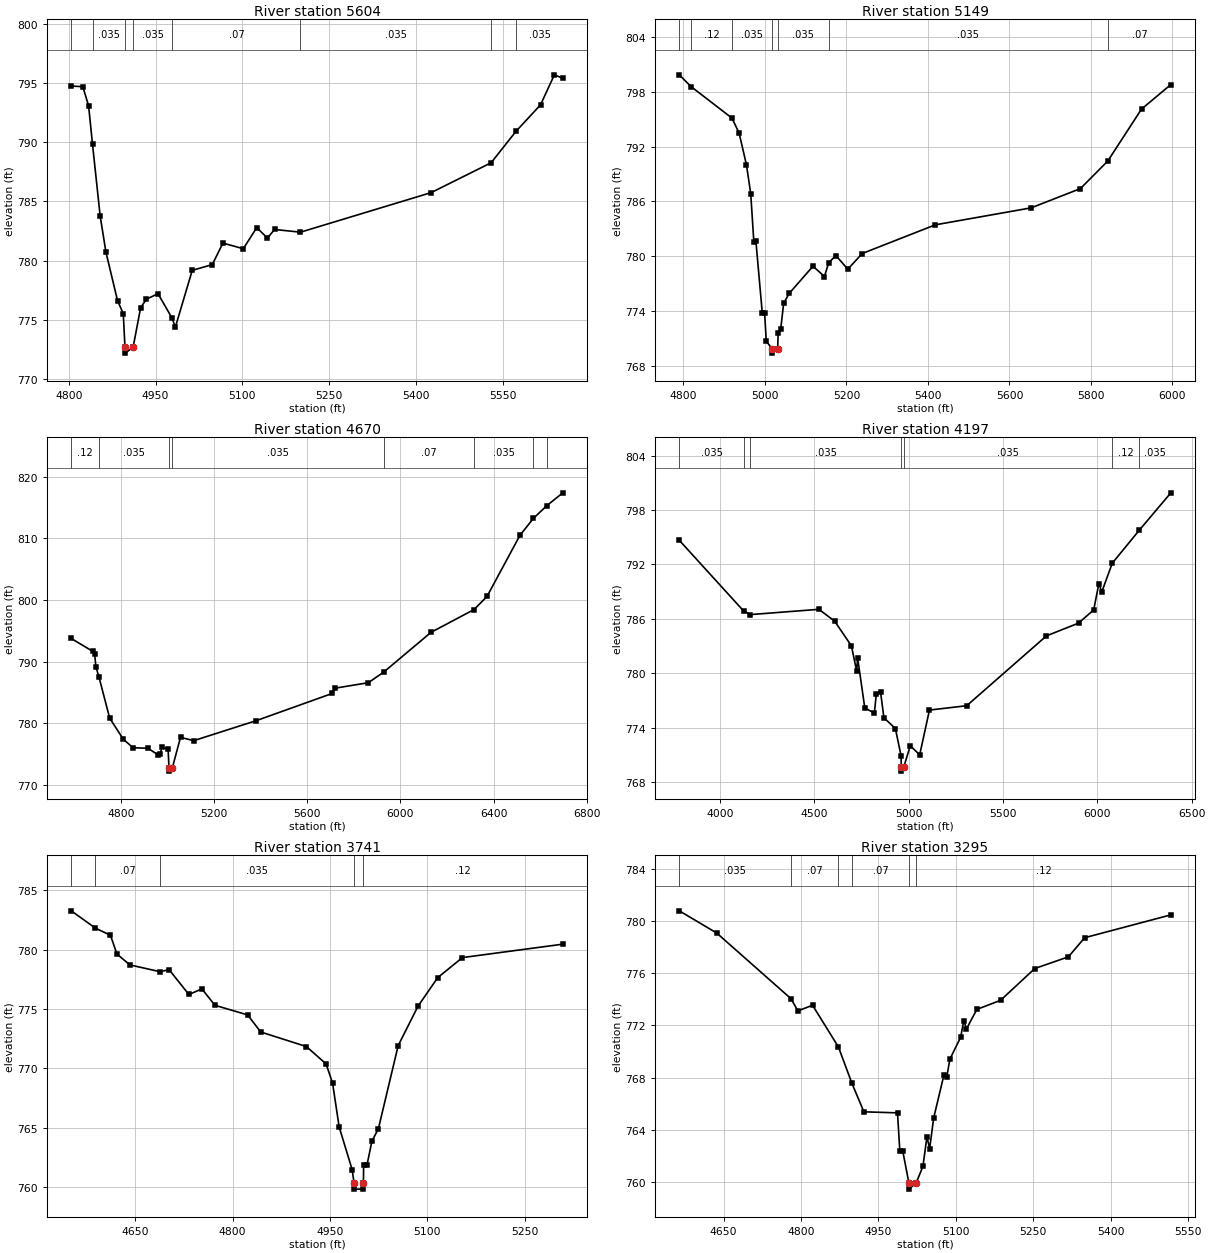
Type RM Length L Ch R = 1 ,5604    ,455,455,455
BEGIN DESCRIPTION:
Blieders Creek Tributary 9 12.0
END DESCRIPTION:
XS GIS Cut Line= 3
        2230025.     13819324.98        2230025.       13819125.
      2229774.99     13818524.98
#Sta/Elev= 30
  4804.2  794.76  4824.2  794.71  4834.2  793.09    4841  789.82  4854.2  783.77
  4864.2  780.71  4884.2  776.62  4894.2   775.5  4897.1  772.67  4897.6  772.17
  4911.2  772.67  4924.2  776.02  4934.2  776.73  4954.2   777.2  4978.7  775.12
  4984.2  774.36  5013.4  779.17  5048.1  779.66  5066.5  781.48  5101.7     781
    5125  782.79  5143.4   781.9  5155.8  782.63  5200.6   782.4  5426.7  785.75
  5530.2  788.27  5573.6  790.95  5615.7  793.17  5639.6  795.71  5654.2  795.42
#Mann= 8 ,-1 , 0
  4804.2     .12       0    4841    .035       0  4897.1     .05       0
  4911.2    .035       0  4978.7     .07       0  5200.6    .035       0
  5530.2     .07       0  5573.6    .035       0
Bank Sta=4897.1,4911.2
XS Rating Curve= 0 ,0
Exp/Cntr=0.3,0.1

Type RM Length L Ch R = 1 ,5149    ,479,479,479
BEGIN DESCRIPTION:
Blieders Creek Tributary 9 11.0
END DESCRIPTION:
XS GIS Cut Line= 3
      2230374.99     13819425.02        2230425.       13819225.
      2229824.99     13818424.98
#Sta/Elev= 30
  4789.8  799.86  4818.4  798.58  4919.1  795.12  4936.7  793.47  4954.7  789.98
  4965.1  786.86  4972.8  781.53  4977.9  781.61  4993.4   773.8  4999.1   773.8
  5003.3  770.69  5017.1  769.88  5017.6  769.38  5031.2  769.88  5032.4  771.54
  5038.7  772.04    5046  774.85  5059.5  775.92  5117.9   778.9    5146  777.77
  5156.4  779.28  5174.1  780.07  5203.3  778.57  5238.7  780.29  5417.9  783.43
  5653.3  785.29  5774.1   787.4  5841.3  790.42  5924.1  796.11    5996  798.79
#Mann= 7 ,-1 , 0
  4789.8     .07       0  4818.4     .12       0  4919.1    .035       0
  5017.1    .035       0  5031.2    .035       0  5156.4    .035       0
  5841.3     .07       0
Bank Sta=5017.1,5031.2
XS Rating Curve= 0 ,0
Exp/Cntr=0.3,0.1

Type RM Length L Ch R = 1 ,4670    ,473,473,473
BEGIN DESCRIPTION:
Blieders Creek Tributary 9 10.0
END DESCRIPTION:
XS GIS Cut Line= 3
        2230725.       13819425.        2230825.       13819025.
      2229624.98     13817824.98
#Sta/Elev= 30
  4587.7  793.74  4680.5  791.64  4688.2  791.23  4693.4  789.14  4706.3  787.55
  4752.6  780.82  4811.9  777.36  4853.1  776.03  4917.6  775.93  4958.8  774.89
  4969.1  774.98  4976.8  776.14  5003.5  775.74  5007.1  772.73  5007.6  772.23
  5021.3  772.73  5056.6  777.71  5113.2  777.17  5381.9  780.42  5707.1  784.82
  5721.3  785.69  5862.7  786.57  5928.3  788.28  6131.4  794.73  6316.5  798.44
  6371.8  800.55  6513.2  810.46  6570.8  813.21  6627.6  815.25  6697.1  817.36
#Mann= 8 ,-1 , 0
  4587.7     .12       0  4706.3    .035       0  5007.1    .035       0
  5021.3    .035       0  5928.3     .07       0  6316.5    .035       0
  6570.8     .07       0  6627.6     .12       0
Bank Sta=5007.1,5021.3
XS Rating Curve= 0 ,0
Exp/Cntr=0.3,0.1

Type RM Length L Ch R = 1 ,4197    ,456,456,456
BEGIN DESCRIPTION:
Blieders Creek Tributary 9 9.0
END DESCRIPTION:
XS GIS Cut Line= 3
      2231024.99     13820025.04        2231225.       13818825.
      2230525.02     13817625.04
#Sta/Elev= 30
  3783.8  794.67  4124.8  786.87  4161.3  786.47  4523.9  787.05  4607.6  785.74
  4696.3  783.02  4724.1  780.23  4729.2   781.7  4767.2  776.16  4817.9   775.6
  4828.1  777.66  4850.9  777.89  4868.6  775.08  4929.4  773.89  4959.8  770.86
  4960.3  769.69  4960.8  769.19  4974.5  769.69  5008.3  771.98  5058.3     771
    5110  775.93  5307.6  776.41  5730.2  784.12  5900.5  785.53  5980.7  786.99
    6008  789.88  6023.7  788.98    6079  792.14    6223   795.8  6389.6  799.91
#Mann= 7 ,-1 , 0
  3783.8    .035       0  4124.8     .07       0  4161.3    .035       0
  4960.3    .035       0  4974.5    .035       0    6079     .12       0
    6223    .035       0
Bank Sta=4960.3,4974.5
XS Rating Curve= 0 ,0
Exp/Cntr=0.3,0.1

Type RM Length L Ch R = 1 ,3741    ,446,446,446
BEGIN DESCRIPTION:
Blieders Creek Tributary 9 8.0
END DESCRIPTION:
XS GIS Cut Line= 3
        2231525.     13819074.98        2231575.       13818625.
        2231625.     13818324.99
#Sta/Elev= 30
  4551.6  783.28  4588.9  781.82    4612  781.22    4622  779.63  4642.1  778.72
  4687.5  778.16  4702.5  778.31  4732.7  776.23  4752.8   776.7  4772.9  775.32
  4823.2  774.51  4843.4  773.07  4913.8  771.84    4944  770.38    4954  768.76
  4964.1  765.08  4984.2  761.46  4987.1  760.33  4987.6  759.83    5001  759.83
  5001.5  760.33  5001.8  761.83  5006.9  761.83  5014.5  763.86  5024.6  764.93
    5055  771.92  5085.5  775.24  5115.9  777.65  5153.9  779.34  5308.5  780.47
#Mann= 5 ,-1 , 0
  4551.6    .035       0  4588.9     .07       0  4687.5    .035       0
  4987.1    .035       0  5001.5     .12       0
Bank Sta=4987.1,5001.5
XS Rating Curve= 0 ,0
Exp/Cntr=0.3,0.1

Type RM Length L Ch R = 1 ,3295    ,446,446,446
BEGIN DESCRIPTION:
Blieders Creek Tributary 9 7.0
END DESCRIPTION:
XS GIS Cut Line= 3
        2231725.     13819125.01        2231975.       13818775.
      2231825.01     13818275.04
#Sta/Elev= 30
  4564.3  780.77  4636.8  779.07  4780.4  774.05  4794.1  773.11  4822.4  773.54
  4872.5  770.35  4898.8  767.55  4921.9  765.38    4987   765.3  4991.4  762.41
    4997  762.41  5008.9  759.96  5009.4  759.46  5023.4  759.96  5036.2   761.2
    5044  763.47  5049.2  762.56  5057.1  764.92  5077.1  768.23  5082.3  768.02
  5088.4  769.41  5109.3  771.09  5115.4  772.37  5120.6  771.73  5140.6  773.22
  5186.7  773.92  5252.8  776.35  5318.1  777.25  5349.4  778.71  5516.4  780.46
#Mann= 6 ,-1 , 0
  4564.3    .035       0  4780.4     .07       0  4872.5    .035       0
  4898.8     .07       0  5008.9     .05       0  5023.4     .12       0
Bank Sta=5008.9,5023.4
XS Rating Curve= 0 ,0
Exp/Cntr=0.3,0.1

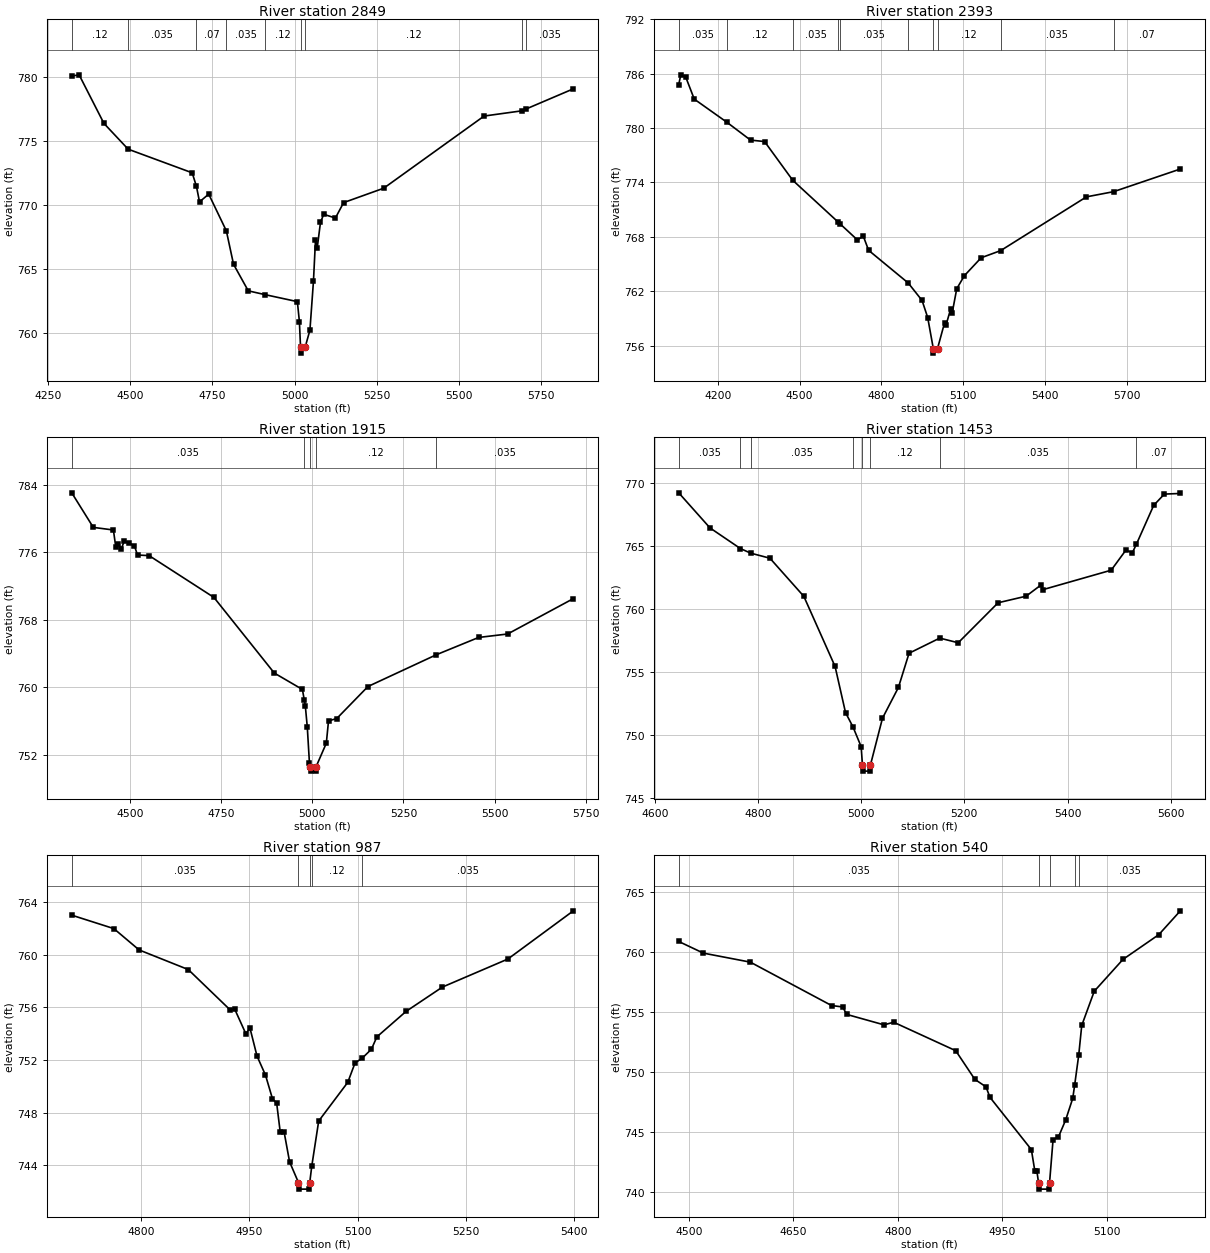
Type RM Length L Ch R = 1 ,2849    ,456,456,456
BEGIN DESCRIPTION:
Blieders Creek Tributary 9 6.0
END DESCRIPTION:
XS GIS Cut Line= 3
      2231774.99     13819225.01        2232375.       13818925.
      2232075.01     13818125.03
#Sta/Elev= 30
  4322.6  780.04    4345  780.14  4420.4  776.36  4494.1  774.35  4688.8  772.51
  4701.7  771.46  4711.1  770.25  4739.1  770.85  4792.7  767.99  4814.5  765.39
  4859.3  763.32  4909.3  763.03  5008.6  762.48  5014.8  760.92  5018.2  758.97
  5018.7  758.47  5032.7  758.97  5046.8  760.26  5057.5  764.05  5063.7  767.25
  5069.1  766.69  5078.9  768.65  5088.7  769.28  5124.3  768.99  5149.2  770.19
  5271.1  771.31  5576.4  776.93  5692.1  777.34  5703.2  777.47  5847.8  779.05
#Mann= 9 ,-1 , 0
  4322.6     .12       0  4494.1    .035       0  4701.7     .07       0
  4792.7    .035       0  4909.3     .12       0  5018.2     .05       0
  5032.7     .12       0  5692.1     .07       0  5703.2    .035       0
Bank Sta=5018.2,5032.7
XS Rating Curve= 0 ,0
Exp/Cntr=0.3,0.1

Type RM Length L Ch R = 1 ,2393    ,478,478,478
BEGIN DESCRIPTION:
Blieders Creek Tributary 9 5.0
END DESCRIPTION:
XS GIS Cut Line= 3
      2233001.09      13819990.2        2232775.       13819075.
      2232375.02     13818275.04
#Sta/Elev= 30
  4057.4  784.79  4064.9  785.87  4083.4   785.6  4114.3  783.19  4232.8  780.66
  4320.3  778.67  4371.8  778.51  4474.9  774.24  4641.5  769.62  4649.1  769.41
  4711.7  767.66  4733.3  768.08  4752.9  766.51  4897.8  762.91  4948.6  760.98
  4969.2   759.1  4989.8  755.67  4990.3  755.17  5005.2  755.67  5030.9  758.51
  5036.5  758.27  5053.2  760.04  5058.8  759.58  5075.6  762.27  5103.5  763.71
    5165  765.69  5236.6  766.48  5550.7  772.41    5650  772.98  5894.5  775.48
#Mann= 10 ,-1 , 0
  4057.4    .035       0  4232.8     .12       0  4474.9    .035       0
  4641.5     .12       0  4649.1    .035       0  4897.8     .12       0
  4989.8     .05       0  5005.2     .12       0  5236.6    .035       0
    5650     .07       0
Bank Sta=4989.8,5005.2
XS Rating Curve= 0 ,0
Exp/Cntr=0.3,0.1

Type RM Length L Ch R = 1 ,1915    ,462,462,462
BEGIN DESCRIPTION:
Blieders Creek Tributary 9 4.0
END DESCRIPTION:
XS GIS Cut Line= 3
      2233501.37     13819568.57        2233225.       13818975.
      2232624.97     13818574.98
#Sta/Elev= 30
  4340.3  783.08  4399.4  778.98  4454.6  778.67    4461  776.66  4466.5  777.03
  4476.6  776.46  4483.9  777.32  4498.7   777.1  4512.3  776.78  4520.7   775.7
  4552.5  775.63  4730.3  770.67  4895.8   761.7    4973  759.75    4978  758.53
  4980.9  757.83  4986.4  755.29  4992.3  751.01  4994.9  750.56  4995.4  750.06
  5009.8  750.06  5010.3  750.56  5038.6  753.38  5044.6  756.02  5067.2   756.3
  5152.8   760.1  5340.4  763.87  5456.3  765.92  5535.9  766.33  5716.2  770.53
#Mann= 5 ,-1 , 0
  4340.3    .035       0    4978     .12       0  4994.9     .05       0
  5010.3     .12       0  5340.4    .035       0
Bank Sta=4994.9,5010.3
XS Rating Curve= 0 ,0
Exp/Cntr=0.3,0.1

Type RM Length L Ch R = 1 ,1453    ,466,466,466
BEGIN DESCRIPTION:
Blieders Creek Tributary 9 3.0
END DESCRIPTION:
XS GIS Cut Line= 3
      2233724.97       13818625.        2233375.       13818575.
      2232774.99       13818425.
#Sta/Elev= 30
  4646.5  769.19  4707.1  766.41  4766.2  764.77    4786  764.41  4823.2  764.01
  4888.9  760.99  4949.5  755.43  4969.7  751.78  4984.2  750.64    5000  749.08
  5002.5  747.64    5003  747.14  5017.6  747.14  5018.1  747.64  5041.3  751.33
  5072.2  753.77  5092.8  756.48  5152.3  757.68  5188.1  757.31  5265.4  760.48
  5319.6     761  5347.9  761.87  5353.1  761.53  5484.5  763.06  5512.8  764.64
  5525.7  764.46  5533.4  765.12  5566.9   768.2  5587.6  769.09  5618.5  769.14
#Mann= 8 ,-1 , 0
  4646.5    .035       0  4766.2     .12       0    4786    .035       0
  4984.2     .12       0  5002.5     .05       0  5018.1     .12       0
  5152.3    .035       0  5533.4     .07       0
Bank Sta=5002.5,5018.1
XS Rating Curve= 0 ,0
Exp/Cntr=0.3,0.1

Type RM Length L Ch R = 1 ,987     ,447,447,447
BEGIN DESCRIPTION:
Blieders Creek Tributary 9 2.0
END DESCRIPTION:
XS GIS Cut Line= 3
      2233575.03     13818275.02        2233325.       13818125.
        2232925.       13818175.
#Sta/Elev= 30
  4703.9  762.99  4762.2  761.97  4797.2  760.35  4865.3  758.86  4923.6  755.78
  4929.4  755.88  4944.9     754  4950.8   754.4  4960.5  752.29  4972.2  750.85
  4981.9  749.05  4987.7  748.72  4992.6  746.53    4998  746.53  5005.6  744.26
  5017.9  742.69  5018.4  742.19    5033  742.19  5033.5  742.69  5036.3  743.93
  5045.9  747.36  5086.2   750.3  5096.3  751.78  5105.7  752.11  5118.9  752.81
  5126.5  753.75  5166.8  755.68  5217.2  757.53  5307.9  759.66  5398.6  763.32
#Mann= 5 ,-1 , 0
  4703.9    .035       0  5017.9    .035       0  5033.5    .035       0
  5036.3     .12       0  5105.7    .035       0
Bank Sta=5017.9,5033.5
XS Rating Curve= 0 ,0
Exp/Cntr=0.3,0.1

Type RM Length L Ch R = 1 ,540     ,0,0,0
BEGIN DESCRIPTION:
Blieders Creek Tributary 9 1.0
END DESCRIPTION:
XS GIS Cut Line= 3
      2233624.99     13818174.99        2233375.       13817725.
      2233175.02       13817675.
#Sta/Elev= 30
  4485.2  760.87  4520.6   759.9  4588.1  759.15  4704.8  755.54  4720.8  755.42
  4726.6   754.8  4780.3  753.93  4794.1  754.15  4883.3  751.78  4910.7   749.4
  4926.8  748.77  4932.5   747.9    4992  743.55  4997.1  741.73    5000  741.73
  5002.4  740.76  5002.9  740.26  5017.6  740.26  5018.1  740.76  5023.2  744.39
  5030.9   744.6  5041.2     746  5051.5  747.82  5054.3  748.95  5060.1  751.43
  5064.4  753.88  5082.4  756.73  5123.7  759.38  5175.2  761.44  5206.1  763.42
#Mann= 5 ,-1 , 0
  4485.2    .035       0  5002.4    .035       0  5018.1    .035       0
  5054.3     .12       0  5060.1    .035       0
Bank Sta=5002.4,5018.1
XS Rating Curve= 0 ,0
Exp/Cntr=0.3,0.1

Chan Stop Cuts=-1
Use User Specified Reach Order=0
Composite Channel Slope=5