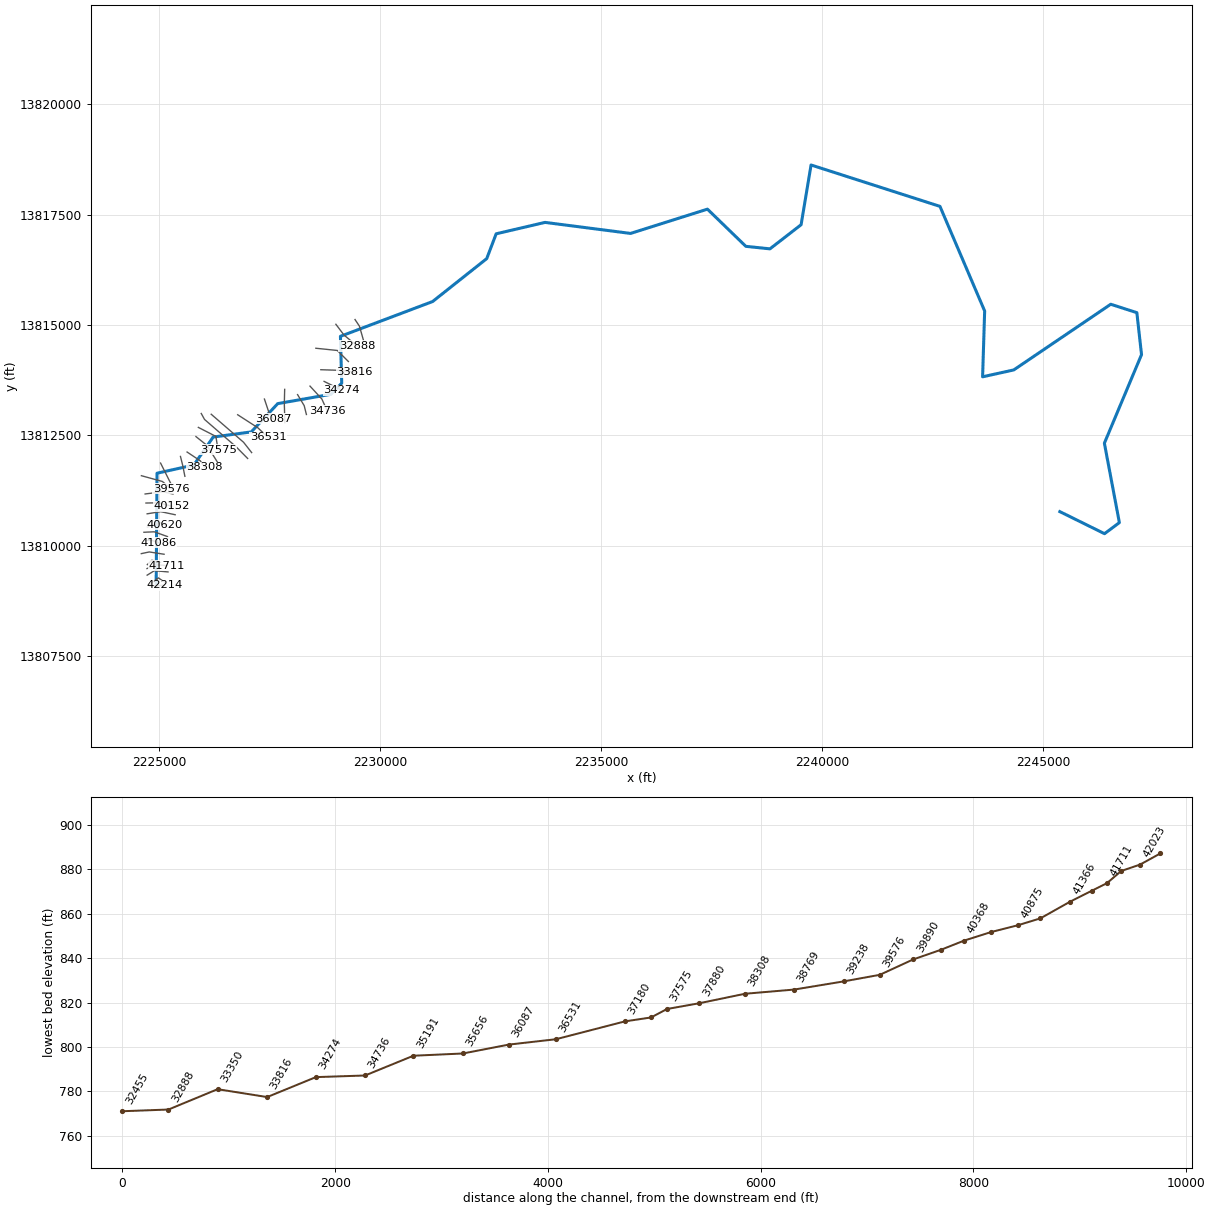
--- Blieders Creek.prj (project) ---

Proj Title=Blieders Creek Base Level Engineering
Current Plan=p01
Default Exp/Contr=0.3,0.1
English Units
Geom File=g01
Flow File=f01
Plan File=p01
Y Axis Title=Elevation
X Axis Title(PF)=Main Channel Distance
X Axis Title(XS)=Station
BEGIN DESCRIPTION:
Blieders Creek
END DESCRIPTION:
DSS Export Rating Curves= 0
DSS Export Rating Curve Sorted= 0
DSS Export Volume Flow Curves= 0
DXF OffsetX= 0
DXF OffsetY= 0
DXF ScaleX= 1
DXF ScaleY= 10

--- Blieders Creek.p01 (plan) ---

Plan Title=Multiple Run
Program Version=4.10
Short Identifier=Multiple
Geom File=g01
Flow File=f01
Subcritical Flow
K Sum by GR= 0
Std Step Tol= 0.01
Critical Tol= 0.01
Num of Std Step Trials= 20
Max Error Tol= 0.3
Flow Tol Ratio= 0.001
Split Flow NTrial= 30
Split Flow Tol= 0.02
Split Flow Ratio= 0.02
Log Output Level= 0
Friction Slope Method= 1
Unsteady Friction Slope Method= 2
Unsteady Bridges Friction Slope Method= 1
Parabolic Critical Depth
Global Vel Dist= 1 , 1 , 1
Global Log Level= 0
CheckData=True
Encroach Param=-1 ,0,0, 0
BEGIN DESCRIPTION:
Multiple Run
END DESCRIPTION:
Computation Interval=1HOUR
Output Interval=1HOUR
Run HTab= 0
Run UNet= 0
Run PostProcess= 0
Run WQNet= 0
UNET Theta= 1
UNET Theta Warmup= 1
UNET ZTol= 0.02
UNET ZSATol= 0.05
UNET MxIter= 20
UNET MaxInSteps= 0
UNET DtIC= 0
UNET DtMin= 0
UNET MaxCRTS= 20
UNET WFStab= 2
UNET SFStab= 1
UNET WFX= 1
UNET SFX= 1
UNET DSS MLevel= 4
UNET DZMax Abort= 100
UNET Convert EG Bridges= 0
UNET Use Existing IB Tables=-1
UNET Froude Reduction=False
UNET Froude Limit= 1
UNET Froude Power= 10
UNET Time Slicing=0,0, 5
UNET Junction Losses=0
Instantaneous Interval=1HOUR
Write IC File= 0
Write IC File at Sim End=0
Echo Input=False
Echo Parameters=False
Echo Output=False
Write Detailed= 0
WQ AD Non Conservative
WQ ULTIMATE=-1
WQ Max Comp Step=1HOUR
WQ Output Interval=15MIN
WQ Output Selected Increments= 0
WQ Output face flow=0
WQ Output face velocity=0
WQ Output face area=0
WQ Output face dispersion=0
WQ Output cell volume=0
WQ Output cell surface area=0
WQ Output cell continuity=0
WQ Output cumulative cell continuity=0
WQ Output face conc=0
WQ Output face dconc_dx=0
WQ Output face courant=0
WQ Output face peclet=0
WQ Output face adv mass=0
WQ Output face disp mass=0
WQ Output cell mass=0
WQ Output cell source sink temp=0
WQ Output cell source sink nsm=0
WQ Output MaxMinRange=-1
WQ Daily Max Min Mean=-1
WQ Daily Range=0
WQ Daily Time=0
WQ Create Restart=0
WQ Fixed Restart=0
WQ System Summary=0
WQ Use Fixed Temperature=0
Sorting and Armoring Iterations= 10
XS Update Threshold= 0.02
Hydraulics Update Threshold= 0.02
Energy Slope Method= 1
Volume Change Method= 0
XS Weighting Method= 0
Number of US Weighted Cross Sections= 1
Number of DS Weighted Cross Sections= 1
Upstream XS Weight=0.25
Main XS Weight=0.5
Downstream XS Weight=0.25
Number of DS XS's Weighted with US Boundary= 1
Upstream Boundary Weight= 1
Weight of XSs Associated with US Boundary= 0
Number of US XS's Weighted with DS Boundary= 1
Downstream Boundary Weight= 0.5
Weight of XSs Associated with DS Boundary= 0.5
Sediment Output Level= 4
Mass or Volume Output= 0
Output Increment Type= 1
Profile and TS Output Increment= 10
XS Output Flag= 0
XS Output Increment= 10
Disregard all LS=0
Disregard all Conn=0
Disregard all Breaches=0
Disregard all Pumps=0

--- Blieders Creek.f01 (steady flow) ---

Flow Title=Multiple
Program Version=4.10
Number of Profiles= 7
Profile Names=10-year,25-year,50-year,1pct_min,100-year,1pct_plu,500-year
River Rch & RM=Blieders Creek,Reach-1         ,42214
     320     499     656     420     838    1671    1345
River Rch & RM=Blieders Creek,Reach-1         ,39576
    1502    2582    3622    2458    4905    9786    8902
River Rch & RM=Blieders Creek,Reach-1         ,36531
    1746    3018    4248    2891    5769   11510   10532
River Rch & RM=Blieders Creek,Reach-1         ,34274
    1896    3275    4606    3130    6244   12459   11366
River Rch & RM=Blieders Creek,Reach-1         ,29230
    2625    4596    6524    4467    8913   17785   16487
River Rch & RM=Blieders Creek,Reach-1         ,26849
    4869    8701   12519    8673   17306   34529   32761
River Rch & RM=Blieders Creek,Reach-1         ,24671
    1474    2490    3449    2308    4604    9186    8124
River Rch & RM=Blieders Creek,Reach-1         ,21686
    1894    3241    4527    3052    6090   12152   10917
River Rch & RM=Blieders Creek,Reach-1         ,17851
    2049    3512    4912    3314    6612   13193   11870
River Rch & RM=Blieders Creek,Reach-1         ,11362
    2723    4723    6658    4523    9025   18008   16433
River Rch & RM=Blieders Creek,Reach-1         ,3980
    2968    5166    7300    4971    9918   19790   18140
Boundary for River Rch & Prof#=Blieders Creek,Reach-1         , 1
Up Type= 0
Dn Type= 1
Dn Known WS=631.6
Boundary for River Rch & Prof#=Blieders Creek,Reach-1         , 2
Up Type= 0
Dn Type= 1
Dn Known WS=634.2
Boundary for River Rch & Prof#=Blieders Creek,Reach-1         , 3
Up Type= 0
Dn Type= 1
Dn Known WS=636.1
Boundary for River Rch & Prof#=Blieders Creek,Reach-1         , 4
Up Type= 0
Dn Type= 1
Dn Known WS=634.2
Boundary for River Rch & Prof#=Blieders Creek,Reach-1         , 5
Up Type= 0
Dn Type= 1
Dn Known WS=636.8
Boundary for River Rch & Prof#=Blieders Creek,Reach-1         , 6
Up Type= 0
Dn Type= 1
Dn Known WS=639
Boundary for River Rch & Prof#=Blieders Creek,Reach-1         , 7
Up Type= 0
Dn Type= 1
Dn Known WS=638.8
DSS Import GetInterval= 0
DSS Import GetPeak= 0
DSS Import FillOption= 0

--- Blieders Creek.g01 (geometry) ---

Geom Title=Existing Conditions
Program Version=4.10

River Reach=Blieders Creek  ,Reach-1
Reach XY= 30
        2224925.       13809075.       2224944.6     13811645.16
      2225777.42     13811830.41      2226215.29     13812464.25
      2227077.29     13812580.84      2227676.47     13813221.47
      2228881.33     13813433.04      2229123.96     13813685.43
      2229094.84     13814745.39      2231181.05     13815533.16
      2232405.37     13816504.84      2232618.92     13817066.87
        2233725.       13817325.      2235659.84     13817075.38
      2237400.09     13817625.21      2238268.83     13816782.86
       2238814.5      13816726.2      2239519.54     13817272.55
      2239744.98     13818625.05      2242661.37     13817688.21
      2243672.75     13815319.07      2243626.48      13813828.6
      2244331.67      13813984.3      2246526.47     13815471.45
      2247116.84     13815281.05      2247222.74     13814330.94
       2246382.1       13812325.      2246721.38      13810526.5
      2246385.49     13810275.94      2245374.26     13810775.49

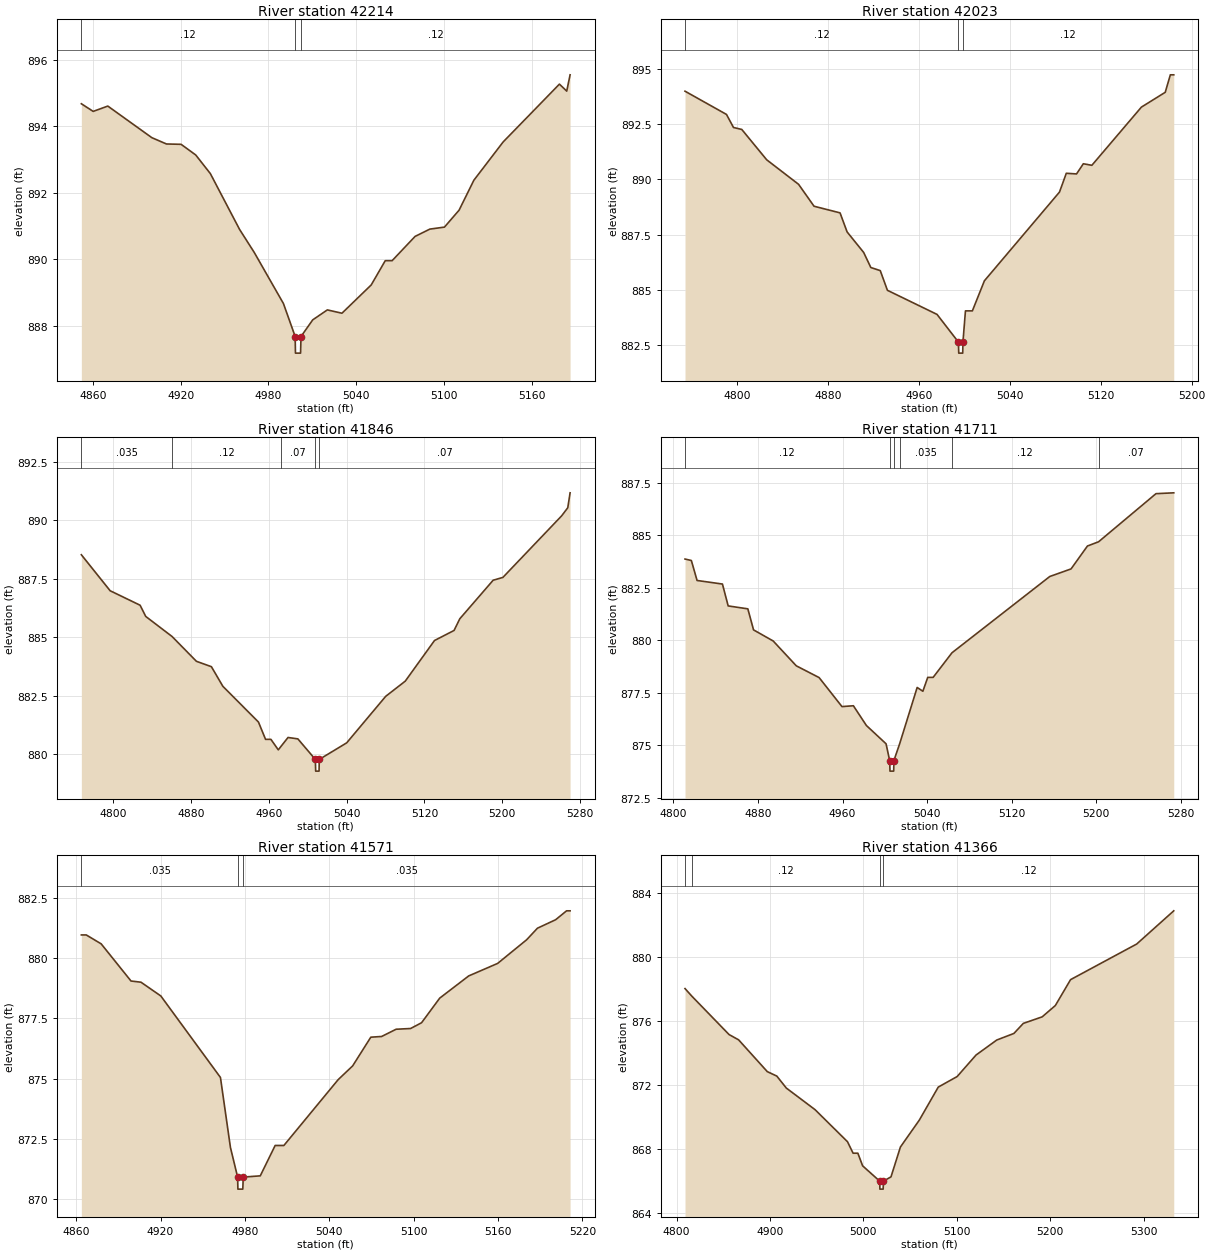
Type RM Length L Ch R = 1 ,42214   ,191,191,191
BEGIN DESCRIPTION:
X18254
END DESCRIPTION:
XS GIS Cut Line= 3
      2224776.86     13809096.46       2224989.3     13809099.94
      2225110.58     13809110.34
#Sta/Elev= 30
  4852.1  894.68  4860.2  894.45  4870.2  894.61  4900.3  893.66  4910.3  893.47
  4920.3  893.46  4930.3  893.14  4940.3  892.58  4960.3   890.9  4970.3  890.21
  4990.3  888.67  4998.3  887.68  4998.5  887.18    5002  887.18  5002.3  887.68
  5010.3  888.18  5020.3  888.48  5030.3  888.38  5050.3  889.23  5059.9  889.96
  5064.6  889.96  5080.3  890.69  5090.4  890.91  5100.4  890.97  5110.4  891.48
  5120.5  892.38  5140.5  893.53    5179  895.27    5184  895.06  5186.3  895.55
#Mann= 3 ,-1 , 0
  4852.1     .12       0  4998.3     .05       0  5002.3     .12       0
Bank Sta=4998.3,5002.3
XS Rating Curve= 0 ,0
Exp/Cntr=0.3,0.1

Type RM Length L Ch R = 1 ,42023   ,177,177,177
BEGIN DESCRIPTION:
Blieders Creek 83.0
END DESCRIPTION:
XS GIS Cut Line= 3
      2224774.98     13809124.98        2224975.       13809275.
      2225124.99       13809175.
#Sta/Elev= 30
  4753.9  893.99  4790.4  892.94  4796.6  892.35  4803.9  892.26  4825.8  890.89
  4853.9  889.78  4867.5  888.79  4890.4  888.49  4896.6  887.63  4911.2   886.7
  4917.5  886.02  4925.8  885.88  4932.1  884.99  4975.8   883.9  4994.6  882.65
  4994.9  882.15  4998.4  882.15  4998.6  882.65  5000.8  884.06  5006.9  884.06
  5017.5  885.42  5083.6  889.43  5089.6  890.28  5098.6  890.25  5104.6  890.71
  5112.1  890.64  5155.7  893.27  5176.7  893.94  5181.2  894.73  5184.2  894.73
#Mann= 3 ,-1 , 0
  4753.9     .12       0  4994.6     .05       0  4998.6     .12       0
Bank Sta=4994.6,4998.6
XS Rating Curve= 0 ,0
Exp/Cntr=0.3,0.1

Type RM Length L Ch R = 1 ,41846   ,135,135,135
BEGIN DESCRIPTION:
X18249
END DESCRIPTION:
XS GIS Cut Line= 3
       2224721.2     13809336.72      2224884.84     13809437.69
      2225193.81     13809409.92
#Sta/Elev= 30
  4767.3  888.53  4796.9  886.99  4827.7  886.37  4833.5  885.89  4860.6  885.03
  4885.6  883.97    4901  883.74  4912.8   882.9  4949.4  881.37  4956.7  880.63
  4962.2  880.63  4969.8  880.18  4972.4  880.32  4979.8  880.71  4989.9  880.65
  5007.9  879.77  5008.2  879.27  5011.7  879.27  5011.9  879.77  5040.1  880.48
  5080.2  882.47  5100.3  883.12  5130.4  884.86  5150.5  885.29  5156.4  885.79
  5190.7  887.44  5200.7  887.56    5261  890.19  5267.4  890.54  5269.8  891.18
#Mann= 5 ,-1 , 0
  4767.3    .035       0  4860.6     .12       0  4972.4     .07       0
  5007.9     .05       0  5011.9     .07       0
Bank Sta=5007.9,5011.9
XS Rating Curve= 0 ,0
Exp/Cntr=0.3,0.1

Type RM Length L Ch R = 1 ,41711   ,140,140,140
BEGIN DESCRIPTION:
X18253
END DESCRIPTION:
XS GIS Cut Line= 3
      2224717.66     13809486.42      2224930.11     13809573.49
      2225161.69     13809552.75
#Sta/Elev= 30
  4811.1  883.86  4817.1  883.79  4822.5  882.84  4846.5  882.67  4851.9  881.63
  4870.5  881.49  4875.9  880.49  4894.5  879.96  4916.3  878.78  4937.9  878.22
  4959.5  876.84  4970.3  876.88  4982.6  875.94  5001.2  875.07  5004.6  874.27
  5004.9  873.77  5008.4  873.77  5008.6  874.27  5014.1  875.08  5030.6  877.75
    5036  877.57  5040.6  878.23  5045.7  878.23  5063.5   879.4    5156  883.03
  5176.1  883.39  5191.6  884.48  5202.1  884.68  5256.4  886.97  5273.2  887.01
#Mann= 6 ,-1 , 0
  4811.1     .12       0  5004.6     .05       0  5008.6     .12       0
  5014.1    .035       0  5063.5     .12       0  5202.1     .07       0
Bank Sta=5004.6,5008.6
XS Rating Curve= 0 ,0
Exp/Cntr=0.3,0.1

Type RM Length L Ch R = 1 ,41571   ,205,205,205
BEGIN DESCRIPTION:
Blieders Creek 82.0
END DESCRIPTION:
XS GIS Cut Line= 3
      2224725.03     13809575.03        2224825.       13809675.
      2225024.97     13809625.01
#Sta/Elev= 30
  4863.7  880.96  4867.2  880.96  4877.8  880.59    4899  879.05  4906.1     879
  4920.2  878.43  4962.6  875.05  4969.7  872.15  4974.8  870.92    4975  870.42
  4978.5  870.42  4978.8  870.92  4990.9  870.97  5001.5  872.23  5007.7  872.23
  5046.3  874.96  5056.6  875.53  5069.5  876.72  5077.2  876.75  5087.5  877.05
  5097.8  877.08  5105.6  877.32  5118.5  878.34  5139.1  879.26  5159.7  879.78
  5180.3  880.76    5188  881.24  5200.9  881.59  5208.7  881.96  5211.2  881.96
#Mann= 3 ,-1 , 0
  4863.7    .035       0  4974.8    .035       0  4978.8    .035       0
Bank Sta=4974.8,4978.8
XS Rating Curve= 0 ,0
Exp/Cntr=0.3,0.1

Type RM Length L Ch R = 1 ,41366   ,280,280,280
BEGIN DESCRIPTION:
X18250
END DESCRIPTION:
XS GIS Cut Line= 3
      2224588.85     13809824.19      2224769.94     13809862.49
      2225104.19     13809810.27
#Sta/Elev= 30
    4809  878.04  4816.4  877.56  4856.2  875.16  4866.4  874.83  4897.1  872.84
  4907.3  872.56  4917.5  871.81  4948.2  870.46    4983  868.45    4989  867.73
  4994.1  867.73  4999.2  866.94  5017.5  865.98  5017.7  865.48  5021.2  865.48
  5021.5  865.98  5029.6  866.25  5039.7  868.12  5059.9   869.8  5080.2  871.87
  5100.4  872.53  5120.7  873.88  5142.9  874.82  5161.2  875.23  5171.3  875.86
  5191.5  876.27  5205.6  876.98  5221.9   878.6  5292.7  880.83  5332.4  882.91
#Mann= 4 ,-1 , 0
    4809    .035       0  4816.4     .12       0  5017.5     .05       0
  5021.5     .12       0
Bank Sta=5017.5,5021.5
XS Rating Curve= 0 ,0
Exp/Cntr=0.3,0.1

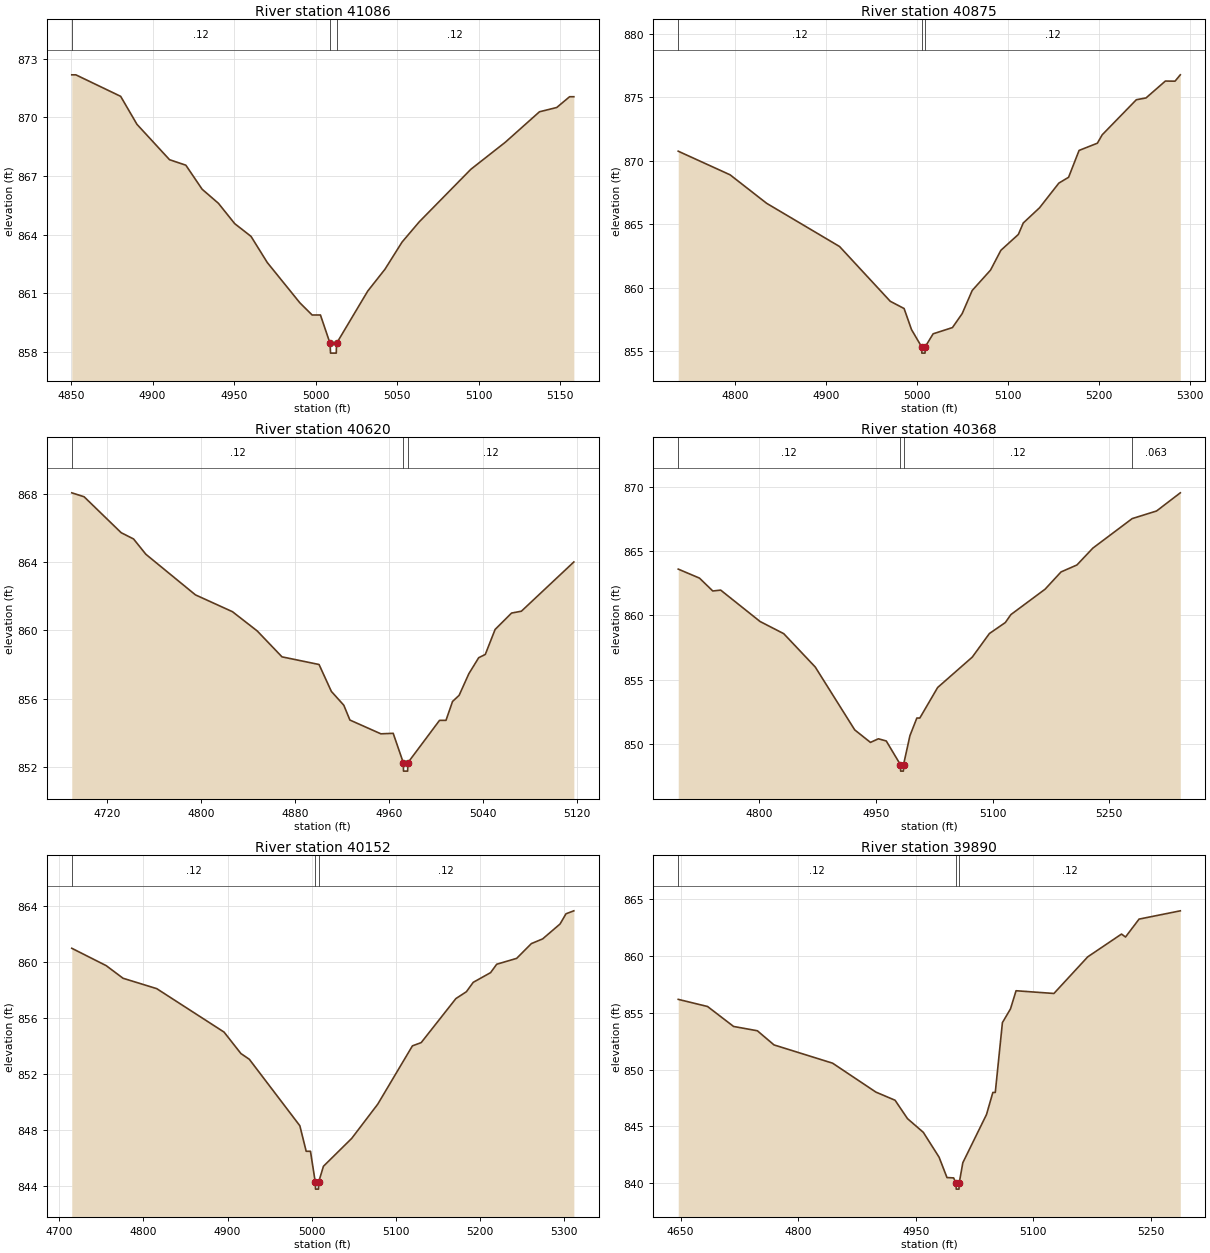
Type RM Length L Ch R = 1 ,41086   ,211,211,211
BEGIN DESCRIPTION:
Blieders Creek 81.0
END DESCRIPTION:
XS GIS Cut Line= 3
        2224675.       13810125.        2224825.       13810125.
      2224974.98     13810075.01
#Sta/Elev= 28
  4850.4  872.17  4852.9  872.17  4880.4  871.07  4890.4  869.64  4910.4  867.83
  4920.4  867.55  4930.4  866.32  4940.4   865.6  4950.4  864.56  4960.4  863.91
  4970.4  862.57  4990.4  860.51  4997.9  859.89    5003  859.89  5008.9  858.44
  5009.2  857.94  5012.7  857.94  5012.9  858.44    5032  861.11  5042.6  862.23
  5053.1  863.62  5063.6  864.65  5095.3  867.34  5116.4  868.72  5137.4  870.28
    5148   870.5  5155.9  871.05  5158.5  871.05
#Mann= 3 ,-1 , 0
  4850.4     .12       0  5008.9     .05       0  5012.9     .12       0
Bank Sta=5008.9,5012.9
XS Rating Curve= 0 ,0
Exp/Cntr=0.3,0.1

Type RM Length L Ch R = 1 ,40875   ,255,255,255
BEGIN DESCRIPTION:
X18252
END DESCRIPTION:
XS GIS Cut Line= 3
      2224648.02     13810308.18      2224881.36     13810318.63
      2225180.45     13810210.82
#Sta/Elev= 30
  4737.6  870.74  4794.6  868.88  4834.7  866.64  4914.8  863.24  4970.5  858.93
  4985.7  858.36  4993.8  856.71  5004.9  855.35  5005.2  854.85  5008.7  854.85
  5008.9  855.35  5017.6  856.37  5038.8  856.86  5049.5  857.96  5060.5  859.78
  5080.6  861.38    5092  862.94  5111.2  864.19  5116.6  865.09  5134.5  866.29
  5155.7  868.23  5166.4  868.69  5177.9   870.8    5198  871.37  5203.3  872.03
  5240.8  874.79  5251.4  874.93  5272.7  876.26  5283.3  876.25  5289.1  876.75
#Mann= 3 ,-1 , 0
  4737.6     .12       0  5004.9     .05       0  5008.9     .12       0
Bank Sta=5004.9,5008.9
XS Rating Curve= 0 ,0
Exp/Cntr=0.3,0.1

Type RM Length L Ch R = 1 ,40620   ,252,252,252
BEGIN DESCRIPTION:
Blieders Creek 80.0
END DESCRIPTION:
XS GIS Cut Line= 3
      2224725.04     13810425.01        2225025.       13810525.
      2225125.01     13810474.99
#Sta/Elev= 30
  4689.6  868.08  4700.1  867.85  4731.7  865.74  4742.3  865.37  4752.8  864.47
    4795  862.09  4826.6   861.1  4847.7  859.97  4868.8  858.45  4900.4     858
  4910.9  856.42  4921.5  855.61  4926.7  854.74  4953.1  853.93  4963.6  853.96
  4972.2  852.24  4972.4  851.74  4975.9  851.74  4976.2  852.24  5003.1  854.72
  5008.6  854.72  5014.2  855.83  5019.8  856.19  5028.1  857.46  5036.5   858.4
  5042.1  858.59  5050.5  860.06  5064.5  861.02  5072.9  861.13  5117.6  864.02
#Mann= 3 ,-1 , 0
  4689.6     .12       0  4972.2     .05       0  4976.2     .12       0
Bank Sta=4972.2,4976.2
XS Rating Curve= 0 ,0
Exp/Cntr=0.3,0.1

Type RM Length L Ch R = 1 ,40368   ,216,216,216
BEGIN DESCRIPTION:
X18251
END DESCRIPTION:
XS GIS Cut Line= 3
      2224721.14     13810726.01       2225027.6     13810774.77
      2225354.86     13810705.14
#Sta/Elev= 30
  4696.3  863.59  4723.6  862.89  4740.7  861.89  4750.8  861.96  4801.5  859.52
  4831.8  858.58  4872.3  855.99    4923  851.11  4943.2  850.14  4953.4  850.42
  4963.5  850.25  4981.7  848.41    4982  847.91  4985.5  847.91  4985.7  848.41
  4993.9  850.66  5002.8  852.03  5006.6  852.03  5029.5   854.4    5074  856.76
    5096  858.59  5116.4  859.44  5123.6  860.06  5167.5  862.03    5188  863.37
  5208.4  863.91  5228.9  865.22  5279.4  867.51  5310.7   868.1  5341.2  869.51
#Mann= 4 ,-1 , 0
  4696.3     .12       0  4981.7     .05       0  4985.7     .12       0
  5279.4    .063       0
Bank Sta=4981.7,4985.7
XS Rating Curve= 0 ,0
Exp/Cntr=0.3,0.1

Type RM Length L Ch R = 1 ,40152   ,262,262,262
BEGIN DESCRIPTION:
Blieders Creek 79.0
END DESCRIPTION:
XS GIS Cut Line= 3
      2224694.12      13810970.1        2224975.       13810975.
      2225280.88      13810898.2
#Sta/Elev= 30
  4714.9  860.99  4755.8  859.75  4775.8  858.85  4815.8  858.11  4895.8  855.01
  4915.8  853.48  4925.8  853.07  4985.8  848.33  4993.3  846.51  4998.4  846.51
  5004.1  844.31  5004.4  843.81  5007.9  843.81  5008.1  844.31  5013.8  845.44
  5047.4  847.43  5078.3  849.87  5119.5  854.03  5129.9  854.26  5171.1   857.4
  5183.6  857.89  5191.7  858.56  5212.3  859.25  5219.6  859.85  5243.3  860.27
  5260.7  861.32  5274.2  861.66  5294.8  862.72  5301.9  863.45  5311.2  863.66
#Mann= 3 ,-1 , 0
  4714.9     .12       0  5004.1     .05       0  5008.1     .12       0
Bank Sta=5004.1,5008.1
XS Rating Curve= 0 ,0
Exp/Cntr=0.3,0.1

Type RM Length L Ch R = 1 ,39890   ,314,314,314
BEGIN DESCRIPTION:
Blieders Creek 78.0
END DESCRIPTION:
XS GIS Cut Line= 3
      2224674.96       13811175.      2225076.11      13811226.3
      2225306.26     13811174.14
#Sta/Elev= 30
  4647.1  856.19  4684.5  855.56  4717.7   853.8    4748  853.42  4769.3  852.17
    4844  850.56  4899.2  848.01  4923.7  847.29  4939.5  845.67  4959.7  844.46
  4979.8  842.27  4989.9  840.47  4998.4  840.44  5001.4  839.95  5001.7  839.45
  5005.2  839.45  5005.4  839.95  5010.1  841.78  5040.3  846.03  5048.4  847.98
  5051.5  847.98  5060.6  854.14  5070.9  855.35    5078  856.95  5126.3  856.71
  5169.4  859.94  5212.5  861.95  5217.6  861.69  5234.9  863.27  5287.5     864
#Mann= 3 ,-1 , 0
  4647.1     .12       0  5001.4     .05       0  5005.4     .12       0
Bank Sta=5001.4,5005.4
XS Rating Curve= 0 ,0
Exp/Cntr=0.3,0.1

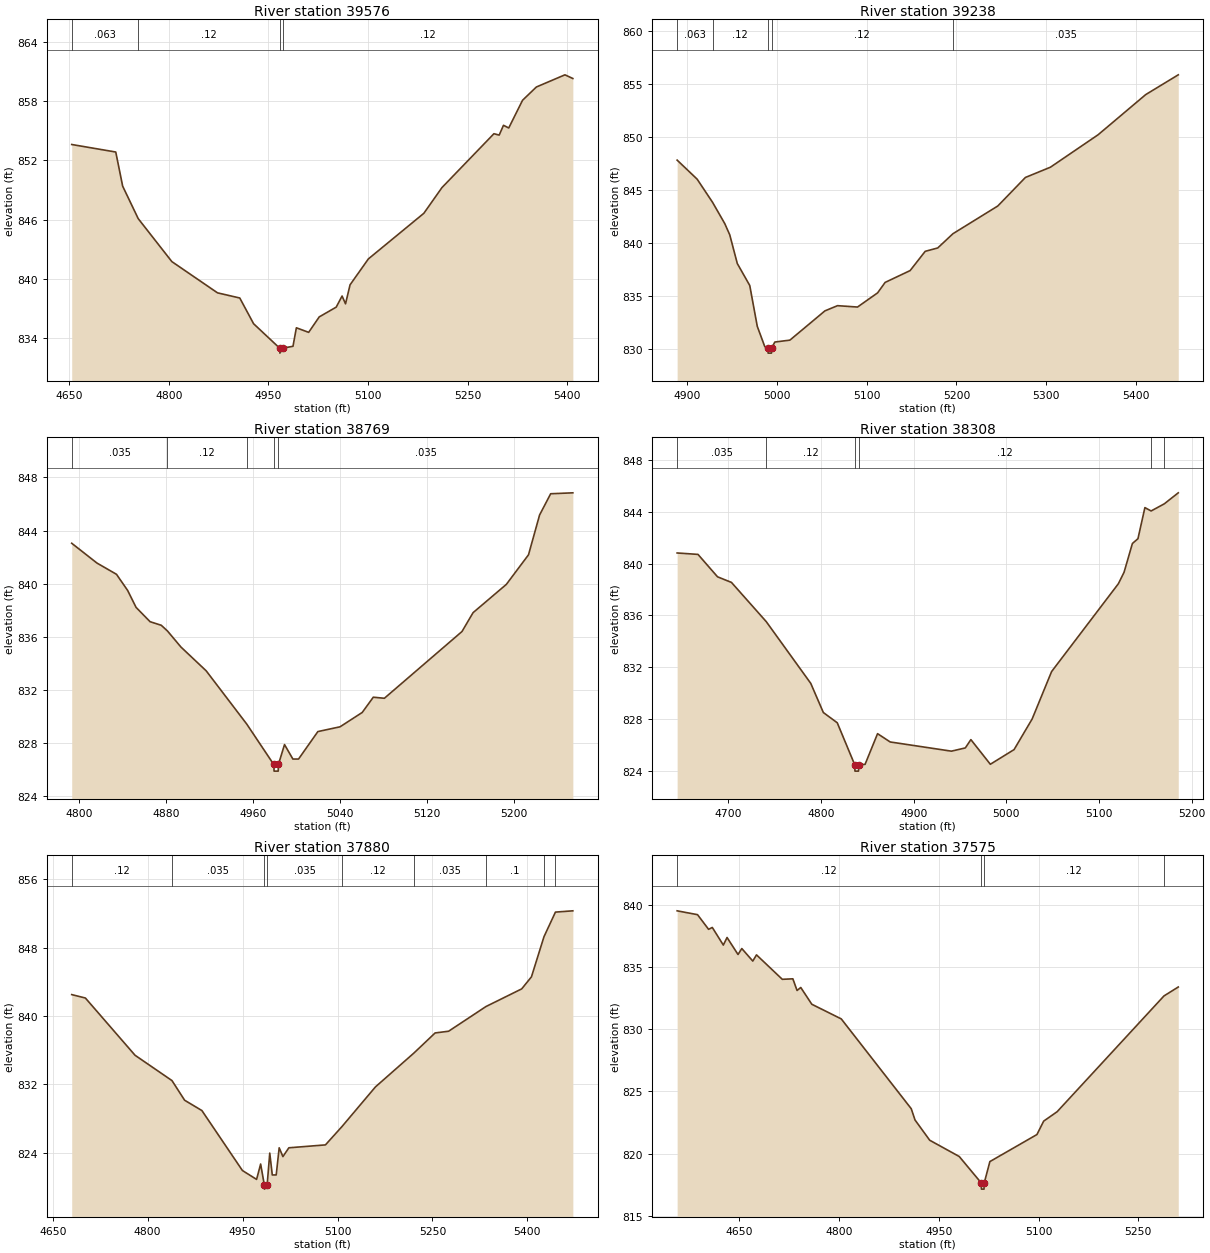
Type RM Length L Ch R = 1 ,39576   ,338,338,338
BEGIN DESCRIPTION:
X18255
END DESCRIPTION:
XS GIS Cut Line= 3
      2224591.04     13811588.98      2225064.12     13811458.77
      2225268.14     13811291.65
#Sta/Elev= 30
  4653.8   853.6  4720.1  852.84  4730.5  849.39  4753.9  846.11  4804.5  841.77
  4873.3  838.61  4906.8  838.09  4927.6  835.49  4966.9  833.02  4967.2  832.52
  4971.2  833.02  4986.9  833.21    4992  835.08  5010.5  834.62  5026.4  836.18
    5052  837.17  5060.8  838.29    5066   837.5  5072.8  839.42  5100.4  842.04
  5183.9  846.65  5211.2  849.25  5289.4  854.69  5297.3  854.55  5303.8  855.54
  5311.7  855.27  5332.5  858.07  5353.3  859.41  5396.3  860.64  5408.2  860.27
#Mann= 4 ,-1 , 0
  4653.8    .063       0  4753.9     .12       0  4966.9     .05       0
  4971.2     .12       0
Bank Sta=4966.9,4971.2
XS Rating Curve= 0 ,0
Exp/Cntr=0.3,0.1

Type RM Length L Ch R = 1 ,39238   ,469,469,469
BEGIN DESCRIPTION:
Blieders Creek 77.0
END DESCRIPTION:
XS GIS Cut Line= 3
      2225025.01     13811874.98        2225075.       13811775.
        2225275.       13811375.
#Sta/Elev= 30
  4888.5  847.83  4910.8  846.03    4928  843.84  4941.6  841.83  4947.2  840.76
  4955.6  838.05  4969.5  835.97  4977.9   832.1  4986.3  830.18  4989.7  830.07
    4990  829.57  4993.7  829.57    4994  830.07  4997.5  830.62  5014.3   830.8
  5053.4  833.57  5067.4  834.06  5089.7  833.93  5112.1  835.27  5120.5  836.26
  5148.4  837.38  5165.2   839.2  5179.2  839.52  5196.2  840.87  5246.2  843.49
    5277  846.19  5304.9  847.16  5358.1  850.23  5411.2  854.03  5447.5   855.9
#Mann= 5 ,-1 , 0
  4888.5    .063       0    4928     .12       0  4989.7     .05       0
    4994     .12       0  5196.2    .035       0
Bank Sta=4989.7,4994
XS Rating Curve= 0 ,0
Exp/Cntr=0.3,0.1

Type RM Length L Ch R = 1 ,38769   ,461,461,461
BEGIN DESCRIPTION:
Blieders Creek 76.0
END DESCRIPTION:
XS GIS Cut Line= 3
      2225475.01     13812024.97        2225525.       13811825.
        2225575.     13811574.98
#Sta/Elev= 30
  4793.5  843.04  4816.7  841.55  4834.7   840.7    4845  839.48  4852.7  838.21
  4865.6  837.13  4875.9  836.86  4881.6  836.43    4894  835.22  4917.2  833.43
  4954.6  829.41  4979.4  826.37  4979.7  825.87  4983.5  825.87  4983.7  826.37
  4989.3  827.87    4997  826.78  5002.2  826.78    5020  828.85  5040.4  829.21
  5060.8  830.29    5071  831.44  5081.2  831.36  5152.6  836.39  5162.8  837.81
  5193.4  839.94  5213.8  842.17    5224  845.17  5234.2  846.77  5254.6  846.84
#Mann= 5 ,-1 , 0
  4793.5    .035       0  4881.6     .12       0  4954.6    .035       0
  4979.4    .035       0  4983.7    .035       0
Bank Sta=4979.4,4983.7
XS Rating Curve= 0 ,0
Exp/Cntr=0.3,0.1

Type RM Length L Ch R = 1 ,38308   ,428,428,428
BEGIN DESCRIPTION:
Blieders Creek 75.0
END DESCRIPTION:
XS GIS Cut Line= 3
      2225624.99       13812125.        2225925.       13811925.
      2226024.98     13811775.03
#Sta/Elev= 30
  4644.7  840.82  4667.2  840.71  4688.3  838.98  4703.3  838.55  4740.9  835.52
  4788.9  830.76  4802.5  828.51  4817.5  827.72  4836.3  824.49  4836.6  823.99
  4840.4  823.99  4840.7  824.49  4847.5  824.51    4861  826.88  4874.6  826.24
  4940.7  825.53  4955.7  825.78  4961.7  826.42  4982.7  824.52  5008.3  825.65
  5027.8  828.01  5048.8  831.67  5120.9  838.45    5127  839.33    5136  841.55
    5142  841.92  5149.5  844.32  5156.2  844.06  5170.4  844.61  5185.5  845.46
#Mann= 6 ,-1 , 0
  4644.7    .035       0  4740.9     .12       0  4836.3     .05       0
  4840.7     .12       0  5156.2    .035       0  5170.4      .1       0
Bank Sta=4836.3,4840.7
XS Rating Curve= 0 ,0
Exp/Cntr=0.3,0.1

Type RM Length L Ch R = 1 ,37880   ,305,305,305
BEGIN DESCRIPTION:
Blieders Creek 74.0
END DESCRIPTION:
XS GIS Cut Line= 3
      2225825.04     13812474.97        2226075.       13812275.
        2226325.     13811875.01
#Sta/Elev= 30
    4680  842.51  4701.6  842.11    4780  835.41  4838.4  832.44  4858.4  830.14
  4885.7  828.93  4949.7  821.91  4972.1  820.87  4978.5  822.67  4984.3  820.23
  4984.6  819.73  4988.8  820.23  4992.9  823.95  4996.9  821.39  5003.1  821.39
  5007.8  824.57  5013.7  823.54  5023.1  824.57  5080.9  824.91  5106.7  827.03
  5159.9   831.7  5220.6  835.66  5254.2  838.02  5275.5  838.22  5334.5  841.11
    5391  843.18  5406.4  844.59  5426.2  849.29  5444.3  852.17  5471.8  852.32
#Mann= 9 ,-1 , 0
    4680     .12       0  4838.4    .035       0  4984.3    .035       0
  4988.8    .035       0  5106.7     .12       0  5220.6    .035       0
  5334.5      .1       0  5426.2    .063       0  5444.3    .035       0
Bank Sta=4984.3,4988.8
XS Rating Curve= 0 ,0
Exp/Cntr=0.3,0.1

Type RM Length L Ch R = 1 ,37575   ,150,150,150
BEGIN DESCRIPTION:
Blieders Creek 73.0
END DESCRIPTION:
XS GIS Cut Line= 3
      2225880.12     13812682.71      2226277.23     13812478.74
        2226325.       13812175.
#Sta/Elev= 30
  4556.3  839.56    4587  839.25  4603.6  838.07  4609.2  838.22  4625.8   836.8
  4631.4  837.41  4647.9  836.04  4653.6  836.52  4670.1  835.51  4675.7  836.01
  4714.5  834.04  4730.4  834.08  4736.7  833.14  4742.3  833.38  4758.9  832.03
  4803.2  830.85  4908.5  823.61  4914.2   822.7  4936.3  821.07  4980.7  819.76
  5013.8  817.63  5014.1  817.13    5018  817.13  5018.3  817.63  5026.8  819.35
  5097.6  821.53  5107.7  822.61    5128  823.37  5288.7   832.7  5310.2  833.42
#Mann= 4 ,-1 , 0
  4556.3     .12       0  5013.8     .05       0  5018.3     .12       0
  5288.7    .035       0
Bank Sta=5013.8,5018.3
XS Rating Curve= 0 ,0
Exp/Cntr=0.3,0.1

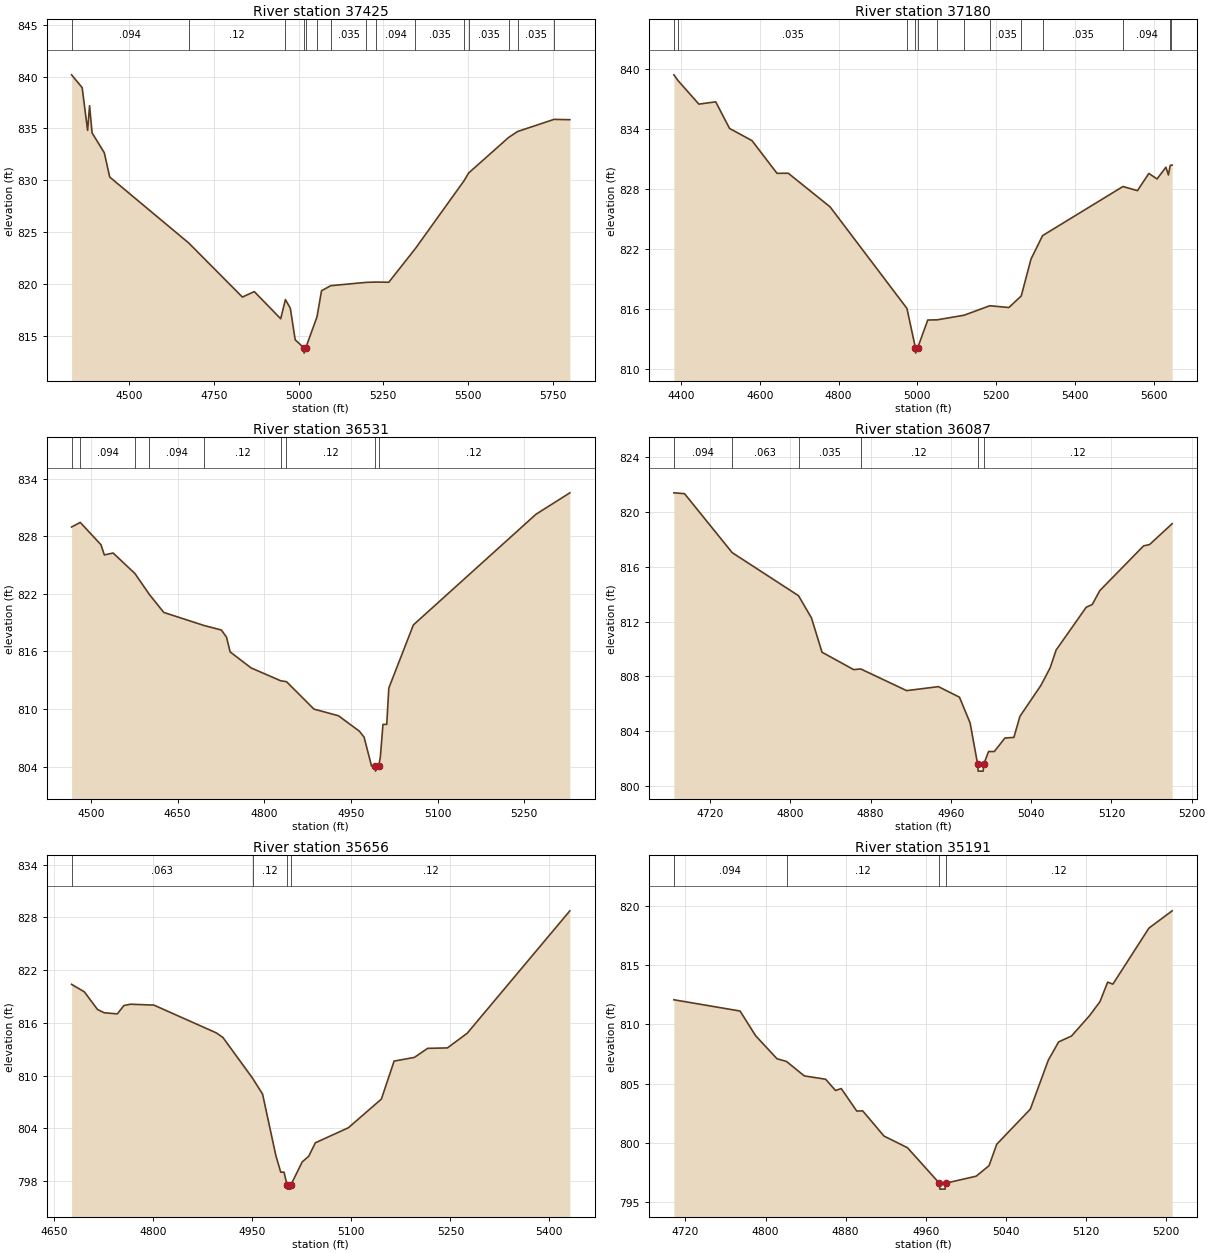
Type RM Length L Ch R = 1 ,37425   ,245,245,245
BEGIN DESCRIPTION:
X18256
END DESCRIPTION:
XS GIS Cut Line= 4
      2225945.22     13812997.98      2226019.86     13812862.59
       2226733.4     13812244.53      2226994.99     13811979.48
#Sta/Elev= 30
  4329.6  840.18  4360.9  838.94  4376.9  834.82  4382.7   837.2  4390.1  834.58
  4426.2  832.66  4442.3  830.31  4675.8  823.94  4833.9  818.73    4869  819.26
  4946.9  816.64  4960.9  818.49  4975.4  817.65  4989.7  814.61  5015.6  813.82
    5016  813.32  5020.8  813.82  5054.1  816.82  5067.5  819.34  5094.7  819.83
  5199.4  820.15  5228.5  820.18    5266  820.16  5344.7  823.42  5488.5  829.97
  5501.6   830.7  5619.6  834.13  5646.3  834.71  5753.9  835.88  5800.6  835.85
#Mann= 15 ,-1 , 0
  4329.6    .094       0  4675.8     .12       0  4960.9    .035       0
  5015.6    .035       0  5020.8    .035       0  5054.1     .12       0
  5094.7    .035       0  5199.4     .12       0  5228.5    .094       0
  5344.7    .035       0  5488.5     .12       0  5501.6    .035       0
  5619.6    .094       0  5646.3    .035       0  5753.9     .12       0
Bank Sta=5015.6,5020.8
XS Rating Curve= 0 ,0
Exp/Cntr=0.3,0.1

Type RM Length L Ch R = 1 ,37180   ,649,649,649
BEGIN DESCRIPTION:
Blieders Creek 72.0
END DESCRIPTION:
XS GIS Cut Line= 3
      2226170.91     13812980.64      2226903.54     13812345.23
      2227085.86     13812112.55
#Sta/Elev= 30
  4381.6  839.39  4392.7  838.79  4445.1  836.46  4487.9  836.69    4523  834.03
    4580  832.81  4643.6  829.54  4672.1  829.55  4778.5  826.18  4973.5  816.03
  4995.2  812.06  4995.6  811.56  5000.5  812.06  5026.3  814.87  5050.2  814.89
  5118.6  815.35    5184   816.3  5232.4  816.12  5263.8  817.28  5288.4  820.95
  5317.9  823.31    5522  828.22  5558.9  827.81  5587.8  829.53  5608.6  828.98
  5631.2  830.15  5637.5  829.38    5642  830.32  5644.2  830.36    5647  830.36
#Mann= 13 ,-1 , 0
  4381.6    .094       0  4392.7    .035       0  4973.5    .094       0
  4995.2     .05       0  5000.5    .094       0  5050.2    .035       0
  5118.6    .094       0    5184    .035       0  5263.8    .094       0
  5317.9    .035       0    5522    .094       0    5642    .035       0
  5644.2    .094       0
Bank Sta=4995.2,5000.5
XS Rating Curve= 0 ,0
Exp/Cntr=0.3,0.1

Type RM Length L Ch R = 1 ,36531   ,444,444,444
BEGIN DESCRIPTION:
Blieders Creek 71.0
END DESCRIPTION:
XS GIS Cut Line= 3
      2226769.87     13812969.17        2227225.       13812675.
      2227457.77     13812454.87
#Sta/Elev= 30
  4466.5  828.95  4481.5  829.43  4517.3  827.11  4523.2  826.04  4538.4  826.24
  4576.2   824.1  4601.3  821.91  4626.1  820.05  4695.8  818.69  4725.7  818.22
  4734.6  817.48  4740.9  815.94  4777.2  814.27  4828.5  812.93  4838.4  812.84
    4886  809.98  4928.3  809.29  4964.6  807.68  4972.7  807.06  4985.7  804.03
  4991.9  804.02  4992.4  803.52  4997.8  804.02  5000.8  804.97  5005.4  808.39
  5011.9  808.39  5015.5  812.17    5058  818.75    5270  830.27  5328.8  832.51
#Mann= 9 ,-1 , 0
  4466.5    .063       0  4481.5    .094       0  4576.2    .063       0
  4601.3    .094       0  4695.8     .12       0  4828.5    .094       0
  4838.4     .12       0  4991.9     .05       0  4997.8     .12       0
Bank Sta=4991.9,4997.8
XS Rating Curve= 0 ,0
Exp/Cntr=0.3,0.1

Type RM Length L Ch R = 1 ,36087   ,431,431,431
BEGIN DESCRIPTION:
Blieders Creek 70.0
END DESCRIPTION:
XS GIS Cut Line= 3
      2227374.99     13813325.03        2227475.       13813025.
      2227574.98     13812875.03
#Sta/Elev= 30
    4684  821.39  4694.6  821.33  4742.1  817.03  4808.2  813.89  4821.1  812.27
  4831.6  809.77  4863.2   808.5  4870.2  808.55  4915.9  806.97  4947.6  807.26
  4968.6  806.49  4979.2  804.61  4986.7   801.6  4987.2   801.1  4992.2   801.1
  4992.7   801.6  4997.6  802.53  5003.3  802.53  5013.8  803.51  5022.8  803.56
  5028.8  805.09  5049.8  807.36  5058.9  808.63  5064.9  809.93  5094.9  813.05
  5100.9  813.25  5108.4  814.26    5152  817.52    5158  817.62  5180.5  819.14
#Mann= 6 ,-1 , 0
    4684    .094       0  4742.1    .063       0  4808.2    .035       0
  4870.2     .12       0  4986.7     .05       0  4992.7     .12       0
Bank Sta=4986.7,4992.7
XS Rating Curve= 0 ,0
Exp/Cntr=0.3,0.1

Type RM Length L Ch R = 1 ,35656   ,465,465,465
BEGIN DESCRIPTION:
Blieders Creek 69.0
END DESCRIPTION:
XS GIS Cut Line= 3
      2227833.22     13813544.26        2227825.       13813225.
      2227837.54     13812789.55
#Sta/Elev= 30
    4676  820.39  4695.3  819.54  4715.3  817.53  4725.3  817.16  4745.3  817.03
  4755.3  817.98  4765.3  818.13  4800.7  818.03  4895.3  814.87  4905.3  814.35
  4950.2  809.72  4965.4  807.91  4985.4  800.96  4992.9  799.03  4997.9  799.03
  5002.4   797.6  5002.9   797.1  5007.9   797.1  5008.4   797.6  5025.4  800.19
  5035.4  800.85  5045.4  802.37  5095.4  804.08  5145.4  807.34  5164.7  811.66
  5195.4  812.08  5215.5  813.11  5245.5  813.16  5275.5  814.83    5431  828.75
#Mann= 4 ,-1 , 0
    4676    .063       0  4950.2     .12       0  5002.4     .05       0
  5008.4     .12       0
Bank Sta=5002.4,5008.4
XS Rating Curve= 0 ,0
Exp/Cntr=0.3,0.1

Type RM Length L Ch R = 1 ,35191   ,455,455,455
BEGIN DESCRIPTION:
Blieders Creek 68.0
END DESCRIPTION:
XS GIS Cut Line= 3
      2228124.99     13813425.02        2228275.       13813175.
      2228324.99     13812975.03
#Sta/Elev= 30
  4708.4  812.08  4774.5  811.13  4790.1  809.04  4811.4   807.1  4820.9  806.87
  4838.7  805.65    4860  805.37  4869.8  804.42  4875.6  804.58  4891.1  802.68
    4897   802.7  4918.3  800.57  4941.7  799.59  4973.6  796.59  4974.1  796.09
  4979.3  796.09  4979.8  796.59  5010.3  797.18  5023.2  798.07  5030.9  799.88
  5064.4  802.84  5082.4  806.98  5092.7  808.52  5105.6  809.02  5123.7  810.75
    5134  811.92  5141.7  813.57  5146.9   813.4  5182.9  818.13  5206.1  819.59
#Mann= 4 ,-1 , 0
  4708.4    .094       0  4820.9     .12       0  4973.6     .05       0
  4979.8     .12       0
Bank Sta=4973.6,4979.8
XS Rating Curve= 0 ,0
Exp/Cntr=0.3,0.1

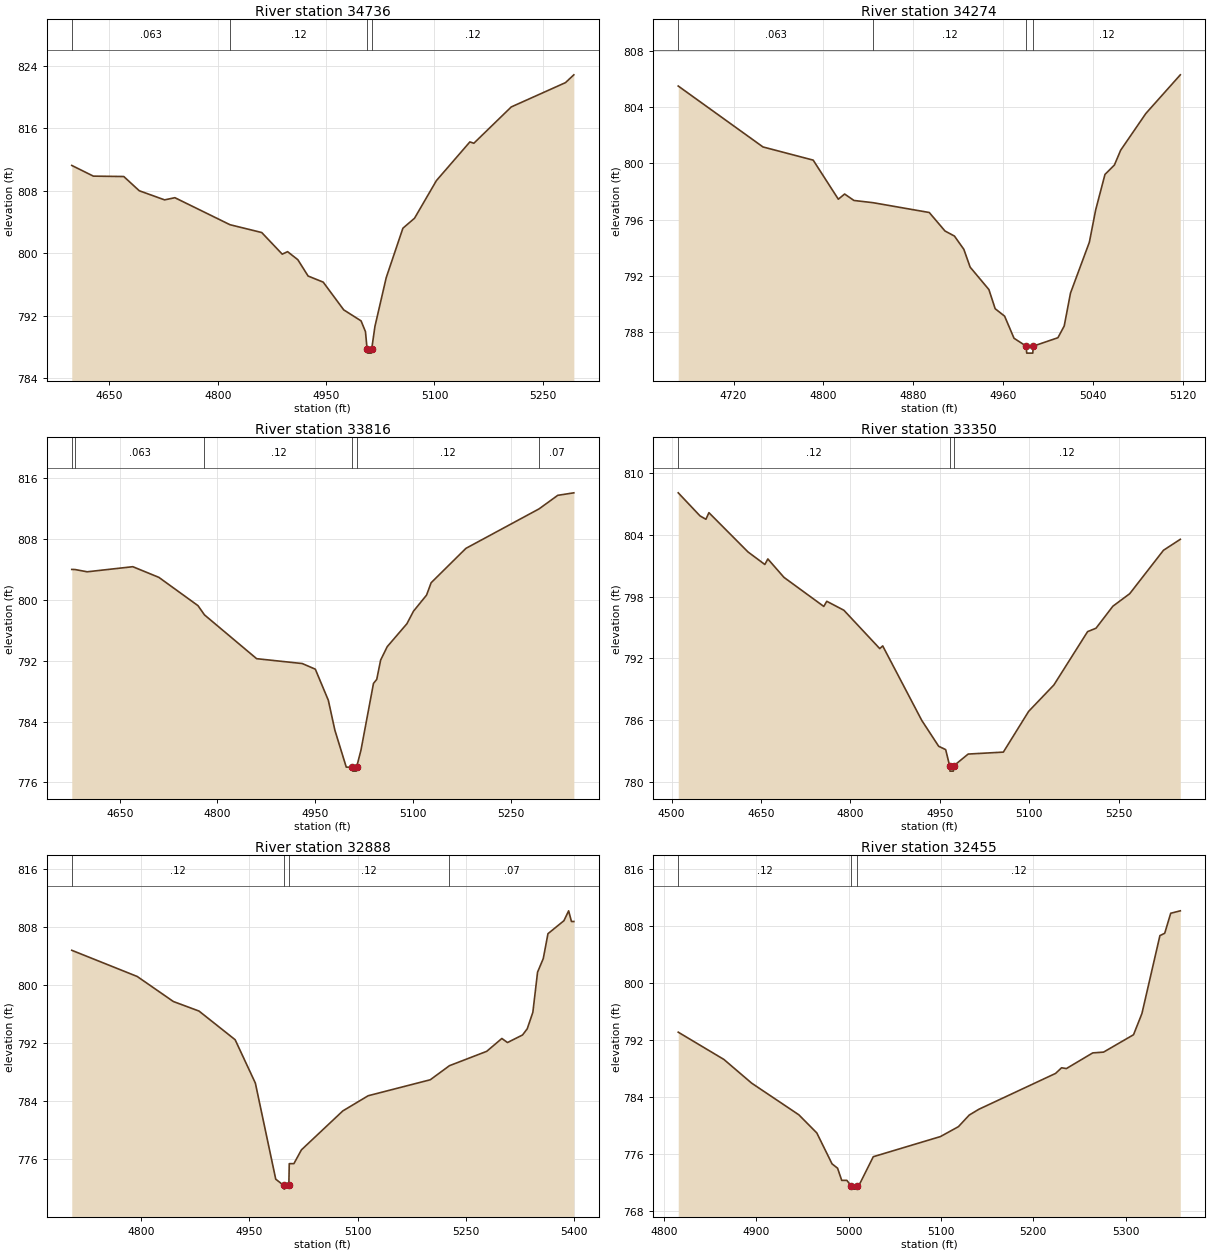
Type RM Length L Ch R = 1 ,34736   ,462,462,462
BEGIN DESCRIPTION:
Blieders Creek 67.0
END DESCRIPTION:
XS GIS Cut Line= 3
      2228406.16     13813618.03        2228675.       13813325.
      2228796.74     13813053.85
#Sta/Elev= 30
    4598  811.22  4627.9  809.85    4670   809.8  4691.4  807.98  4726.5  806.81
  4740.7  807.09    4817  803.63  4860.9  802.63  4889.3  799.86  4896.7  800.18
  4910.9  799.15  4925.1  797.06    4946  796.28  4974.4  792.73  4998.4  791.32
  5004.5  789.94  5006.8  787.69  5007.3  787.19  5012.6  787.19  5013.1  787.69
  5017.6  790.61  5033.2  796.85  5056.3  803.18  5072.4  804.46  5102.7  809.28
    5149  814.23  5154.5  814.06  5206.3  818.71  5281.3  821.82  5292.9  822.82
#Mann= 4 ,-1 , 0
    4598    .063       0    4817     .12       0  5006.8     .05       0
  5013.1     .12       0
Bank Sta=5006.8,5013.1
XS Rating Curve= 0 ,0
Exp/Cntr=0.3,0.1

Type RM Length L Ch R = 1 ,34274   ,458,458,458
BEGIN DESCRIPTION:
Blieders Creek 66.0
END DESCRIPTION:
XS GIS Cut Line= 3
      2228724.99     13813725.01        2229025.       13813575.
      2229124.97     13813525.01
#Sta/Elev= 30
  4670.7  805.53  4746.2  801.18  4790.9  800.24  4813.3  797.45  4818.9  797.82
  4827.2  797.36  4844.3   797.2  4894.3   796.5  4908.3  795.18  4916.7  794.82
  4925.1  793.87  4930.7   792.6  4947.4     791    4953  789.63  4961.4   789.1
  4969.8  787.52  4980.6  786.96  4981.1  786.46  4986.5  786.46    4987  786.96
  5008.9  787.56  5014.5   788.4  5020.1  790.75  5036.9  794.38  5042.5  796.68
  5050.8  799.22  5059.2  799.89  5064.8  800.95  5087.2  803.57  5117.9  806.33
#Mann= 4 ,-1 , 0
  4670.7    .063       0  4844.3     .12       0  4980.6     .05       0
    4987     .12       0
Bank Sta=4980.6,4987
XS Rating Curve= 0 ,0
Exp/Cntr=0.3,0.1

Type RM Length L Ch R = 1 ,33816   ,466,466,466
BEGIN DESCRIPTION:
Blieders Creek 65.0
END DESCRIPTION:
XS GIS Cut Line= 3
      2228651.32     13813989.15        2229075.       13813975.
      2229419.56      13813934.9
#Sta/Elev= 30
  4576.4  803.99  4581.3  803.98  4600.1  803.68  4670.1  804.35  4710.1  802.95
  4770.2  799.23  4780.1  798.02  4860.2  792.26  4930.3  791.62  4950.3  790.88
  4970.3  786.79  4980.3  782.87  4997.8  778.01  5007.1  777.98  5007.6  777.48
  5013.1  777.48  5013.6  777.98  5020.4  780.24  5039.6  789.01  5044.6  789.54
  5050.6  792.08  5060.7  793.84  5090.9  796.85    5101   798.5  5121.1  800.62
  5128.1  802.24  5181.5  806.76  5293.8  811.95  5322.5  813.73  5347.2  814.06
#Mann= 6 ,-1 , 0
  4576.4     .12       0  4581.3    .063       0  4780.1     .12       0
  5007.1     .05       0  5013.6     .12       0  5293.8     .07       0
Bank Sta=5007.1,5013.6
XS Rating Curve= 0 ,0
Exp/Cntr=0.3,0.1

Type RM Length L Ch R = 1 ,33350   ,462,462,462
BEGIN DESCRIPTION:
Blieders Creek 64.0
END DESCRIPTION:
XS GIS Cut Line= 3
      2228538.49     13814475.27        2229025.       13814425.
      2229275.03     13814174.97
#Sta/Elev= 30
    4511  808.09  4547.7  805.84  4557.5  805.52  4562.5  806.16  4628.1  802.34
  4656.4  801.12  4661.4  801.66  4688.4  799.87  4755.3  797.04  4760.3  797.54
    4789  796.67  4849.2  792.94  4854.2   793.2  4919.7  785.96  4948.1  783.44
  4959.9  783.11  4966.6  781.52  4967.1  781.02  4972.7  781.02  4973.2  781.52
  4997.6  782.68  5056.7  782.87  5099.1  786.83  5141.5   789.4  5198.1  794.59
  5212.2  794.92  5240.5  797.06  5268.8  798.28  5325.4   802.5  5353.7  803.57
#Mann= 3 ,-1 , 0
    4511     .12       0  4966.6     .05       0  4973.2     .12       0
Bank Sta=4966.6,4973.2
XS Rating Curve= 0 ,0
Exp/Cntr=0.3,0.1

Type RM Length L Ch R = 1 ,32888   ,433,433,433
BEGIN DESCRIPTION:
Blieders Creek 63.0
END DESCRIPTION:
XS GIS Cut Line= 3
      2228992.04     13815017.84        2229175.       13814775.
      2229475.03     13814524.97
#Sta/Elev= 30
  4704.6  804.78  4795.2  801.17  4845.2  797.72  4880.6  796.41  4930.6  792.46
  4958.6  786.48  4986.8  773.24  4997.9  772.37  4998.4  771.87  5004.9  772.37
  5005.5  775.38  5011.9  775.38  5022.3  777.28  5079.6  782.65  5114.7  784.74
  5200.6  786.94  5227.1  788.88  5278.7  790.86  5299.6  792.63  5307.4  792.07
  5328.2  793.11  5334.7  793.96  5342.5  796.24    5349  801.77  5356.9  803.64
  5363.4  807.07  5385.5  808.86    5392  810.22  5395.9  808.75  5399.2  808.75
#Mann= 4 ,-1 , 0
  4704.6     .12       0  4997.9     .05       0  5004.9     .12       0
  5227.1     .07       0
Bank Sta=4997.9,5004.9
XS Rating Curve= 0 ,0
Exp/Cntr=0.3,0.1

Type RM Length L Ch R = 1 ,32455   ,468,468,468
BEGIN DESCRIPTION:
Blieders Creek 62.0
END DESCRIPTION:
XS GIS Cut Line= 3
      2229425.02     13815124.97        2229525.       13814975.
      2229624.99     13814625.04
#Sta/Elev= 30
  4815.2  793.14  4864.7  789.31  4894.8  785.98  4945.9  781.54  4965.4  778.99
  4981.9  774.65  4987.9  774.04  4992.4  772.33    4998  772.33  5002.3   771.6
  5002.8   771.1  5008.9   771.1  5009.4   771.6  5012.3  771.94  5026.6  775.65
  5099.4  778.48  5118.9  779.87  5130.6   781.5    5141  782.31  5224.2  787.35
  5230.7  788.14  5235.9  788.03  5264.5  790.23  5276.2  790.34  5308.7  792.78
  5317.8  795.76  5337.3   806.7  5342.5  807.03    5349  809.84  5359.4  810.18
#Mann= 3 ,-1 , 0
  4815.2     .12       0  5002.3     .05       0  5009.4     .12       0
Bank Sta=5002.3,5009.4
XS Rating Curve= 0 ,0
Exp/Cntr=0.3,0.1