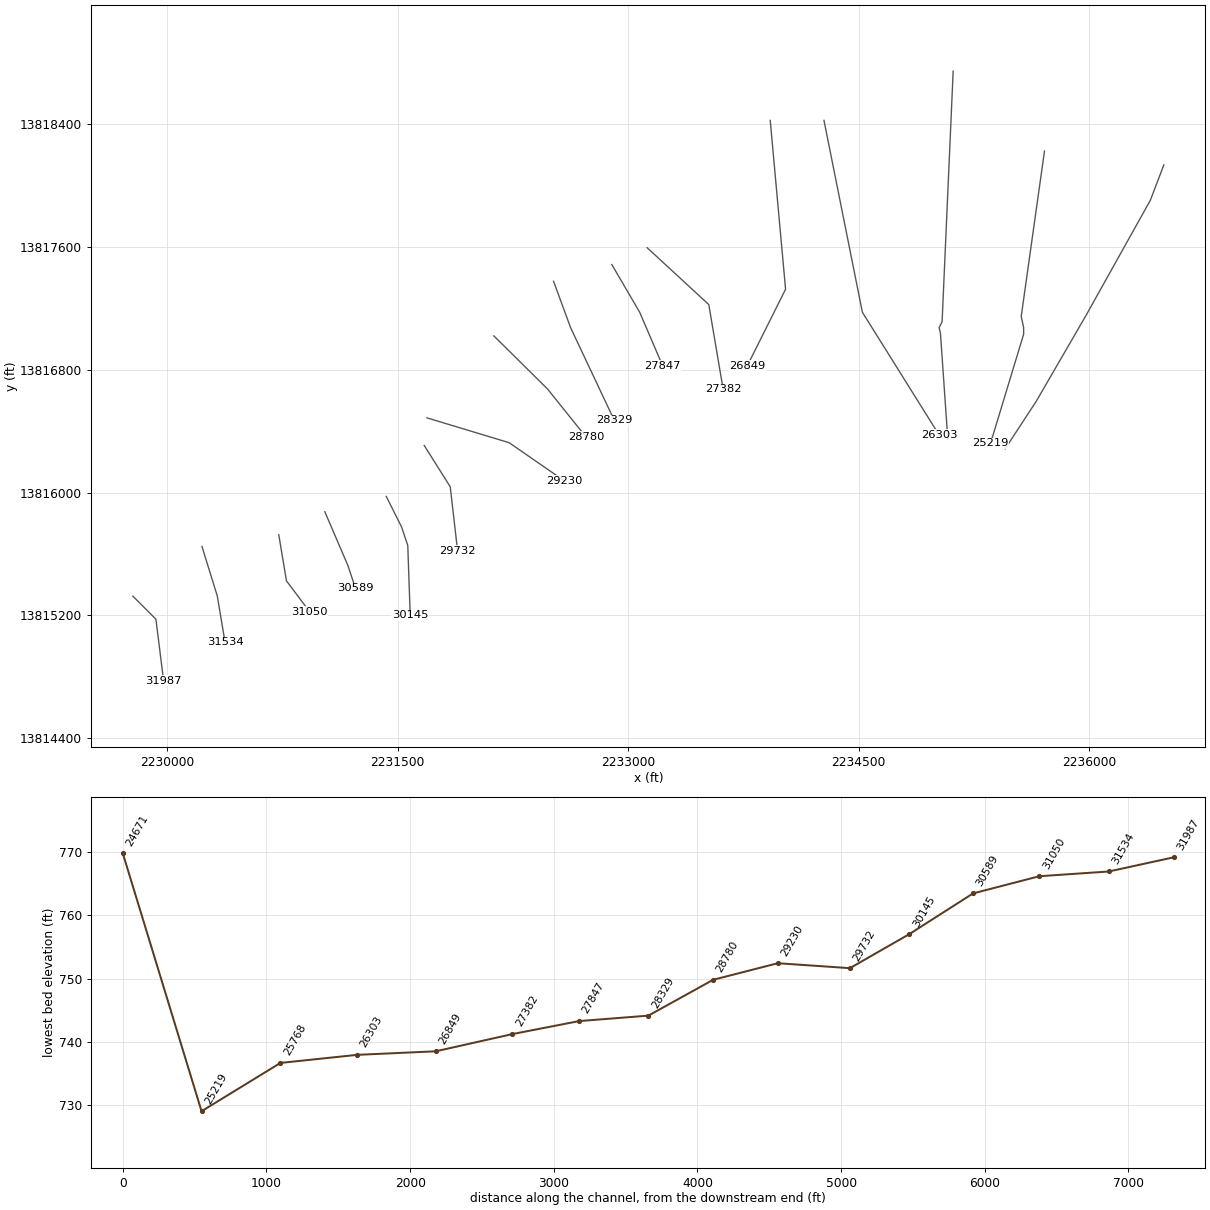
HEC-RAS study Blieders Creek.prj: Blieders Creek Base Level Engineering

--- Blieders Creek.g01 (geometry) --- (continued)

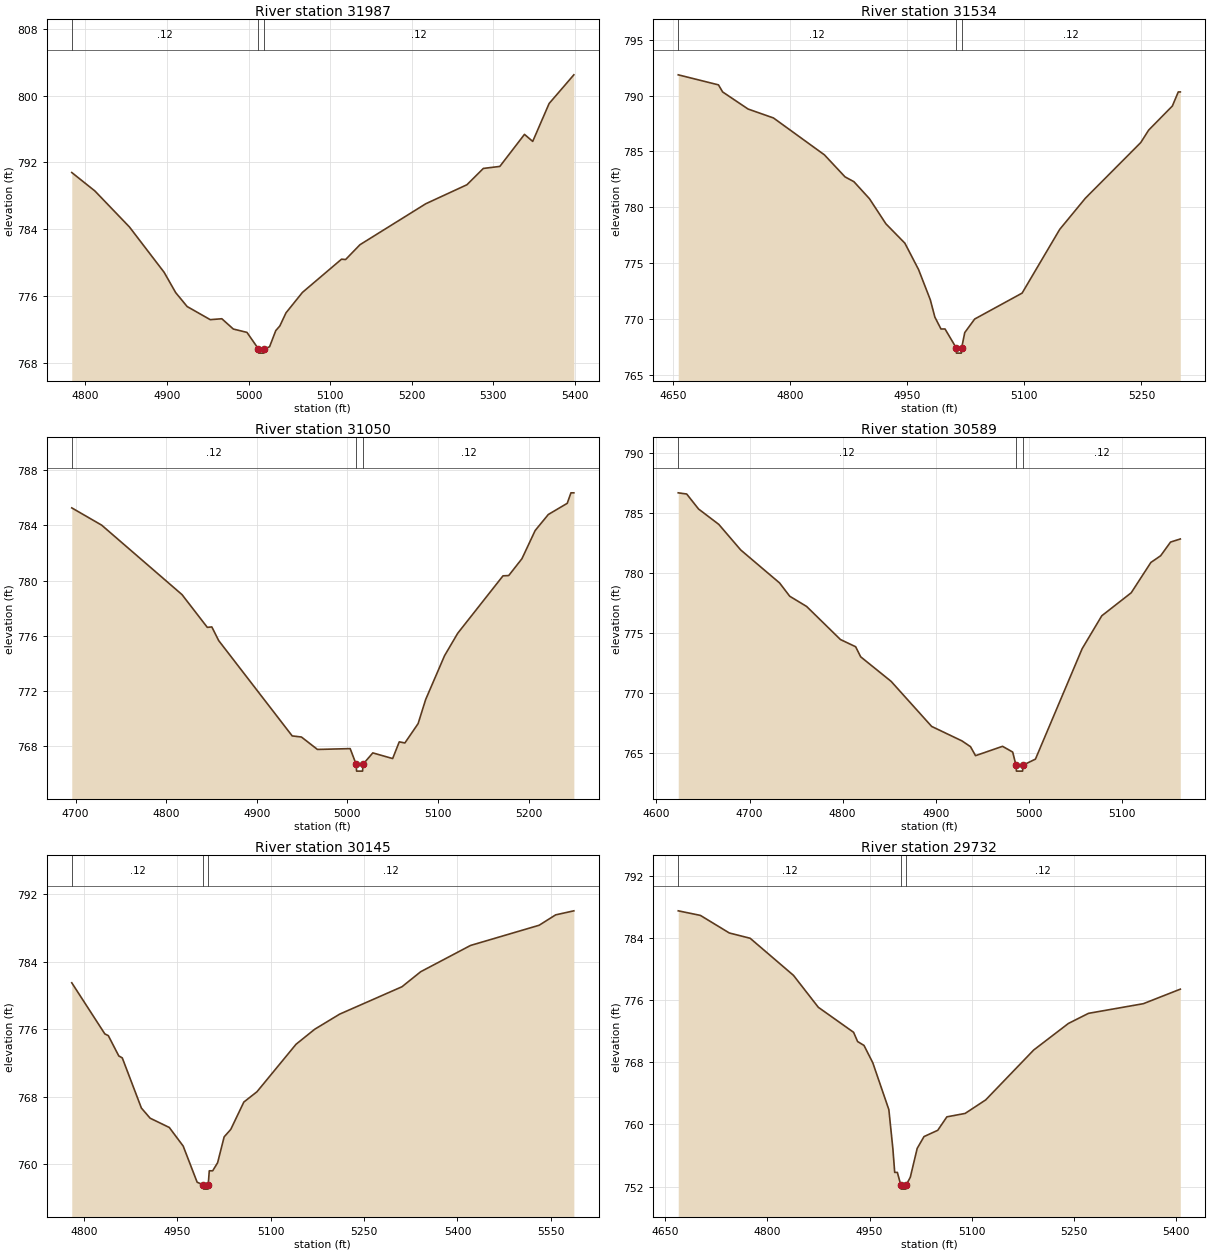
Type RM Length L Ch R = 1 ,31987   ,453,453,453
BEGIN DESCRIPTION:
Blieders Creek 61.0
END DESCRIPTION:
XS GIS Cut Line= 3
      2229774.98     13815325.02        2229925.       13815175.
        2229975.     13814774.97
#Sta/Elev= 30
  4783.3   790.8  4811.6   788.6    4854  784.29  4896.5  778.87  4910.6  776.45
  4924.7  774.78    4953  773.21  4967.2  773.32  4981.3  772.09    4998  771.69
  5012.1  769.71  5012.6  769.21  5018.7  769.21  5019.2  769.71  5025.7  769.97
  5033.3   771.9  5038.3  772.46  5045.8  774.02    5066  776.47  5113.9  780.44
  5118.9   780.4  5136.5  782.17  5217.2  787.07  5267.6  789.34  5287.7  791.29
  5307.9  791.53  5338.1  795.36  5348.2  794.52  5368.3  799.05  5398.6  802.48
#Mann= 3 ,-1 , 0
  4783.3     .12       0  5012.1     .05       0  5019.2     .12       0
Bank Sta=5012.1,5019.2
XS Rating Curve= 0 ,0
Exp/Cntr=0.3,0.1

Type RM Length L Ch R = 1 ,31534   ,484,484,484
BEGIN DESCRIPTION:
Blieders Creek 60.0
END DESCRIPTION:
XS GIS Cut Line= 3
      2230224.72     13815649.27        2230325.       13815325.
      2230375.01     13815024.96
#Sta/Elev= 30
  4656.3  791.86  4707.9  790.96  4713.2  790.33  4745.8   788.8  4778.4     788
  4843.7   784.7  4870.1  782.73  4881.5   782.3  4901.5  780.77  4922.5  778.53
  4946.8   776.8  4964.3  774.45  4979.4  771.74  4985.3  770.18  4993.1  769.12
  4998.3  769.12  5012.4  767.46  5012.9  766.96  5019.2  766.96  5019.7  767.46
  5023.6   768.8  5036.3  770.01  5097.1  772.33  5145.3  778.03  5178.2  780.82
  5249.2   785.8  5259.3  786.91  5289.7  789.07  5297.3  790.33  5299.9  790.33
#Mann= 3 ,-1 , 0
  4656.3     .12       0  5012.4     .05       0  5019.7     .12       0
Bank Sta=5012.4,5019.7
XS Rating Curve= 0 ,0
Exp/Cntr=0.3,0.1

Type RM Length L Ch R = 1 ,31050   ,461,461,461
BEGIN DESCRIPTION:
Blieders Creek 59.0
END DESCRIPTION:
XS GIS Cut Line= 3
      2230724.99     13815725.03        2230775.       13815425.
      2230925.02     13815224.98
#Sta/Elev= 30
  4695.8  785.27  4728.8  784.02  4817.5  778.99  4845.4  776.62  4850.4  776.65
    4858  775.66  4939.1  768.76  4949.3  768.68    4967  767.78  5003.1  767.84
  5009.7  766.71  5010.2  766.21  5016.8  766.21  5017.3  766.71  5028.1  767.53
    5050  767.12  5057.3  768.33  5063.5  768.25  5078.1  769.65  5086.4  771.39
  5107.3  774.57  5121.8  776.19  5171.8  780.35  5178.1  780.37  5192.7  781.59
  5207.3  783.63  5221.8  784.79  5242.7   785.6  5246.8  786.36    5250  786.36
#Mann= 3 ,-1 , 0
  4695.8     .12       0  5009.7     .05       0  5017.3     .12       0
Bank Sta=5009.7,5017.3
XS Rating Curve= 0 ,0
Exp/Cntr=0.3,0.1

Type RM Length L Ch R = 1 ,30589   ,444,444,444
BEGIN DESCRIPTION:
Blieders Creek 58.0
END DESCRIPTION:
XS GIS Cut Line= 3
        2231025.       13815875.        2231175.       13815525.
        2231225.       13815375.
#Sta/Elev= 30
  4623.5  786.71  4632.6  786.61  4645.3  785.36    4667  784.08  4690.6  781.94
  4732.3  779.19  4743.2  778.08  4761.3  777.23  4797.6  774.47  4813.9  773.87
  4819.3  773.03    4852  770.98  4895.5  767.22  4928.1  766.01  4937.2  765.53
  4942.6  764.78  4971.6  765.56  4982.5  765.08    4986  763.99  4986.5  763.49
  4993.1  763.49  4993.6  763.99  5006.9  764.49    5057   773.7  5078.1  776.45
  5109.7  778.37  5130.8   780.9  5141.3  781.46  5151.9   782.6  5162.4  782.86
#Mann= 3 ,-1 , 0
  4623.5     .12       0    4986     .05       0  4993.6     .12       0
Bank Sta=4986,4993.6
XS Rating Curve= 0 ,0
Exp/Cntr=0.3,0.1

Type RM Length L Ch R = 1 ,30145   ,413,413,413
BEGIN DESCRIPTION:
Blieders Creek 57.0
END DESCRIPTION:
XS GIS Cut Line= 4
      2231424.99     13815975.03        2231525.       13815775.
      2231564.97      13815655.1      2231580.97      13815199.2
#Sta/Elev= 30
  4780.7  781.48  4833.8  775.43  4839.4  775.22  4856.2  772.82  4861.8  772.59
  4892.5  766.65  4906.5  765.45  4937.3  764.35  4959.6  762.15    4982  757.87
  4992.1  757.55  4992.6  757.05  4999.3  757.05  4999.8  757.55  5001.5  759.22
    5007  759.22  5014.9  760.18  5025.4  763.24    5036  764.12    5057  767.36
  5078.1  768.58  5140.8   774.2  5170.8  775.98  5210.9  777.77  5310.9  781.01
    5341  782.79    5421   785.9  5531.1  788.29  5557.6  789.52  5586.9     790
#Mann= 3 ,-1 , 0
  4780.7     .12       0  4992.1     .05       0  4999.8     .12       0
Bank Sta=4992.1,4999.8
XS Rating Curve= 0 ,0
Exp/Cntr=0.3,0.1

Type RM Length L Ch R = 1 ,29732   ,502,502,502
BEGIN DESCRIPTION:
X18257
END DESCRIPTION:
XS GIS Cut Line= 3
      2231672.19     13816306.86      2231841.46     13816037.76
      2231889.21      13815621.1
#Sta/Elev= 30
  4669.1  787.48  4701.7  786.89  4744.1  784.63  4774.7  783.95  4838.3  779.18
  4874.8  775.07  4926.6  771.85  4932.5  770.66  4941.9  770.16  4954.8  767.93
  4978.4   761.9  4984.3  756.87    4987  753.82  4990.9  753.82    4996  752.17
  4996.5  751.67  5003.2  751.67  5003.7  752.17  5009.9   753.2    5020  756.91
    5030  758.43  5050.2  759.24  5063.6  760.97  5090.4  761.41  5120.6  763.15
  5191.1  769.57  5242.1  772.99  5271.6  774.29  5352.1  775.53  5406.4   777.4
#Mann= 3 ,-1 , 0
  4669.1     .12       0    4996     .05       0  5003.7     .12       0
Bank Sta=4996,5003.7
XS Rating Curve= 0 ,0
Exp/Cntr=0.3,0.1

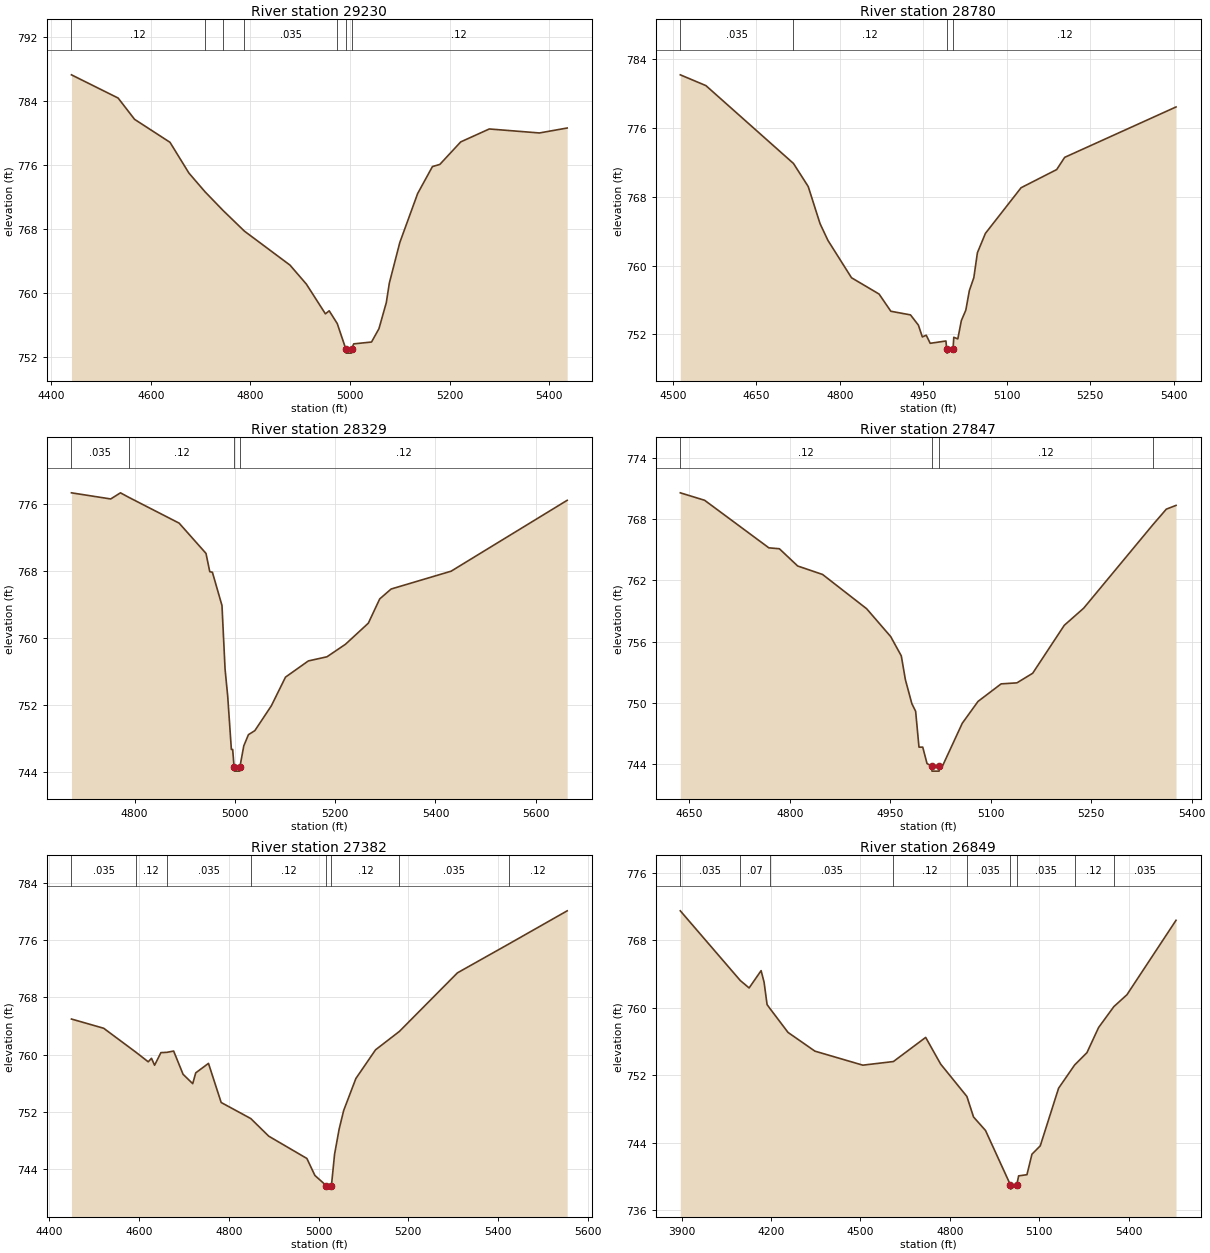
Type RM Length L Ch R = 1 ,29230   ,450,450,450
BEGIN DESCRIPTION:
Blieders Creek 56.0
END DESCRIPTION:
XS GIS Cut Line= 3
      2231689.58     13816486.97        2232225.       13816325.
      2232583.63     13816076.84
#Sta/Elev= 30
  4440.6   787.3  4534.4  784.39  4567.3  781.73  4638.5  778.85  4676.6  774.99
  4708.9  772.65    4745  770.32  4787.9  767.73  4879.5  763.47  4912.4  761.09
  4950.6  757.37  4958.2  757.75  4974.4  756.15  4991.7  752.95  4992.2  752.45
  5002.6  752.45  5003.1  752.95  5007.4  753.61  5043.2  753.84  5058.1  755.51
  5072.9  758.78    5079  761.23    5100   766.3  5135.8  772.43  5165.5  775.81
  5180.4  776.08  5222.3   778.9  5279.7  780.52  5380.4  780.02  5436.1  780.64
#Mann= 7 ,-1 , 0
  4440.6     .12       0  4708.9    .035       0    4745     .12       0
  4787.9    .035       0  4974.4     .12       0  4991.7     .05       0
  5003.1     .12       0
Bank Sta=4991.7,5003.1
XS Rating Curve= 0 ,0
Exp/Cntr=0.3,0.1

Type RM Length L Ch R = 1 ,28780   ,451,451,451
BEGIN DESCRIPTION:
Blieders Creek 55.0
END DESCRIPTION:
XS GIS Cut Line= 3
      2232125.73     13817020.85        2232475.       13816675.
      2232724.69     13816363.31
#Sta/Elev= 30
  4513.5  782.14  4559.5  780.89  4716.9  771.85  4743.4  769.17  4764.6  764.87
  4778.8  762.92  4821.2  758.58  4870.7  756.69  4891.9  754.69  4927.2  754.27
  4941.4  753.08  4948.5  751.71  4955.5  751.91  4962.6  750.97  4990.9  751.24
  4992.2  750.33  4992.7  749.83  5003.7  750.33    5005  751.67  5012.2  751.48
  5018.6  753.61  5026.6  754.82    5033   757.1    5041  758.59  5047.4  761.48
  5061.8  763.73  5125.9  769.03  5189.9  771.14  5204.3  772.56  5404.4  778.41
#Mann= 4 ,-1 , 0
  4513.5    .035       0  4716.9     .12       0  4992.2     .05       0
  5003.7     .12       0
Bank Sta=4992.2,5003.7
XS Rating Curve= 0 ,0
Exp/Cntr=0.3,0.1

Type RM Length L Ch R = 1 ,28329   ,482,482,482
BEGIN DESCRIPTION:
Blieders Creek 54.0
END DESCRIPTION:
XS GIS Cut Line= 3
      2232514.21     13817376.72        2232625.       13817075.
      2232909.16      13816471.8
#Sta/Elev= 30
  4674.3  777.29  4752.6  776.56    4772  777.29  4789.7  776.72    4889  773.68
  4942.5  770.08    4950  767.91  4955.3  767.83  4974.4  763.87  4980.5  756.33
  4985.8  753.07  4993.1  746.74  4995.7  746.74  4998.5  744.66    4999  744.16
  5009.6  744.16  5010.1  744.66  5017.8  747.16  5027.1   748.5  5039.9  748.98
  5072.7  751.93    5101  755.35  5146.6  757.28  5183.6  757.77  5220.5  759.26
  5266.1  761.77  5288.8  764.66  5311.6  765.84  5431.1  767.96  5662.5   776.4
#Mann= 4 ,-1 , 0
  4674.3    .035       0  4789.7     .12       0  4998.5     .05       0
  5010.1     .12       0
Bank Sta=4998.5,5010.1
XS Rating Curve= 0 ,0
Exp/Cntr=0.3,0.1

Type RM Length L Ch R = 1 ,27847   ,465,465,465
BEGIN DESCRIPTION:
Blieders Creek 53.0
END DESCRIPTION:
XS GIS Cut Line= 3
      2232893.97     13817485.25        2233075.       13817175.
        2233225.     13816824.99
#Sta/Elev= 30
  4636.7  770.57    4673  769.84  4768.9  765.18  4784.6  765.09  4811.9   763.4
  4849.1  762.57  4914.9  759.21  4950.8  756.48  4966.6  754.59  4972.7  752.26
  4982.3  749.92    4988  749.16    4993  745.65  4998.6  745.65    5005  744.04
  5011.9   743.8  5012.4   743.3    5023   743.3  5023.5   743.8  5028.5  743.86
  5057.6  747.99  5081.1  750.13  5115.6  751.85  5139.2  751.95  5162.7  752.89
  5209.9  757.59  5238.9  759.27  5341.7  767.41  5362.2  768.97  5376.7  769.34
#Mann= 4 ,-1 , 0
  4636.7     .12       0  5011.9     .05       0  5023.5     .12       0
  5341.7    .035       0
Bank Sta=5011.9,5023.5
XS Rating Curve= 0 ,0
Exp/Cntr=0.3,0.1

Type RM Length L Ch R = 1 ,27382   ,533,533,533
BEGIN DESCRIPTION:
Blieders Creek 52.0
END DESCRIPTION:
XS GIS Cut Line= 3
      2233123.57      13817595.5        2233525.       13817225.
      2233618.37     13816673.63
#Sta/Elev= 30
    4449  764.98  4520.9  763.69  4592.5  760.36  4620.2  759.01  4627.5   759.5
  4634.4  758.53  4648.5  760.29  4661.8  760.33  4676.9  760.51  4697.9  757.27
  4719.4  755.96  4726.2  757.47  4754.6  758.79  4782.9  753.33  4848.9  751.09
    4889  748.63    4974  745.52  4991.9  743.15  5017.1  741.74  5017.6  741.24
  5028.8  741.74  5035.8  746.12    5046  749.63  5056.1  752.22  5083.3  756.68
  5127.1  760.68  5180.5  763.26  5309.7  771.42  5425.1  775.48  5554.5  780.08
#Mann= 8 ,-1 , 0
    4449    .035       0  4592.5     .12       0  4661.8    .035       0
  4848.9     .12       0  5017.1     .05       0  5028.8     .12       0
  5180.5    .035       0  5425.1     .12       0
Bank Sta=5017.1,5028.8
XS Rating Curve= 0 ,0
Exp/Cntr=0.3,0.1

Type RM Length L Ch R = 1 ,26849   ,546,546,546
BEGIN DESCRIPTION:
Blieders Creek 51.0
END DESCRIPTION:
XS GIS Cut Line= 3
        2233925.     13818424.99        2234025.       13817325.
      2233775.02     13816825.04
#Sta/Elev= 30
  3895.5   771.5  4096.8  763.24  4126.4  762.36  4166.6  764.41  4176.6  763.05
  4186.7  760.39  4195.3  759.97    4257  757.09  4347.3  754.87    4508  753.21
  4610.6  753.64  4718.9   756.5  4769.1  753.34  4857.2   749.5  4879.5  747.07
  4919.7  745.47  5003.3  739.02  5003.8  738.52  5024.6  739.02  5030.8  740.09
  5058.7  740.23  5075.5  742.66  5103.4  743.65  5164.9  750.48  5218.9  753.24
    5260  754.69  5299.1  757.67  5350.4  760.15  5394.1  761.55    5559  770.38
#Mann= 9 ,-1 , 0
  3895.5    .035       0  4096.8     .07       0  4195.3    .035       0
  4610.6     .12       0  4857.2    .035       0  5003.3    .035       0
  5024.6    .035       0  5218.9     .12       0  5350.4    .035       0
Bank Sta=5003.3,5024.6
XS Rating Curve= 0 ,0
Exp/Cntr=0.3,0.1

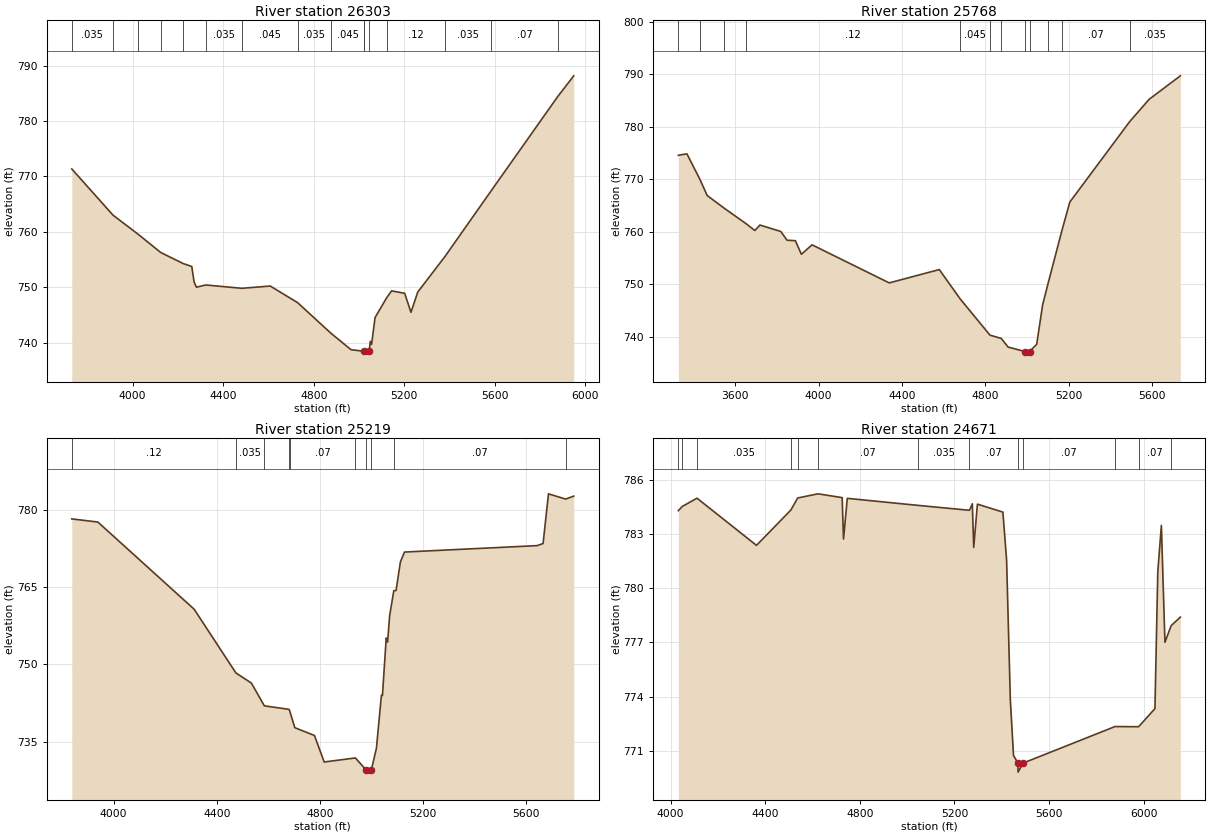
Type RM Length L Ch R = 1 ,26303   ,535,535,535
BEGIN DESCRIPTION:
Blieders Creek 50.0
END DESCRIPTION:
XS GIS Cut Line= 3
      2234274.99     13818425.05        2234525.       13817175.
        2235025.       13816375.
#Sta/Elev= 30
  3730.9  771.36  3913.1  763.03  4023.9  759.59  4123.7   756.3  4223.4  754.29
  4261.2  753.77  4271.4  750.98  4281.6  750.03  4323.2  750.43  4482.6  749.83
    4608  750.24  4728.7  747.25  4875.9  741.74  4964.9  738.76  5023.7  738.47
  5023.9  738.46  5024.4  737.96  5045.3  738.46  5049.9  740.26  5055.8  739.71
  5071.2  744.56  5123.1  748.17  5144.3  749.37    5202  748.93  5229.8   745.5
  5259.8  749.15  5378.9   755.5  5585.3  767.48  5878.7  784.43  5949.1  788.15
#Mann= 16 ,-1 , 0
  3730.9    .035       0  3913.1     .12       0  4023.9    .035       0
  4123.7     .12       0  4223.4     .07       0  4323.2    .035       0
  4482.6    .045       0  4728.7    .035       0  4875.9    .045       0
  5023.7    .035       0  5023.9    .045       0  5045.3    .035       0
  5123.1     .12       0  5378.9    .035       0  5585.3     .07       0
  5878.7    .035       0
Bank Sta=5023.9,5045.3
XS Rating Curve= 0 ,0
Exp/Cntr=0.3,0.1

Type RM Length L Ch R = 1 ,25768   ,549,549,549
BEGIN DESCRIPTION:
Blieders Creek 49.0
END DESCRIPTION:
XS GIS Cut Line= 5
       2235116.2     13818746.11      2235044.14     13817113.29
        2235025.       13817075.      2235033.46     13817036.93
      2235081.48     13816345.91
#Sta/Elev= 30
  3326.9  774.56  3368.1  774.84    3430  770.01  3465.4   766.9  3546.6  764.49
  3651.7  761.54  3693.9  760.23  3718.4  761.27  3818.5  760.05  3848.5  758.38
  3888.6  758.29  3917.4   755.7  3968.6   757.5    4339  750.25  4579.2  752.79
  4679.8  747.18  4822.3   740.3  4876.5  739.67  4909.6  738.02  4990.5  737.18
    4991  736.68  5012.2  737.18  5046.6  738.55  5075.1  746.07  5102.2   750.3
  5167.3  760.17  5205.4  765.64  5493.3     781  5586.4  785.23  5735.8   789.7
#Mann= 12 ,-1 , 0
  3326.9    .035       0    3430     .12       0  3546.6    .035       0
  3651.7     .12       0  4679.8    .045       0  4822.3    .035       0
  4876.5    .045       0  4990.5    .045       0  5012.2    .045       0
  5102.2    .035       0  5167.3     .07       0  5493.3    .035       0
Bank Sta=4990.5,5012.2
XS Rating Curve= 0 ,0
Exp/Cntr=0.3,0.1

Type RM Length L Ch R = 1 ,25219   ,548,548,548
BEGIN DESCRIPTION:
Blieders Creek 48.0
END DESCRIPTION:
XS GIS Cut Line= 5
      2235710.82     13818225.25      2235559.35     13817148.04
        2235575.       13817075.        2235575.     13817031.69
      2235359.63     13816321.12
#Sta/Elev= 30
  3837.4  778.32  3938.6  777.71  4312.3  760.75  4474.5  748.34  4534.4  746.38
  4584.9  741.94  4680.4  741.26  4682.7  741.03  4703.1  737.69  4779.4  736.17
  4817.2  731.01  4938.1   731.8  4978.8  729.54  4979.3  729.04  5000.5  729.54
  5019.9   733.7  5039.1  743.96  5043.2  743.96  5057.9  755.14  5063.2  754.36
  5071.1  759.46  5087.3  764.34  5096.1  764.39  5112.9  769.95    5129  771.87
  5643.6  773.12  5666.7  773.53  5687.6   783.2  5754.2  782.18  5785.7  782.75
#Mann= 10 ,-1 , 0
  3837.4     .12       0  4474.5    .035       0  4584.9     .07       0
  4680.4    .035       0  4682.7     .07       0  4938.1    .035       0
  4978.8    .035       0  5000.5    .035       0  5087.3     .07       0
  5754.2    .035       0
Bank Sta=4978.8,5000.5
XS Rating Curve= 0 ,0
Exp/Cntr=0.3,0.1

Type RM Length L Ch R = 1 ,24671   ,422,422,422
BEGIN DESCRIPTION:
Blieders Creek 47.0
END DESCRIPTION:
XS GIS Cut Line= 5
      2236487.97     13818135.09      2236400.42     13817905.29
      2235980.23     13817152.46      2235658.01     13816596.26
      2235454.73     13816285.15
#Sta/Elev= 30
  4032.5  784.28  4049.1  784.51  4111.3  784.97    4363  782.36  4508.7  784.32
  4537.1  784.98  4623.3  785.21  4725.2     785  4730.9  782.71  4746.9  784.96
  5047.1  784.57  5263.4   784.3  5275.6  784.66  5281.4  782.25  5297.1  784.64
  5404.8   784.2  5420.5  781.55  5436.3  773.82  5449.7  770.74  5468.5  770.32
    5469  769.82  5490.3  770.32    5879  772.34  5978.6  772.33  6047.7  773.33
  6059.8  780.91  6074.9  783.46    6090     777  6116.3  777.92    6155  778.39
#Mann= 13 ,-1 , 0
  4032.5    .035       0  4049.1     .07       0  4111.3    .035       0
  4508.7     .07       0  4537.1    .035       0  4623.3     .07       0
  5047.1    .035       0  5263.4     .07       0  5468.5     .05       0
  5490.3     .07       0    5879    .035       0  5978.6     .07       0
  6116.3    .035       0
Bank Sta=5468.5,5490.3
XS Rating Curve= 0 ,0
Exp/Cntr=0.3,0.1