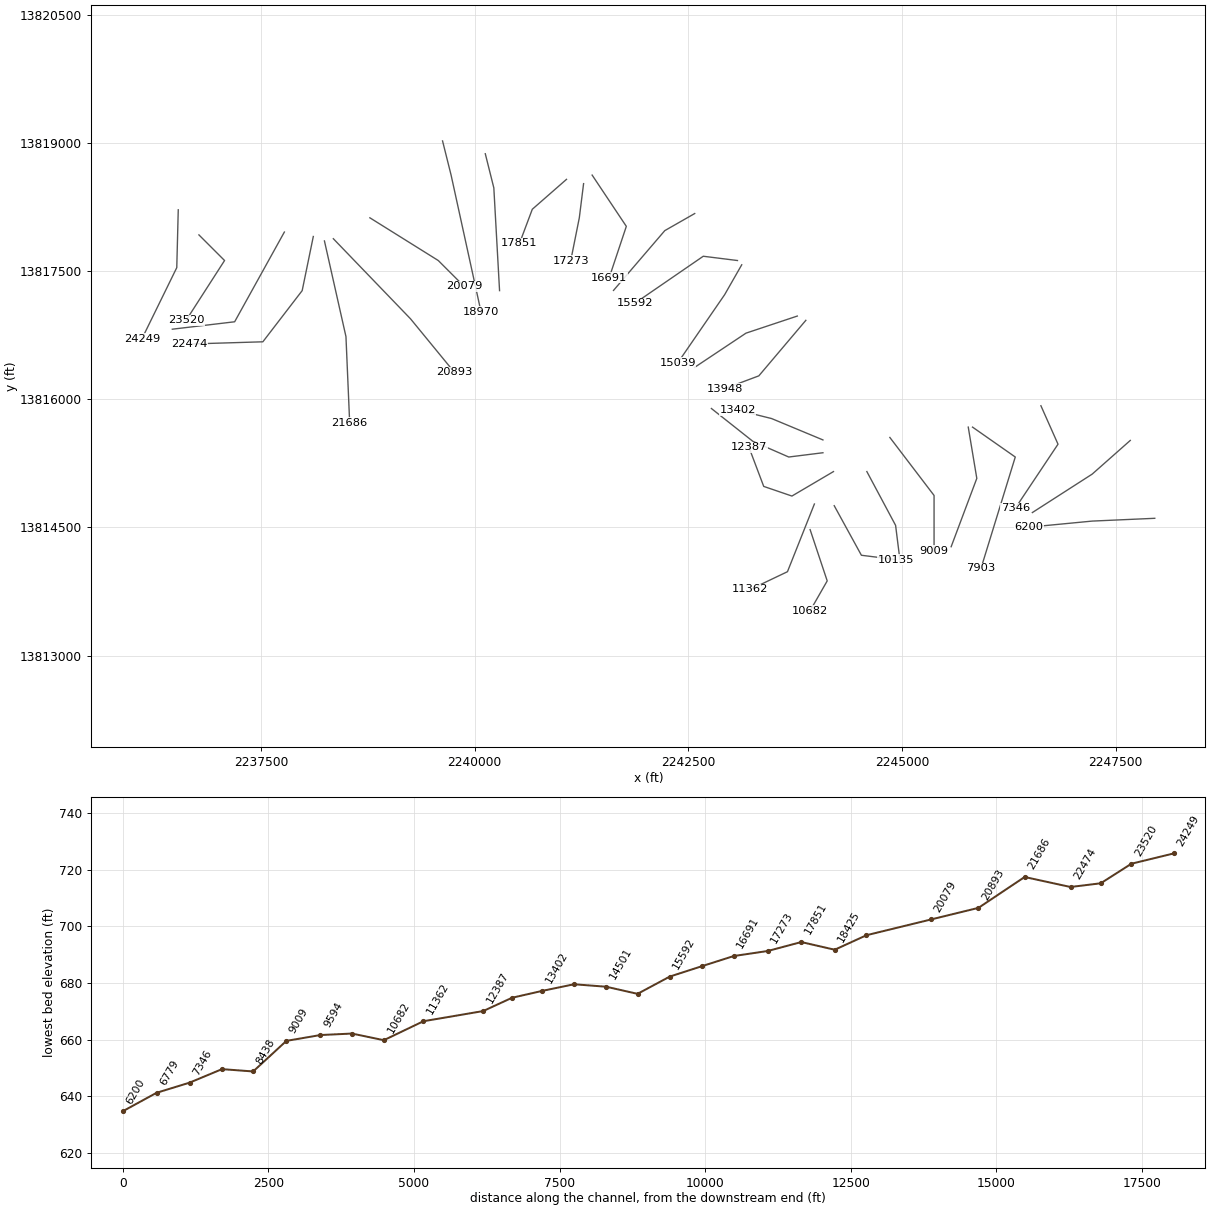
HEC-RAS study Blieders Creek.prj: Blieders Creek Base Level Engineering

--- Blieders Creek.g01 (geometry) --- (continued)

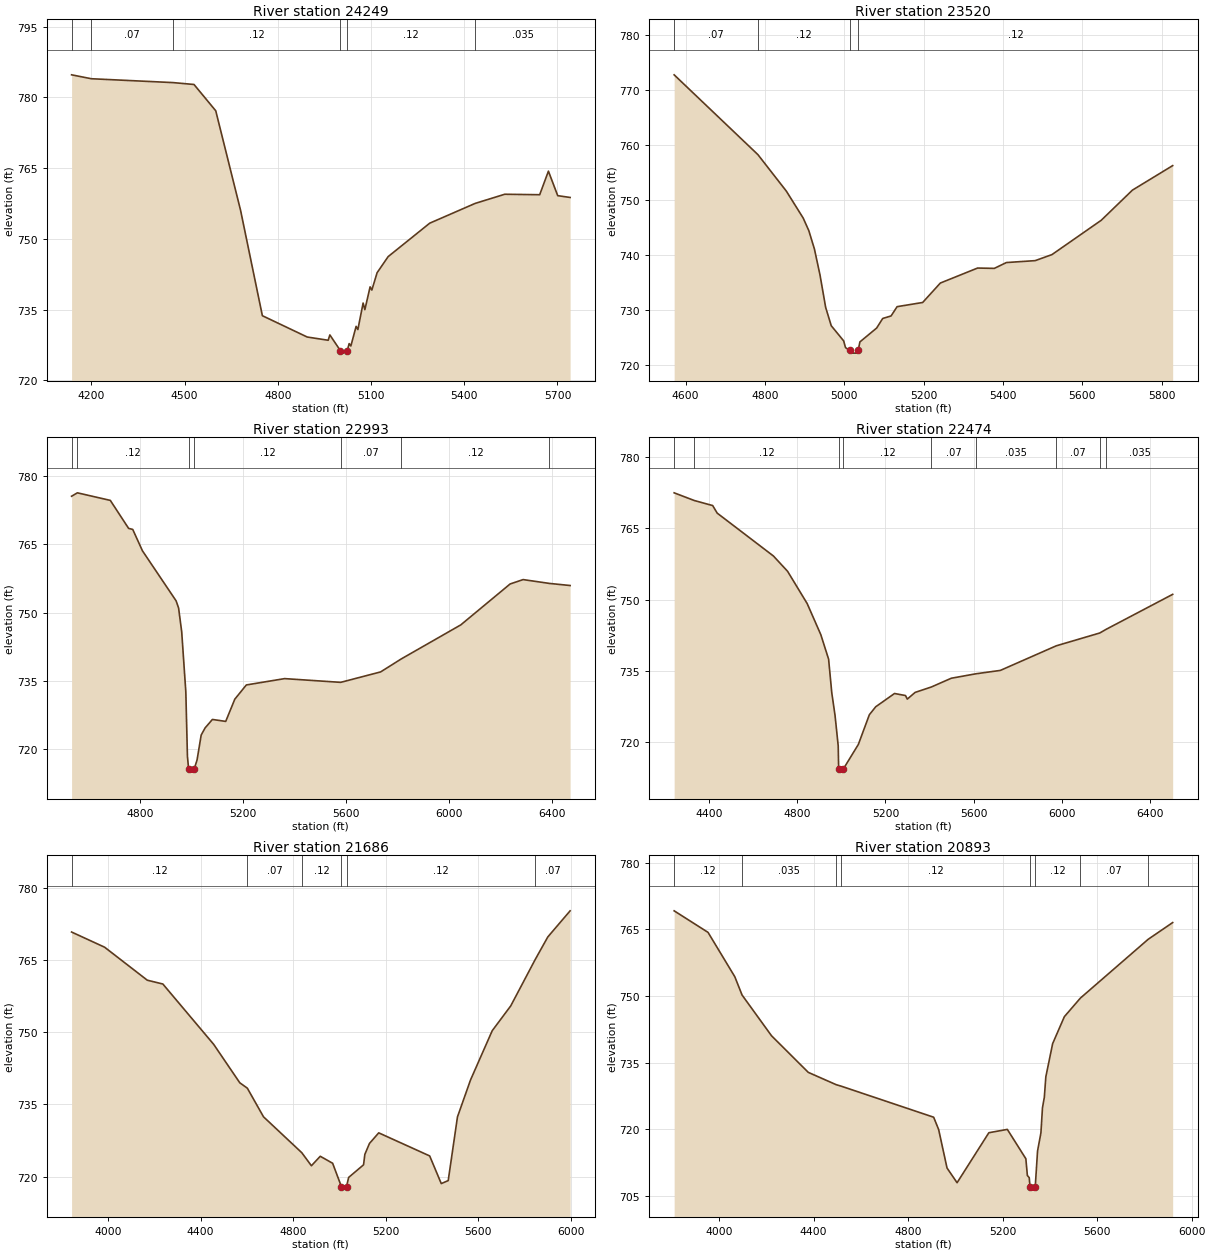
Type RM Length L Ch R = 1 ,24249   ,729,729,729
BEGIN DESCRIPTION:
Blieders Creek 46.0
END DESCRIPTION:
XS GIS Cut Line= 3
       2236533.3     13818218.74      2236515.94     13817541.67
      2236108.37     13816709.18
#Sta/Elev= 30
  4136.6   784.8  4200.3  783.97  4463.2  783.15  4530.5  782.75  4600.5  777.17
  4680.5  756.01  4750.5  733.69  4894.7  729.17  4962.2  728.48  4967.7  729.61
  5001.9  726.25  5002.4  725.75  5023.7  726.25  5029.7  727.77  5035.3  727.27
  5052.2  731.43  5057.8  730.75  5074.7  736.38  5080.3  734.97  5097.2  739.81
  5102.8  739.13  5119.7  742.81  5155.3  746.23    5289  753.32  5435.3  757.52
  5530.4  759.46  5642.9  759.36    5671  764.36  5700.9  759.16  5740.8  758.78
#Mann= 6 ,-1 , 0
  4136.6    .035       0  4200.3     .07       0  4463.2     .12       0
  5001.9     .05       0  5023.7     .12       0  5435.3    .035       0
Bank Sta=5001.9,5023.7
XS Rating Curve= 0 ,0
Exp/Cntr=0.3,0.1

Type RM Length L Ch R = 1 ,23520   ,527,527,527
BEGIN DESCRIPTION:
Blieders Creek 45.0
END DESCRIPTION:
XS GIS Cut Line= 3
      2236775.03     13817924.97        2237075.       13817625.
      2236624.99     13816924.99
#Sta/Elev= 30
  4571.4  772.78  4782.5  758.25  4854.2   751.6  4896.6   746.7  4910.8  744.41
  4924.9  741.07    4939  736.33  4953.2  730.45  4967.3   727.1  4998.6  724.34
  5003.2  723.12  5013.4  722.61  5013.9  722.11  5034.7  722.11  5035.2  722.61
  5039.5  724.15  5081.8  726.68    5097  728.42  5118.1  728.88  5133.3  730.57
  5197.7  731.33  5242.3  734.87  5336.1   737.6  5378.3  737.54  5408.7   738.6
  5481.4  738.95  5523.6  740.05  5647.8   746.3  5726.4  751.79  5827.8  756.25
#Mann= 4 ,-1 , 0
  4571.4     .07       0  4782.5     .12       0  5013.4     .05       0
  5035.2     .12       0
Bank Sta=5013.4,5035.2
XS Rating Curve= 0 ,0
Exp/Cntr=0.3,0.1

Type RM Length L Ch R = 1 ,22993   ,519,519,519
BEGIN DESCRIPTION:
X18259
END DESCRIPTION:
XS GIS Cut Line= 3
       2237774.6      13817958.3      2237193.02     13816907.99
      2236463.85     13816821.18
#Sta/Elev= 30
  4534.7  775.53  4557.2  776.28    4685  774.62    4756  768.48    4772  768.25
  4809.8  763.55  4940.3  752.58    4950  751.01  4962.1  745.77  4978.1  732.57
  4984.3  718.47  4988.9  715.71  4989.4  715.21  5010.8  715.71  5021.6  717.64
  5037.7  723.13  5052.9  724.69  5081.2  726.55  5132.9  726.12  5168.2     731
  5212.9  734.12  5361.5  735.51  5579.1  734.69  5734.1  736.98  5814.5  739.84
  6045.5  747.31  6236.8  756.28  6287.2  757.24  6389.3   756.4  6469.6  755.94
#Mann= 7 ,-1 , 0
  4534.7     .07       0  4557.2     .12       0  4988.9     .05       0
  5010.8     .12       0  5579.1     .07       0  5814.5     .12       0
  6389.3     .07       0
Bank Sta=4988.9,5010.8
XS Rating Curve= 0 ,0
Exp/Cntr=0.3,0.1

Type RM Length L Ch R = 1 ,22474   ,788,788,788
BEGIN DESCRIPTION:
X18258
END DESCRIPTION:
XS GIS Cut Line= 4
      2238113.17     13817906.27      2237982.96     13817272.57
      2237522.89     13816673.61      2236663.47     13816647.57
#Sta/Elev= 30
  4241.2  772.48  4332.6  770.86    4416   769.8  4436.5  768.21  4691.7  759.18
  4755.9  755.96  4844.8  749.17  4906.7  742.62    4942  737.47  4956.5  730.35
  4971.1  725.67  4985.6  719.22  4987.6   714.4  4988.1   713.9  5009.5   714.4
    5077  719.52  5126.9  725.77  5155.9  727.45  5241.1  730.24  5290.9  729.81
  5299.1  729.06  5334.5  730.47  5408.8  731.62  5498.5  733.45    5612   734.4
  5721.3   735.1  5975.1  740.28    6172  742.97  6201.8  743.76  6503.2  751.11
#Mann= 9 ,-1 , 0
  4241.2     .07       0  4332.6     .12       0  4987.6     .05       0
  5009.5     .12       0  5408.8     .07       0    5612    .035       0
  5975.1     .07       0    6172     .12       0  6201.8    .035       0
Bank Sta=4987.6,5009.5
XS Rating Curve= 0 ,0
Exp/Cntr=0.3,0.1

Type RM Length L Ch R = 1 ,21686   ,793,793,793
BEGIN DESCRIPTION:
Blieders Creek 44.0
END DESCRIPTION:
XS GIS Cut Line= 3
      2238243.36      13817854.2      2238495.11     13816734.38
      2238538.46     13815728.69
#Sta/Elev= 30
  3842.6  770.79  3985.3  767.64  4169.8  760.79    4237     760  4456.8  747.47
  4569.5   739.5  4602.1  738.38    4672  732.44  4837.6  724.98    4879  722.28
  4917.2  724.25  4970.7   722.8  5008.8  717.93  5009.3  717.43  5030.8  717.93
  5039.8  719.85  5104.4  722.48  5109.9  724.64  5129.9  726.91  5169.9  729.11
  5390.1  724.32  5440.2  718.58  5470.2   719.2  5510.2  732.42  5566.8  740.11
  5660.4  750.31  5740.4  755.46  5846.1  765.08  5900.6  769.77    5997  775.19
#Mann= 6 ,-1 , 0
  3842.6     .12       0  4602.1     .07       0  4837.6     .12       0
  5008.8     .05       0  5030.8     .12       0  5846.1     .07       0
Bank Sta=5008.8,5030.8
XS Rating Curve= 0 ,0
Exp/Cntr=0.3,0.1

Type RM Length L Ch R = 1 ,20893   ,814,814,814
BEGIN DESCRIPTION:
Blieders Creek 43.0
END DESCRIPTION:
XS GIS Cut Line= 3
      2238347.55      13817880.2      2239250.32     13816942.71
      2239762.45     13816317.73
#Sta/Elev= 30
  3810.2  769.16  3953.6  764.31  4066.8  754.34  4097.5  750.22  4222.2  741.05
  4377.8  732.81  4495.9  730.04  4517.9  729.69  4908.3  722.72  4929.4  719.95
  4964.9  711.29  5007.4  707.98  5141.9  719.23  5220.1  719.98  5298.4  713.38
  5304.8  709.61  5312.7  709.12  5316.1  707.04  5316.6  706.54  5338.1  707.04
  5347.9   715.1  5362.2  719.22  5368.7  724.82  5376.6  727.21    5383  731.82
  5411.8  739.28  5461.3  745.34  5529.3  749.53  5815.7  762.74  5919.7  766.52
#Mann= 8 ,-1 , 0
  3810.2     .12       0  4097.5    .035       0  4495.9     .07       0
  4517.9     .12       0  5316.1     .05       0  5338.1     .12       0
  5529.3     .07       0  5815.7    .035       0
Bank Sta=5316.1,5338.1
XS Rating Curve= 0 ,0
Exp/Cntr=0.3,0.1

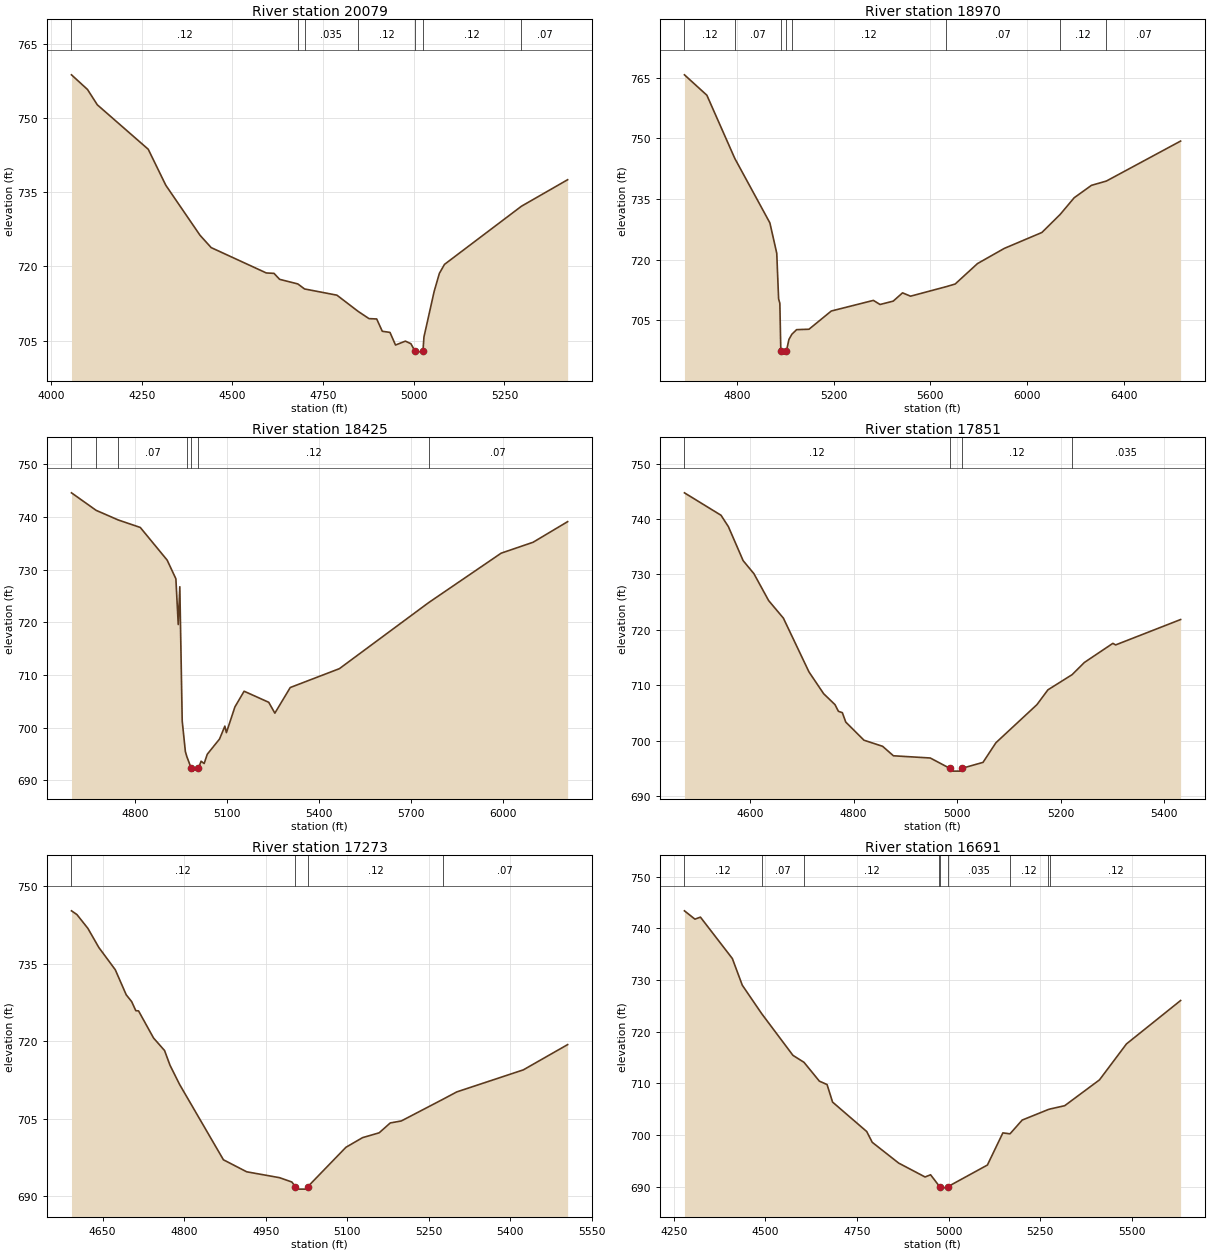
Type RM Length L Ch R = 1 ,20079   ,1109,1109,1109
BEGIN DESCRIPTION:
Blieders Creek 42.0
END DESCRIPTION:
XS GIS Cut Line= 3
      2238775.04     13818124.98        2239575.       13817625.
      2239874.99     13817325.01
#Sta/Elev= 30
  4056.6  758.83  4100.8  755.86  4127.9  752.75  4268.2  743.75  4316.6  736.46
  4410.9  726.33  4441.6  723.83  4593.7  718.69  4614.9  718.61  4630.3   717.4
  4680.5  716.47  4699.1  715.45  4788.3  714.19  4846.9   710.9  4876.7  709.44
  4897.9  709.37  4913.3  706.88  4934.5  706.65  4949.8  704.09    4977  704.88
  4992.3  704.35  5002.7  702.95  5003.2  702.45  5025.5  702.95  5028.2  705.73
  5056.5  715.01  5070.7  718.61  5084.8  720.43  5296.9  732.21  5424.2  737.58
#Mann= 7 ,-1 , 0
  4056.6     .12       0  4680.5     .07       0  4699.1    .035       0
  4846.9     .12       0  5002.7     .05       0  5025.5     .12       0
  5296.9     .07       0
Bank Sta=5002.7,5025.5
XS Rating Curve= 0 ,0
Exp/Cntr=0.3,0.1

Type RM Length L Ch R = 1 ,18970   ,545,545,545
BEGIN DESCRIPTION:
Blieders Creek 41.0
END DESCRIPTION:
XS GIS Cut Line= 3
      2239625.01     13819024.97        2239725.       13818625.
        2240075.     13817025.01
#Sta/Elev= 30
  4583.8  765.75  4676.5   760.7  4791.9  745.06  4936.8  729.12  4965.2  721.61
  4972.9  710.29    4978  709.21    4982  697.39  4982.5  696.89  5005.1  697.39
  5015.5  700.27  5027.5  701.55  5047.3   702.7  5098.4   702.8  5190.6  707.31
  5364.6  709.94    5392  708.92  5446.5  709.76  5484.9   711.8  5518.1  710.98
  5665.7  713.34  5702.4  713.99  5794.5  719.04  5905.3   722.8  6060.7  726.74
  6135.8  731.18  6194.1  735.33  6265.4   738.4  6327.3  739.47  6633.9  749.36
#Mann= 8 ,-1 , 0
  4583.8     .12       0  4791.9     .07       0    4982     .05       0
  5005.1     .07       0  5027.5     .12       0  5665.7     .07       0
  6135.8     .12       0  6327.3     .07       0
Bank Sta=4982,5005.1
XS Rating Curve= 0 ,0
Exp/Cntr=0.3,0.1

Type RM Length L Ch R = 1 ,18425   ,574,574,574
BEGIN DESCRIPTION:
Blieders Creek 40.0
END DESCRIPTION:
XS GIS Cut Line= 3
        2240125.       13818875.        2240225.       13818475.
      2240291.98     13817272.58
#Sta/Elev= 30
  4593.6  744.57  4673.9  741.25    4746  739.42  4817.8     738  4905.4   731.8
  4933.8  728.26  4941.5  719.58  4946.6  726.75  4954.4   701.3  4964.7  695.49
  4969.4  694.54  4984.1  692.27  4984.6  691.77  5007.2  692.27  5015.9  693.65
  5025.9  693.21    5036  694.97    5076  697.86  5093.4  700.31  5098.4  699.07
  5126.1  703.95  5156.1  706.93  5236.3  704.83  5256.3  702.77  5306.4  707.63
  5466.6  711.21  5757.4  723.74  5993.6  733.12  6097.6  735.19  6210.2   739.1
#Mann= 7 ,-1 , 0
  4593.6     .07       0  4673.9     .12       0    4746     .07       0
  4969.4     .12       0  4984.1     .05       0  5007.2     .12       0
  5757.4     .07       0
Bank Sta=4984.1,5007.2
XS Rating Curve= 0 ,0
Exp/Cntr=0.3,0.1

Type RM Length L Ch R = 1 ,17851   ,578,578,578
BEGIN DESCRIPTION:
Blieders Creek 39.0
END DESCRIPTION:
XS GIS Cut Line= 3
      2241074.97     13818574.98        2240675.       13818225.
      2240524.99     13817824.97
#Sta/Elev= 30
  4473.3  744.71    4544  740.66  4558.2  738.61  4586.7  732.47  4607.6  730.11
    4636  725.26  4664.5  722.09  4713.9  712.39  4742.3  708.45  4764.2  706.48
  4770.8  705.28  4778.4  705.03    4785  703.33  4820.2  700.06  4856.2  698.96
  4877.1  697.25  4948.3  696.85  4986.1  694.98  4986.6  694.48  5008.8  694.48
  5009.3  694.98  5050.2  696.06  5075.1   699.6  5154.3  706.47  5175.6  709.15
  5222.5   711.9    5246  714.09  5301.1  717.54  5306.5  717.26    5432  721.84
#Mann= 4 ,-1 , 0
  4473.3     .12       0  4986.1     .05       0  5009.3     .12       0
  5222.5    .035       0
Bank Sta=4986.1,5009.3
XS Rating Curve= 0 ,0
Exp/Cntr=0.3,0.1

Type RM Length L Ch R = 1 ,17273   ,582,582,582
BEGIN DESCRIPTION:
Blieders Creek 38.0
END DESCRIPTION:
XS GIS Cut Line= 3
      2241274.99     13818524.95        2241225.       13818125.
      2241124.99     13817624.97
#Sta/Elev= 30
  4592.7  745.28  4602.7  744.56  4622.9  741.88    4643  738.18  4673.3  733.86
  4693.4  729.01  4703.5  727.67  4711.1  725.92  4716.1  725.88  4743.8  720.61
    4764  718.19  4774.1  715.32  4791.7  711.61  4872.3  697.01  4915.1  694.68
  4975.6  693.54  4998.3   692.7  5004.5  691.82    5005  691.32  5027.3  691.32
  5027.8  691.82  5097.7  699.43  5128.3   701.3  5158.9  702.24  5179.3  704.15
  5199.7  704.54  5276.2  708.74  5301.7  710.17  5424.1  714.44  5505.7  719.34
#Mann= 4 ,-1 , 0
  4592.7     .12       0  5004.5     .05       0  5027.8     .12       0
  5276.2     .07       0
Bank Sta=5004.5,5027.8
XS Rating Curve= 0 ,0
Exp/Cntr=0.3,0.1

Type RM Length L Ch R = 1 ,16691   ,537,537,537
BEGIN DESCRIPTION:
Blieders Creek 37.0
END DESCRIPTION:
XS GIS Cut Line= 3
      2241374.99     13818625.01        2241775.       13818025.
      2241574.99     13817424.98
#Sta/Elev= 30
  4279.4  743.39    4308  741.78    4323  742.17  4410.1  734.16  4437.2     729
  4489.7  723.54  4575.4  715.43  4605.6  714.08  4647.5  710.44  4668.5  709.78
  4683.5  706.39  4776.7  700.69  4791.7  698.61  4863.8  694.59  4935.9   691.9
  4950.9  692.33  4975.2  690.07  4975.4  690.05  4975.9  689.55  4998.7  690.05
  5105.9  694.21  5148.1  700.43  5167.6  700.25  5200.8  702.91  5272.4  704.96
    5278  705.07  5316.8  705.69  5411.6  710.68  5485.4  717.65    5633  726.04
#Mann= 9 ,-1 , 0
  4279.4     .12       0  4489.7     .07       0  4605.6     .12       0
  4975.2    .035       0  4975.4    .035       0  4998.7    .035       0
  5167.6     .12       0  5272.4     .07       0    5278     .12       0
Bank Sta=4975.4,4998.7
XS Rating Curve= 0 ,0
Exp/Cntr=0.3,0.1

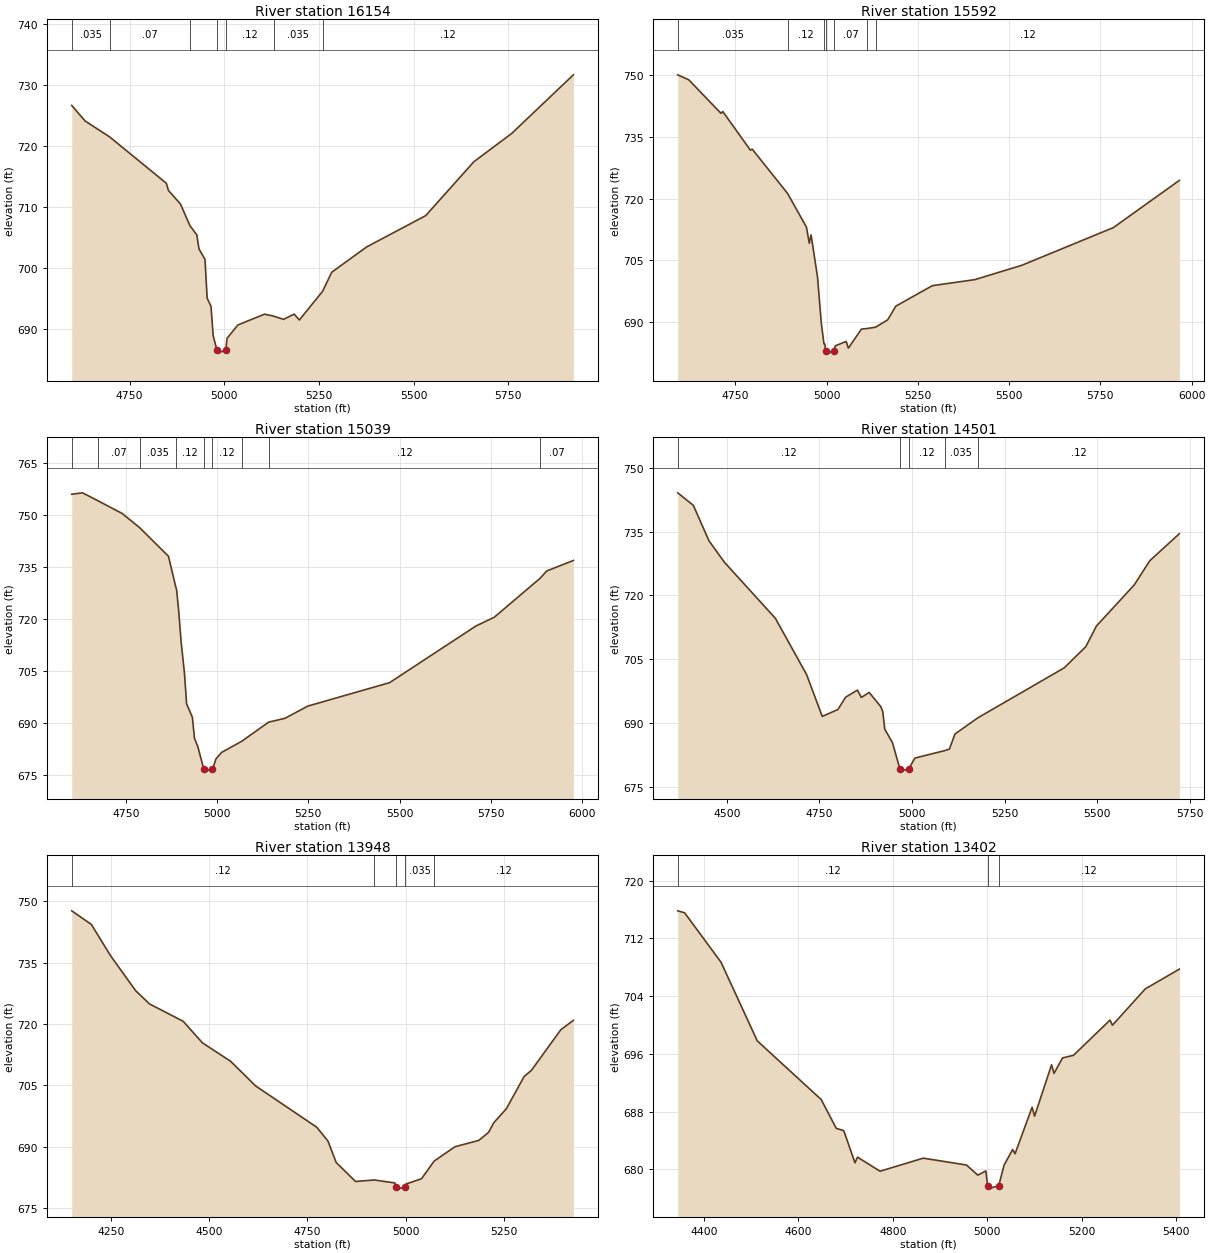
Type RM Length L Ch R = 1 ,16154   ,562,562,562
BEGIN DESCRIPTION:
Blieders Creek 36.0
END DESCRIPTION:
XS GIS Cut Line= 3
      2242574.98     13818174.99        2242225.       13817975.
      2241625.03     13817275.03
#Sta/Elev= 30
    4597  726.68  4632.2  724.13    4697  721.52  4846.8  713.91  4852.5  712.72
  4884.2   710.5  4909.2  706.95  4927.4  705.43  4933.1  703.12    4949  701.42
  4954.7  695.04  4964.8  693.72  4970.6   688.9  4980.4  686.53  4980.9  686.03
  5003.9  686.53  5007.2  688.46  5035.8  690.65    5106  692.42    5130  692.11
  5156.5  691.57  5184.5  692.44  5198.2  691.47  5259.5  696.17  5283.8  699.31
    5376  703.46  5531.9  708.59  5659.2  717.44  5759.1  722.08    5922   731.7
#Mann= 7 ,-1 , 0
    4597    .035       0    4697     .07       0  4909.2     .12       0
  4980.4     .05       0  5003.9     .12       0    5130    .035       0
  5259.5     .12       0
Bank Sta=4980.4,5003.9
XS Rating Curve= 0 ,0
Exp/Cntr=0.3,0.1

Type RM Length L Ch R = 1 ,15592   ,553,553,553
BEGIN DESCRIPTION:
Blieders Creek 35.0
END DESCRIPTION:
XS GIS Cut Line= 3
      2243075.02       13817625.        2242675.       13817675.
      2241874.96     13817124.97
#Sta/Elev= 30
  4592.4  750.16  4622.6  748.95  4710.8  740.78  4715.9   741.2  4791.5  731.78
  4796.5  732.03  4893.3  721.24  4945.1  713.01  4952.7  709.11  4957.7  711.14
  4975.4  700.82  4985.5  689.77  4992.9  684.57  4995.5   684.5  4997.3   682.8
  4997.8   682.3  5020.8   682.8  5023.9  684.06  5053.7  685.16  5059.8  683.52
  5095.6  688.16  5109.6  688.28  5134.4  688.63  5167.4   690.4  5189.7  693.75
  5289.8  698.75  5406.2  700.22  5534.7  703.71  5785.7  712.91  5966.4  724.42
#Mann= 7 ,-1 , 0
  4592.4    .035       0  4893.3     .12       0  4992.9     .07       0
  4997.3     .05       0  5020.8     .07       0  5109.6    .035       0
  5134.4     .12       0
Bank Sta=4997.3,5020.8
XS Rating Curve= 0 ,0
Exp/Cntr=0.3,0.1

Type RM Length L Ch R = 1 ,15039   ,538,538,538
BEGIN DESCRIPTION:
Blieders Creek 34.0
END DESCRIPTION:
XS GIS Cut Line= 3
      2243125.01     13817575.02        2242925.       13817225.
      2242374.97     13816424.96
#Sta/Elev= 30
  4602.2  755.96  4631.7  756.36  4672.8  754.14  4740.4  750.41  4788.1  746.34
  4867.1   738.1  4887.4  729.17  4889.4  728.43  4895.2   722.3  4901.7  713.57
    4911  704.35  4916.8  695.58  4932.6  691.74  4938.4  685.67  4947.7  683.21
    4964  676.71  4964.5  676.21  4987.6  676.71  4997.4  679.76  5012.8  681.61
  5067.8  684.81  5141.4  690.31    5186  691.42  5248.9  694.94  5472.8  701.69
  5709.2     718  5759.7  720.54  5885.5  731.79  5903.3  733.86  5976.2  736.88
#Mann= 9 ,-1 , 0
  4602.2    .035       0  4672.8     .07       0  4788.1    .035       0
  4887.4     .12       0    4964     .05       0  4987.6     .12       0
  5067.8     .07       0  5141.4     .12       0  5885.5     .07       0
Bank Sta=4964,4987.6
XS Rating Curve= 0 ,0
Exp/Cntr=0.3,0.1

Type RM Length L Ch R = 1 ,14501   ,553,553,553
BEGIN DESCRIPTION:
Blieders Creek 33.0
END DESCRIPTION:
XS GIS Cut Line= 3
      2243774.99       13816975.        2243175.       13816775.
      2242574.96     13816374.97
#Sta/Elev= 30
  4367.5  744.09  4409.7  741.15  4451.8  732.83    4494  727.73    4631  714.62
  4715.3  701.39  4757.5  691.58  4799.7  693.19  4820.7   696.1  4852.4  697.75
  4862.9  696.02    4884  697.21  4915.6  693.86  4920.9  692.66  4926.2  688.58
  4947.2  685.35  4967.1  679.22  4967.6  678.72  4990.7  679.22  5007.5  681.79
  5088.2  683.54  5100.6   683.9  5115.6  687.44  5177.7  691.26  5410.1  702.96
  5468.7  707.96  5497.2  712.79  5599.4  722.46  5641.4  728.15  5721.1  734.49
#Mann= 5 ,-1 , 0
  4367.5     .12       0  4967.1     .05       0  4990.7     .12       0
  5088.2    .035       0  5177.7     .12       0
Bank Sta=4967.1,4990.7
XS Rating Curve= 0 ,0
Exp/Cntr=0.3,0.1

Type RM Length L Ch R = 1 ,13948   ,546,546,546
BEGIN DESCRIPTION:
Blieders Creek 32.0
END DESCRIPTION:
XS GIS Cut Line= 3
      2243874.97     13816924.96        2243325.       13816275.
      2242925.02     13816125.01
#Sta/Elev= 30
  4149.2  747.69  4199.2  744.36  4248.6  736.63  4312.3  728.13  4347.4  724.91
  4433.2  720.66  4482.6  715.36    4554  710.89  4617.8  704.85  4773.8  694.73
  4802.3  691.35  4823.2  686.11  4872.6  681.46  4920.2  681.83  4972.6  681.11
  4975.1  680.09  4975.6  679.59  4998.8  680.09  5000.6  680.82  5040.7  682.13
  5072.9  686.45  5126.1  689.97  5186.6  691.51  5211.6  693.47  5224.9  695.84
  5256.9  699.25  5302.3  707.15    5321  708.67  5395.8   718.6  5427.8  720.89
#Mann= 5 ,-1 , 0
  4149.2     .12       0  4920.2    .035       0  4975.1    .035       0
  4998.8    .035       0  5072.9     .12       0
Bank Sta=4975.1,4998.8
XS Rating Curve= 0 ,0
Exp/Cntr=0.3,0.1

Type RM Length L Ch R = 1 ,13402   ,518,518,518
BEGIN DESCRIPTION:
Blieders Creek 31.0
END DESCRIPTION:
XS GIS Cut Line= 3
      2244075.02     13815524.99        2243475.       13815775.
      2243075.03     13815874.99
#Sta/Elev= 30
  4344.5  715.81  4359.1  715.54  4436.1   708.7    4513  697.79  4648.4  689.66
  4680.3  685.66  4696.1  685.36  4719.9   680.9  4725.3  681.68    4773  679.73
  4864.5  681.54  4956.1  680.59  4979.9  679.19  4997.1  679.77  5000.7  677.75
  5001.2  677.25  5024.4  677.75  5035.7  680.59  5053.8  682.74  5058.9  682.15
    5095   688.6  5100.2  687.36  5136.2  694.48  5141.4  693.29  5159.4  695.43
  5182.6  695.79  5259.9  700.67  5265.1  699.96  5334.7     705  5406.8  707.73
#Mann= 3 ,-1 , 0
  4344.5     .12       0  5000.7     .05       0  5024.4     .12       0
Bank Sta=5000.7,5024.4
XS Rating Curve= 0 ,0
Exp/Cntr=0.3,0.1

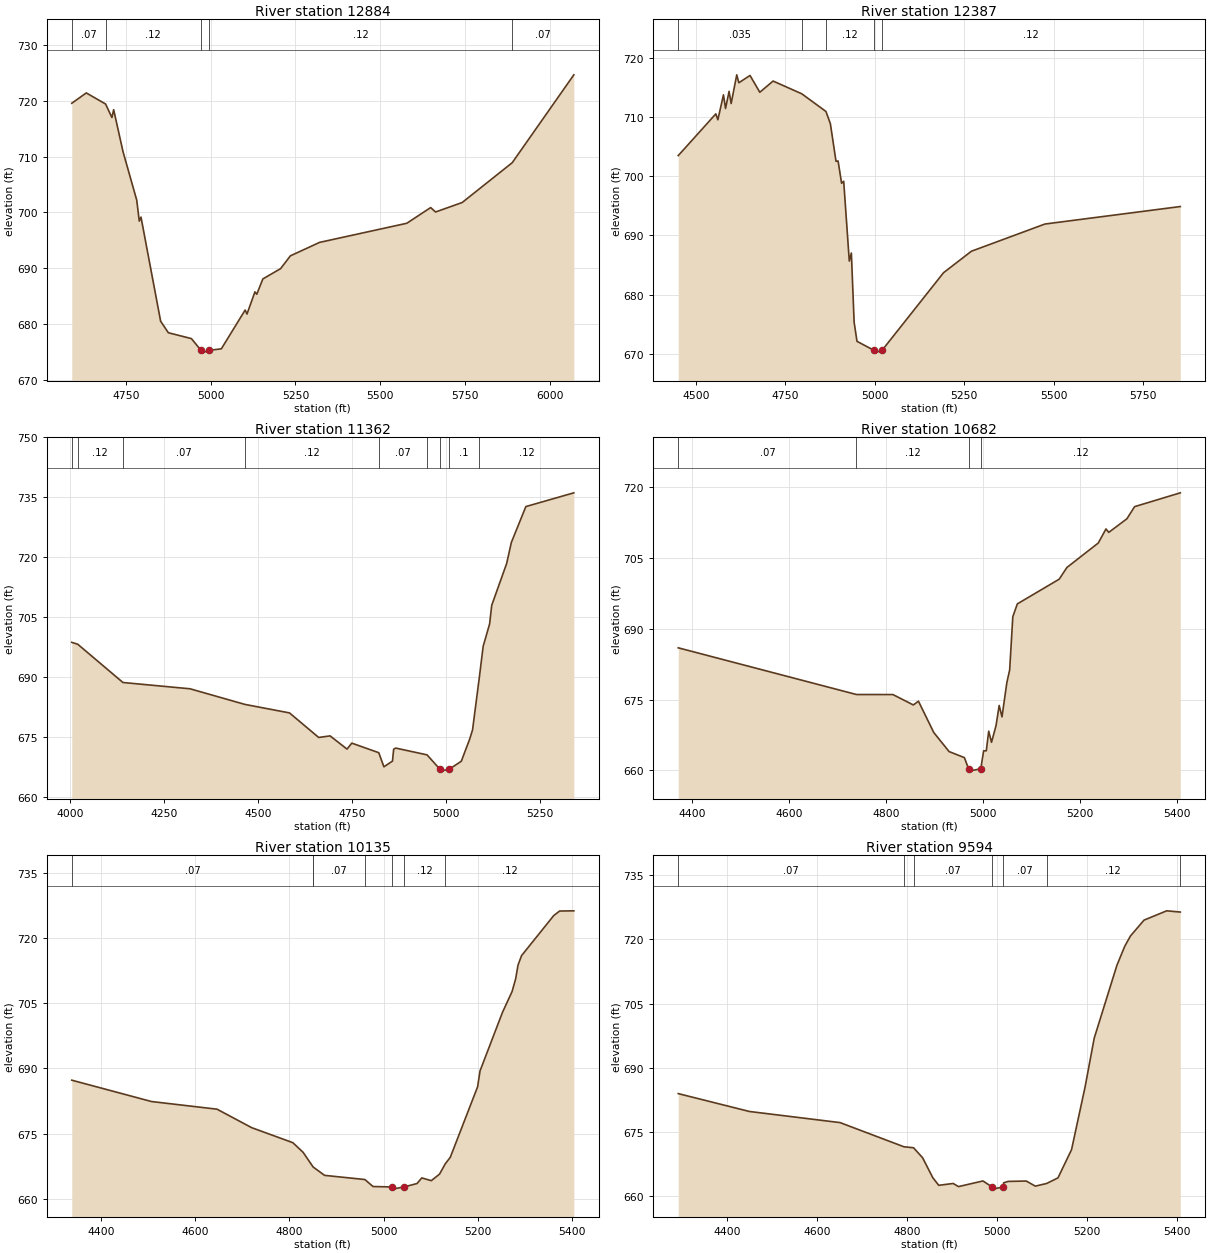
Type RM Length L Ch R = 1 ,12884   ,497,497,497
BEGIN DESCRIPTION:
Blieders Creek 30.0
END DESCRIPTION:
XS GIS Cut Line= 4
        2244075.       13815375.        2243675.       13815325.
      2243255.24     13815508.64      2242770.18     13815892.89
#Sta/Elev= 30
  4590.5  719.55  4633.3   721.4  4690.1  719.42  4708.9     717    4714   718.4
  4741.7  710.86    4782  702.22  4789.5  698.46  4794.6  699.17  4852.5  680.54
  4875.2  678.48  4943.2  677.43  4971.6  675.33  4972.1  674.83  4995.4  675.33
  5031.4   675.6  5101.6  682.54  5107.1  681.83  5130.4  685.79  5135.9  685.37
  5153.8  688.11  5206.1  689.95  5234.9  692.24  5321.1  694.65  5578.1  698.07
  5648.5  700.88    5663  700.09  5741.5  701.79  5888.9  708.91  6070.6  724.64
#Mann= 5 ,-1 , 0
  4590.5     .07       0  4690.1     .12       0  4971.6     .05       0
  4995.4     .12       0  5888.9     .07       0
Bank Sta=4971.6,4995.4
XS Rating Curve= 0 ,0
Exp/Cntr=0.3,0.1

Type RM Length L Ch R = 1 ,12387   ,1025,1025,1025
BEGIN DESCRIPTION:
X18260
END DESCRIPTION:
XS GIS Cut Line= 4
      2244198.21      13815154.5      2243712.12     13814868.06
      2243382.26     13814980.91      2243209.52     13815438.66
#Sta/Elev= 30
  4451.2  703.45  4556.1  710.49  4561.9   709.5  4577.5   713.7  4583.3   711.4
  4593.2  714.29    4599  712.24  4614.6  717.08  4620.4  715.74  4651.7  716.97
    4679  714.14  4716.1  716.03  4796.2  713.88  4863.7   710.9  4876.1  708.83
  4891.8   702.5  4897.6  702.54  4907.4  698.79  4913.3  699.12  4928.9  685.66
  4934.7  687.02  4942.4  675.35  4950.4  672.12    4997  670.63  4997.5  670.13
  5020.8  670.63    5192  683.69  5269.9  687.32  5475.3  691.91  5853.3  694.86
#Mann= 5 ,-1 , 0
  4451.2    .035       0  4796.2     .07       0  4863.7     .12       0
    4997     .05       0  5020.8     .12       0
Bank Sta=4997,5020.8
XS Rating Curve= 0 ,0
Exp/Cntr=0.3,0.1

Type RM Length L Ch R = 1 ,11362   ,680,680,680
BEGIN DESCRIPTION:
Blieders Creek 29.0
END DESCRIPTION:
XS GIS Cut Line= 3
      2243974.98     13814774.95      2243660.04     13813982.64
      2243224.97     13813774.98
#Sta/Elev= 30
  4004.6  698.75  4020.5  698.28  4140.7  688.71  4318.9  687.14    4465  683.23
  4583.4  681.11    4661  674.97  4691.4  675.36  4736.3  672.06    4749  673.55
  4820.7  671.16  4834.4  667.63  4857.2  669.06  4860.3  672.04  4865.8  672.31
    4949  670.62  4983.1  667.05  4983.6  666.55  5008.4  667.05  5040.1  669.02
  5062.2   674.5    5070  676.85  5087.5  689.59  5098.3  697.78  5115.4  703.37
    5121  708.01  5160.8   718.5  5173.1  723.71  5211.7   732.7  5339.3  736.14
#Mann= 9 ,-1 , 0
  4004.6     .07       0  4020.5     .12       0  4140.7     .07       0
    4465     .12       0  4820.7     .07       0    4949      .1       0
  4983.1     .05       0  5008.4      .1       0  5087.5     .12       0
Bank Sta=4983.1,5008.4
XS Rating Curve= 0 ,0
Exp/Cntr=0.3,0.1

Type RM Length L Ch R = 1 ,10682   ,547,547,547
BEGIN DESCRIPTION:
Blieders Creek 28.0
END DESCRIPTION:
XS GIS Cut Line= 3
      2243924.99     13814475.04        2244125.       13813875.
        2243925.     13813525.01
#Sta/Elev= 30
  4371.8  685.98  4739.3  676.09  4814.6  676.08  4856.7  673.88  4867.3  674.67
  4898.9  668.04  4930.5     664  4962.1  662.72  4970.6  660.36  4971.1  659.86
  4995.9  660.36  5001.7  664.16  5007.2  664.16  5012.2  668.32    5018  665.97
  5027.3  669.51  5033.8  673.77  5039.6  671.36  5049.6  678.61  5055.4  681.28
  5061.9  692.56  5071.2  695.28  5157.6  700.52  5173.5     703  5238.2  708.18
  5254.1  711.16  5259.8  710.43  5297.3  713.32  5313.1  715.88  5407.4  718.81
#Mann= 4 ,-1 , 0
  4371.8     .07       0  4739.3     .12       0  4970.6     .05       0
  4995.9     .12       0
Bank Sta=4970.6,4995.9
XS Rating Curve= 0 ,0
Exp/Cntr=0.3,0.1

Type RM Length L Ch R = 1 ,10135   ,541,541,541
BEGIN DESCRIPTION:
Blieders Creek 27.0
END DESCRIPTION:
XS GIS Cut Line= 3
      2244206.92     13814755.21        2244525.       13814175.
      2244925.01       13814125.
#Sta/Elev= 30
  4338.3  687.29  4507.5  682.37  4646.4  680.61  4719.9  676.35  4807.1   672.9
  4828.9  670.68  4849.6  667.39    4850  667.31  4874.5  665.37  4959.9  664.41
  4977.2   662.8  5017.6   662.7  5018.1   662.2  5042.9   662.7  5070.5  663.49
  5080.6  664.78  5100.8  664.15  5118.4  665.67  5130.3  668.01  5141.1  669.54
    5199  685.77  5204.1  689.41  5251.9  702.95  5272.1   707.7  5279.6  710.59
  5284.7  713.78  5292.2  715.97  5360.3  725.18  5372.9  726.24  5403.1  726.29
#Mann= 7 ,-1 , 0
  4338.3     .07       0  4849.6     .12       0    4850     .07       0
  4959.9     .12       0  5017.6     .05       0  5042.9     .12       0
  5130.3     .12       0
Bank Sta=5017.6,5042.9
XS Rating Curve= 0 ,0
Exp/Cntr=0.3,0.1

Type RM Length L Ch R = 1 ,9594    ,585,585,585
BEGIN DESCRIPTION:
Blieders Creek 26.0
END DESCRIPTION:
XS GIS Cut Line= 3
      2244588.85     13815154.53        2244925.       13814525.
        2244975.     13814124.97
#Sta/Elev= 30
  4290.7  683.98  4448.9  679.81  4650.7  677.21  4792.7  671.57  4814.1  671.34
  4834.3     669    4857  664.34  4870.2  662.57  4902.3     663  4914.1  662.27
  4968.6  663.59  4988.8  662.18  4989.3  661.68  5014.2  662.18  5014.4  663.14
  5024.5  663.48  5064.8  663.57    5085  662.38  5110.3     663  5135.4  664.31
  5165.6   670.9  5195.8   685.6    5216  696.92  5266.4  713.91    5284   718.4
  5296.6  720.77  5326.8  724.48  5377.2  726.65  5406.8  726.37  5407.5  726.37
#Mann= 7 ,-1 , 0
  4290.7     .07       0  4792.7    .035       0  4814.1     .07       0
  4988.8     .05       0  5014.2     .07       0  5110.3     .12       0
  5406.8     .07       0
Bank Sta=4988.8,5014.2
XS Rating Curve= 0 ,0
Exp/Cntr=0.3,0.1

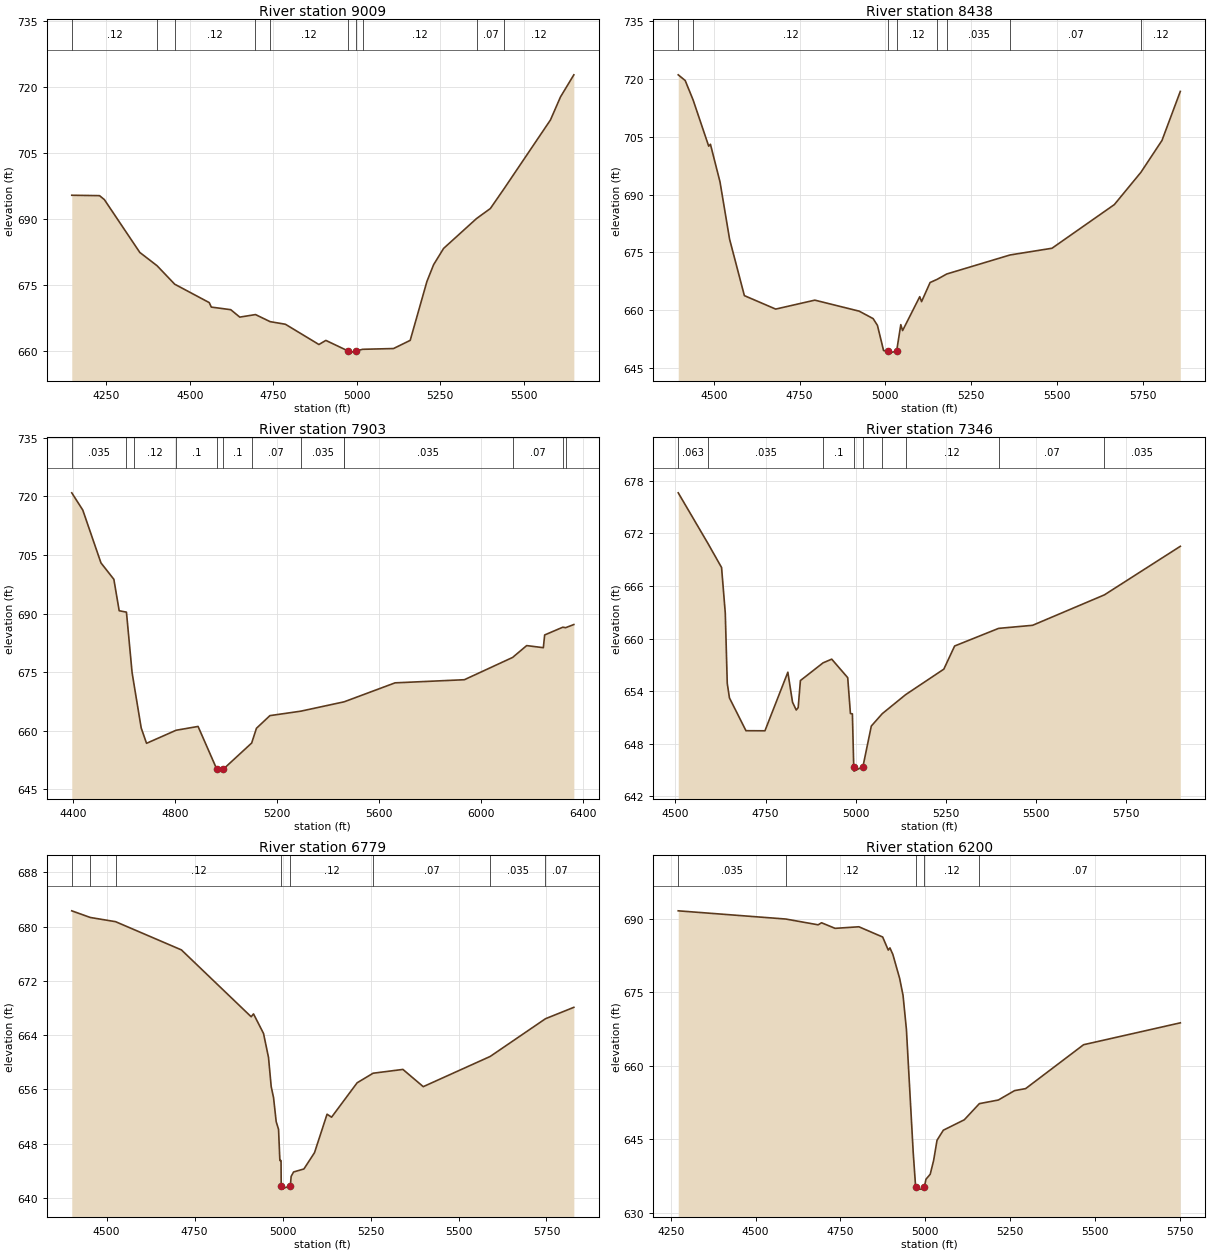
Type RM Length L Ch R = 1 ,9009    ,571,571,571
BEGIN DESCRIPTION:
Blieders Creek 25.0
END DESCRIPTION:
XS GIS Cut Line= 3
      2244857.93     13815553.86        2245375.       13814875.
        2245375.     13814225.05
#Sta/Elev= 30
  4146.7  695.49  4229.8   695.4  4244.3   694.5  4350.4   682.5  4402.2  679.47
  4454.9  675.28  4558.3   671.1  4564.5  670.08  4622.7  669.49  4649.8   667.8
  4696.8  668.38  4740.7  666.77  4786.4  666.18  4886.7  661.58  4907.5  662.51
  4973.8  660.12  4974.3  659.62  4999.2  660.12  5017.4  660.49    5110  660.66
    5160  662.52    5210  675.88    5230   679.7    5260  683.41  5358.7   690.2
    5400  692.47  5442.2   697.1    5580   712.6    5610  717.83    5650  722.85
#Mann= 10 ,-1 , 0
  4146.7     .12       0  4402.2    .063       0  4454.9     .12       0
  4696.8     .07       0  4740.7     .12       0  4973.8     .05       0
  4999.2     .12       0  5017.4     .12       0  5358.7     .07       0
  5442.2     .12       0
Bank Sta=4973.8,4999.2
XS Rating Curve= 0 ,0
Exp/Cntr=0.3,0.1

Type RM Length L Ch R = 1 ,8438    ,535,535,535
BEGIN DESCRIPTION:
Blieders Creek 24.0
END DESCRIPTION:
XS GIS Cut Line= 3
      2245774.99     13815675.04        2245875.       13815075.
      2245575.01     13814275.02
#Sta/Elev= 30
  4396.4  721.06  4416.7  719.58  4439.8  714.52  4485.2  702.54  4490.2  703.04
  4518.1  693.27    4546   678.4  4589.1  663.75  4680.3  660.26  4794.4  662.58
  4923.6  659.72  4964.2  657.79  4976.8  656.02  4994.6  649.51  5007.1  649.33
  5007.6  648.83  5032.6  649.33  5044.8  656.22  5050.1  654.69    5100  663.48
  5105.3  662.19  5130.2  667.16  5150.7  667.98  5178.7  669.37  5363.3  674.31
  5485.3  676.05  5666.9  687.38  5744.4  695.77  5805.7  704.03  5859.1  716.76
#Mann= 8 ,-1 , 0
  4396.4    .035       0  4439.8     .12       0  5007.1     .05       0
  5032.6     .12       0  5150.7     .07       0  5178.7    .035       0
  5363.3     .07       0  5744.4     .12       0
Bank Sta=5007.1,5032.6
XS Rating Curve= 0 ,0
Exp/Cntr=0.3,0.1

Type RM Length L Ch R = 1 ,7903    ,557,557,557
BEGIN DESCRIPTION:
Blieders Creek 23.0
END DESCRIPTION:
XS GIS Cut Line= 3
        2245825.       13815675.        2246325.       13815325.
      2245924.99     13814024.97
#Sta/Elev= 30
  4395.3   720.9  4438.5  716.49  4509.9  702.96  4560.5  698.76  4581.4  690.71
  4609.9  690.35    4632  674.91  4639.9  671.73  4667.8  660.71  4688.7  656.77
  4804.5  660.11    4891  661.09  4964.5  650.15    4965  649.65    4990  650.15
  5101.3  656.84  5120.1  660.62    5173  663.86  5294.3     665    5464  667.39
  5464.1  667.39  5664.1  672.25  5936.1  673.05  6125.6  678.76  6180.7  681.79
  6246.1  681.25  6251.3  684.51  6322.6   686.5  6333.4  686.37  6365.8  687.18
#Mann= 13 ,-1 , 0
  4395.3    .035       0  4609.9    .063       0  4639.9     .12       0
  4804.5      .1       0  4964.5     .05       0    4990      .1       0
  5101.3     .07       0  5294.3    .035       0    5464     .07       0
  5464.1    .035       0  6125.6     .07       0  6322.6    .035       0
  6333.4     .07       0
Bank Sta=4964.5,4990
XS Rating Curve= 0 ,0
Exp/Cntr=0.3,0.1

Type RM Length L Ch R = 1 ,7346    ,567,567,567
BEGIN DESCRIPTION:
Blieders Creek 22.0
END DESCRIPTION:
XS GIS Cut Line= 3
      2246625.02     13815924.96        2246825.       13815475.
      2246324.99     13814724.99
#Sta/Elev= 30
  4507.7  676.62    4591  670.79    4628   668.1  4638.3  662.91  4643.8  654.88
  4649.9  653.23  4695.7  649.49  4748.4  649.48    4812  656.16    4825  652.74
  4835.3  651.85  4840.7  652.13  4846.9  655.21  4909.8  657.23  4933.8  657.65
  4978.2  655.54  4985.7  651.45  4991.2  651.41  4994.9  645.38  4995.4  644.88
  5020.4  645.38  5043.7  650.02    5074  651.43  5138.9   653.6    5245  656.51
    5275  659.15    5397  661.16  5491.4  661.51  5690.7  664.98  5901.5  670.52
#Mann= 9 ,-1 , 0
  4507.7    .063       0    4591    .035       0  4909.8      .1       0
  4994.9     .05       0  5020.4      .1       0    5074      .1       0
  5138.9     .12       0    5397     .07       0  5690.7    .035       0
Bank Sta=4994.9,5020.4
XS Rating Curve= 0 ,0
Exp/Cntr=0.3,0.1

Type RM Length L Ch R = 1 ,6779    ,579,579,579
BEGIN DESCRIPTION:
Blieders Creek 21.0
END DESCRIPTION:
XS GIS Cut Line= 3
      2247670.47     13815519.12        2247225.       13815125.
      2246524.96     13814674.98
#Sta/Elev= 30
  4400.8  682.31  4453.5  681.33  4525.3  680.71  4712.5  676.55  4910.7   666.7
  4917.4  667.12  4945.8  664.24    4960   660.7  4967.6  656.42  4974.3  654.78
  4981.8  651.24  4988.5  650.11  4992.3  645.51  4995.6  645.51  4996.1   641.8
  4996.6   641.3  5022.1   641.8  5024.3  643.18  5031.3  643.83  5060.6  644.27
  5090.7  646.67  5126.4  652.34  5139.2   651.9  5211.9  656.97  5257.2  658.38
    5342  658.94  5399.8   656.4    5590  660.85  5747.2  666.41  5827.8  668.09
#Mann= 8 ,-1 , 0
  4400.8     .12       0  4453.5     .07       0  4525.3     .12       0
  4996.1     .05       0  5022.1     .12       0  5257.2     .07       0
    5590    .035       0  5747.2     .07       0
Bank Sta=4996.1,5022.1
XS Rating Curve= 0 ,0
Exp/Cntr=0.3,0.1

Type RM Length L Ch R = 1 ,6200    ,531,531,531
BEGIN DESCRIPTION:
Blieders Creek 20.0
END DESCRIPTION:
XS GIS Cut Line= 3
      2247956.95     13814607.64        2247225.       13814575.
      2246481.21     13814503.47
#Sta/Elev= 30
    4272  691.67  4589.3  689.99  4684.4  688.81  4694.4  689.23  4734.4  688.09
  4804.5  688.41  4874.6  686.32    4891  683.65    4896   684.1  4904.6  682.76
  4924.6  677.87  4934.6  674.41  4944.6  667.43  4964.6   642.3  4971.7   635.3
  4972.2   634.8  4997.2   634.8  4997.7   635.3  5002.2  636.82  5014.7  637.84
  5024.8  640.66  5034.8  644.79  5053.4  646.84  5115.2  648.97  5159.6  652.27
  5215.6  653.01  5263.4  654.93    5296  655.34  5466.8  664.31  5751.9  668.78
#Mann= 5 ,-1 , 0
    4272    .035       0  4589.3     .12       0  4971.7     .05       0
  4997.7     .12       0  5159.6     .07       0
Bank Sta=4971.7,4997.7
XS Rating Curve= 0 ,0
Exp/Cntr=0.3,0.1