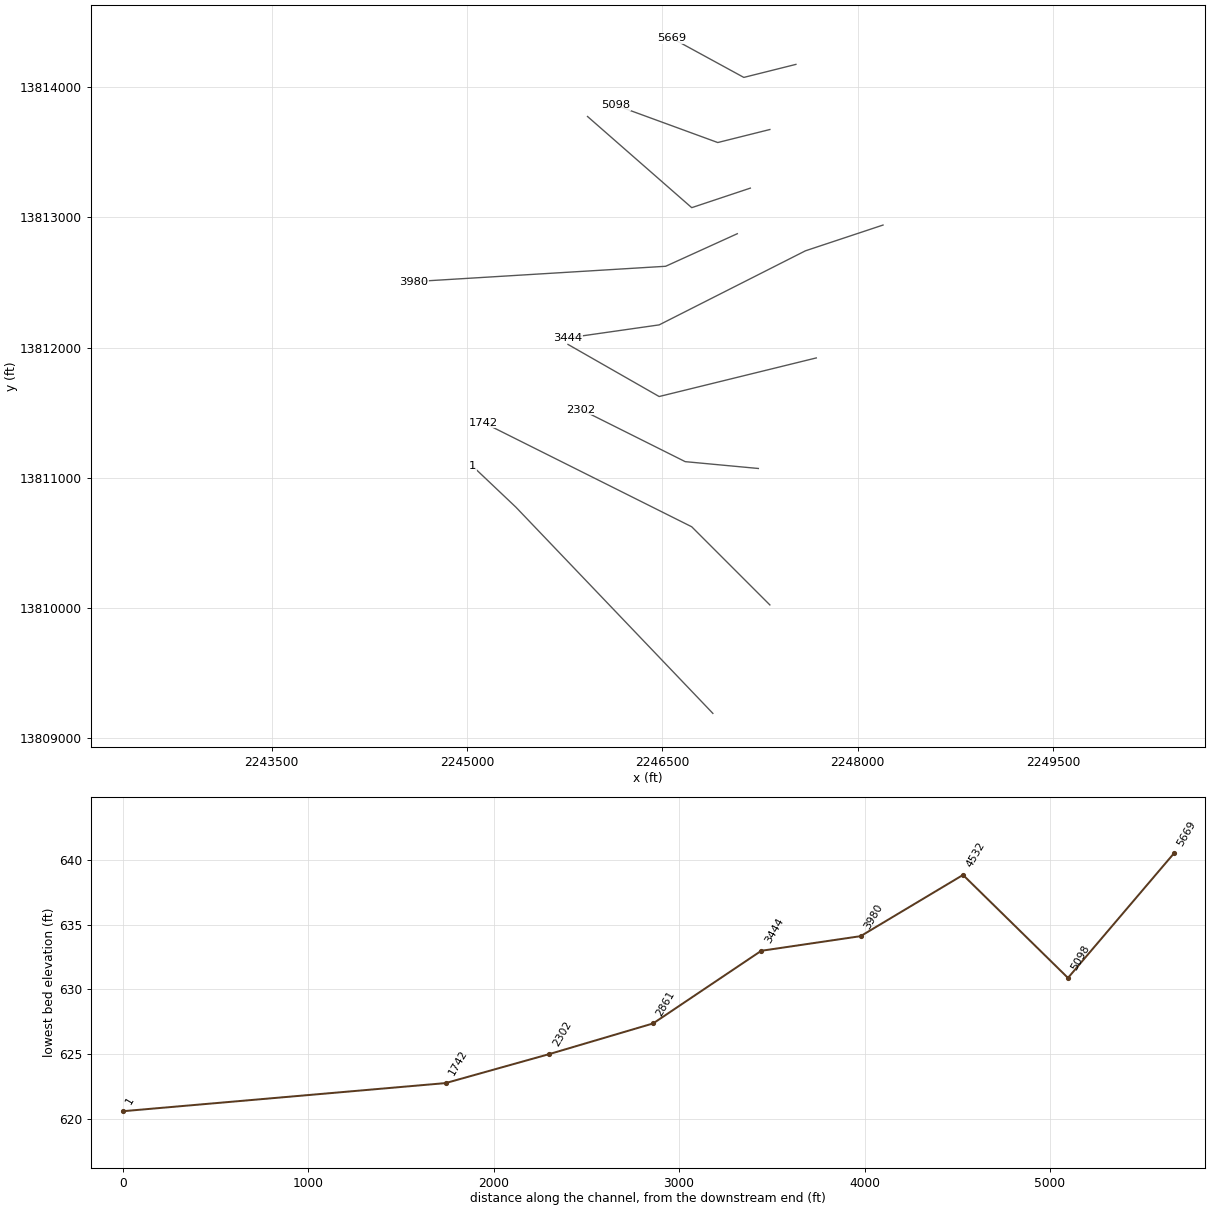
HEC-RAS study Blieders Creek.prj: Blieders Creek Base Level Engineering

--- Blieders Creek.g01 (geometry) --- (continued)

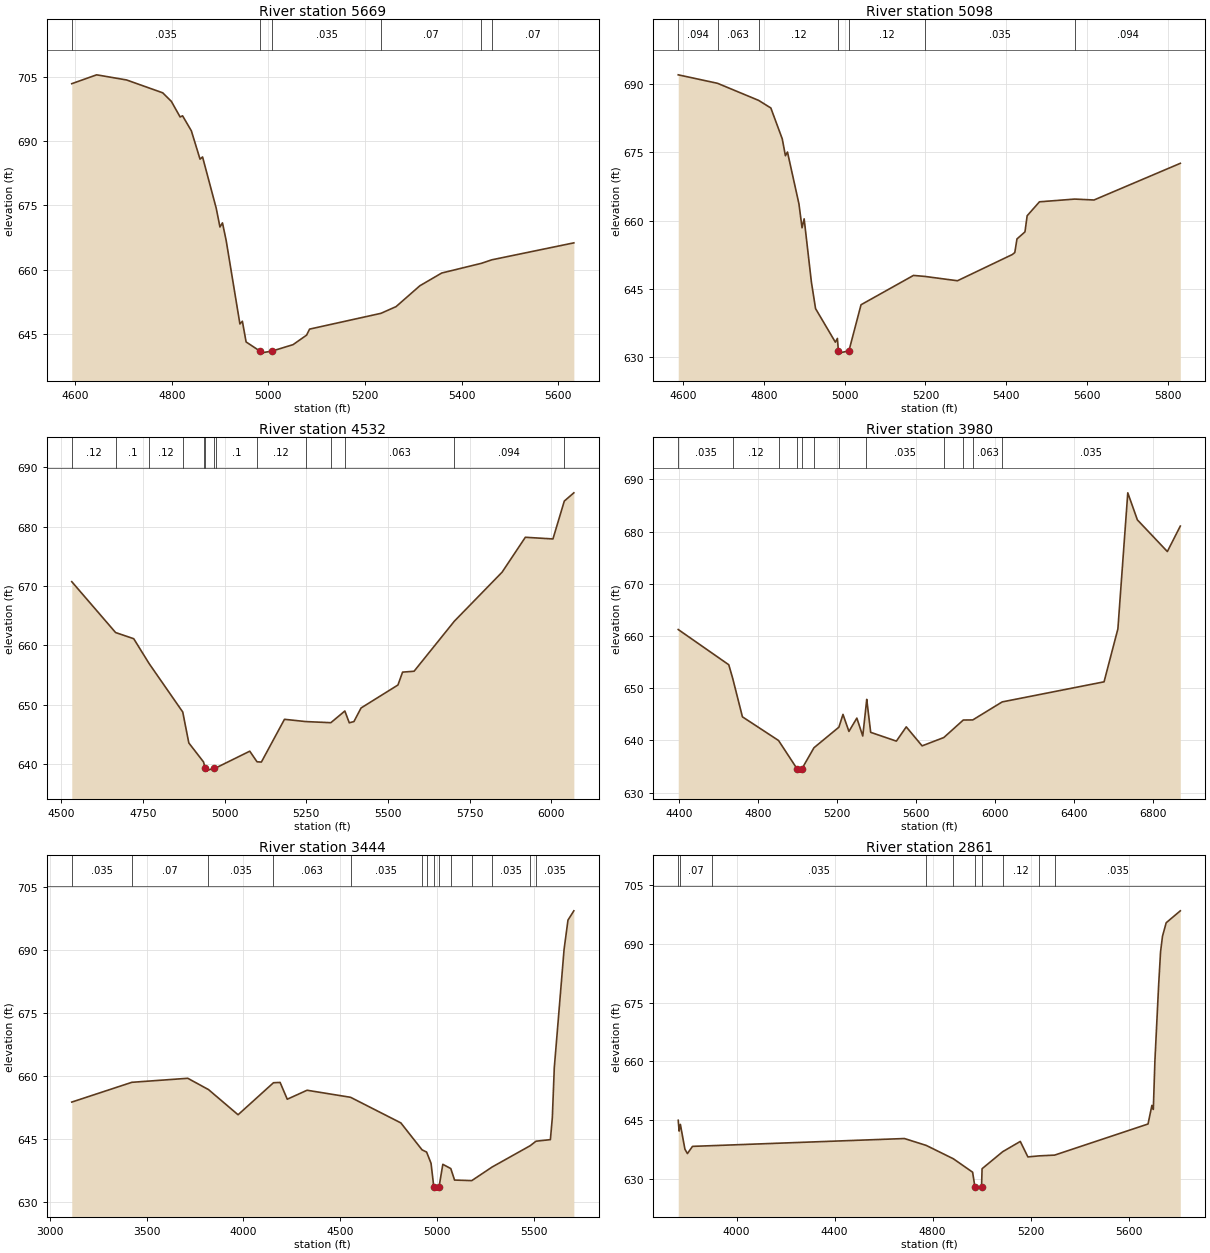
Type RM Length L Ch R = 1 ,5669    ,571,571,571
BEGIN DESCRIPTION:
Blieders Creek 19.0
END DESCRIPTION:
XS GIS Cut Line= 3
      2247524.97     13814174.99        2247125.       13814075.
      2246574.98     13814375.01
#Sta/Elev= 30
  4593.2  703.46  4644.7  705.53  4706.6  704.33  4781.3  701.33  4799.3  699.32
  4817.4  695.68  4822.5  695.95  4840.6  692.45  4858.6  685.82  4863.8  686.34
  4892.1  674.34  4899.8  669.97    4905  670.93  4912.7  666.79  4941.1  647.31
  4946.2  647.94  4953.9   643.1  4982.2  640.99  4982.7  640.49  5008.2  640.99
    5051  642.47    5079  644.69  5085.2   646.1  5232.9  649.79  5264.2  651.36
  5313.5  656.24  5358.6  659.21  5440.8  661.48  5462.4   662.3    5632  666.26
#Mann= 6 ,-1 , 0
  4593.2    .035       0  4982.2    .035       0  5008.2    .035       0
  5232.9     .07       0  5440.8    .035       0  5462.4     .07       0
Bank Sta=4982.2,5008.2
XS Rating Curve= 0 ,0
Exp/Cntr=0.3,0.1

Type RM Length L Ch R = 1 ,5098    ,566,566,566
BEGIN DESCRIPTION:
Blieders Creek 18.0
END DESCRIPTION:
XS GIS Cut Line= 3
      2247325.05     13813675.01        2246925.       13813575.
      2246144.24     13813860.54
#Sta/Elev= 30
  4587.6  691.99  4684.9  690.13  4786.7  686.38    4817  684.71  4845.3  677.92
  4853.1  674.23  4858.2  675.04  4886.6  663.66  4894.3  658.41  4899.5  660.37
  4917.5  646.47  4927.8  640.66  4976.8   633.3  4981.9  634.12  4984.3  631.39
  4984.8  630.89  5010.4  631.39  5040.4  641.51  5170.3  647.95  5198.6  647.73
  5279.3  646.78  5415.2  652.54  5421.3  652.97  5426.7  655.96  5446.5  657.51
  5451.9  661.05  5482.4  664.11  5569.8  664.71  5617.5  664.51  5831.3  672.56
#Mann= 7 ,-1 , 0
  4587.6    .094       0  4684.9    .063       0  4786.7     .12       0
  4984.3     .05       0  5010.4     .12       0  5198.6    .035       0
  5569.8    .094       0
Bank Sta=4984.3,5010.4
XS Rating Curve= 0 ,0
Exp/Cntr=0.3,0.1

Type RM Length L Ch R = 1 ,4532    ,552,552,552
BEGIN DESCRIPTION:
Blieders Creek 17.0
END DESCRIPTION:
XS GIS Cut Line= 3
      2247174.98     13813224.99        2246725.       13813075.
      2245925.03     13813774.98
#Sta/Elev= 30
  4531.7  670.75  4665.9  662.18  4721.4  661.14  4768.7  656.94  4871.5  648.79
  4890.1  643.58  4935.1  640.38  4940.3  639.33  4940.8  638.83  4966.4  639.33
  4974.3  639.41  5076.7  642.19    5099   640.4  5112.3  640.36    5183  647.56
  5247.9  647.18    5325  646.99  5367.8  648.96  5381.4  646.97  5395.6  647.18
  5417.5  649.47  5530.4  653.34  5544.6  655.51  5579.8  655.66  5703.1  664.09
  5849.3  672.35  5920.5  678.23    6005  677.95  6039.8  684.33    6069  685.72
#Mann= 14 ,-1 , 0
  4531.7     .12       0  4665.9      .1       0  4768.7     .12       0
  4871.5      .1       0  4935.1     .12       0  4940.3     .05       0
  4966.4     .12       0  4974.3      .1       0    5099     .12       0
  5247.9      .1       0    5325     .12       0  5367.8    .063       0
  5703.1    .094       0  6039.8    .035       0
Bank Sta=4940.3,4966.4
XS Rating Curve= 0 ,0
Exp/Cntr=0.3,0.1

Type RM Length L Ch R = 1 ,3980    ,536,536,536
BEGIN DESCRIPTION:
Blieders Creek 16.0
END DESCRIPTION:
XS GIS Cut Line= 3
      2247075.04     13812875.02        2246525.       13812625.
      2244589.39     13812506.98
#Sta/Elev= 30
  4395.8  661.24  4651.8  654.49  4671.4  651.93    4721  644.51  4903.9  639.98
  4996.9  634.61  4997.4  634.11  5023.1  634.61  5083.4  638.59  5209.7  642.53
  5230.4  644.98  5260.5  641.72  5300.6  644.27  5330.6  640.84  5347.2   646.6
  5350.7  647.86  5370.7  641.54  5500.9  639.86    5551  642.59  5631.2  638.95
  5741.3  640.55  5839.8   643.9  5887.9  643.92  6036.8  647.37  6552.9  651.22
    6623  661.36  6673.1  687.43  6721.7  682.25  6873.5  676.18  6939.2  681.06
#Mann= 12 ,-1 , 0
  4395.8    .035       0  4671.4     .12       0  4903.9    .035       0
  4996.9    .035       0  5023.1    .035       0  5083.4      .1       0
  5209.7     .07       0  5347.2    .035       0  5741.3    .094       0
  5839.8    .035       0  5887.9    .063       0  6036.8    .035       0
Bank Sta=4996.9,5023.1
XS Rating Curve= 0 ,0
Exp/Cntr=0.3,0.1

Type RM Length L Ch R = 1 ,3444    ,583,583,583
BEGIN DESCRIPTION:
Blieders Creek 15.0
END DESCRIPTION:
XS GIS Cut Line= 4
       2248193.8     13812941.54      2247598.22     13812743.75
        2246475.       13812175.      2245774.98       13812075.
#Sta/Elev= 30
  3113.9  653.72  3424.2  658.43  3713.2  659.39  3820.2   656.7    3973   650.7
  4155.9  658.33  4190.2   658.4  4227.1   654.4  4329.4  656.54  4554.2  654.86
  4813.9  648.76  4923.5  642.34    4947  641.81  4969.9  639.13  4984.2  633.48
  4984.7  632.98  5011.1  633.48  5030.8  638.89  5071.9  637.88  5091.4  635.14
  5180.4  635.01  5285.9  638.26  5481.9  643.32  5512.2   644.4  5586.4  644.77
  5596.5  650.02  5606.6  661.89  5657.1  690.08  5677.3  697.08  5707.6  699.29
#Mann= 14 ,-1 , 0
  3113.9    .035       0  3424.2     .07       0  3820.2    .035       0
  4155.9    .063       0  4554.2    .035       0  4923.5     .07       0
    4947    .035       0  4984.2    .035       0  5011.1    .035       0
  5071.9     .12       0  5180.4     .07       0  5285.9    .035       0
  5481.9    .094       0  5512.2    .035       0
Bank Sta=4984.2,5011.1
XS Rating Curve= 0 ,0
Exp/Cntr=0.3,0.1

Type RM Length L Ch R = 1 ,2861    ,559,559,559
BEGIN DESCRIPTION:
Blieders Creek 14.0
END DESCRIPTION:
XS GIS Cut Line= 3
      2247681.43     13811921.34        2246475.       13811625.
      2245775.02     13812024.99
#Sta/Elev= 30
  3761.9  644.95  3765.4  642.19  3767.1  642.75  3770.6   643.9  3789.1  637.59
  3799.4  636.45    3820  638.29  3899.3  638.47  4684.8  640.29    4774  638.53
  4884.5  635.12    4963   631.7  4972.5  627.88    4973  627.38  4999.4  627.88
  5001.6  632.59  5085.9  636.94  5157.5  639.55  5188.5   635.6  5235.3  635.87
  5297.5  636.06  5678.7     644  5694.5  648.75  5700.3  647.72  5706.8  660.16
  5721.9  679.32  5729.8  687.92  5737.7  691.92  5752.8  695.36  5810.4   698.4
#Mann= 10 ,-1 , 0
  3761.9    .035       0  3767.1     .07       0  3899.3    .035       0
    4774     .07       0  4884.5     .12       0  4972.5     .05       0
  4999.4     .12       0  5085.9     .12       0  5235.3     .07       0
  5297.5    .035       0
Bank Sta=4972.5,4999.4
XS Rating Curve= 0 ,0
Exp/Cntr=0.3,0.1

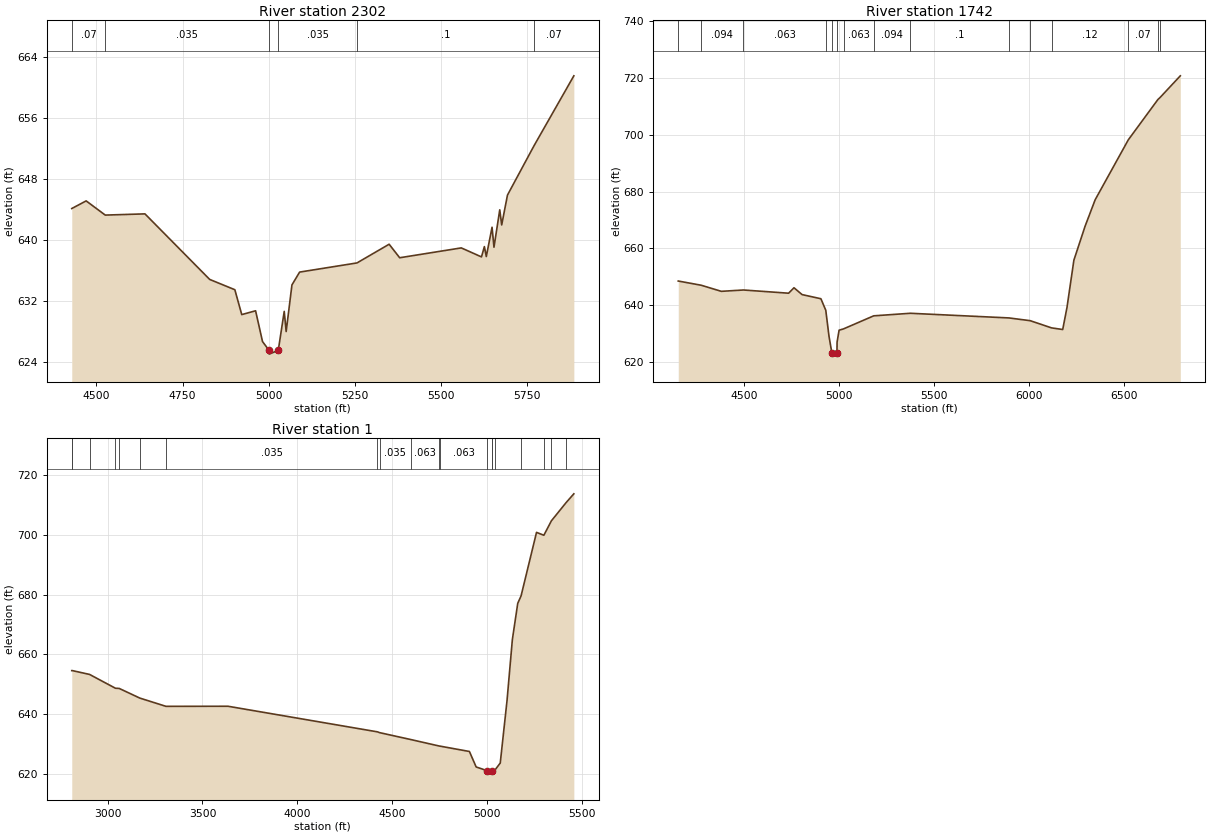
Type RM Length L Ch R = 1 ,2302    ,560,560,560
BEGIN DESCRIPTION:
Blieders Creek 13.0
END DESCRIPTION:
XS GIS Cut Line= 3
      2247236.65     13811072.52        2246675.       13811125.
      2245875.02     13811524.99
#Sta/Elev= 30
  4428.2   644.1    4470   645.1  4525.5  643.24  4640.8   643.4  4828.8  634.81
  4901.9  633.46    4922   630.2  4962.2   630.7  4982.3  626.67  5001.2  625.52
  5001.7  625.02  5028.1  625.52  5045.4  630.62    5051  627.98  5067.8  634.09
  5090.1  635.77  5256.7  636.97  5350.1  639.42  5380.8  637.65  5559.7  638.94
  5618.4  637.76  5626.8  639.11  5632.4  637.81  5649.1  641.65  5654.7  639.03
  5671.5  643.93  5677.1  641.95  5693.9  645.86  5770.8  652.31  5886.7  661.49
#Mann= 6 ,-1 , 0
  4428.2     .07       0  4525.5    .035       0  5001.2    .035       0
  5028.1    .035       0  5256.7      .1       0  5770.8     .07       0
Bank Sta=5001.2,5028.1
XS Rating Curve= 0 ,0
Exp/Cntr=0.3,0.1

Type RM Length L Ch R = 1 ,1742    ,1741,1741,1741
BEGIN DESCRIPTION:
Blieders Creek 12.0
END DESCRIPTION:
XS GIS Cut Line= 3
      2247325.01     13810024.99        2246725.       13810625.
        2245125.       13811425.
#Sta/Elev= 30
  4156.1  648.53  4276.6  647.05  4382.4   644.9  4498.9  645.37  4735.9  644.24
  4764.2  646.16  4806.7  643.75  4905.6  642.29  4931.2  638.22  4948.1  629.06
  4962.9  623.28  4963.4  622.78  4989.9  623.28  4990.5     627  5001.1  631.21
  5024.4  631.67    5183  636.27  5375.4  637.17  5893.3  635.53  6005.1  634.56
  6116.9  632.03  6175.8  631.45  6198.1  639.18  6234.5  655.89  6293.2  667.82
  6346.3  677.17  6520.3  698.27  6675.9  712.48  6687.4   713.2  6793.5  720.82
#Mann= 15 ,-1 , 0
  4156.1      .1       0  4276.6    .094       0  4498.9    .063       0
  4931.2    .035       0  4962.9    .035       0  4989.9    .035       0
  5024.4    .063       0    5183    .094       0  5375.4      .1       0
  5893.3    .094       0  6005.1    .063       0  6116.9     .12       0
  6520.3     .07       0  6675.9     .12       0  6687.4    .094       0
Bank Sta=4962.9,4989.9
XS Rating Curve= 0 ,0
Exp/Cntr=0.3,0.1

Type RM Length L Ch R = 1 ,1       ,0,0,0
BEGIN DESCRIPTION:
Blieders Creek 11.0tiein
END DESCRIPTION:
XS GIS Cut Line= 3
      2246887.35     13809192.33      2245375.14      13810775.4
      2245042.27     13811090.75
#Sta/Elev= 30
  2810.6  654.59  2814.2  654.59  2904.6  653.31  3040.9  648.69    3061  648.62
  3169.3   645.4  3307.5  642.63  3634.6  642.66  4422.8  634.09  4433.9  633.83
  4601.1  631.48  4748.3  629.35  4754.4  629.29  4907.7  627.52  4943.2  622.34
  5000.3  621.11  5000.8  620.61  5027.4  621.11  5028.7  621.13  5040.5  621.15
  5070.3  623.66  5105.9  644.48  5134.2  664.99  5162.5   677.1  5180.1   679.6
  5261.6  700.87  5300.3   699.9    5340  704.73    5418  710.86  5458.4  713.77
#Mann= 20 ,-1 , 0
  2810.6    .063       0  2814.2    .094       0  2904.6    .035       0
  3040.9    .094       0    3061    .035       0  3169.3    .063       0
  3307.5    .035       0  4422.8    .063       0  4433.9    .035       0
  4601.1    .063       0  4748.3    .094       0  4754.4    .063       0
  5000.3     .05       0  5027.4    .063       0  5028.7    .035       0
  5040.5    .063       0  5180.1    .094       0  5300.3    .035       0
    5340    .063       0    5418    .035       0
Bank Sta=5000.3,5027.4
XS Rating Curve= 0 ,0
Exp/Cntr=0.3,0.1

Chan Stop Cuts=-1
Use User Specified Reach Order=0
Composite Channel Slope=5