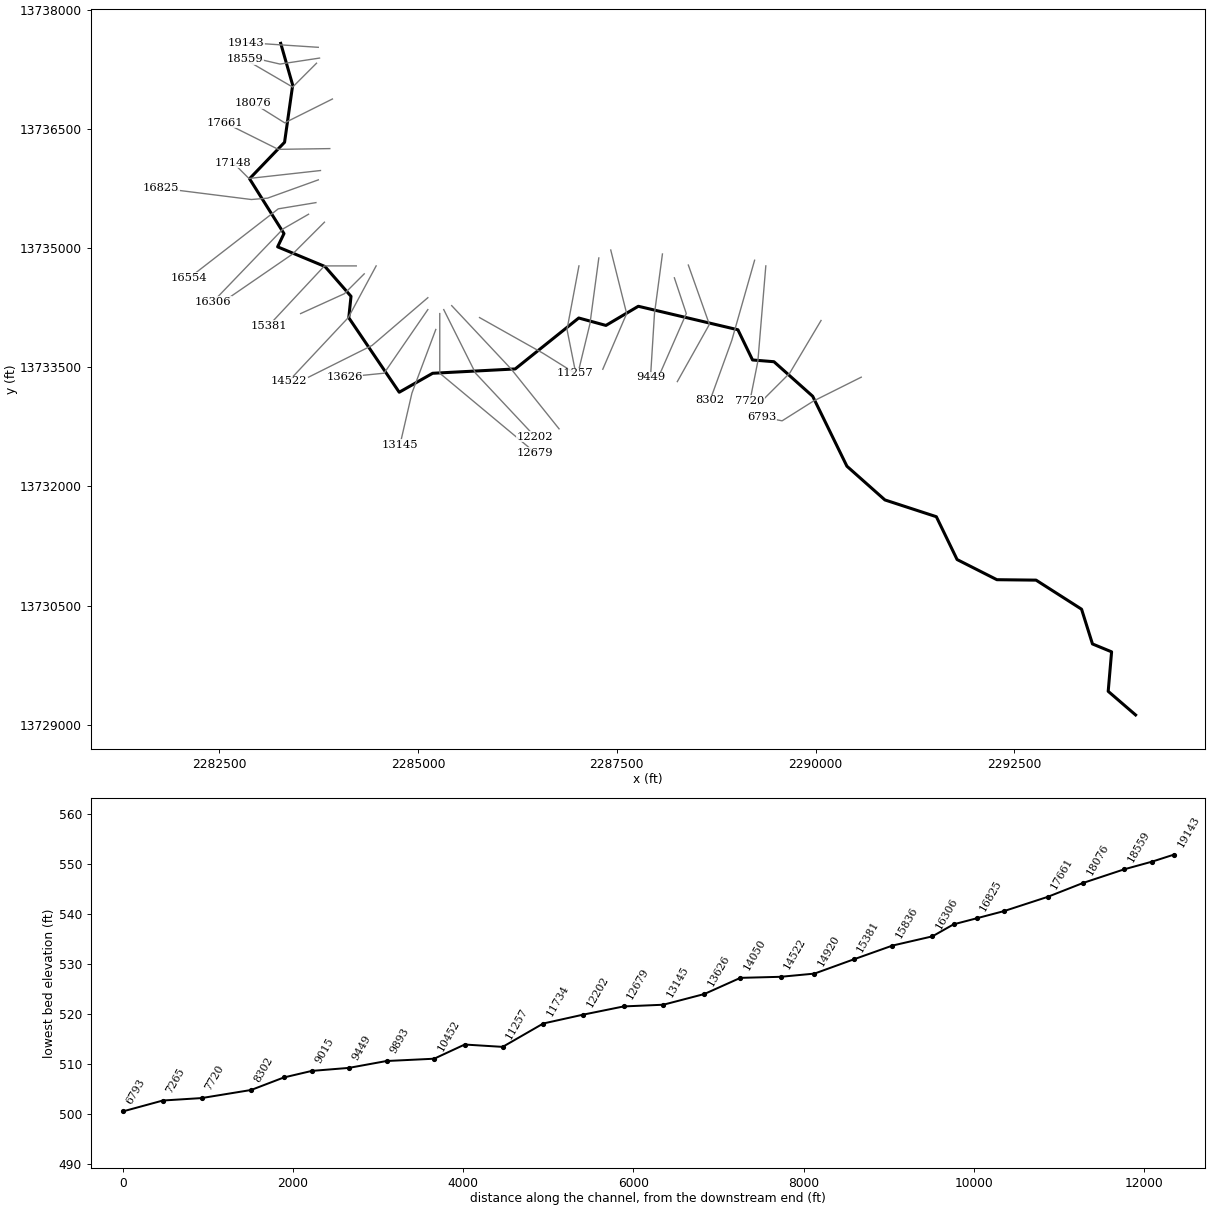
--- CAMPBELL BRANCH.prj (project) ---

Proj Title=CAMPBELL BRANCH Base Level Engineering
Current Plan=p01
Default Exp/Contr=0.3,0.1
English Units
Geom File=g01
Flow File=f01
Plan File=p01
Y Axis Title=Elevation
X Axis Title(PF)=Main Channel Distance
X Axis Title(XS)=Station
BEGIN DESCRIPTION:
CAMPBELL BRANCH
END DESCRIPTION:
DSS Export Rating Curves= 0
DSS Export Rating Curve Sorted= 0
DSS Export Volume Flow Curves= 0
DXF OffsetX= 0
DXF OffsetY= 0
DXF ScaleX= 1
DXF ScaleY= 10

--- CAMPBELL BRANCH.p01 (plan) ---

Plan Title=Multiple Run
Short Identifier=Multiple
Geom File=g01
Flow File=f01
Subcritical Flow
K Sum by GR= 0
Std Step Tol= 0.01
Critical Tol= 0.01
Num of Std Step Trials= 20
Max Error Tol= 0.3
Flow Tol Ratio= 0.001
Split Flow NTrial= 30
Split Flow Tol= 0.02
Split Flow Ratio= 0.02
Log Output Level= 0
Friction Slope Method= 1
Unsteady Friction Slope Method= 2
Unsteady Bridges Friction Slope Method= 1
Parabolic Critical Depth
Global Vel Dist=  1 , 1 , 1
Global Log Level= 0
CheckData=True
Encroach Param= -1, 0, 0, 0
BEGIN DESCRIPTION:
Multiple Run
END DESCRIPTION:

--- CAMPBELL BRANCH.f01 (steady flow) ---

Flow Title=Multiple
Number of Profiles=7
Profile Names=10-year,25-year,50-year,1pct_min,100-year,1pct_plu,500-year
River Rch & RM= CAMPBELL BRANCH,Reach-1,19143
     453     716     948     609    1216    2426    1975
River Rch & RM= CAMPBELL BRANCH,Reach-1,15836
    1231    2058    2830    1880    3750    7483    6525
River Rch & RM= CAMPBELL BRANCH,Reach-1,13145
    1361    2283    3145    2092    4173    8327    7281
River Rch & RM= CAMPBELL BRANCH,Reach-1,10811
    1611    2720    3764    2513    5015   10006    8832
River Rch & RM= CAMPBELL BRANCH,Reach-1,6793
    1796    3039    4212    2815    5617   11206    9910
River Rch & RM= CAMPBELL BRANCH,Reach-1,1430
    1870    3170    4399    2943    5873   11718   10385
Boundary for River Rch & Prof#=CAMPBELL BRANCH,Reach-1,1
Up Type=0
Dn Type=3
Dn Slope=0.005
Boundary for River Rch & Prof#=CAMPBELL BRANCH,Reach-1,2
Up Type=0
Dn Type=3
Dn Slope=0.005
Boundary for River Rch & Prof#=CAMPBELL BRANCH,Reach-1,3
Up Type=0
Dn Type=3
Dn Slope=0.005
Boundary for River Rch & Prof#=CAMPBELL BRANCH,Reach-1,4
Up Type=0
Dn Type=3
Dn Slope=0.005
Boundary for River Rch & Prof#=CAMPBELL BRANCH,Reach-1,5
Up Type=0
Dn Type=3
Dn Slope=0.005
Boundary for River Rch & Prof#=CAMPBELL BRANCH,Reach-1,6
Up Type=0
Dn Type=3
Dn Slope=0.005
Boundary for River Rch & Prof#=CAMPBELL BRANCH,Reach-1,7
Up Type=0
Dn Type=3
Dn Slope=0.005

--- CAMPBELL BRANCH.g01 (geometry) ---

Geom Title=Existing Conditions
Program Version=4.10

River Reach=CAMPBELL BRANCH ,Reach-1
Reach XY= 30
        2283275.       13737575.       2283425.4       13737050.
      2283323.31     13736330.46      2282882.83     13735871.77
      2283315.89     13735181.73      2283236.07     13735014.92
      2283831.48     13734767.31      2284158.87     13734392.08
      2284130.81     13734122.71      2284765.18     13733185.46
      2285185.28     13733424.01      2286223.54     13733478.54
      2287022.55     13734119.54      2287364.45     13734026.08
      2287771.77     13734267.15        2289024.     13733971.46
       2289208.2     13733591.42      2289477.45     13733569.54
      2289964.52      13733134.8      2290394.63     13732254.84
      2290872.55     13731830.46      2291519.42     13731619.42
      2291780.26     13731080.47      2292280.71     13730826.89
       2292773.5     13730821.39      2293345.55     13730455.56
      2293482.68     13730018.48      2293723.13     13729919.31
      2293680.45     13729422.53        2294025.       13729125.

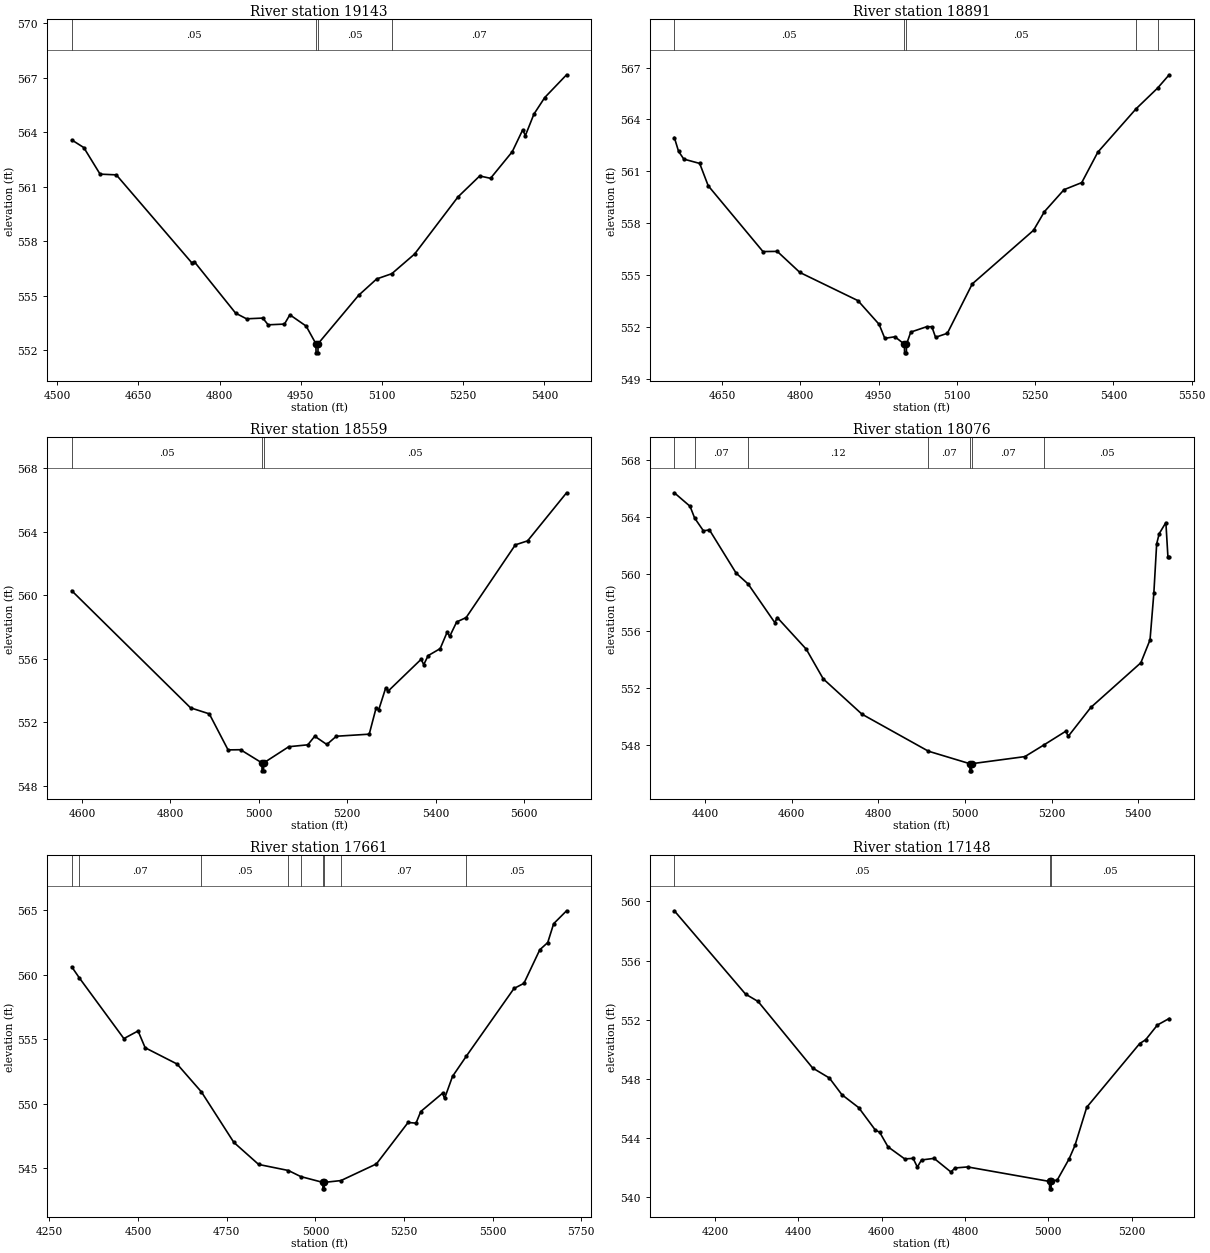
Type RM Length L Ch R = 1 ,19143   ,252,252,252
BEGIN DESCRIPTION:
X18401
END DESCRIPTION:
XS GIS Cut Line= 2
      2283747.27     13737525.24      2282834.83     13737585.02
#Sta/Elev= 30
  4526.7  563.57    4549  563.15  4579.1  561.69  4609.1  561.65  4748.5  556.82
  4753.5  556.87  4829.6  554.05  4849.7  553.74  4879.7  553.78  4889.7  553.41
  4919.8  553.45  4929.8  553.96  4959.9  553.34  4977.9  552.37  4978.2  551.87
  4981.7  551.87  4981.9  552.37  5056.8  555.03  5090.2  555.93  5118.2  556.22
  5160.3   557.3  5240.5  560.44  5280.6  561.59  5300.6  561.46  5340.7  562.92
    5360  564.12    5365  563.81  5380.8  564.99  5400.8   565.9  5441.1  567.15
#Mann= 4 ,-1 , 0
  4526.7     .05       0  4977.9     .05       0  4981.9     .05       0
  5118.2     .07       0
Bank Sta=4977.9,4981.9
XS Rating Curve= 0 ,0
Exp/Cntr=0.3,0.1

Type RM Length L Ch R = 1 ,18891   ,332,332,332
BEGIN DESCRIPTION:
CAMPBELL BRANCH 40.0
END DESCRIPTION:
XS GIS Cut Line= 3
      2283763.01     13737389.93      2283265.92     13737314.42
      2282831.73      13737415.1
#Sta/Elev= 30
  4558.4  562.95  4566.5  562.15  4576.6   561.7    4607  561.45  4623.3  560.16
  4728.3  556.35  4755.7  556.36  4799.1  555.14  4910.4  553.51  4950.9  552.14
  4961.8  551.33  4981.2  551.42  4999.4  550.99  4999.7  550.49  5003.2  550.49
  5003.4  550.99  5011.6  551.69  5041.9     552    5052     552  5059.1  551.39
  5081.7  551.62  5129.5  554.48  5246.9  557.58  5267.8  558.66  5305.3  559.93
  5339.3  560.34  5370.1   562.1  5443.4  564.61  5484.7  565.81  5506.9  566.58
#Mann= 5 ,-1 , 0
  4558.4     .05       0  4999.4     .05       0  5003.4     .05       0
  5443.4     .07       0  5484.7     .05       0
Bank Sta=4999.4,5003.4
XS Rating Curve= 0 ,0
Exp/Cntr=0.3,0.1

Type RM Length L Ch R = 1 ,18559   ,483,483,483
BEGIN DESCRIPTION:
CAMPBELL BRANCH 39.0
END DESCRIPTION:
XS GIS Cut Line= 3
      2283724.98     13737324.98        2283425.       13737025.
      2282824.96     13737375.02
#Sta/Elev= 30
  4576.9  560.28  4845.6   552.9    4888  552.52  4930.4  550.25  4958.7  550.26
    5007  549.43  5007.2  548.93  5010.7  548.93    5011  549.43  5067.7  550.45
  5110.7  550.57  5126.4  551.11  5153.7  550.59  5175.2  551.11  5249.6  551.24
  5265.3  552.91  5271.1  552.78  5286.8  554.15  5292.6  553.96    5367  555.96
  5372.8  555.62  5382.8  556.19    5410  556.63  5425.8  557.67  5431.5   557.4
  5447.3  558.31  5468.8  558.59    5580  563.17  5607.7  563.42  5695.8  566.45
#Mann= 3 ,-1 , 0
  4576.9     .05       0    5007     .05       0    5011     .05       0
Bank Sta=5007,5011
XS Rating Curve= 0 ,0
Exp/Cntr=0.3,0.1

Type RM Length L Ch R = 1 ,18076   ,415,415,415
BEGIN DESCRIPTION:
CAMPBELL BRANCH 38.0
END DESCRIPTION:
XS GIS Cut Line= 3
        2283925.       13736875.        2283325.       13736575.
      2282925.02     13736824.99
#Sta/Elev= 30
  4328.8  565.73  4365.1  564.78  4375.6  563.96  4395.9  563.06  4409.9  563.12
  4471.4  560.09  4499.3  559.32  4560.8  556.61  4566.4  556.97  4633.5  554.74
  4672.6  552.66    4762  550.18  4915.4  547.58  5011.2   546.7  5011.4   546.2
  5014.9   546.2  5015.2   546.7  5138.2   547.2  5183.2  548.04  5232.5  548.98
  5238.4  548.63  5290.3  550.65  5405.9  553.79  5427.1   555.4  5435.9  558.67
  5442.4  562.14  5448.3  562.86  5463.7  563.64  5468.4  561.23  5471.3  561.23
#Mann= 7 ,-1 , 0
  4328.8     .05       0  4375.6     .07       0  4499.3     .12       0
  4915.4     .07       0  5011.2     .05       0  5015.2     .07       0
  5183.2     .05       0
Bank Sta=5011.2,5015.2
XS Rating Curve= 0 ,0
Exp/Cntr=0.3,0.1

Type RM Length L Ch R = 1 ,17661   ,513,513,513
BEGIN DESCRIPTION:
CAMPBELL BRANCH 37.0
END DESCRIPTION:
XS GIS Cut Line= 3
      2283892.11     13736250.93      2283243.89     13736241.49
      2282575.01       13736575.
#Sta/Elev= 30
  4312.7  560.62  4334.2  559.76  4459.8  555.06  4499.8  555.65  4519.8  554.35
  4609.8  553.09  4678.5  550.93  4769.9  547.02  4839.9  545.31  4923.9  544.84
  4958.7  544.37    5021  543.92  5021.3  543.42  5024.8  543.42    5025  543.92
    5072  544.06  5172.1  545.35  5261.4  548.56  5283.8  548.51  5297.2  549.41
  5358.7  550.83  5364.3  550.42  5386.7  552.13  5425.5  553.69  5560.1  558.94
  5588.1  559.34  5632.9  561.94  5655.3   562.5    5672  563.96  5708.4  564.96
#Mann= 9 ,-1 , 0
  4312.7     .05       0  4334.2     .07       0  4678.5     .05       0
  4923.9     .07       0  4958.7     .05       0    5021     .05       0
    5025     .05       0    5072     .07       0  5425.5     .05       0
Bank Sta=5021,5025
XS Rating Curve= 0 ,0
Exp/Cntr=0.3,0.1

Type RM Length L Ch R = 1 ,17148   ,323,323,323
BEGIN DESCRIPTION:
CAMPBELL BRANCH 36.0
END DESCRIPTION:
XS GIS Cut Line= 3
        2283775.       13735975.        2282875.       13735875.
      2282674.99     13736075.01
#Sta/Elev= 30
  4101.9  559.36  4272.9  553.73  4303.1  553.23  4433.9  548.74  4474.2  548.06
  4504.4  546.93  4544.6  546.06  4584.9  544.53  4594.9   544.4    4615  543.41
  4655.3  542.59  4675.4  542.63  4685.5  542.04  4695.5  542.52  4725.7  542.63
    4766  541.71    4776  541.98  4806.2  542.05  5002.9  541.07  5003.2  540.57
  5006.7  540.57  5006.9  541.07  5021.6  541.17  5049.9  542.59    5064   543.5
  5092.3  546.08  5219.6  550.39  5233.7  550.64    5262  551.64  5290.3  552.08
#Mann= 3 ,-1 , 0
  4101.9     .05       0  5002.9     .05       0  5006.9     .05       0
Bank Sta=5002.9,5006.9
XS Rating Curve= 0 ,0
Exp/Cntr=0.3,0.1

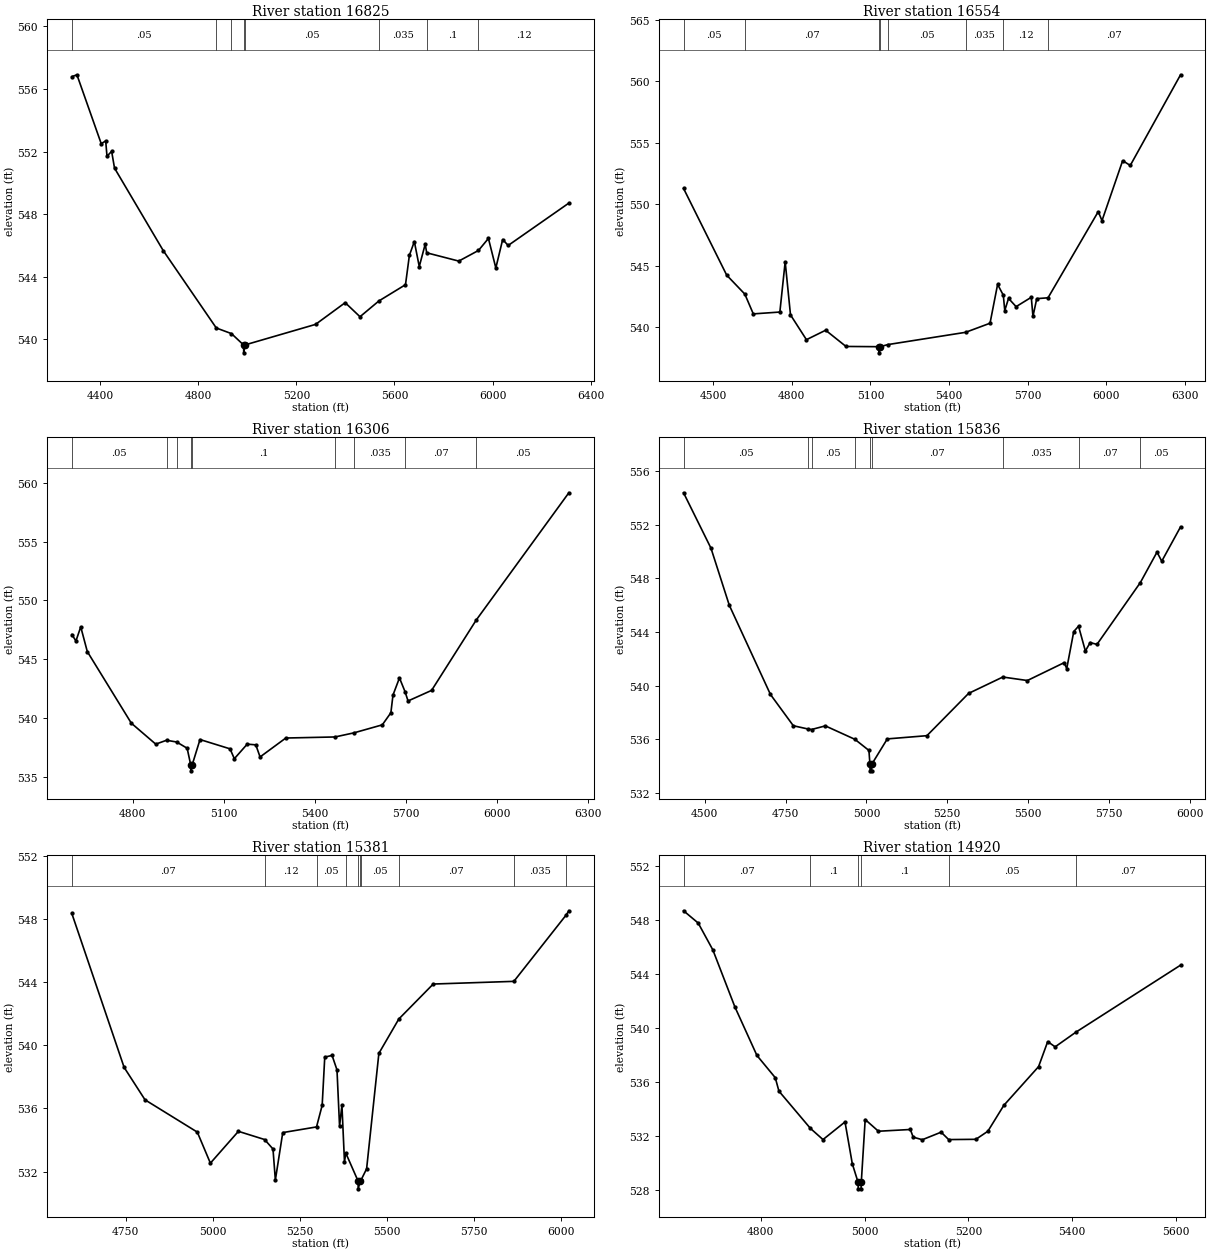
Type RM Length L Ch R = 1 ,16825   ,271,271,271
BEGIN DESCRIPTION:
X18402
END DESCRIPTION:
XS GIS Cut Line= 4
      2283747.91     13735857.65      2283109.89     13735627.62
       2282905.9     13735610.26      2281769.33     13735753.41
#Sta/Elev= 30
  4283.1  556.79  4303.9  556.91  4403.1   552.5  4421.3  552.68  4426.6   551.7
  4445.6  552.01  4457.3  550.94  4656.2  545.66  4872.7  540.71  4934.6  540.35
  4984.3  539.62  4984.6  539.12  4988.3  539.62  5277.8  540.94  5398.8  542.33
  5459.2  541.43  5536.4  542.44  5644.9  543.48  5660.8  545.36    5681  546.24
  5701.1  544.64  5725.3  546.07  5731.5  545.52  5862.4  544.99  5942.7  545.67
  5983.4  546.44  6013.6  544.55  6041.5  546.37    6064  545.99  6311.6   548.7
#Mann= 8 ,-1 , 0
  4283.1     .05       0  4872.7     .07       0  4934.6     .05       0
  4984.3     .05       0  4988.3     .05       0  5536.4    .035       0
  5731.5      .1       0  5942.7     .12       0
Bank Sta=4984.3,4988.3
XS Rating Curve= 0 ,0
Exp/Cntr=0.3,0.1

Type RM Length L Ch R = 1 ,16554   ,248,248,248
BEGIN DESCRIPTION:
CAMPBELL BRANCH 35.0
END DESCRIPTION:
XS GIS Cut Line= 3
      2283717.53     13735571.19      2283244.44     13735493.07
      2282124.98     13734624.99
#Sta/Elev= 30
  4387.2  551.29  4551.9  544.23    4621  542.69  4653.3  541.08  4754.6  541.23
  4774.9  545.32  4795.2     541    4856  538.98  4929.3  539.75  5006.9  538.43
  5133.1  538.41  5133.4  537.91  5137.8  538.41  5166.1  538.58  5463.2  539.58
  5556.4  540.32  5585.3  543.48  5607.1   542.6  5612.6  541.35    5627  542.34
  5655.9  541.67  5713.8  542.43  5720.2  540.88  5734.7  542.32  5777.7  542.39
  5969.2   549.4  5983.6  548.67  6062.4  553.55  6091.4  553.16  6283.3  560.54
#Mann= 8 ,-1 , 0
  4387.2     .05       0    4621     .07       0  5133.1     .05       0
  5137.8     .07       0  5166.1     .05       0  5463.2    .035       0
  5607.1     .12       0  5777.7     .07       0
Bank Sta=5133.1,5137.8
XS Rating Curve= 0 ,0
Exp/Cntr=0.3,0.1

Type RM Length L Ch R = 1 ,16306   ,470,470,470
BEGIN DESCRIPTION:
CAMPBELL BRANCH 34.0
END DESCRIPTION:
XS GIS Cut Line= 3
      2283624.97     13735424.99       2283305.2     13735241.33
      2282424.97     13734324.97
#Sta/Elev= 30
  4598.8   547.1  4612.4  546.55  4628.2  547.75  4649.8  545.65  4795.1  539.56
  4875.6  537.78  4911.3  538.11  4944.7  537.96  4979.2  537.43    4991  536.01
  4991.3  535.51  4995.7  536.01  5021.6  538.17  5120.7  537.38  5134.8  536.54
  5177.3  537.78  5205.6  537.72  5219.7  536.69  5304.6   538.3  5466.8  538.39
  5529.4  538.74  5622.9  539.42  5651.2  540.45  5658.1  541.95  5679.5  543.41
  5697.9  542.24  5707.8  541.45  5785.5  542.35  5932.7  548.33  6238.2  559.15
#Mann= 9 ,-1 , 0
  4598.8     .05       0  4911.3     .07       0  4944.7      .1       0
    4991     .05       0  4995.7      .1       0  5466.8     .07       0
  5529.4    .035       0  5697.9     .07       0  5932.7     .05       0
Bank Sta=4991,4995.7
XS Rating Curve= 0 ,0
Exp/Cntr=0.3,0.1

Type RM Length L Ch R = 1 ,15836   ,455,455,455
BEGIN DESCRIPTION:
CAMPBELL BRANCH 33.0
END DESCRIPTION:
XS GIS Cut Line= 3
      2283824.98     13735324.98        2283425.       13734925.
      2282624.98     13734374.99
#Sta/Elev= 30
  4434.8  554.38  4519.6  550.25  4576.2     546  4703.5  539.35  4774.2  537.02
    4821  536.77  4830.4  536.74  4873.2  537.01  4964.4  536.01  5007.9  535.18
    5011  534.16  5011.5  533.66  5016.4  533.66  5016.9  534.16  5064.7  536.04
  5187.2  536.28    5316  539.43  5421.8  540.65  5497.7  540.39  5611.4  541.72
  5619.4  541.28  5641.1  544.04  5655.9  544.44    5677  542.59  5691.9  543.22
  5712.8  543.08    5847  547.69  5898.5  549.96  5913.1  549.28  5971.3  551.84
#Mann= 9 ,-1 , 0
  4434.8     .05       0    4821     .07       0  4830.4     .05       0
  4964.4     .07       0    5011     .05       0  5016.9     .07       0
  5421.8    .035       0  5655.9     .07       0    5847     .05       0
Bank Sta=5011,5016.9
XS Rating Curve= 0 ,0
Exp/Cntr=0.3,0.1

Type RM Length L Ch R = 1 ,15381   ,461,461,461
BEGIN DESCRIPTION:
CAMPBELL BRANCH 32.0
END DESCRIPTION:
XS GIS Cut Line= 3
      2284224.97       13734775.        2283825.       13734775.
      2283124.99     13734024.99
#Sta/Elev= 30
    4596  548.38    4746  538.61    4806  536.55    4956   534.5  4993.5  532.53
  5073.9  534.55    5149  534.03  5173.1  533.43  5179.9  531.46  5201.1  534.47
    5298  534.83  5314.2   536.2  5321.6  539.26  5342.6  539.37  5356.7  538.45
  5364.1  534.88  5370.9   536.2  5378.2  532.62    5382  533.17  5417.1   531.4
  5417.6   530.9  5423.4   531.4    5426  531.47  5441.7  532.17  5476.9   539.5
  5534.1  541.68  5632.8   543.9  5864.2  544.07  6014.8   548.3  6021.9  548.55
#Mann= 10 ,-1 , 0
    4596     .07       0    5149     .12       0    5298     .05       0
    5382     .12       0  5417.1     .05       0  5423.4     .12       0
    5426     .05       0  5534.1     .07       0  5864.2    .035       0
  6014.8     .05       0
Bank Sta=5417.1,5423.4
XS Rating Curve= 0 ,0
Exp/Cntr=0.3,0.1

Type RM Length L Ch R = 1 ,14920   ,398,398,398
BEGIN DESCRIPTION:
CAMPBELL BRANCH 31.0
END DESCRIPTION:
XS GIS Cut Line= 3
      2284324.97     13734674.97        2284075.       13734425.
      2283524.96     13734174.98
#Sta/Elev= 30
  4651.2  548.71  4679.4   547.8  4707.7   545.8  4750.2  541.56  4792.6  537.96
  4827.9  536.31    4835  535.31  4895.7  532.54  4919.9  531.71  4962.3  533.02
  4976.4  529.91  4987.4  528.55  4987.9  528.05  4993.2  528.05  4993.7  528.55
  5001.2   533.2  5026.7  532.33  5088.2  532.46  5093.7  531.89  5111.3   531.7
  5147.5  532.26  5162.1  531.71  5214.5  531.73  5237.6  532.33  5268.3  534.25
  5335.3  537.13  5352.9  538.99  5367.2   538.6  5407.2  539.69  5608.9  544.67
#Mann= 6 ,-1 , 0
  4651.2     .07       0  4895.7      .1       0  4987.4     .05       0
  4993.7      .1       0  5162.1     .05       0  5407.2     .07       0
Bank Sta=4987.4,4993.7
XS Rating Curve= 0 ,0
Exp/Cntr=0.3,0.1

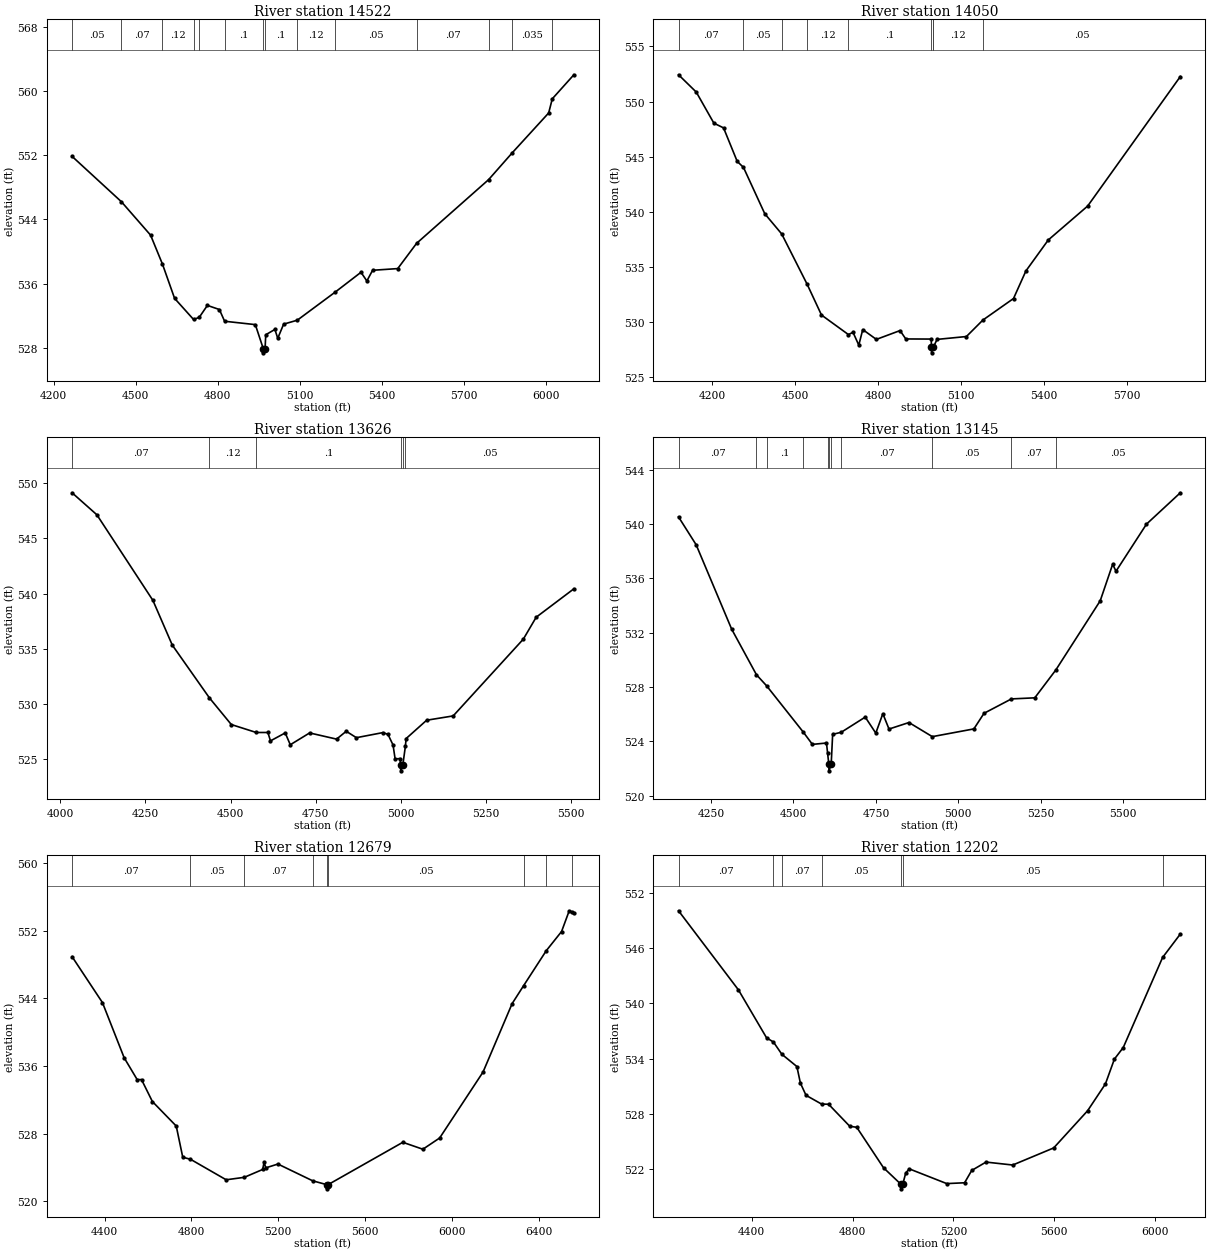
Type RM Length L Ch R = 1 ,14522   ,472,472,472
BEGIN DESCRIPTION:
CAMPBELL BRANCH 30.0
END DESCRIPTION:
XS GIS Cut Line= 3
      2284474.98     13734774.96        2284125.       13734125.
      2283374.99     13733324.99
#Sta/Elev= 30
  4267.6  551.85  4447.9  546.21  4554.7  542.05  4598.2  538.44  4642.4  534.19
  4711.8  531.56  4732.5  531.82  4762.4  533.31  4806.2   532.8  4825.4  531.34
  4937.7  530.92  4966.9  527.91  4967.4  527.41  4973.3  527.91  4975.8  529.66
  5009.2  530.32  5019.7  529.22  5041.2  530.98  5091.1  531.47  5230.7  534.99
    5324  537.43  5345.5  536.35  5366.5  537.68  5458.4  537.89  5527.3  541.03
  5790.8  548.96  5877.8  552.32  6010.3  557.25  6023.5  559.01  6102.4     562
#Mann= 14 ,-1 , 0
  4267.6     .05       0  4447.9     .07       0  4598.2     .12       0
  4711.8      .1       0  4732.5     .12       0  4825.4      .1       0
  4966.9     .05       0  4973.3      .1       0  5091.1     .12       0
  5230.7     .05       0  5527.3     .07       0  5790.8     .05       0
  5877.8    .035       0  6023.5     .05       0
Bank Sta=4966.9,4973.3
XS Rating Curve= 0 ,0
Exp/Cntr=0.3,0.1

Type RM Length L Ch R = 1 ,14050   ,424,424,424
BEGIN DESCRIPTION:
CAMPBELL BRANCH 29.0
END DESCRIPTION:
XS GIS Cut Line= 3
      2285124.99     13734374.99        2284425.       13733775.
      2283624.97     13733374.99
#Sta/Elev= 30
  4078.4  552.43  4142.6  550.86  4206.3  548.04  4241.4  547.61  4290.8  544.57
  4313.4  544.03  4390.6  539.82  4451.8  537.99    4544  533.42  4595.9  530.63
  4693.2  528.86    4710  529.06  4730.9   527.9  4745.2  529.31  4794.5  528.42
  4880.2  529.22    4901  528.46  4993.2  528.45  4993.8   527.7  4994.3   527.2
  5000.3   527.7  5000.4   527.7  5014.3  528.42  5120.5  528.68  5179.9  530.17
    5291  532.13  5335.8  534.63  5416.8  537.44  5559.4  540.52  5894.8  552.27
#Mann= 9 ,-1 , 0
  4078.4     .07       0  4313.4     .05       0  4451.8     .07       0
    4544     .12       0  4693.2      .1       0  4993.8     .05       0
  5000.3      .1       0  5000.4     .12       0  5179.9     .05       0
Bank Sta=4993.8,5000.3
XS Rating Curve= 0 ,0
Exp/Cntr=0.3,0.1

Type RM Length L Ch R = 1 ,13626   ,481,481,481
BEGIN DESCRIPTION:
CAMPBELL BRANCH 28.0
END DESCRIPTION:
XS GIS Cut Line= 3
      2285124.98     13734224.97        2284575.       13733425.
      2284074.98       13733375.
#Sta/Elev= 30
  4034.6  549.12  4107.4  547.13    4272  539.38  4328.8  535.34  4437.9  530.56
  4502.1  528.15  4575.4  527.43  4609.6  527.43  4617.1  526.67  4660.4  527.39
  4675.3  526.32  4732.1  527.39  4811.2  526.83  4839.6  527.54  4869.4  526.96
  4947.2  527.42  4962.1  527.26    4977   526.3  4983.1  525.04  4997.9  525.07
  4999.1  524.46  4999.6  523.96  5005.6  524.46  5013.2  526.17  5015.4  526.88
  5075.7  528.54  5153.6  528.93  5359.6  535.88  5397.3  537.86  5507.9  540.43
#Mann= 6 ,-1 , 0
  4034.6     .07       0  4437.9     .12       0  4575.4      .1       0
  4999.1     .05       0  5005.6      .1       0  5013.2     .05       0
Bank Sta=4999.1,5005.6
XS Rating Curve= 0 ,0
Exp/Cntr=0.3,0.1

Type RM Length L Ch R = 1 ,13145   ,466,466,466
BEGIN DESCRIPTION:
CAMPBELL BRANCH 27.0
END DESCRIPTION:
XS GIS Cut Line= 3
      2285225.02     13733975.05        2284925.       13733175.
      2284775.01     13732525.03
#Sta/Elev= 30
  4151.5  540.53  4204.9  538.48  4312.6  532.26  4387.8   528.9  4418.4  528.09
  4529.9  524.67  4557.4  523.77  4600.1  523.87  4603.4  523.14  4607.1  522.32
  4607.6  521.82  4614.4  522.32  4618.8  524.51  4644.7  524.66  4717.6  525.78
  4749.6   524.6    4771  526.03  4789.7   524.9  4850.2  525.38    4921  524.34
    5047  524.91  5077.8  526.06  5160.9  527.12  5231.7   527.2  5295.4  529.25
  5430.1  534.35  5467.8  537.04    5478  536.53  5570.4     540    5673  542.31
#Mann= 11 ,-1 , 0
  4151.5     .07       0  4387.8     .12       0  4418.4      .1       0
  4529.9     .12       0  4603.4      .1       0  4607.1     .05       0
  4614.4      .1       0  4644.7     .07       0    4921     .05       0
  5160.9     .07       0  5295.4     .05       0
Bank Sta=4607.1,4614.4
XS Rating Curve= 0 ,0
Exp/Cntr=0.3,0.1

Type RM Length L Ch R = 1 ,12679   ,477,477,477
BEGIN DESCRIPTION:
CAMPBELL BRANCH 26.0
END DESCRIPTION:
XS GIS Cut Line= 3
        2285275.     13734174.99        2285275.       13733425.
      2286474.97     13732425.03
#Sta/Elev= 30
  4250.1  548.92  4390.1  543.49  4490.1  536.97  4550.1  534.39  4570.1  534.39
  4620.1   531.8  4730.1   528.9  4760.1  525.21  4795.3  524.98  4960.1  522.55
  5043.6  522.84  5128.3  523.77  5134.8  524.62  5142.6  523.96  5198.6  524.41
  5358.6  522.43  5422.7  521.98  5423.2  521.48  5430.1  521.98    5774  526.98
  5866.4  526.16  5943.8  527.49  6143.6  535.28  6277.7  543.37  6330.3  545.48
  6434.9  549.62  6505.5  551.89  6540.7  554.34  6554.4  554.21  6562.1  554.04
#Mann= 9 ,-1 , 0
  4250.1     .07       0  4795.3     .05       0  5043.6     .07       0
  5358.6     .05       0  5422.7     .05       0  5430.1     .05       0
  6330.3     .07       0  6434.9     .05       0  6554.4     .07       0
Bank Sta=5422.7,5430.1
XS Rating Curve= 0 ,0
Exp/Cntr=0.3,0.1

Type RM Length L Ch R = 1 ,12202   ,468,468,468
BEGIN DESCRIPTION:
CAMPBELL BRANCH 25.0
END DESCRIPTION:
XS GIS Cut Line= 3
        2285325.       13734225.        2285725.       13733425.
      2286474.99     13732625.01
#Sta/Elev= 30
  4109.4  550.07    4347  541.47  4458.8  536.25  4485.9   535.8  4519.2  534.47
    4579  533.13  4592.9  531.33  4615.3     530  4676.9  529.05  4704.8  529.03
  4788.6  526.64  4816.6  526.52  4922.8  522.12  4991.7  520.33  4992.2  519.83
  4999.1  520.33  5010.9  521.56  5025.1     522  5173.6   520.4  5244.4  520.49
  5272.7  521.83  5329.4  522.74  5435.4  522.42    5598  524.28  5732.4  528.32
  5803.2  531.24  5838.8  533.94    5874   535.2    6030  544.99  6100.4  547.54
#Mann= 7 ,-1 , 0
  4109.4     .07       0  4485.9     .05       0  4519.2     .07       0
  4676.9     .05       0  4991.7     .05       0  4999.1     .05       0
    6030     .07       0
Bank Sta=4991.7,4999.1
XS Rating Curve= 0 ,0
Exp/Cntr=0.3,0.1

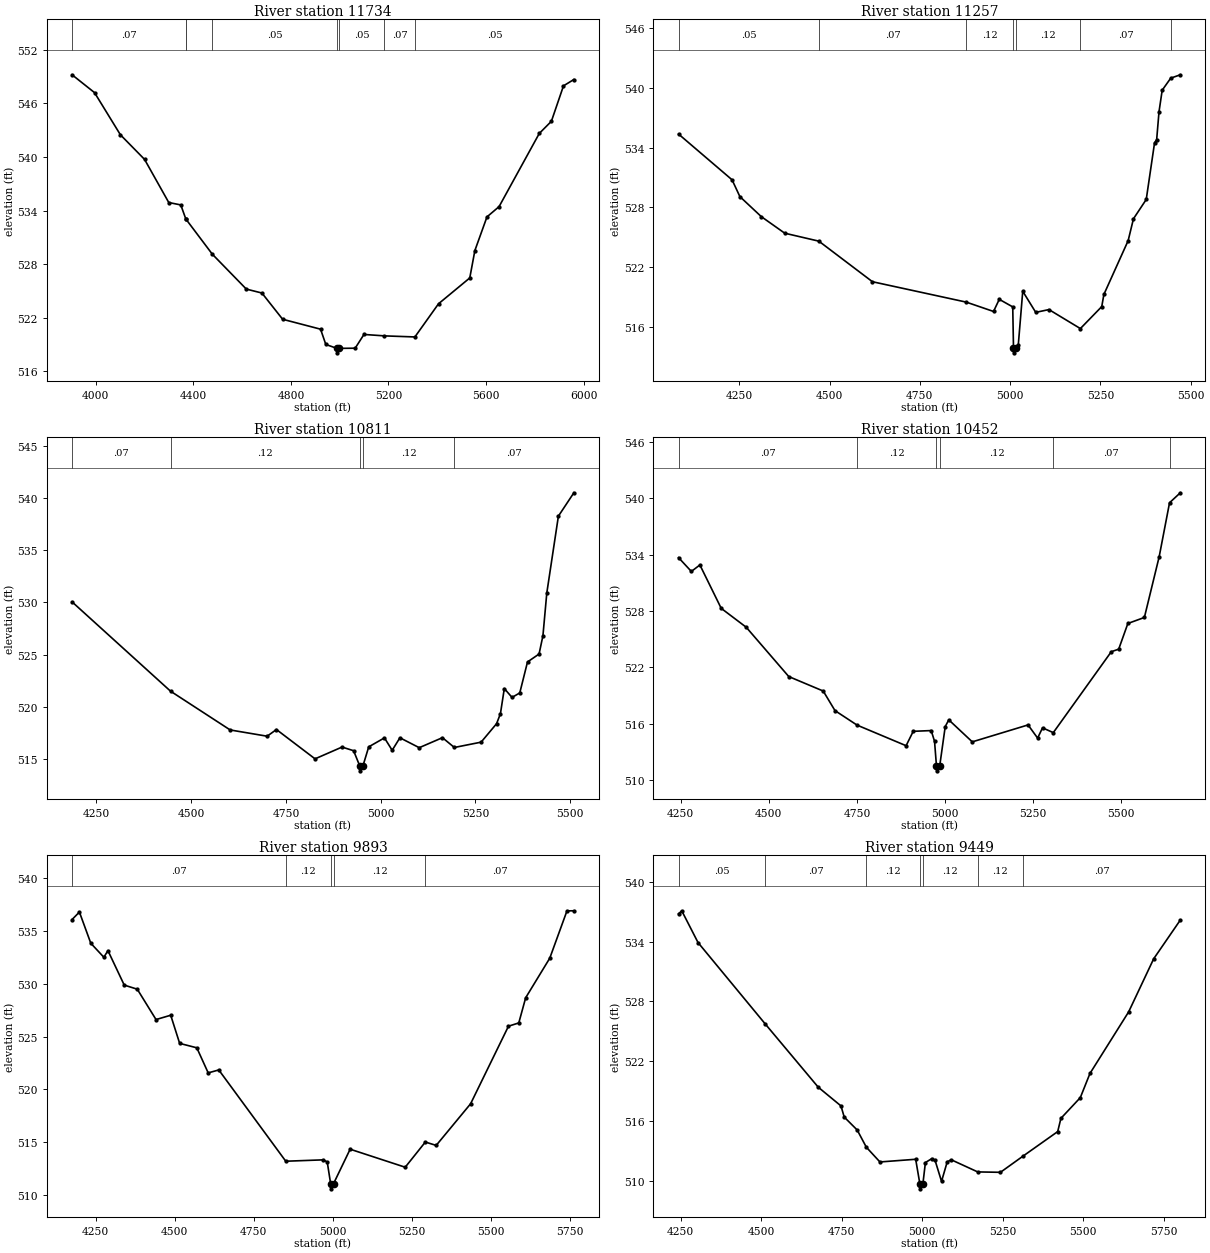
Type RM Length L Ch R = 1 ,11734   ,477,477,477
BEGIN DESCRIPTION:
CAMPBELL BRANCH 24.0
END DESCRIPTION:
XS GIS Cut Line= 3
        2285425.       13734275.        2286175.       13733475.
      2286775.03     13732724.97
#Sta/Elev= 30
  3902.9  549.21    3995  547.21    4101  542.49  4200.1  539.73  4299.3   534.9
  4348.6  534.63  4368.6   533.1  4370.2  533.02  4477.9  529.11  4617.3   525.2
  4681.2  524.76  4766.2  521.82  4921.6  520.71  4943.1     519  4988.7  518.56
  4989.2  518.06  4996.1  518.56  5063.5  518.58  5099.5  520.12  5183.7  519.96
  5308.3  519.84  5405.3  523.56  5533.3  526.45  5554.2  529.52  5603.8  533.29
  5653.4  534.44  5818.3  542.64  5867.9     544  5917.5  547.97    5960  548.68
#Mann= 8 ,-1 , 0
  3902.9     .07       0  4368.6     .05       0  4370.2     .07       0
  4477.9     .05       0  4988.7     .05       0  4996.1     .05       0
  5183.7     .07       0  5308.3     .05       0
Bank Sta=4988.7,4996.1
XS Rating Curve= 0 ,0
Exp/Cntr=0.3,0.1

Type RM Length L Ch R = 1 ,11257   ,446,446,446
BEGIN DESCRIPTION:
CAMPBELL BRANCH 23.0
END DESCRIPTION:
XS GIS Cut Line= 3
      2285775.02     13734124.99        2286575.       13733675.
      2286975.04     13733424.98
#Sta/Elev= 30
  4081.7  535.38  4229.9  530.78  4251.6  529.09  4310.8  527.08  4375.8  525.41
  4470.3  524.61  4618.7  520.53  4878.5  518.48    4954  517.54  4969.9  518.76
  5007.2     518  5009.3  513.88  5009.8  513.38    5017  513.88  5022.6  514.19
  5034.9  519.57  5070.9  517.45  5107.5  517.73  5194.5  515.82  5253.7  518.03
  5259.6  519.25  5326.8  524.66  5341.5  526.86  5376.9   528.8  5399.9  534.49
  5405.8  534.83  5412.3  537.63  5421.1  539.79  5444.7     541  5471.3  541.34
#Mann= 7 ,-1 , 0
  4081.7     .05       0  4470.3     .07       0  4878.5     .12       0
  5009.3     .05       0    5017     .12       0  5194.5     .07       0
  5444.7     .05       0
Bank Sta=5009.3,5017
XS Rating Curve= 0 ,0
Exp/Cntr=0.3,0.1

Type RM Length L Ch R = 1 ,10811   ,359,359,359
BEGIN DESCRIPTION:
CAMPBELL BRANCH 22.0
END DESCRIPTION:
XS GIS Cut Line= 3
        2287025.     13734774.98        2286875.       13733975.
      2286974.99     13733475.03
#Sta/Elev= 30
  4185.8  530.05  4445.5  521.49  4602.9  517.77  4700.4  517.17    4725  517.81
  4826.8     515    4898  516.13  4928.5  515.78  4944.4  514.35  4944.9  513.85
  4953.4  514.35  4968.4  516.15  5009.9  517.01  5030.3  515.82  5050.7  517.02
  5101.7  516.07  5162.9  517.03  5194.3  516.09  5264.9   516.6  5305.7  518.37
  5315.9  519.33  5326.1  521.74  5346.5  520.89  5366.9  521.32  5387.3  524.29
  5417.8  525.05    5428   526.8  5438.2   530.9  5468.8  538.27  5509.6  540.51
#Mann= 5 ,-1 , 0
  4185.8     .07       0  4445.5     .12       0  4944.4     .05       0
  4953.4     .12       0  5194.3     .07       0
Bank Sta=4944.4,4953.4
XS Rating Curve= 0 ,0
Exp/Cntr=0.3,0.1

Type RM Length L Ch R = 1 ,10452   ,559,559,559
BEGIN DESCRIPTION:
CAMPBELL BRANCH 21.0
END DESCRIPTION:
XS GIS Cut Line= 3
        2287275.     13734875.02      2287163.71     13734047.76
      2287025.01     13733475.03
#Sta/Elev= 30
  4243.8  533.67  4280.2   532.2  4304.4  532.89  4364.9  528.28  4435.9  526.27
  4556.6  521.03  4654.4  519.49  4687.8  517.41  4750.4  515.87  4889.6  513.68
  4909.8  515.21  4960.8  515.29  4970.3  514.15  4975.8  511.51  4976.3  511.01
  4984.9  511.51  5000.6  515.71  5010.7  516.43  5077.4  514.09  5235.7  515.89
  5262.8  514.49  5276.8  515.58  5307.3  515.07  5471.9  523.67  5492.9  523.94
  5518.9  526.67  5565.8  527.31  5607.7  533.75  5637.2   539.5  5667.8  540.56
#Mann= 6 ,-1 , 0
  4243.8     .07       0  4750.4     .12       0  4975.8     .05       0
  4984.9     .12       0  5307.3     .07       0  5637.2     .05       0
Bank Sta=4975.8,4984.9
XS Rating Curve= 0 ,0
Exp/Cntr=0.3,0.1

Type RM Length L Ch R = 1 ,9893    ,444,444,444
BEGIN DESCRIPTION:
CAMPBELL BRANCH 20.0
END DESCRIPTION:
XS GIS Cut Line= 3
        2287425.     13734974.98        2287625.       13734175.
      2287324.99     13733474.98
#Sta/Elev= 30
  4175.4   536.1  4198.6  536.81  4234.6  533.85  4275.9  532.52  4288.8  533.15
  4340.3  529.88  4381.5  529.49  4440.8  526.61  4487.2  527.02  4515.5  524.35
  4569.7  523.93  4605.7  521.55  4639.2  521.83  4850.9  513.17  4969.1   513.3
    4982   513.1  4992.7  511.05  4993.2  510.55  5002.1  511.05  5054.4  514.31
  5228.5   512.6  5292.1  514.99  5326.4  514.67  5435.2  518.62  5554.9  525.98
  5587.5  526.29  5609.3  528.68  5685.4  532.43  5739.8  536.92  5761.6  536.93
#Mann= 5 ,-1 , 0
  4175.4     .07       0  4850.9     .12       0  4992.7     .05       0
  5002.1     .12       0  5292.1     .07       0
Bank Sta=4992.7,5002.1
XS Rating Curve= 0 ,0
Exp/Cntr=0.3,0.1

Type RM Length L Ch R = 1 ,9449    ,434,434,434
BEGIN DESCRIPTION:
CAMPBELL BRANCH 19.0
END DESCRIPTION:
XS GIS Cut Line= 3
      2288074.99     13734924.96        2287975.       13734175.
        2287925.     13733374.96
#Sta/Elev= 30
  4243.5  536.79  4253.5   537.1    4304  533.91  4512.8  525.73  4677.3  519.38
  4747.9   517.5    4758  516.38  4798.3  515.08  4826.7  513.35  4868.9  511.87
  4979.9  512.14  4992.9  509.67  4993.4  509.17  5002.3  509.67  5010.1  511.81
  5030.2  512.21  5040.2  512.02  5060.2  509.92  5077.8  511.88  5090.3  512.09
  5172.5  510.87  5243.1  510.83  5312.1  512.43  5420.9  514.92  5430.9  516.25
  5491.1  518.33  5521.1  520.76  5641.3  526.95    5719  532.28  5801.7  536.17
#Mann= 7 ,-1 , 0
  4243.5     .05       0  4512.8     .07       0  4826.7     .12       0
  4992.9     .05       0  5002.3     .12       0  5172.5     .12       0
  5312.1     .07       0
Bank Sta=4992.9,5002.3
XS Rating Curve= 0 ,0
Exp/Cntr=0.3,0.1

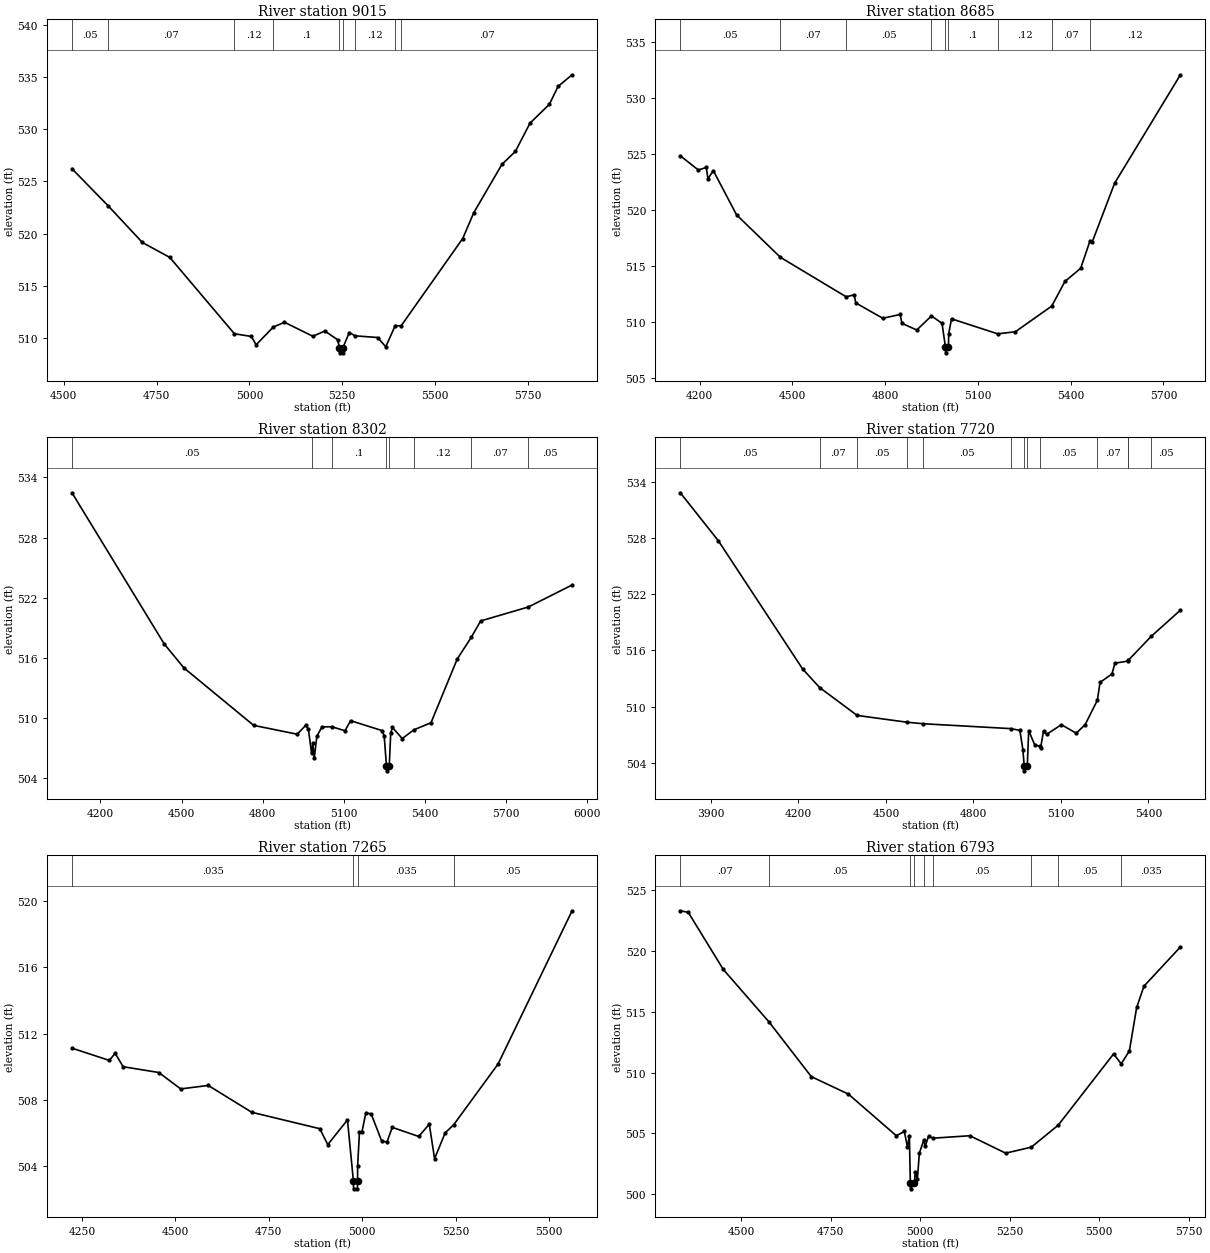
Type RM Length L Ch R = 1 ,9015    ,330,330,330
BEGIN DESCRIPTION:
CAMPBELL BRANCH 18.0
END DESCRIPTION:
XS GIS Cut Line= 3
        2288225.     13734624.99        2288375.       13734175.
      2288025.02     13733375.04
#Sta/Elev= 30
  4521.9  526.22  4619.5  522.66  4711.6  519.15  4785.4  517.72  4959.5   510.4
  5005.2  510.14  5018.1  509.34  5064.2  511.04  5094.5   511.5  5170.9  510.16
  5203.2  510.66  5237.5  509.83  5242.5  509.07    5243  508.57  5251.5  508.57
    5252  509.07  5269.1  510.52  5284.7   510.2  5345.5  510.04  5367.3  509.15
  5392.8  511.18  5408.6  511.15  5574.7  519.53  5604.7  522.02  5680.4  526.64
  5716.6  527.88    5756  530.59  5808.2   532.4  5831.6  534.11  5869.4  535.23
#Mann= 9 ,-1 , 0
  4521.9     .05       0  4619.5     .07       0  4959.5     .12       0
  5064.2      .1       0  5242.5     .05       0    5252      .1       0
  5284.7     .12       0  5392.8      .1       0  5408.6     .07       0
Bank Sta=5242.5,5252
XS Rating Curve= 0 ,0
Exp/Cntr=0.3,0.1

Type RM Length L Ch R = 1 ,8685    ,383,383,383
BEGIN DESCRIPTION:
CAMPBELL BRANCH 17.0
END DESCRIPTION:
XS GIS Cut Line= 3
      2288400.68     13734785.63      2288665.45     13734039.07
      2288262.17     13733319.25
#Sta/Elev= 30
  4137.5  524.86  4195.9  523.59  4221.5  523.82  4226.8  522.81  4244.3  523.53
  4319.4  519.58  4461.1  515.79  4673.7  512.26  4699.6  512.43  4704.9  511.71
  4792.2  510.34  4848.6  510.68  4853.9  509.89  4902.1  509.29  4949.7  510.55
  4983.8  509.89    4995  507.75  4995.5  507.25  5004.5  507.75  5005.5  508.97
  5014.5  510.29  5163.6  508.95  5220.8  509.13  5338.6  511.43  5381.3  513.63
  5432.3  514.81  5462.6  517.28    5470  517.19  5541.8   522.4  5754.7   532.1
#Mann= 9 ,-1 , 0
  4137.5     .05       0  4461.1     .07       0  4673.7     .05       0
  4949.7      .1       0    4995     .05       0  5004.5      .1       0
  5163.6     .12       0  5338.6     .07       0  5462.6     .12       0
Bank Sta=4995,5004.5
XS Rating Curve= 0 ,0
Exp/Cntr=0.3,0.1

Type RM Length L Ch R = 1 ,8302    ,582,582,582
BEGIN DESCRIPTION:
X18403
END DESCRIPTION:
XS GIS Cut Line= 3
      2289234.01     13734846.34      2288947.56     13733839.42
      2288674.11     13733084.17
#Sta/Elev= 30
  4094.6  532.46    4436  517.39    4509     515  4766.8  509.28  4927.7   508.4
  4958.9  509.27  4969.3  508.91  4980.8   506.5  4985.6   507.5  4990.8  505.99
  5000.5   508.2  5019.5  509.13  5056.8  509.14  5104.5  508.74  5125.3  509.75
  5241.9  508.76  5249.5  508.24    5258  505.25  5258.5  504.75  5268.3  505.25
  5273.8  508.52  5280.1  509.07  5316.3  507.97  5359.7  508.84  5422.7  509.54
  5519.9   515.9  5571.4  518.04  5606.6  519.69  5783.1  521.08  5944.7  523.27
#Mann= 8 ,-1 , 0
  4094.6     .05       0  4980.8     .12       0  5056.8      .1       0
    5258     .05       0  5268.3      .1       0  5359.7     .12       0
  5571.4     .07       0  5783.1     .05       0
Bank Sta=5258,5268.3
XS Rating Curve= 0 ,0
Exp/Cntr=0.3,0.1

Type RM Length L Ch R = 1 ,7720    ,455,455,455
BEGIN DESCRIPTION:
CAMPBELL BRANCH 16.0
END DESCRIPTION:
XS GIS Cut Line= 3
        2289375.     13734775.01        2289275.       13733575.
      2289174.99     13733074.97
#Sta/Elev= 30
  3795.4  532.83  3925.9   527.7  4214.4  514.02  4272.8  512.03  4401.3  509.05
  4572.9  508.32    4628  508.16    4928  507.64  4959.4  507.45  4969.5  505.39
  4974.3  503.63  4974.8  503.13  4984.7  503.63  4989.5  507.43  5009.8  505.93
  5027.6  505.74  5030.2  505.56  5040.4   507.4  5050.6  507.02  5101.5  508.06
  5152.5  507.15  5183.1  508.07  5224.8  510.67  5234.1  512.58  5274.9  513.48
  5285.1  514.63    5329  514.85  5330.6  514.93  5409.6   517.5  5509.5  520.29
#Mann= 13 ,-1 , 0
  3795.4     .05       0  4272.8     .07       0  4401.3     .05       0
  4572.9     .07       0    4628     .05       0    4928     .07       0
  4974.3     .05       0  4984.7     .07       0  5027.6     .05       0
  5224.8     .07       0    5329     .12       0  5330.6     .07       0
  5409.6     .05       0
Bank Sta=4974.3,4984.7
XS Rating Curve= 0 ,0
Exp/Cntr=0.3,0.1

Type RM Length L Ch R = 1 ,7265    ,472,472,472
BEGIN DESCRIPTION:
CAMPBELL BRANCH 15.0
END DESCRIPTION:
XS GIS Cut Line= 3
      2290069.62     13734088.16        2289675.       13733425.
      2289274.98     13733024.98
#Sta/Elev= 30
  4223.5  511.13  4323.3  510.39  4338.9  510.82  4360.3  510.01  4455.8  509.66
  4514.2  508.67  4587.9  508.88  4704.3  507.26  4886.1  506.27  4907.6  505.31
  4960.2   506.8    4976  503.14  4976.5  502.64  4986.7  502.64  4987.2  503.14
  4987.4  504.03  4992.3  506.05  4998.7  506.05  5009.3  507.21  5023.5  507.17
  5051.8  505.52  5065.9  505.47    5080  506.35  5150.8   505.8    5179  506.54
  5193.2  504.46  5221.5  506.02    5244   506.5  5362.9  510.17  5560.9  519.42
#Mann= 4 ,-1 , 0
  4223.5    .035       0    4976    .035       0  4987.2    .035       0
    5244     .05       0
Bank Sta=4976,4987.2
XS Rating Curve= 0 ,0
Exp/Cntr=0.3,0.1

Type RM Length L Ch R = 1 ,6793    ,446,446,446
BEGIN DESCRIPTION:
CAMPBELL BRANCH 14.0
END DESCRIPTION:
XS GIS Cut Line= 4
      2290574.99     13733374.99        2289975.       13733075.
      2289579.86     13732825.88      2289324.97       13732875.
#Sta/Elev= 30
  4329.6  523.28  4351.9  523.15  4449.8  518.46  4577.3  514.16  4695.7  509.66
  4799.2  508.23  4933.3  504.81  4955.7  505.16  4964.1   503.9  4969.7  504.82
  4972.4  500.95  4972.9  500.45  4983.7  500.95  4986.4  501.87    4992  501.22
  4997.6  503.38  5010.1  504.46    5014  503.94  5023.3  504.77  5035.9  504.61
  5138.7  504.81  5238.8  503.38  5310.4  503.87  5385.7  505.68  5540.4  511.53
  5561.7  510.71  5584.5  511.78  5604.9  515.34  5625.2  517.09  5727.1  520.31
#Mann= 9 ,-1 , 0
  4329.6     .07       0  4577.3     .05       0  4972.4     .05       0
  4983.7     .05       0  5010.1     .07       0  5035.9     .05       0
  5310.4     .07       0  5385.7     .05       0  5561.7    .035       0
Bank Sta=4972.4,4983.7
XS Rating Curve= 0 ,0
Exp/Cntr=0.3,0.1