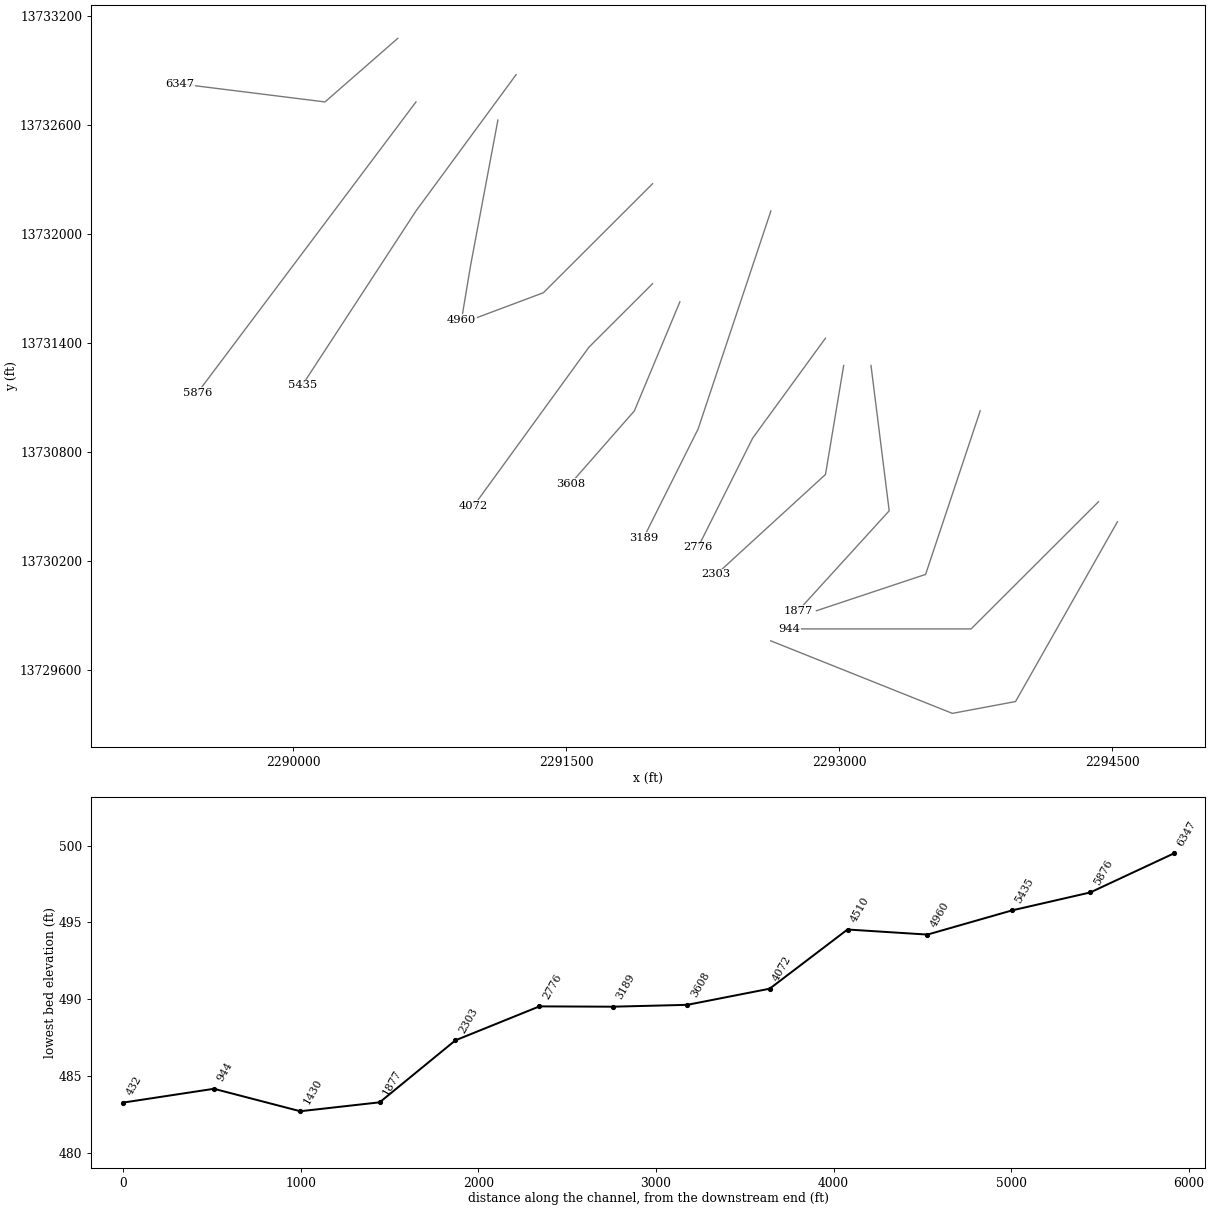
HEC-RAS study CAMPBELL BRANCH.prj: CAMPBELL BRANCH Base Level Engineering

--- CAMPBELL BRANCH.g01 (geometry) --- (continued)

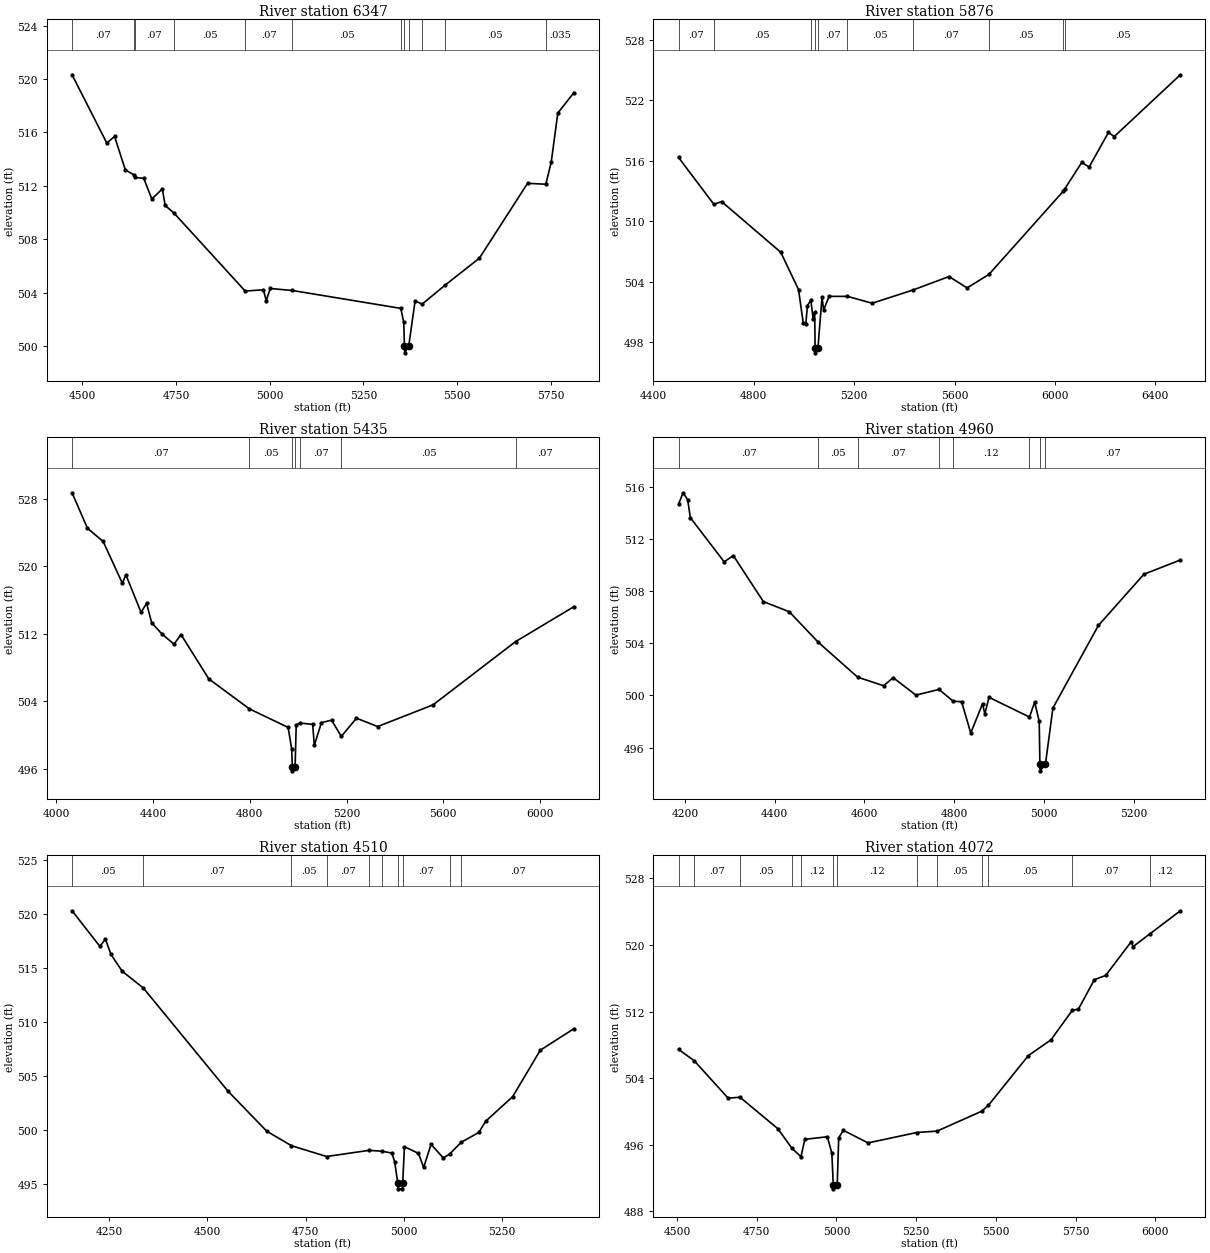
Type RM Length L Ch R = 1 ,6347    ,471,471,471
BEGIN DESCRIPTION:
CAMPBELL BRANCH 13.0
END DESCRIPTION:
XS GIS Cut Line= 3
      2290574.99     13733074.99        2290175.       13732725.
      2289375.02       13732825.
#Sta/Elev= 30
  4473.2  520.32  4565.7  515.21  4586.6   515.7  4615.1   513.2  4638.9  512.81
  4640.3  512.63  4664.4  512.56  4685.8  511.01  4713.8  511.77  4721.4  510.53
  4744.3  509.98  4934.6  504.12  4983.3  504.21  4990.9  503.39  5001.4  504.31
  5060.5  504.16  5349.6  502.82  5357.4  501.77  5359.3  499.99  5359.8  499.49
  5370.6  499.99  5387.7  503.38  5406.6  503.14  5466.7  504.54    5559  506.58
  5687.5  512.19  5736.1  512.12  5750.5  513.76  5768.1  517.45  5810.9  518.98
#Mann= 12 ,-1 , 0
  4473.2     .07       0  4638.9     .05       0  4640.3     .07       0
  4744.3     .05       0  4934.6     .07       0  5060.5     .05       0
  5349.6     .07       0  5359.3     .05       0  5370.6     .07       0
  5406.6     .07       0  5466.7     .05       0  5736.1    .035       0
Bank Sta=5359.3,5370.6
XS Rating Curve= 0 ,0
Exp/Cntr=0.3,0.1

Type RM Length L Ch R = 1 ,5876    ,441,441,441
BEGIN DESCRIPTION:
CAMPBELL BRANCH 12.0
END DESCRIPTION:
XS GIS Cut Line= 3
      2290675.02     13732725.03        2290375.       13732325.
      2289475.02     13731125.03
#Sta/Elev= 30
  4499.9  516.33  4640.8  511.68  4671.8  511.95  4907.2  506.93  4978.1  503.23
  4996.8  499.93  5007.2  499.78  5013.5  501.61  5027.1   502.2  5036.4  500.35
  5042.6  500.98  5044.2  497.45  5044.7  496.95  5055.6  497.45  5071.8  502.49
  5078.1   501.2  5099.9  502.55  5173.2  502.55  5271.8  501.87  5435.3  503.19
  5578.1  504.52  5649.9  503.39  5737.1  504.73    6034     513  6038.4  513.18
  6107.2  515.84  6136.4  515.38  6213.5  518.81  6236.4   518.4  6499.9  524.53
#Mann= 10 ,-1 , 0
  4499.9     .07       0  4640.8     .05       0  5027.1     .07       0
  5044.2     .05       0  5055.6     .07       0  5173.2     .05       0
  5435.3     .07       0  5737.1     .05       0    6034    .035       0
  6038.4     .05       0
Bank Sta=5044.2,5055.6
XS Rating Curve= 0 ,0
Exp/Cntr=0.3,0.1

Type RM Length L Ch R = 1 ,5435    ,475,475,475
BEGIN DESCRIPTION:
CAMPBELL BRANCH 11.0
END DESCRIPTION:
XS GIS Cut Line= 3
      2291224.97     13732874.96        2290675.       13732125.
      2290049.97     13731165.77
#Sta/Elev= 30
  4065.2  528.68  4128.8  524.48  4193.7  522.92  4273.1  517.98  4287.8  518.97
  4350.4  514.54  4373.5  515.59  4394.3   513.3  4437.2  511.96  4486.8  510.76
  4515.5  511.91  4630.5  506.66  4798.6  503.11  4958.6  500.92  4973.2  498.38
    4976  496.28  4976.5  495.78  4987.4  496.28  4992.1  501.23  5009.2  501.43
  5060.1  501.28  5066.8  498.78  5096.3  501.49  5138.5  501.77  5178.5  499.85
  5241.2  502.01  5328.8  501.02    5558  503.59  5899.1  511.07  6140.1   515.2
#Mann= 7 ,-1 , 0
  4065.2     .07       0  4798.6     .05       0    4976     .05       0
  4987.4     .05       0  5009.2     .07       0  5178.5     .05       0
  5899.1     .07       0
Bank Sta=4976,4987.4
XS Rating Curve= 0 ,0
Exp/Cntr=0.3,0.1

Type RM Length L Ch R = 1 ,4960    ,450,450,450
BEGIN DESCRIPTION:
CAMPBELL BRANCH 10.0
END DESCRIPTION:
XS GIS Cut Line= 3
        2291125.     13732624.98        2290975.       13731825.
      2290924.99     13731524.95
#Sta/Elev= 30
    4186  514.67  4196.1  515.55  4206.3  515.02  4212.3  513.64  4287.7  510.25
  4308.1  510.73    4375   507.2  4432.7  506.42  4497.6  504.07  4585.1   501.4
    4643  500.74  4664.2  501.36    4715  500.02  4766.4  500.46  4797.7  499.56
  4816.8  499.51  4837.1  497.11  4863.4  499.36  4868.5  498.58  4877.8  499.85
    4968  498.34  4979.6  499.48  4989.7     498  4991.2  494.71  4991.7  494.21
  5003.5  494.71  5020.2  499.03  5121.6  505.37    5223   509.3  5304.1  510.39
#Mann= 8 ,-1 , 0
    4186     .07       0  4497.6     .05       0  4585.1     .07       0
  4766.4     .05       0  4797.7     .12       0    4968     .07       0
  4991.2     .05       0  5003.5     .07       0
Bank Sta=4991.2,5003.5
XS Rating Curve= 0 ,0
Exp/Cntr=0.3,0.1

Type RM Length L Ch R = 1 ,4510    ,438,438,438
BEGIN DESCRIPTION:
CAMPBELL BRANCH 9.0
END DESCRIPTION:
XS GIS Cut Line= 3
      2291974.99     13732274.99        2291375.       13731675.
      2290975.02     13731525.01
#Sta/Elev= 30
  4156.5  520.26  4227.2  516.97  4241.3  517.64  4255.5  516.22  4283.8  514.67
  4337.6  513.12  4552.5  503.59  4651.5  499.87  4714.2  498.53  4803.7  497.53
  4911.5   498.1    4944  498.02  4969.7  497.85  4976.7  497.02  4984.7  495.04
  4985.2  494.54  4996.5  494.54    4997  495.04  5001.5  498.44  5037.1  497.82
  5050.4  496.52  5069.1  498.66  5100.2   497.4  5116.2  497.75  5145.7  498.84
    5191  499.77  5207.9  500.79  5276.5  503.06  5346.8  507.36  5432.2  509.35
#Mann= 10 ,-1 , 0
  4156.5     .05       0  4337.6     .07       0  4714.2     .05       0
  4803.7     .07       0  4911.5     .12       0    4944     .07       0
  4984.7     .05       0    4997     .07       0  5116.2     .12       0
  5145.7     .07       0
Bank Sta=4984.7,4997
XS Rating Curve= 0 ,0
Exp/Cntr=0.3,0.1

Type RM Length L Ch R = 1 ,4072    ,464,464,464
BEGIN DESCRIPTION:
CAMPBELL BRANCH 8.0
END DESCRIPTION:
XS GIS Cut Line= 3
      2291974.98     13731724.98        2291625.       13731375.
      2290991.83     13730501.74
#Sta/Elev= 30
  4504.8  507.45  4553.9  506.09  4660.3  501.59  4697.5   501.7  4815.9  497.93
  4859.2  495.63  4888.7  494.54  4900.8  496.64  4971.5  496.95  4985.6  494.96
    4990  491.19  4990.5  490.69  5002.4  491.19  5007.1  496.84  5021.8  497.72
  5099.1  496.21    5252  497.46  5315.7  497.63  5455.6  500.02  5476.3  500.72
  5601.7   506.7  5672.8   508.6  5739.9  512.16  5758.6  512.28  5808.9  515.83
  5844.4  516.34  5924.1  520.38  5930.3   519.8  5984.2  521.37  6078.4  524.11
#Mann= 13 ,-1 , 0
  4504.8     .05       0  4553.9     .07       0  4697.5     .05       0
  4859.2     .07       0  4888.7     .12       0    4990     .05       0
  5002.4     .12       0    5252     .07       0  5315.7     .05       0
  5455.6     .07       0  5476.3     .05       0  5739.9     .07       0
  5984.2     .12       0
Bank Sta=4990,5002.4
XS Rating Curve= 0 ,0
Exp/Cntr=0.3,0.1

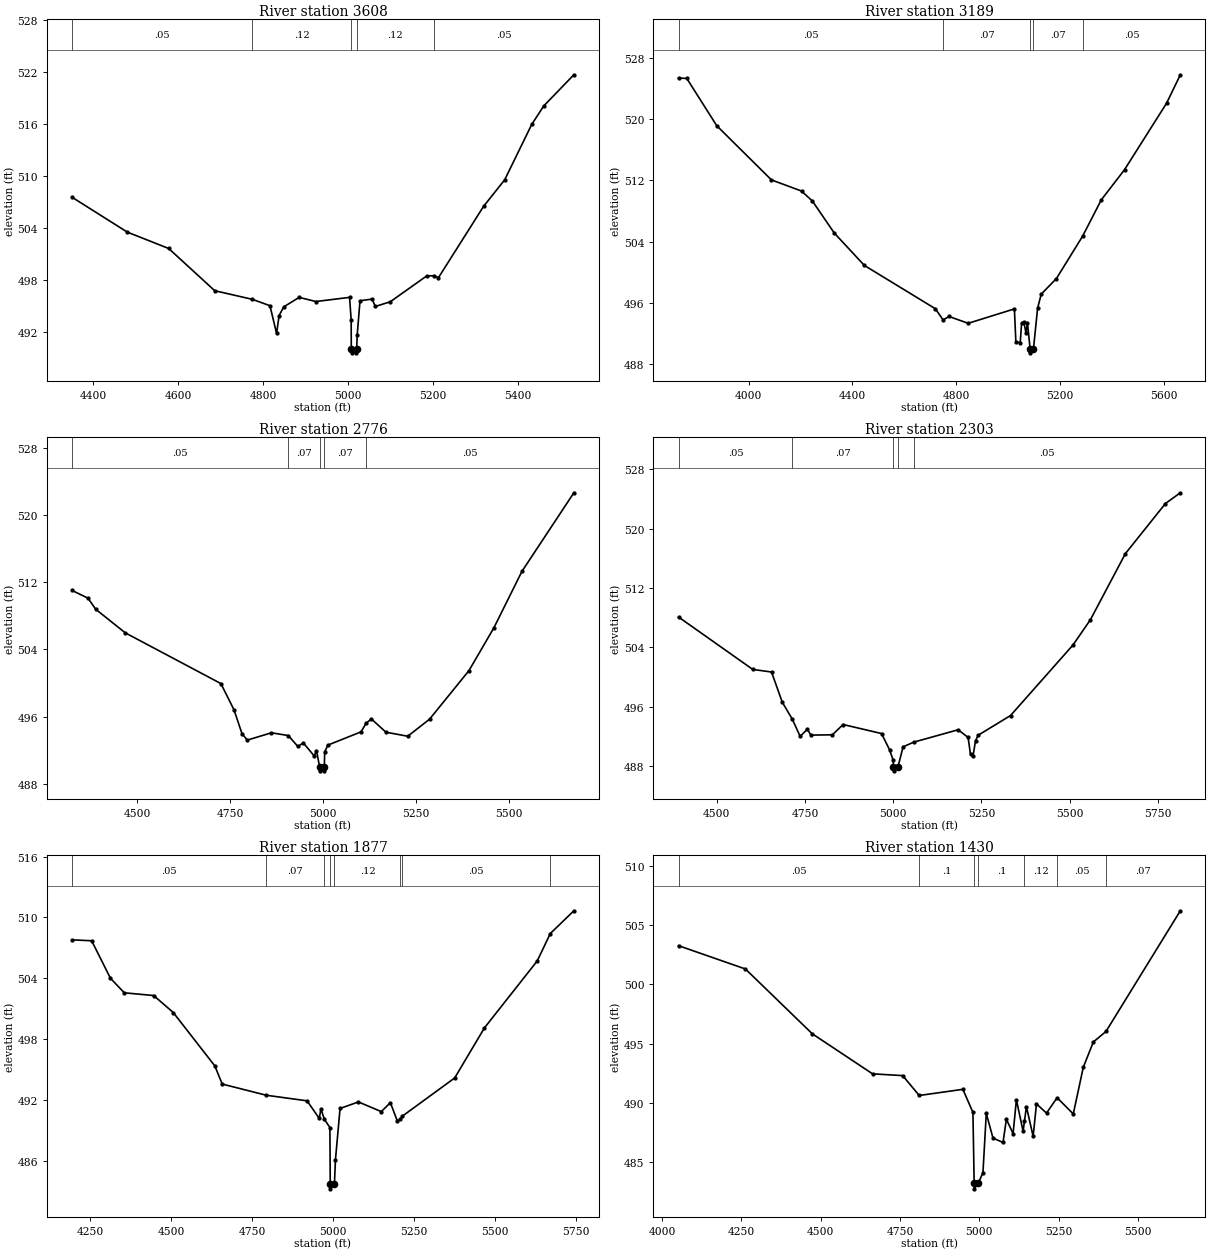
Type RM Length L Ch R = 1 ,3608    ,419,419,419
BEGIN DESCRIPTION:
CAMPBELL BRANCH 7.0
END DESCRIPTION:
XS GIS Cut Line= 3
      2292125.02     13731625.04        2291875.       13731025.
      2291524.97     13730624.97
#Sta/Elev= 30
  4349.9  507.59  4479.9  503.57  4577.4  501.68  4685.8  496.81  4774.6  495.81
  4815.8  495.08  4831.5  491.88  4837.4  493.94  4848.3  494.94  4884.6  496.04
  4924.1  495.56  5003.3  496.04  5007.1  493.47  5007.4  490.14  5007.9  489.64
  5019.6  489.64  5020.1  490.14  5021.3  491.69  5027.9  495.65  5056.4  495.84
    5064  494.99  5099.1  495.53  5184.6   498.5  5201.7  498.54  5212.6  498.31
  5318.9  506.54  5368.7  509.61  5432.3  515.99  5460.7  518.13  5531.5  521.72
#Mann= 5 ,-1 , 0
  4349.9     .05       0  4774.6     .12       0  5007.4     .05       0
  5020.1     .12       0  5201.7     .05       0
Bank Sta=5007.4,5020.1
XS Rating Curve= 0 ,0
Exp/Cntr=0.3,0.1

Type RM Length L Ch R = 1 ,3189    ,413,413,413
BEGIN DESCRIPTION:
CAMPBELL BRANCH 6.0
END DESCRIPTION:
XS GIS Cut Line= 3
      2292625.01     13732125.03        2292225.       13730925.
      2291924.98     13730324.97
#Sta/Elev= 30
  3729.1  525.35  3760.8  525.31  3876.7  519.13  4087.5  512.07  4203.5  510.62
  4245.6  509.31    4330  505.14  4445.9  500.92    4720  495.27  4749.7  493.81
  4772.7  494.26  4846.5  493.37  5024.8  495.25  5030.4  490.95  5047.2  490.85
  5052.7  493.43  5061.1  493.51  5069.5  492.13  5075.1  493.45  5085.5  490.02
    5086  489.52  5098.3  490.02  5114.2  495.32  5128.2  497.17  5186.9  499.21
  5287.9  504.73  5360.2  509.48  5449.6   513.4  5611.8  522.07  5664.9  525.78
#Mann= 5 ,-1 , 0
  3729.1     .05       0  4749.7     .07       0  5085.5     .05       0
  5098.3     .07       0  5287.9     .05       0
Bank Sta=5085.5,5098.3
XS Rating Curve= 0 ,0
Exp/Cntr=0.3,0.1

Type RM Length L Ch R = 1 ,2776    ,473,473,473
BEGIN DESCRIPTION:
CAMPBELL BRANCH 5.0
END DESCRIPTION:
XS GIS Cut Line= 3
      2292924.99     13731424.99        2292525.       13730875.
      2292224.99     13730274.98
#Sta/Elev= 30
  4324.5  511.02  4367.4   510.1  4388.2  508.78  4467.8  505.97  4725.2  499.93
  4760.7  496.78    4782  493.96  4796.3   493.2  4861.2  494.07  4906.9  493.74
  4932.3  492.44    4947  492.87  4976.4  491.31  4982.5  491.96  4990.8  490.04
  4991.3  489.54  5003.1  489.54  5003.6  490.04  5004.6  491.78  5012.9   492.6
  5102.4  494.18  5116.1  495.21  5130.3  495.72  5169.5  494.14  5228.2  493.66
  5286.9  495.69  5393.1  501.48  5460.2  506.58  5535.6  513.29  5675.4  522.65
#Mann= 5 ,-1 , 0
  4324.5     .05       0  4906.9     .07       0  4990.8     .05       0
  5003.6     .07       0  5116.1     .05       0
Bank Sta=4990.8,5003.6
XS Rating Curve= 0 ,0
Exp/Cntr=0.3,0.1

Type RM Length L Ch R = 1 ,2303    ,426,426,426
BEGIN DESCRIPTION:
CAMPBELL BRANCH 4.0
END DESCRIPTION:
XS GIS Cut Line= 3
      2293025.01     13731275.03        2292925.       13730675.
      2292325.04     13730125.03
#Sta/Elev= 30
  4391.7  508.08  4602.1  501.01  4655.3  500.66  4685.7  496.59  4714.1   494.3
  4736.4  491.98  4756.7  492.94  4766.8  492.15  4827.7  492.19  4858.1  493.58
  4967.1  492.36  4989.9  490.16    5000  488.77  5000.6  487.83  5001.1  487.33
  5013.5  487.83  5028.1  490.57  5058.3   491.2  5184.1  492.87  5212.4  491.84
  5219.2  489.54  5226.6  489.38  5233.4  491.38  5240.8  492.13  5332.7  494.79
  5509.6   504.3    5559  507.71  5658.3  516.64  5771.7  523.39  5813.9  524.84
#Mann= 5 ,-1 , 0
  4391.7     .05       0  4714.1     .07       0  5000.6     .05       0
  5013.5     .07       0  5058.3     .05       0
Bank Sta=5000.6,5013.5
XS Rating Curve= 0 ,0
Exp/Cntr=0.3,0.1

Type RM Length L Ch R = 1 ,1877    ,447,447,447
BEGIN DESCRIPTION:
CAMPBELL BRANCH 3.0
END DESCRIPTION:
XS GIS Cut Line= 3
      2293174.99     13731275.05        2293275.       13730475.
      2292774.99     13729924.98
#Sta/Elev= 30
  4194.1   507.8  4254.6  507.71  4312.6  504.02  4355.4  502.59  4446.1  502.32
  4506.6  500.65  4635.1  495.39  4657.7  493.61  4793.8  492.51  4919.8  491.96
  4957.5  490.23  4962.6  491.17  4973.1  490.15  4990.3  489.33  4991.4   483.8
  4991.9   483.3  5004.3   483.8  5007.5  486.18  5021.7  491.21  5078.4  491.85
    5149   490.9  5177.1  491.78  5198.7  489.96  5208.2  490.16  5214.4  490.46
  5375.7  494.21  5467.6  499.14  5630.5  505.72  5670.9  508.42  5743.7  510.66
#Mann= 8 ,-1 , 0
  4194.1     .05       0  4793.8     .07       0  4973.1     .12       0
  4991.4     .05       0  5004.3     .12       0  5208.2     .07       0
  5214.4     .05       0  5670.9     .07       0
Bank Sta=4991.4,5004.3
XS Rating Curve= 0 ,0
Exp/Cntr=0.3,0.1

Type RM Length L Ch R = 1 ,1430    ,486,486,486
BEGIN DESCRIPTION:
CAMPBELL BRANCH 2.0
END DESCRIPTION:
XS GIS Cut Line= 3
      2293774.99     13731024.98        2293475.       13730125.
      2292875.01       13729925.
#Sta/Elev= 30
  4052.4  503.27  4263.2   501.3    4474  495.82  4663.7  492.44  4758.6  492.29
  4810.8  490.61  4948.4  491.13    4980  489.18  4983.9  483.22  4984.4  482.72
  4997.2  483.22  5011.6  484.09  5022.1   489.1  5043.2  487.01  5074.8  486.64
  5085.4   488.6  5106.5  487.39    5117  490.24  5138.1  487.59  5142.4  488.44
  5148.6  489.66  5169.7  487.15  5180.3   489.9  5211.9  489.12  5245.2  490.42
  5296.2  489.05  5327.8     493  5359.4  495.13  5399.2  496.02  5633.5  506.22
#Mann= 7 ,-1 , 0
  4052.4     .05       0  4810.8      .1       0  4983.9     .05       0
  4997.2      .1       0  5142.4     .12       0  5245.2     .05       0
  5399.2     .07       0
Bank Sta=4983.9,4997.2
XS Rating Curve= 0 ,0
Exp/Cntr=0.3,0.1

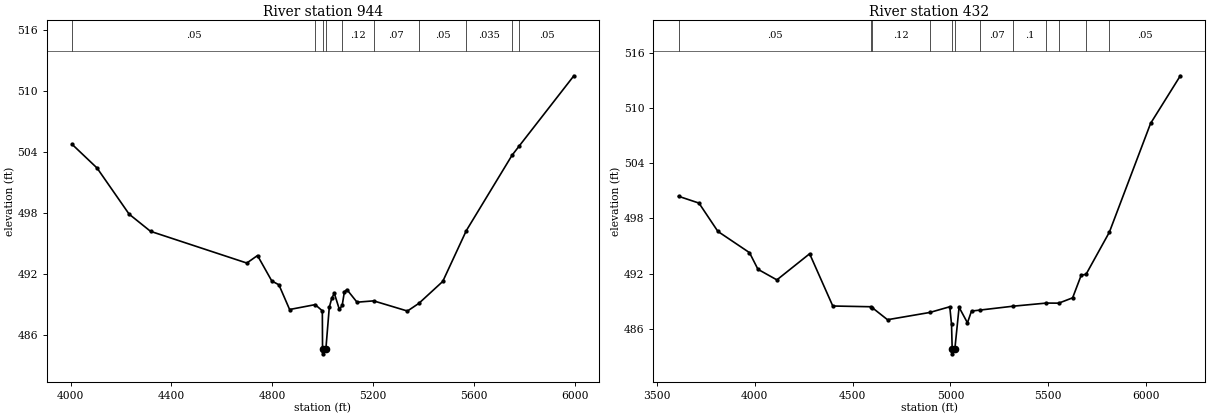
Type RM Length L Ch R = 1 ,944     ,512,512,512
BEGIN DESCRIPTION:
CAMPBELL BRANCH 1.0
END DESCRIPTION:
XS GIS Cut Line= 3
      2294425.02     13730525.02        2293725.       13729825.
      2292724.98       13729825.
#Sta/Elev= 30
  4005.8  504.79  4104.8  502.46  4232.1  497.92    4317  496.23  4698.8  493.11
  4741.2  493.85  4797.8  491.35  4826.1  490.97  4868.5  488.54  4969.9  489.02
  4998.3  488.41  4999.1  484.68  4999.6  484.18  5012.4  484.68  5025.8  488.74
  5035.8  489.66  5045.8  490.14  5065.8  488.55    5077  488.94  5085.8  490.29
  5095.8   490.5  5135.8  489.26  5201.7  489.39  5335.8  488.39  5380.9  489.14
  5475.8   491.3  5569.3   496.3  5750.6  503.71  5780.2  504.66  5995.8  511.53
#Mann= 10 ,-1 , 0
  4005.8     .05       0  4969.9      .1       0  4999.1     .05       0
  5012.4      .1       0    5077     .12       0  5201.7     .07       0
  5380.9     .05       0  5569.3    .035       0  5750.6     .07       0
  5780.2     .05       0
Bank Sta=4999.1,5012.4
XS Rating Curve= 0 ,0
Exp/Cntr=0.3,0.1

Type RM Length L Ch R = 1 ,432     ,0,0,0
BEGIN DESCRIPTION:
X18404
END DESCRIPTION:
XS GIS Cut Line= 4
      2294529.15     13730414.92      2293969.26     13729425.36
      2293622.04     13729360.26      2292623.78     13729759.56
#Sta/Elev= 30
    3610  500.41  3714.4  499.67  3811.2  496.59  3972.8  494.28  4016.1  492.47
  4112.8  491.32  4280.2  494.16  4398.6  488.48  4592.3   488.4  4599.7  488.31
  4678.4  486.99    4895  487.78  4996.8   488.4  5005.7  486.48  5009.1  483.78
  5009.6  483.28  5022.5  483.78  5044.3  488.34  5087.1  486.65  5107.8  487.93
    5152  488.04  5320.7  488.46  5490.8   488.8  5553.7  488.79  5624.8  489.37
  5669.1  491.85    5693  491.91  5812.7  496.51  6023.3  508.33  6175.4  513.51
#Mann= 12 ,-1 , 0
    3610     .05       0  4592.3     .07       0  4599.7     .12       0
    4895      .1       0  5009.1     .05       0  5022.5      .1       0
    5152     .07       0  5320.7      .1       0  5490.8     .12       0
  5553.7     .07       0    5693    .035       0  5812.7     .05       0
Bank Sta=5009.1,5022.5
XS Rating Curve= 0 ,0
Exp/Cntr=0.3,0.1

Chan Stop Cuts=-1
Use User Specified Reach Order=0
Composite Channel Slope=5