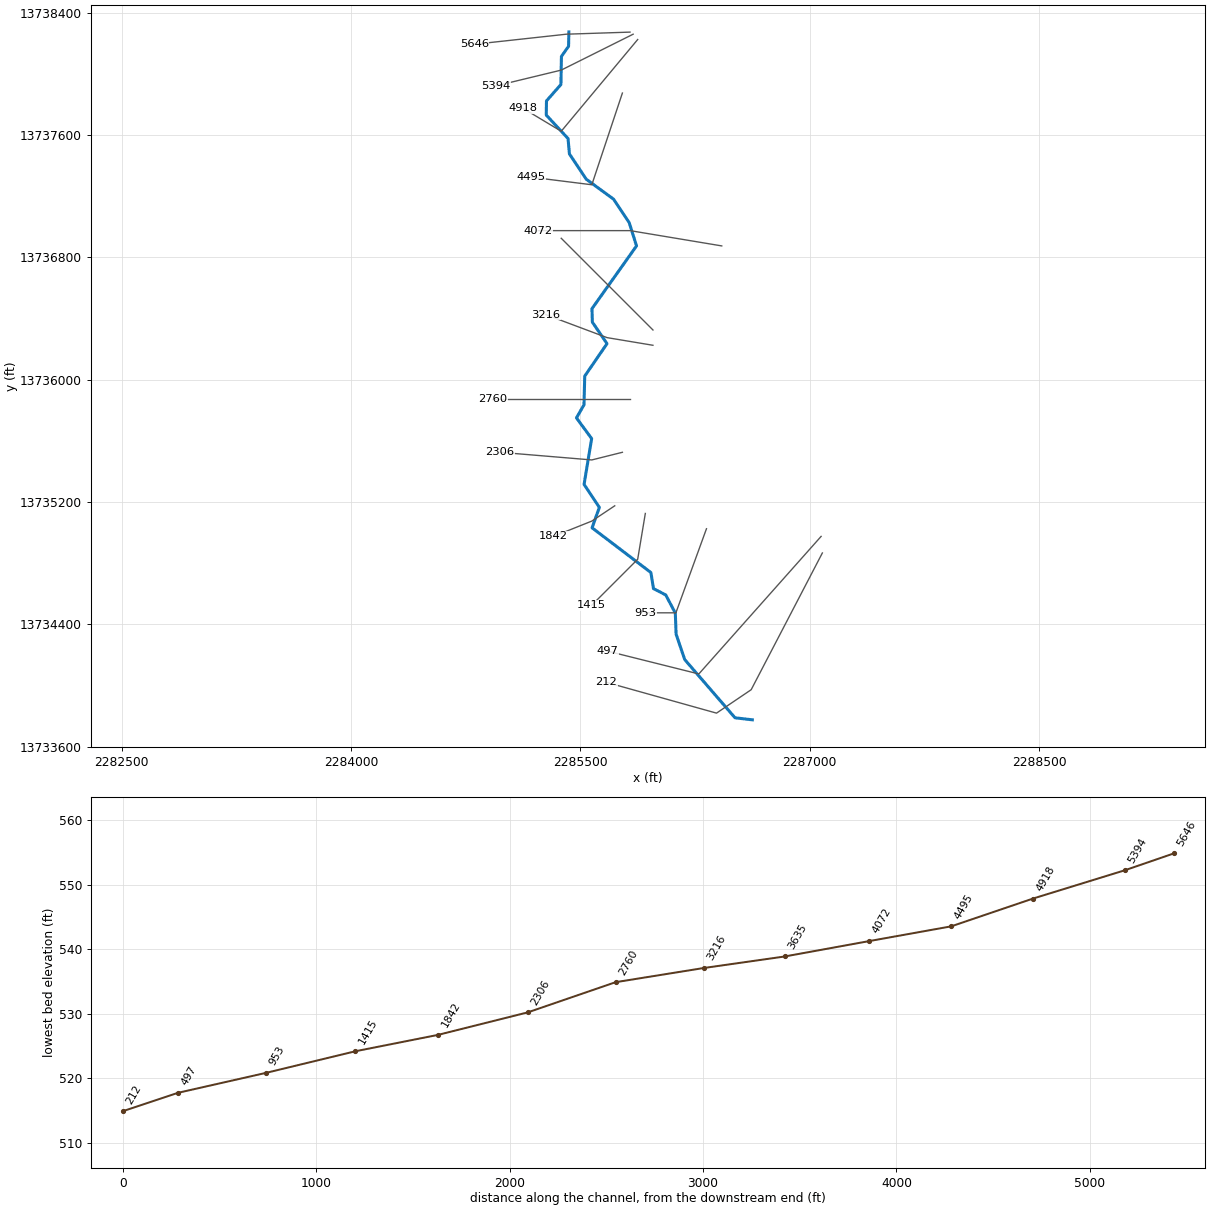
--- CAMPBELL TRIBUTARY 1.prj (project) ---

Proj Title=CAMPBELL TRIBUTARY 1 Base Level Engineering
Current Plan=p01
Default Exp/Contr=0.3,0.1
English Units
Geom File=g01
Flow File=f01
Plan File=p01
BEGIN DESCRIPTION:
CAMPBELL TRIBUTARY 1
END DESCRIPTION:

--- CAMPBELL TRIBUTARY 1.p01 (plan) ---

Plan Title=Multiple Run
Short Identifier=Multiple
Geom File=g01
Flow File=f01
Subcritical Flow
K Sum by GR= 0
Std Step Tol= 0.01
Critical Tol= 0.01
Num of Std Step Trials= 20
Max Error Tol= 0.3
Flow Tol Ratio= 0.001
Split Flow NTrial= 30
Split Flow Tol= 0.02
Split Flow Ratio= 0.02
Log Output Level= 0
Friction Slope Method= 1
Unsteady Friction Slope Method= 2
Unsteady Bridges Friction Slope Method= 1
Parabolic Critical Depth
Global Vel Dist=  1 , 1 , 1
Global Log Level= 0
CheckData=True
Encroach Param= -1, 0, 0, 0
BEGIN DESCRIPTION:
Multiple Run
END DESCRIPTION:

--- CAMPBELL TRIBUTARY 1.f01 (steady flow) ---

Flow Title=Multiple
Number of Profiles=7
Profile Names=10-year,25-year,50-year,1pct_min,100-year,1pct_plu,500-year
River Rch & RM= CAMPBELL TRIBUTA,Reach-1,5646
     384     600     788     502    1002    2000    1603
Boundary for River Rch & Prof#=CAMPBELL TRIBUTA,Reach-1,1
Up Type=0
Dn Type=3
Dn Slope=0.005
Boundary for River Rch & Prof#=CAMPBELL TRIBUTA,Reach-1,2
Up Type=0
Dn Type=3
Dn Slope=0.005
Boundary for River Rch & Prof#=CAMPBELL TRIBUTA,Reach-1,3
Up Type=0
Dn Type=3
Dn Slope=0.005
Boundary for River Rch & Prof#=CAMPBELL TRIBUTA,Reach-1,4
Up Type=0
Dn Type=3
Dn Slope=0.005
Boundary for River Rch & Prof#=CAMPBELL TRIBUTA,Reach-1,5
Up Type=0
Dn Type=3
Dn Slope=0.005
Boundary for River Rch & Prof#=CAMPBELL TRIBUTA,Reach-1,6
Up Type=0
Dn Type=3
Dn Slope=0.005
Boundary for River Rch & Prof#=CAMPBELL TRIBUTA,Reach-1,7
Up Type=0
Dn Type=3
Dn Slope=0.005

--- CAMPBELL TRIBUTARY 1.g01 (geometry) ---

Geom Title=Existing Conditions

River Reach=CAMPBELL TRIBUTA,Reach-1
Reach XY= 30
      2285425.00     13738275.00      2285422.90     13738180.87
      2285376.20     13738114.50      2285372.93     13737930.86
      2285278.47     13737823.50      2285276.96     13737730.89
      2285419.48     13737577.43      2285428.63     13737476.50
      2285538.49     13737311.44      2285716.85     13737181.07
      2285819.47     13737027.42      2285867.47     13736874.99
      2285576.08     13736464.45      2285578.47     13736376.50
      2285674.44     13736235.64      2285528.75     13736023.45
      2285523.76     13735835.50      2285474.51     13735749.96
      2285573.96     13735614.56      2285524.45     13735314.81
      2285624.39     13735164.37      2285576.62     13735031.03
      2285961.59     13734738.30      2285978.19     13734633.35
      2286058.43     13734592.02      2286121.24     13734473.44
      2286126.23     13734335.51      2286182.86     13734168.83
      2286511.65     13733788.34      2286625.00     13733775.00

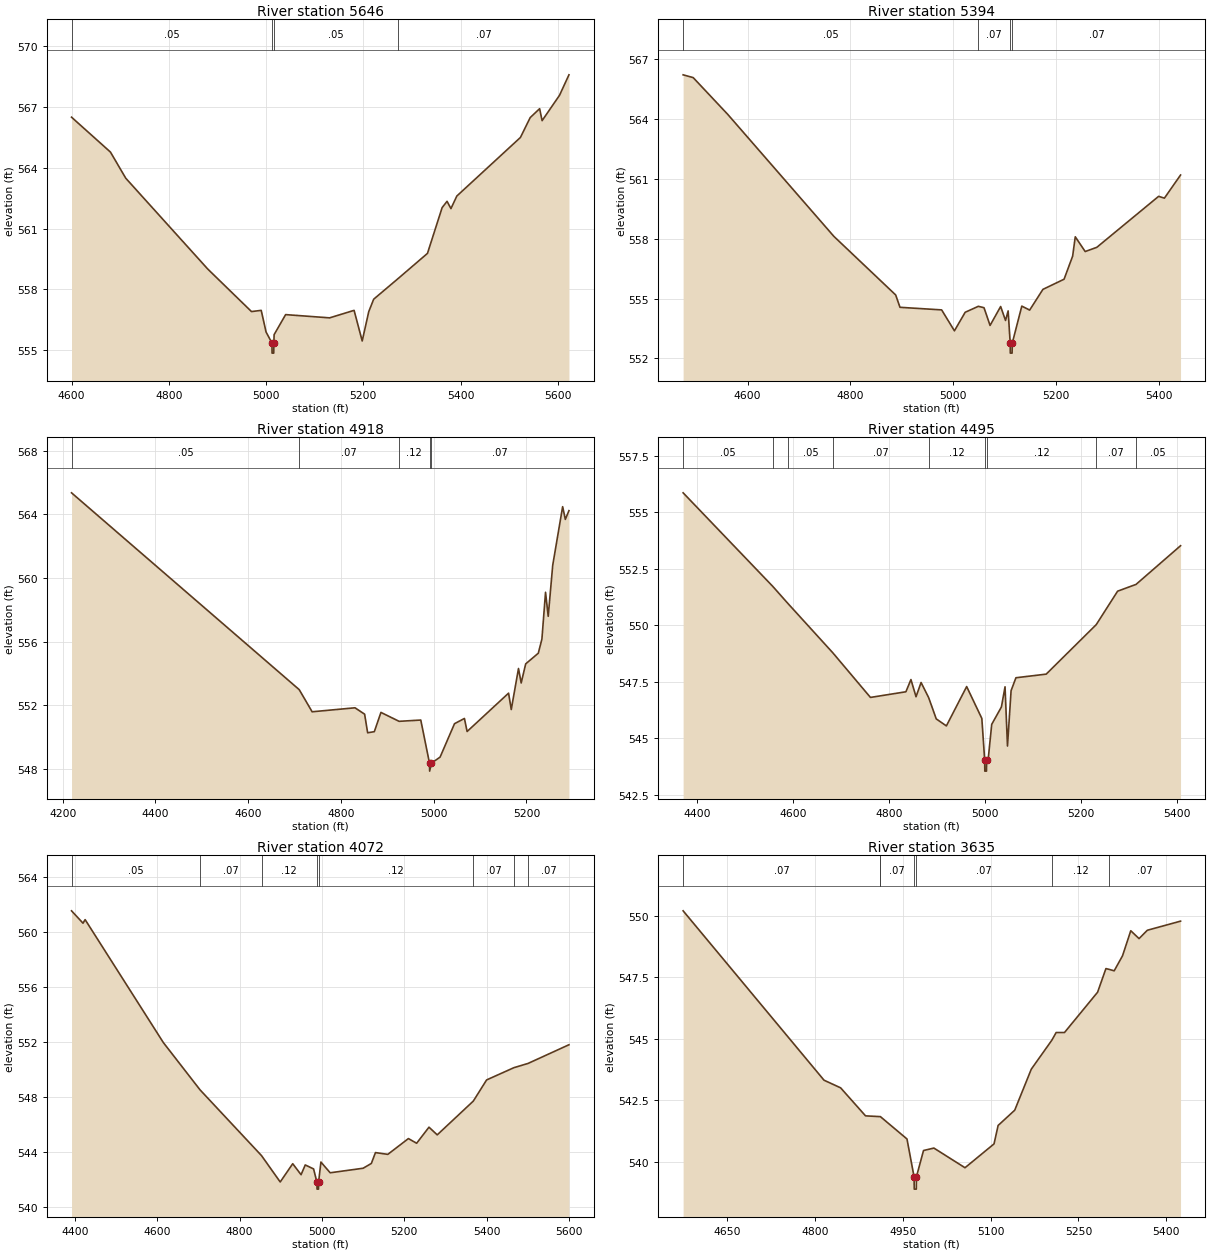
Type RM Length L Ch R = 1,5646,252,252,252
BEGIN DESCRIPTION:
X18405
END DESCRIPTION:
XS GIS Cut Line= 3
      2285824.92     13738273.54      2285408.57     13738259.89
      2284805.74     13738193.92
#Sta/Elev= 30
  4600.0  566.50  4680.0  564.78  4711.5  563.49  4880.1  559.01  4970.1  556.91
  4990.1  556.97  5000.1  555.90  5012.2  555.36  5012.4  554.86  5015.9  554.86
  5016.2  555.36  5016.6  555.77  5040.3  556.76  5130.8  556.60  5181.1  556.97
  5197.8  555.46  5211.3  556.91  5221.4  557.52  5272.2  558.55  5332.0  559.78
  5362.2  562.04  5372.3  562.35  5380.3  561.99  5392.4  562.61  5523.2  565.50
  5543.3  566.48  5562.7  566.92  5567.8  566.33  5603.6  567.58  5623.0  568.59
#Mann=4,-1,0
  4600.0    0.05       0  5012.2    0.05       0  5016.2    0.05       0
  5272.2    0.07       0
Bank Sta=5012.2,5016.2
Exp/Cntr=0.3,0.1

Type RM Length L Ch R = 1,5394,476,476,476
BEGIN DESCRIPTION:
CAMPBELL TRIBUTARY 1 12.0
END DESCRIPTION:
XS GIS Cut Line= 3
      2285845.33     13738259.87      2285375.00     13738025.00
      2284944.52     13737920.93
#Sta/Elev= 30
  4474.3  566.23  4493.9  566.09  4561.0  564.25  4767.9  558.12  4888.2  555.18
  4896.6  554.56  4977.7  554.43  5002.6  553.38  5023.5  554.31  5049.2  554.61
  5060.2  554.54  5072.0  553.65  5092.6  554.60  5102.1  553.90  5107.2  554.38
  5111.2  552.76  5111.4  552.26  5114.9  552.26  5115.2  552.76  5133.8  554.62
  5149.1  554.42  5174.9  555.46  5216.1  555.97  5232.8  557.13  5237.9  558.10
  5257.2  557.36  5279.8  557.57  5400.2  560.13  5411.5  560.04  5442.9  561.20
#Mann=4,-1,0
  4474.3    0.05       0  5049.2    0.07       0  5111.2    0.05       0
  5115.2    0.07       0
Bank Sta=5111.2,5115.2
Exp/Cntr=0.3,0.1

Type RM Length L Ch R = 1,4918,423,423,423
BEGIN DESCRIPTION:
CAMPBELL TRIBUTARY 1 11.0
END DESCRIPTION:
XS GIS Cut Line= 3
      2285875.03     13738225.03      2285375.00     13737625.00
      2285125.01     13737774.99
#Sta/Elev= 30
  4219.2  565.35  4710.2  552.98  4738.0  551.59  4830.4  551.84  4851.2  551.44
  4857.7  550.27  4872.1  550.34  4886.4  551.55  4925.5  550.99  4972.3  551.07
  4991.1  548.36  4991.4  547.86  4995.1  548.36  5013.9  548.74  5045.0  550.84
  5066.4  551.17  5072.2  550.35  5161.6  552.76  5167.4  551.73  5183.0  554.31
  5188.8  553.40  5198.5  554.60  5225.7  555.27  5233.5  556.16  5241.3  559.10
  5247.1  557.59  5256.8  560.80  5278.2  564.48  5284.0  563.68  5291.8  564.23
#Mann=5,-1,0
  4219.2    0.05       0  4710.2    0.07       0  4925.5    0.12       0
  4991.1    0.05       0  4995.1    0.07       0
Bank Sta=4991.1,4995.1
Exp/Cntr=0.3,0.1

Type RM Length L Ch R = 1,4495,423,423,423
BEGIN DESCRIPTION:
CAMPBELL TRIBUTARY 1 10.0
END DESCRIPTION:
XS GIS Cut Line= 3
      2285775.00     13737875.00      2285575.00     13737275.00
      2285174.97     13737325.00
#Sta/Elev= 30
  4371.7  555.86  4558.4  551.72  4589.7  550.97  4683.5  548.78  4761.7  546.81
  4835.5  547.06  4846.0  547.60  4856.6  546.84  4867.1  547.47  4882.9  546.80
  4898.7  545.86  4919.8  545.55  4962.0  547.29  4993.6  545.88  4999.5  544.05
  4999.8  543.55  5003.3  543.55  5003.5  544.05  5006.7  544.05  5014.2  545.62
  5034.4  546.39  5041.9  547.28  5047.0  544.66  5054.5  547.11  5064.6  547.68
  5127.6  547.84  5231.8  550.03  5276.3  551.51  5314.7  551.81  5407.3  553.52
#Mann=9,-1,0
  4371.7    0.05       0  4558.4    0.07       0  4589.7    0.05       0
  4683.5    0.07       0  4882.9    0.12       0  4999.5    0.05       0
  5003.5    0.12       0  5231.8    0.07       0  5314.7    0.05       0
Bank Sta=4999.5,5003.5
Exp/Cntr=0.3,0.1

Type RM Length L Ch R = 1,4072,437,437,437
BEGIN DESCRIPTION:
CAMPBELL TRIBUTARY 1 9.0
END DESCRIPTION:
XS GIS Cut Line= 3
      2286425.01     13736875.00      2285825.00     13736975.00
      2285224.99     13736975.00
#Sta/Elev= 30
  4391.8  561.53  4419.7  560.63  4424.8  560.89  4614.8  551.94  4703.9  548.50
  4853.3  543.71  4898.7  541.79  4929.1  543.12  4949.4  542.32  4959.5  543.03
  4979.8  542.74  4987.9  541.77  4988.2  541.27  4991.7  541.27  4991.9  541.77
  4997.6  543.24  5020.1  542.46  5100.1  542.79  5120.1  543.14  5130.1  543.93
  5160.1  543.80  5210.1  544.95  5230.1  544.61  5260.1  545.78  5280.1  545.22
  5367.8  547.68  5400.1  549.22  5466.3  550.11  5500.7  550.42  5600.1  551.78
#Mann=8,-1,0
  4391.8    0.05       0  4703.9    0.07       0  4853.3    0.12       0
  4987.9    0.05       0  4991.9    0.12       0  5367.8    0.07       0
  5466.3    0.05       0  5500.7    0.07       0
Bank Sta=4987.9,4991.9
Exp/Cntr=0.3,0.1

Type RM Length L Ch R = 1,3635,419,419,419
BEGIN DESCRIPTION:
CAMPBELL TRIBUTARY 1 8.0
END DESCRIPTION:
XS GIS Cut Line= 3
      2285975.02     13736324.98      2285675.00     13736625.00
      2285374.97     13736925.03
#Sta/Elev= 30
  4575.5  550.20  4815.9  543.31  4844.2  543.00  4886.7  541.86  4910.6  541.83
  4912.0  541.83  4957.4  540.92  4969.5  539.38  4969.8  538.88  4973.3  538.88
  4973.5  539.38  4985.6  540.45  5003.3  540.55  5056.4  539.75  5105.9  540.72
  5112.9  541.47  5141.2  542.09  5169.5  543.76  5204.6  544.94  5211.9  545.25
  5226.1  545.25  5282.6  546.89  5296.8  547.85  5302.0  547.82  5310.9  547.76
  5325.1  548.37  5339.2  549.39  5353.3  549.07  5367.5  549.41  5424.1  549.78
#Mann=7,-1,0
  4575.5    0.07       0  4910.6    0.12       0  4912.0    0.07       0
  4969.5    0.05       0  4973.5    0.07       0  5204.6    0.12       0
  5302.0    0.07       0
Bank Sta=4969.5,4973.5
Exp/Cntr=0.3,0.1

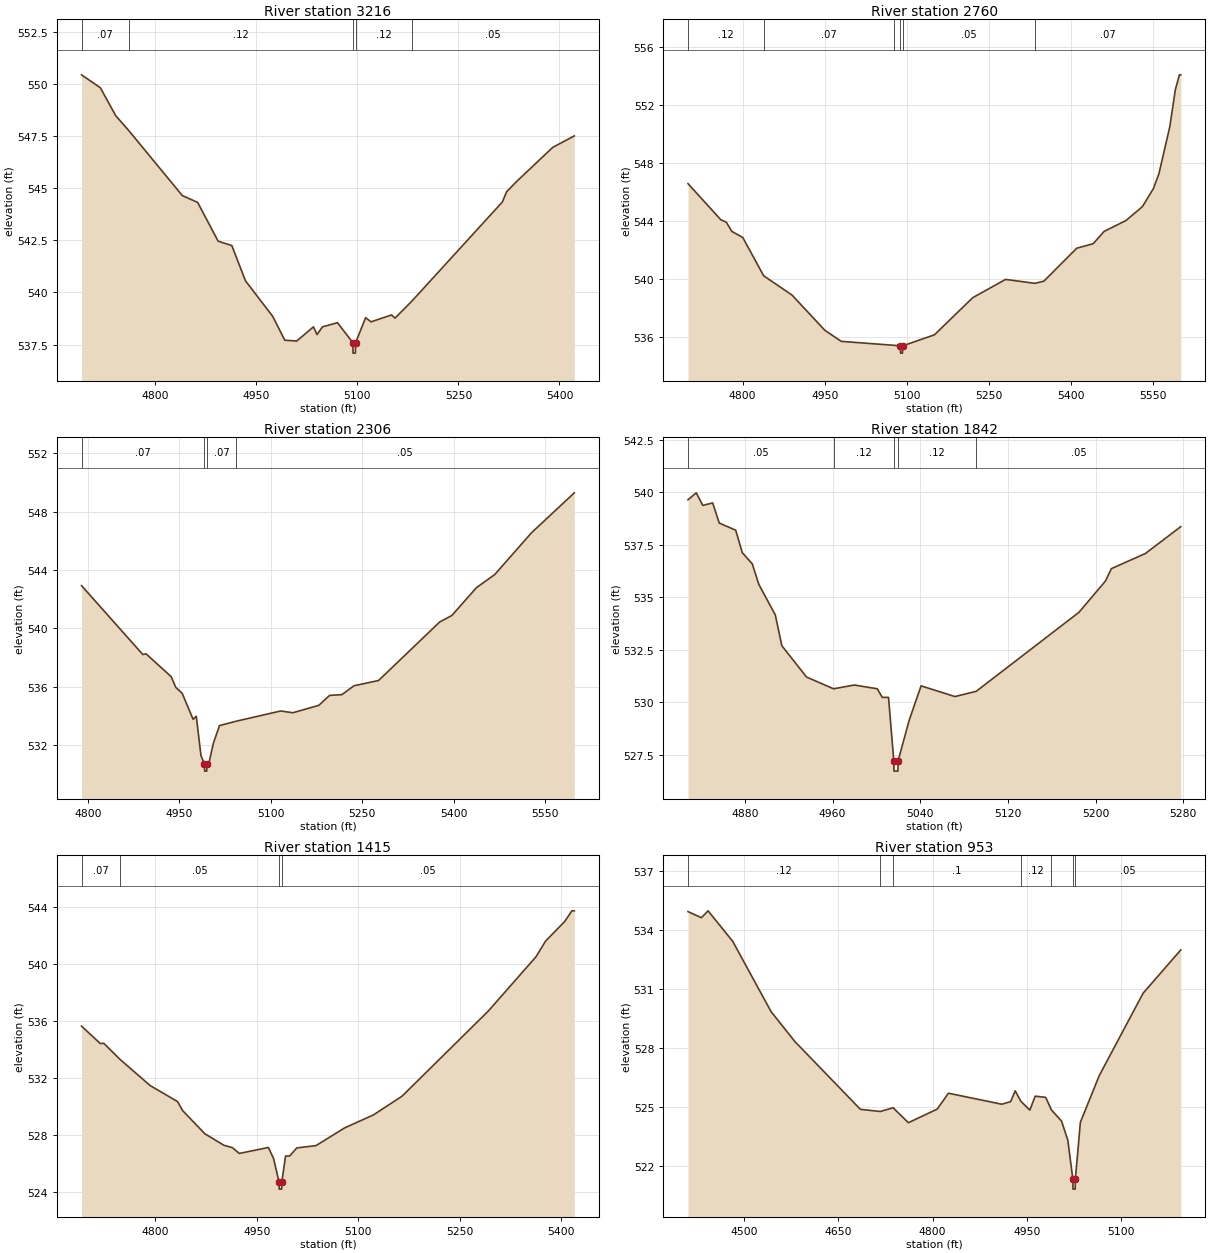
Type RM Length L Ch R = 1,3216,456,456,456
BEGIN DESCRIPTION:
CAMPBELL TRIBUTARY 1 7.0
END DESCRIPTION:
XS GIS Cut Line= 3
      2285974.99     13736225.00      2285675.00     13736275.00
      2285275.02     13736424.99
#Sta/Elev= 30
  4690.7  550.44  4718.6  549.82  4741.4  548.48  4761.2  547.75  4840.2  544.65
  4863.0  544.32  4893.4  542.46  4913.7  542.25  4934.0  540.56  4974.5  538.85
  4992.3  537.71  5010.0  537.67  5034.9  538.35  5040.2  537.98  5048.2  538.35
  5070.5  538.55  5093.4  537.59  5093.6  537.09  5097.1  537.09  5097.4  537.59
  5112.3  538.79  5120.3  538.59  5150.6  538.92  5155.9  538.77  5181.1  539.59
  5315.2  544.34  5321.5  544.83  5336.6  545.33  5390.0  546.96  5422.0  547.51
#Mann=5,-1,0
  4690.7    0.07       0  4761.2    0.12       0  5093.4    0.05       0
  5097.4    0.12       0  5181.1    0.05       0
Bank Sta=5093.4,5097.4
Exp/Cntr=0.3,0.1

Type RM Length L Ch R = 1,2760,454,454,454
BEGIN DESCRIPTION:
CAMPBELL TRIBUTARY 1 6.0
END DESCRIPTION:
XS GIS Cut Line= 3
      2285825.00     13735875.00      2285525.00     13735875.00
      2284925.00     13735875.00
#Sta/Elev= 30
  4700.4  546.57  4760.4  544.08  4770.4  543.91  4780.4  543.28  4800.4  542.86
  4838.6  540.22  4890.4  538.89  4950.4  536.46  4980.4  535.70  5076.2  535.43
  5088.4  535.39  5088.6  534.89  5092.1  534.89  5092.4  535.39  5150.4  536.15
  5220.4  538.71  5280.4  539.97  5334.0  539.70  5350.4  539.85  5410.4  542.12
  5440.4  542.43  5460.4  543.28  5500.4  544.03  5530.4  544.99  5550.4  546.23
  5560.4  547.24  5580.4  550.50  5590.4  553.03  5597.9  554.07  5600.4  554.07
#Mann=6,-1,0
  4700.4    0.12       0  4838.6    0.07       0  5076.2    0.05       0
  5088.4    0.05       0  5092.4    0.05       0  5334.0    0.07       0
Bank Sta=5088.4,5092.4
Exp/Cntr=0.3,0.1

Type RM Length L Ch R = 1,2306,464,464,464
BEGIN DESCRIPTION:
CAMPBELL TRIBUTARY 1 5.0
END DESCRIPTION:
XS GIS Cut Line= 3
      2285775.05     13735525.01      2285575.00     13735475.00
      2284974.98     13735525.00
#Sta/Elev= 30
  4789.4  542.92  4889.9  538.20  4895.1  538.25  4936.3  536.69  4944.1  535.94
  4954.4  535.55  4972.4  533.76  4977.6  533.97  4985.3  531.27  4991.0  530.71
  4991.3  530.21  4994.8  530.21  4995.0  530.71  4998.1  530.71  5005.6  532.12
  5015.7  533.33  5043.0  533.63  5116.0  534.33  5136.1  534.21  5178.7  534.72
  5196.3  535.40  5216.4  535.45  5236.4  536.06  5276.6  536.42  5376.9  540.43
  5397.0  540.88  5437.1  542.78  5467.2  543.68  5527.4  546.54  5597.7  549.28
#Mann=4,-1,0
  4789.4    0.07       0  4991.0    0.05       0  4995.0    0.07       0
  5043.0    0.05       0
Bank Sta=4991,4995
Exp/Cntr=0.3,0.1

Type RM Length L Ch R = 1,1842,427,427,427
BEGIN DESCRIPTION:
CAMPBELL TRIBUTARY 1 4.0
END DESCRIPTION:
XS GIS Cut Line= 3
      2285724.97     13735174.98      2285575.00     13735075.00
      2285325.00     13734975.00
#Sta/Elev= 30
  4828.2  539.64  4835.7  539.97  4841.7  539.37  4850.7  539.49  4856.7  538.53
  4871.7  538.19  4877.7  537.12  4886.8  536.59  4892.8  535.61  4907.8  534.16
  4913.8  532.69  4936.3  531.20  4961.0  530.64  4979.9  530.82  5000.9  530.64
  5005.4  530.23  5011.1  530.23  5015.9  527.22  5016.1  526.72  5019.6  526.72
  5019.9  527.22  5030.0  529.15  5040.8  530.78  5071.7  530.27  5091.1  530.52
  5184.8  534.28  5209.0  535.77  5214.4  536.36  5245.4  537.08  5277.7  538.36
#Mann=5,-1,0
  4828.2    0.05       0  4961.0    0.12       0  5015.9    0.05       0
  5019.9    0.12       0  5091.1    0.05       0
Bank Sta=5015.9,5019.9
Exp/Cntr=0.3,0.1

Type RM Length L Ch R = 1,1415,462,462,462
BEGIN DESCRIPTION:
CAMPBELL TRIBUTARY 1 3.0
END DESCRIPTION:
XS GIS Cut Line= 3
      2285924.99     13735124.96      2285875.00     13734825.00
      2285574.97     13734524.97
#Sta/Elev= 30
  4691.1  535.65  4718.9  534.42  4724.0  534.44  4747.7  533.32  4792.4  531.47
  4833.0  530.34  4840.6  529.70  4873.5  528.07  4901.4  527.27  4914.1  527.10
  4924.2  526.69  4967.3  527.11  4974.9  526.34  4983.1  524.68  4983.3  524.18
  4986.8  524.18  4987.1  524.68  4992.7  526.51  4998.7  526.51  5009.3  527.08
  5037.6  527.24  5080.1  528.49  5122.5  529.40  5164.9  530.72  5292.2  536.70
  5362.9  540.53  5377.0  541.63  5405.3  543.01  5415.9  543.76  5419.5  543.76
#Mann=4,-1,0
  4691.1    0.07       0  4747.7    0.05       0  4983.1    0.05       0
  4987.1    0.05       0
Bank Sta=4983.1,4987.1
Exp/Cntr=0.3,0.1

Type RM Length L Ch R = 1,953,456,456,456
BEGIN DESCRIPTION:
CAMPBELL TRIBUTARY 1 2.0
END DESCRIPTION:
XS GIS Cut Line= 3
      2286325.01     13735025.03      2286125.00     13734475.00
      2285924.96     13734475.00
#Sta/Elev= 30
  4410.2  534.95  4431.5  534.64  4442.2  534.99  4481.4  533.44  4542.6  529.86
  4580.5  528.34  4684.9  524.89  4716.5  524.78  4737.1  524.97  4761.4  524.21
  4807.3  524.90  4825.2  525.71  4910.3  525.15  4924.3  525.28  4931.6  525.83
  4940.7  525.30  4954.9  524.85  4963.5  525.56  4980.2  525.50  4989.4  524.86
  5005.5  524.29  5015.5  523.32  5023.5  521.33  5023.7  520.83  5027.2  520.83
  5027.5  521.33  5035.5  524.23  5065.5  526.60  5135.5  530.80  5195.5  533.00
#Mann=7,-1,0
  4410.2    0.12       0  4716.5    0.05       0  4737.1     0.1       0
  4940.7    0.12       0  4989.4    0.05       0  5023.5    0.05       0
  5027.5    0.05       0
Bank Sta=5023.5,5027.5
Exp/Cntr=0.3,0.1

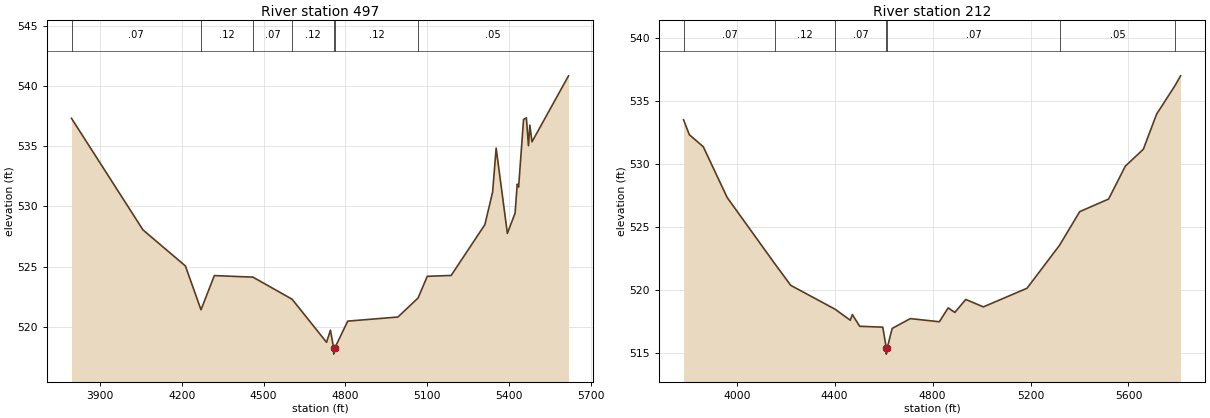
Type RM Length L Ch R = 1,497,285,285,285
BEGIN DESCRIPTION:
CAMPBELL TRIBUTARY 1 1.0
END DESCRIPTION:
XS GIS Cut Line= 3
      2287074.97     13734974.97      2286275.00     13734075.00
      2285674.98     13734225.00
#Sta/Elev= 30
  3795.8  537.30  4057.9  528.04  4213.4  525.05  4270.7  521.41  4319.6  524.25
  4461.2  524.12  4604.6  522.29  4731.1  518.71  4745.3  519.72  4757.1  518.23
  4757.3  517.73  4761.1  518.23  4808.8  520.47  4992.8  520.81  5066.7  522.39
  5100.4  524.19  5188.0  524.26  5311.7  528.48  5340.1  531.19  5353.0  534.83
  5394.2  527.75  5422.5  529.44  5430.3  531.84  5435.4  531.60  5453.5  537.20
  5463.8  537.35  5471.5  535.03  5476.6  536.74  5484.4  535.35  5618.4  540.83
#Mann=7,-1,0
  3795.8    0.07       0  4270.7    0.12       0  4461.2    0.07       0
  4604.6    0.12       0  4757.1    0.05       0  4761.1    0.12       0
  5066.7    0.05       0
Bank Sta=4757.1,4761.1
Exp/Cntr=0.3,0.1

Type RM Length L Ch R = 1,212,0,0,0
BEGIN DESCRIPTION:
X18406
END DESCRIPTION:
XS GIS Cut Line= 4
      2287083.12     13734866.53      2286617.44     13733971.95
      2286390.73     13733818.77      2285670.60     13734020.16
#Sta/Elev= 30
  3782.8  533.48  3806.3  532.30  3863.4  531.34  3961.0  527.31  4156.8  522.02
  4220.6  520.34  4401.2  518.45  4463.8  517.57  4472.2  518.02  4502.3  517.09
  4596.4  517.02  4610.8  515.38  4611.1  514.88  4614.8  515.38  4634.9  516.92
  4709.0  517.70  4827.5  517.45  4863.5  518.55  4890.8  518.19  4935.4  519.22
  5007.3  518.63  5185.6  520.11  5318.4  523.52  5400.8  526.19  5518.8  527.19
  5587.1  529.80  5660.6  531.14  5714.7  533.92  5790.8  536.22  5812.7  536.97
#Mann=7,-1,0
  3782.8    0.07       0  4156.8    0.12       0  4401.2    0.07       0
  4610.8    0.05       0  4614.8    0.07       0  5318.4    0.05       0
  5790.8    0.07       0
Bank Sta=4610.8,4614.8
Exp/Cntr=0.3,0.1

Chan Stop Cuts=-1