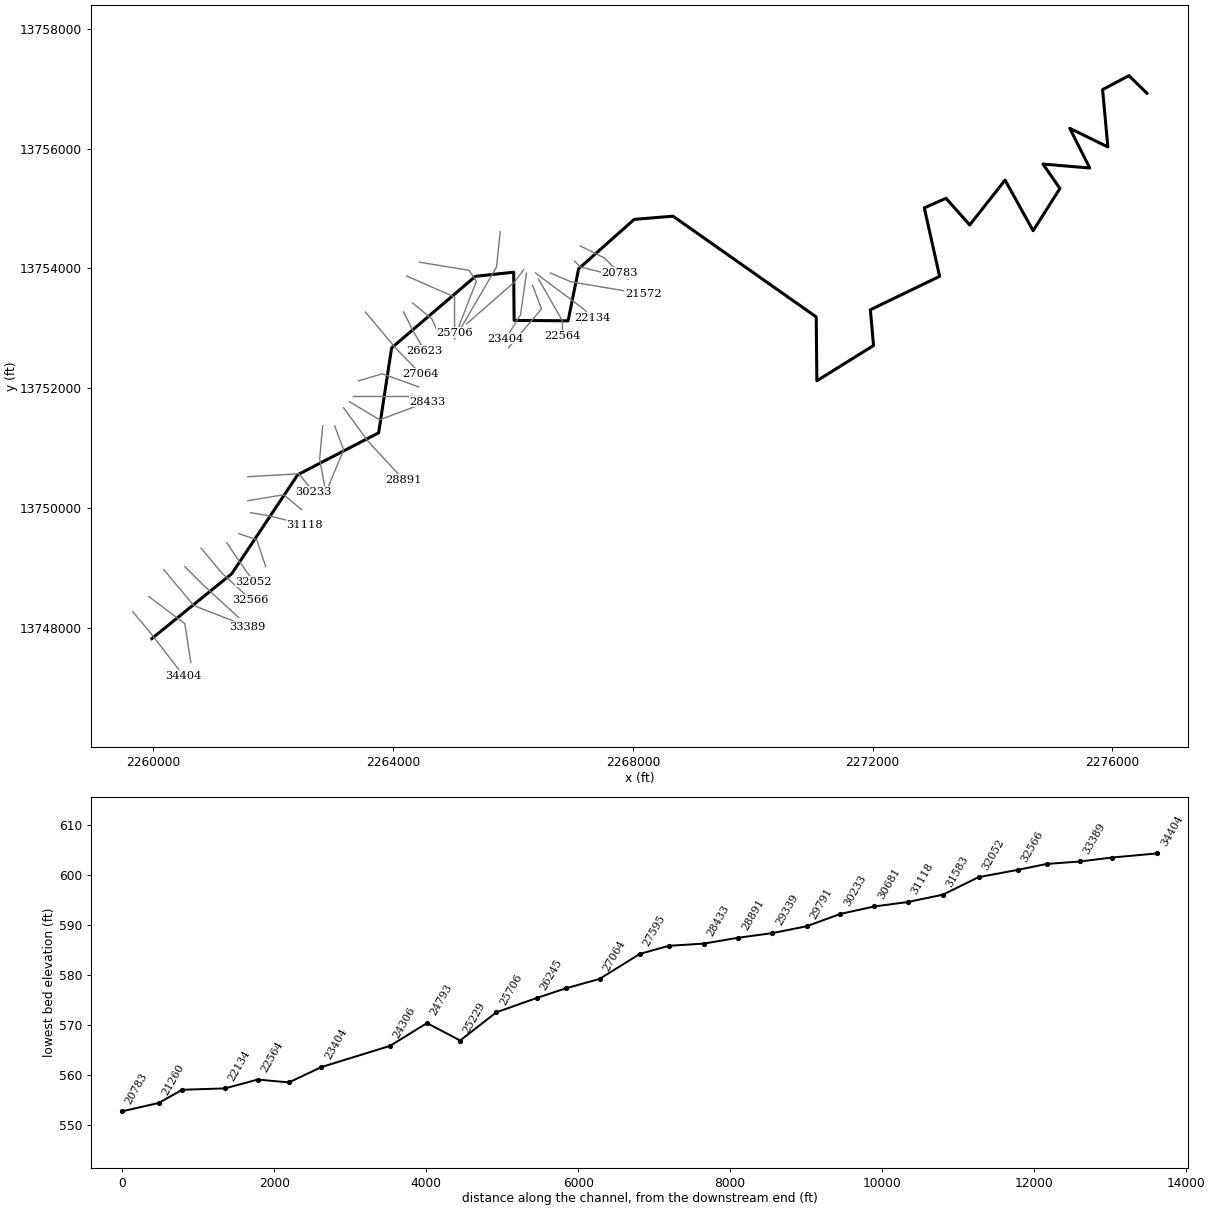
--- COTTONWOOD CREEK SOUTH 2.prj (project) ---

Proj Title=COTTONWOOD CREEK SOUTH 2 Base Level Engineering
Current Plan=p01
Default Exp/Contr=0.3,0.1
English Units
Geom File=g01
Flow File=f01
Plan File=p01
Y Axis Title=Elevation
X Axis Title(PF)=Main Channel Distance
X Axis Title(XS)=Station
BEGIN DESCRIPTION:
COTTONWOOD CREEK SOUTH 2
END DESCRIPTION:
DSS Export Rating Curves= 0
DSS Export Rating Curve Sorted= 0
DSS Export Volume Flow Curves= 0
DXF OffsetX= 0
DXF OffsetY= 0
DXF ScaleX= 1
DXF ScaleY= 10

--- COTTONWOOD CREEK SOUTH 2.p01 (plan) ---

Plan Title=Multiple Run
Short Identifier=Multiple
Geom File=g01
Flow File=f01
Subcritical Flow
K Sum by GR= 0
Std Step Tol= 0.01
Critical Tol= 0.01
Num of Std Step Trials= 20
Max Error Tol= 0.3
Flow Tol Ratio= 0.001
Split Flow NTrial= 30
Split Flow Tol= 0.02
Split Flow Ratio= 0.02
Log Output Level= 0
Friction Slope Method= 1
Unsteady Friction Slope Method= 2
Unsteady Bridges Friction Slope Method= 1
Parabolic Critical Depth
Global Vel Dist=  1 , 1 , 1
Global Log Level= 0
CheckData=True
Encroach Param= -1, 0, 0, 0
BEGIN DESCRIPTION:
Multiple Run
END DESCRIPTION:

--- COTTONWOOD CREEK SOUTH 2.f01 (steady flow) ---

Flow Title=Multiple
Number of Profiles=7
Profile Names=10-year,25-year,50-year,1pct_min,100-year,1pct_plu,500-year
River Rch & RM= COTTONWOOD CREEK,Reach-1,34404
     380     590     771     488     975    1945    1540
River Rch & RM= COTTONWOOD CREEK,Reach-1,32052
     679    1087    1452     937    1870    3732    3072
River Rch & RM= COTTONWOOD CREEK,Reach-1,27064
    1115    1840    2507    1649    3290    6564    5611
River Rch & RM= COTTONWOOD CREEK,Reach-1,24793
    1407    2343    3211    2122    4235    8450    7299
River Rch & RM= COTTONWOOD CREEK,Reach-1,18563
    1505    2510    3444    2278    4546    9071    7848
River Rch & RM= COTTONWOOD CREEK,Reach-1,14326
    1983    3347    4627    3081    6148   12267   10758
River Rch & RM= COTTONWOOD CREEK,Reach-1,2757
    2053    3472    4808    3206    6397   12764   11226
Boundary for River Rch & Prof#=COTTONWOOD CREEK,Reach-1,1
Up Type=0
Dn Type=3
Dn Slope=0.005
Boundary for River Rch & Prof#=COTTONWOOD CREEK,Reach-1,2
Up Type=0
Dn Type=3
Dn Slope=0.005
Boundary for River Rch & Prof#=COTTONWOOD CREEK,Reach-1,3
Up Type=0
Dn Type=3
Dn Slope=0.005
Boundary for River Rch & Prof#=COTTONWOOD CREEK,Reach-1,4
Up Type=0
Dn Type=3
Dn Slope=0.005
Boundary for River Rch & Prof#=COTTONWOOD CREEK,Reach-1,5
Up Type=0
Dn Type=3
Dn Slope=0.005
Boundary for River Rch & Prof#=COTTONWOOD CREEK,Reach-1,6
Up Type=0
Dn Type=3
Dn Slope=0.005
Boundary for River Rch & Prof#=COTTONWOOD CREEK,Reach-1,7
Up Type=0
Dn Type=3
Dn Slope=0.005

--- COTTONWOOD CREEK SOUTH 2.g01 (geometry) ---

Geom Title=Existing Conditions
Program Version=4.10

River Reach=COTTONWOOD CREEK,Reach-1
Reach XY= 30
        2259975.       13747825.      2261308.36      13748907.4
      2262408.33     13750558.35      2263758.57     13751258.23
        2263975.       13752675.      2265372.69     13753869.17
      2266011.64     13753938.35      2266018.33     13753133.95
      2266919.03     13753127.14      2267094.79     13753995.49
       2268022.3     13754819.64      2268669.14     13754872.93
      2271058.73     13753192.21      2271069.23     13752126.46
      2272014.66     13752714.88      2271961.76     13753311.38
      2273116.86     13753868.94      2272861.79     13755011.37
      2273223.77     13755171.57      2273618.91     13754726.57
      2274208.96     13755474.83      2274677.47     13754630.45
      2275124.14     13755335.32      2274841.39     13755742.64
      2275621.66     13755676.72      2275288.47     13756338.71
      2275923.75     13756028.36      2275835.75     13756984.68
      2276275.09     13757217.71        2276575.       13756925.

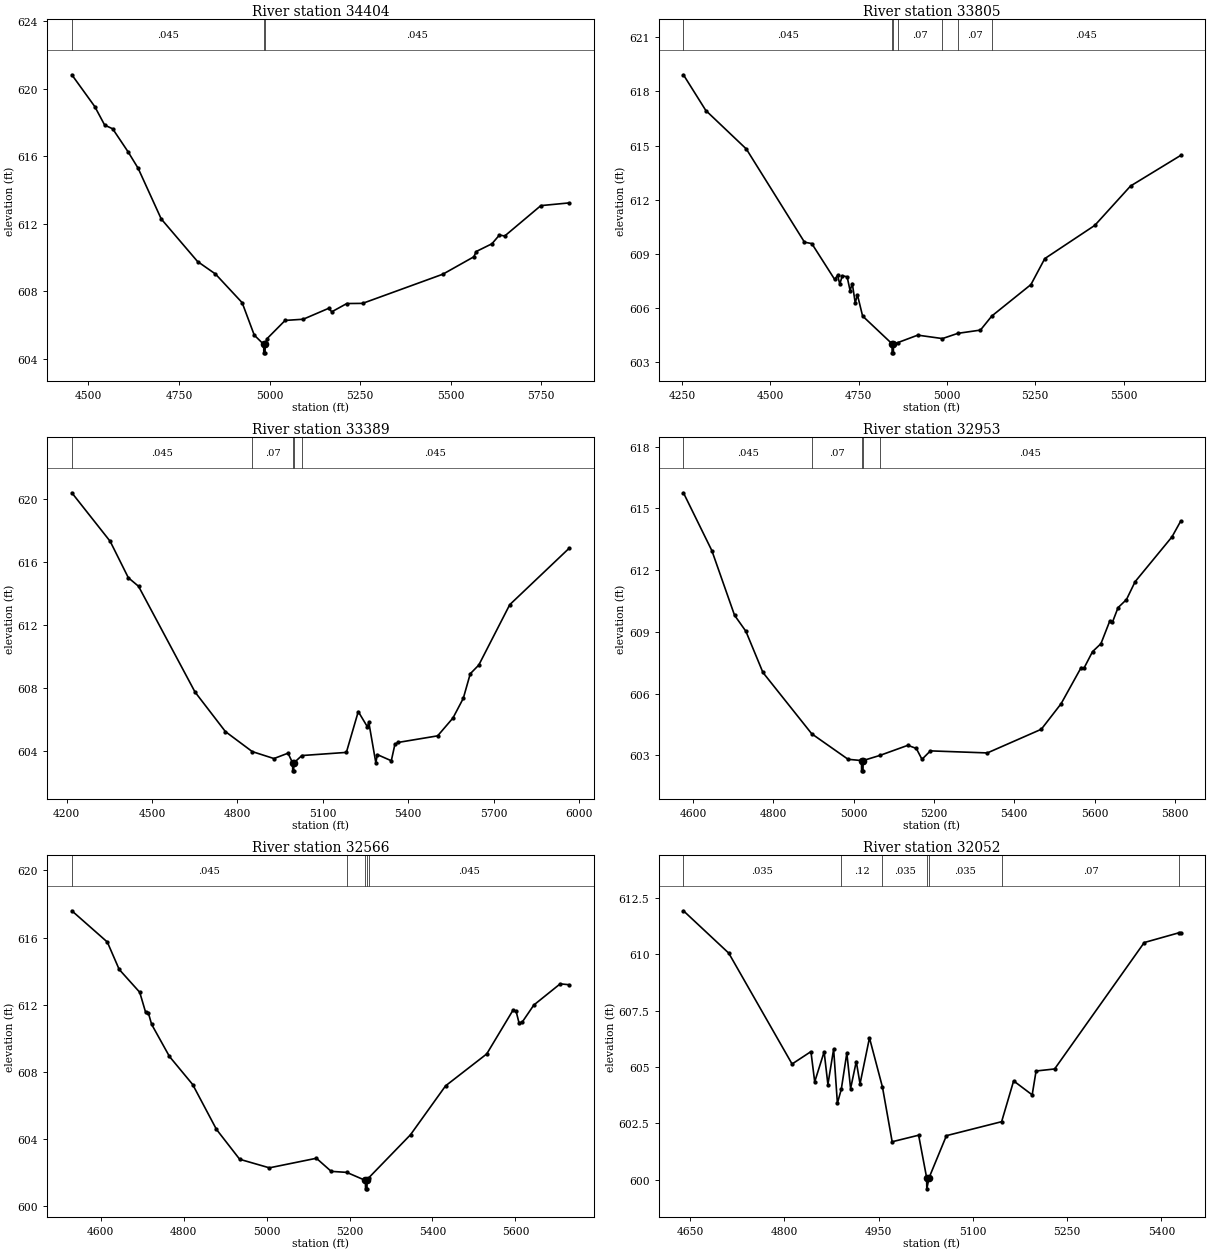
Type RM Length L Ch R = 1 ,34404   ,599,599,599
BEGIN DESCRIPTION:
COTTONWOOD CREEK SOUTH 2 59.0
END DESCRIPTION:
XS GIS Cut Line= 3
      2259655.46     13748273.82      2259954.84     13747917.03
      2260508.25     13747199.64
#Sta/Elev= 30
  4454.4  620.82  4517.6  618.94    4545  617.84  4567.1  617.62  4609.5  616.26
  4637.4  615.28  4701.1  612.28  4801.3  609.76  4850.7  609.02  4924.4  607.32
  4957.8   605.4  4983.9  604.85  4984.1  604.35  4987.6  604.35  4987.9  604.85
  4993.1  605.19    5043  606.27  5092.8  606.34  5163.4  606.99  5171.6  606.78
  5213.2  607.27  5256.7  607.28  5478.4  609.01  5563.8  610.04  5570.1  610.35
  5613.6  610.81  5634.4  611.33  5648.9  611.27  5748.6  613.07  5826.2  613.23
#Mann= 3 ,-1 , 0
  4454.4    .045       0  4983.9    .045       0  4987.9    .045       0
Bank Sta=4983.9,4987.9
XS Rating Curve= 0 ,0
Exp/Cntr=0.3,0.1

Type RM Length L Ch R = 1 ,33805   ,416,416,416
BEGIN DESCRIPTION:
COTTONWOOD CREEK SOUTH 2 58.0
END DESCRIPTION:
XS GIS Cut Line= 3
      2259925.02     13748524.99        2260525.       13748075.
        2260625.     13747425.03
#Sta/Elev= 30
  4253.8  618.92  4317.3  616.94  4431.9  614.81  4596.5  609.65  4617.3  609.57
  4681.9  607.59  4690.2  607.81  4696.5  607.33  4703.8  607.79  4717.3  607.73
  4725.7  606.97  4731.9  607.36  4740.2  606.29  4746.5  606.73  4761.1  605.56
  4844.5  604.02  4844.7  603.52  4848.2  603.52  4848.5  604.02  4861.3  604.09
  4917.3   604.5  4987.2  604.31  5030.9   604.6  5094.8  604.78    5127  605.56
  5237.7   607.3    5277  608.74  5418.6  610.58  5519.8  612.76  5661.4  614.45
#Mann= 7 ,-1 , 0
  4253.8    .045       0  4844.5    .045       0  4848.5    .045       0
  4861.3     .07       0  4987.2    .045       0  5030.9     .07       0
    5127    .045       0
Bank Sta=4844.5,4848.5
XS Rating Curve= 0 ,0
Exp/Cntr=0.3,0.1

Type RM Length L Ch R = 1 ,33389   ,436,436,436
BEGIN DESCRIPTION:
COTTONWOOD CREEK SOUTH 2 57.0
END DESCRIPTION:
XS GIS Cut Line= 3
      2260174.99     13748975.01        2260675.       13748375.
        2261575.       13748025.
#Sta/Elev= 30
  4218.3  620.37    4353  617.29  4416.8  614.98  4452.6  614.44  4651.1  607.73
  4757.9  605.22  4852.3  603.95  4928.4  603.51  4977.9  603.85  4994.1  603.23
  4994.3  602.73  4997.8  602.73  4998.1  603.23  5026.5   603.7  5182.9   603.9
  5224.7  606.49  5256.5  605.53  5261.8   605.8  5286.4  603.24  5291.7  603.76
  5340.8  603.37  5353.4  604.41  5364.1  604.53  5503.6  604.95  5557.3  606.08
  5593.7  607.33  5618.2  608.89  5648.1  609.44  5756.9  613.27    5965  616.84
#Mann= 5 ,-1 , 0
  4218.3    .045       0  4852.3     .07       0  4994.1     .05       0
  4998.1     .07       0  5026.5    .045       0
Bank Sta=4994.1,4998.1
XS Rating Curve= 0 ,0
Exp/Cntr=0.3,0.1

Type RM Length L Ch R = 1 ,32953   ,387,387,387
BEGIN DESCRIPTION:
COTTONWOOD CREEK SOUTH 2 56.0
END DESCRIPTION:
XS GIS Cut Line= 3
      2260524.97     13749025.03        2260825.       13748725.
      2261425.04     13748174.97
#Sta/Elev= 30
  4575.9  615.76  4646.7  612.95  4703.2  609.81  4731.5  609.03  4773.9  607.03
  4895.5  604.05  4986.1  602.81  5019.5  602.75  5019.7  602.25  5023.2  602.25
  5023.5  602.75  5065.4     603  5134.9  603.49  5155.9  603.34  5170.1  602.81
  5191.1  603.22  5332.9  603.12  5467.3  604.27  5516.6  605.51  5566.6  607.27
  5573.4  607.23  5594.9  608.04  5615.9  608.43  5637.5  609.51  5644.3  609.46
  5658.5  610.18  5679.4  610.57    5701  611.44  5792.9  613.62  5814.2  614.37
#Mann= 5 ,-1 , 0
  4575.9    .045       0  4895.5     .07       0  5019.5     .05       0
  5023.5     .07       0  5065.4    .045       0
Bank Sta=5019.5,5023.5
XS Rating Curve= 0 ,0
Exp/Cntr=0.3,0.1

Type RM Length L Ch R = 1 ,32566   ,514,514,514
BEGIN DESCRIPTION:
COTTONWOOD CREEK SOUTH 2 55.0
END DESCRIPTION:
XS GIS Cut Line= 3
      2260795.55     13749335.99      2261140.04     13748921.78
      2261624.97     13748475.03
#Sta/Elev= 30
  4530.8   617.6  4616.3  615.74  4644.9  614.11  4694.4  612.75  4708.7  611.55
  4715.2  611.52  4723.1  610.84    4766  608.93    4822  607.26  4879.3  604.59
  4935.3  602.81  5006.9   602.3  5120.2  602.87  5155.9  602.09  5193.3  602.03
  5238.4  601.55  5238.6  601.05  5242.1  601.05  5242.4  601.55  5246.9  601.72
    5347  604.27  5431.5  607.18  5530.7  609.08  5594.2  611.69  5601.6  611.61
  5608.4  610.94  5615.8  610.96  5644.2  611.99  5707.7  613.25  5728.9   613.2
#Mann= 5 ,-1 , 0
  4530.8    .045       0  5193.3     .07       0  5238.4    .045       0
  5242.4     .07       0  5246.9    .045       0
Bank Sta=5238.4,5242.4
XS Rating Curve= 0 ,0
Exp/Cntr=0.3,0.1

Type RM Length L Ch R = 1 ,32052   ,469,469,469
BEGIN DESCRIPTION:
COTTONWOOD CREEK SOUTH 2 54.0
END DESCRIPTION:
XS GIS Cut Line= 3
        2261225.     13749424.99        2261425.       13749125.
      2261675.02     13748774.97
#Sta/Elev= 30
  4639.7  611.93  4711.8  610.05  4812.5  605.13  4842.5  605.68  4848.5  604.34
  4863.5  605.67  4869.5  604.22  4878.6  605.79  4884.6  603.39  4890.8  604.01
  4899.6  605.62  4905.6  604.04  4914.6  605.24  4920.6  604.25  4935.6  606.29
  4956.3   604.1  4971.7  601.68  5013.8  601.97  5026.5  600.09  5026.8  599.59
  5030.5  600.09    5058  601.95  5145.8  602.57  5164.9  604.38  5194.4  603.76
  5200.6  604.82  5230.1  604.91  5372.6  610.52  5428.7  610.96  5430.4  610.96
#Mann= 7 ,-1 , 0
  4639.7    .035       0  4890.8     .12       0  4956.3    .035       0
  5026.5    .035       0  5030.5    .035       0  5145.8     .07       0
  5428.7    .045       0
Bank Sta=5026.5,5030.5
XS Rating Curve= 0 ,0
Exp/Cntr=0.3,0.1

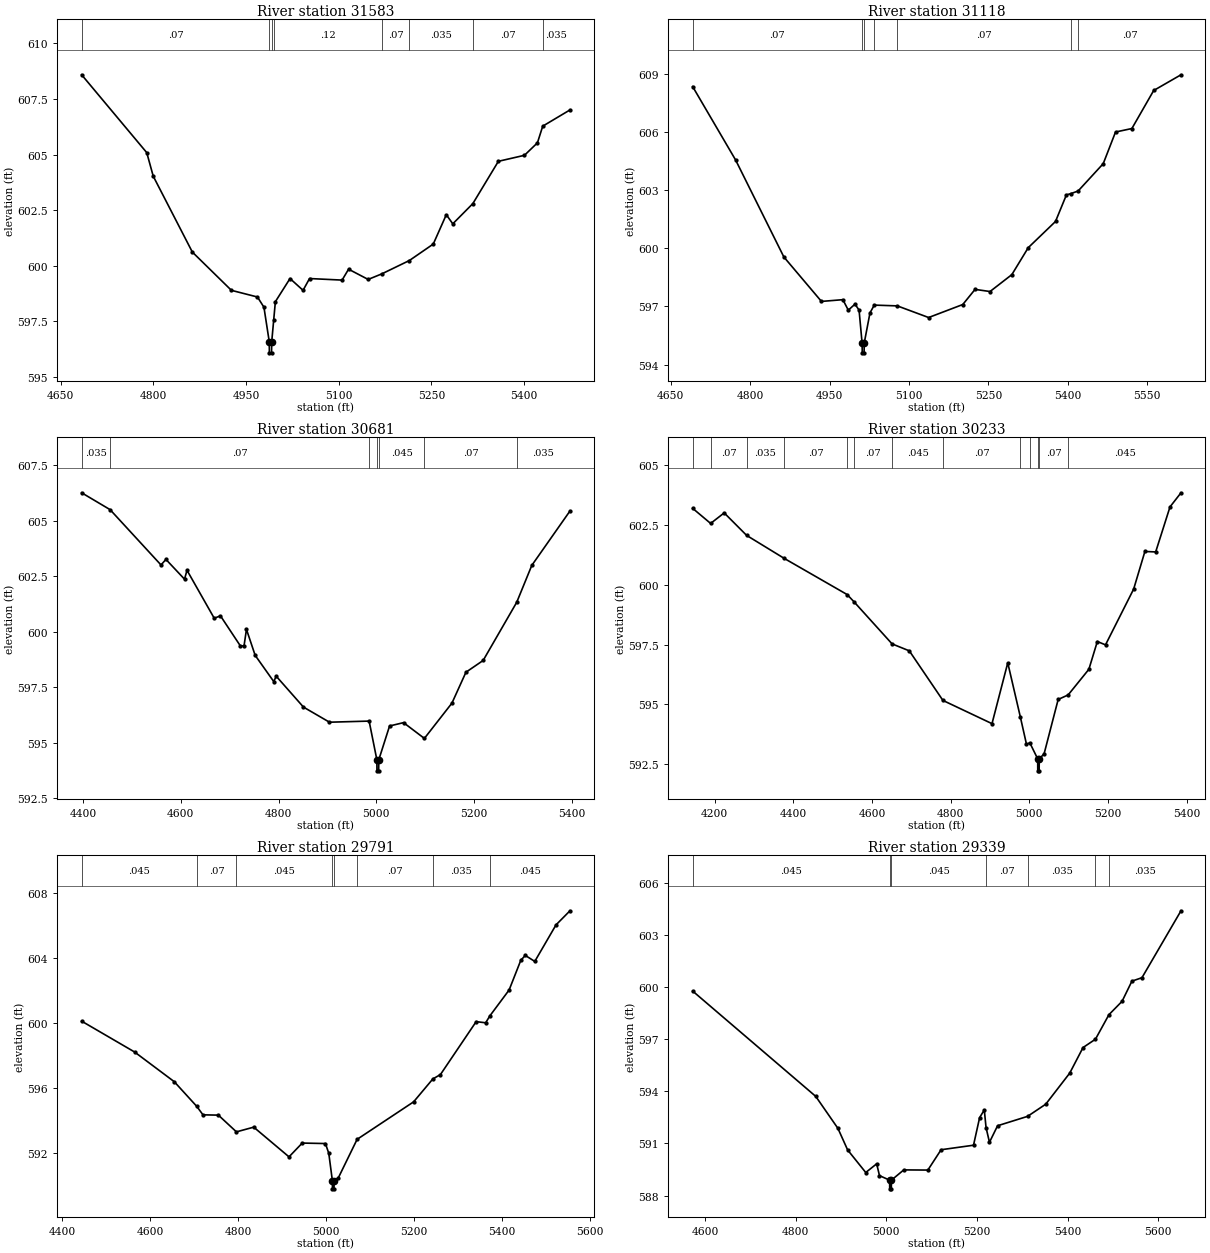
Type RM Length L Ch R = 1 ,31583   ,465,465,465
BEGIN DESCRIPTION:
COTTONWOOD CREEK SOUTH 2 53.0
END DESCRIPTION:
XS GIS Cut Line= 3
      2261425.03     13749574.99        2261725.       13749475.
      2261874.99     13749025.04
#Sta/Elev= 30
  4683.8  608.59  4789.2  605.09  4799.7  604.03    4863  600.62  4926.2   598.9
  4968.4   598.6  4978.9  598.14  4987.5  596.59  4987.7  596.09  4991.2  596.09
  4991.5  596.59  4994.7  597.57  4997.4  598.39  5021.1  599.43  5042.2   598.9
  5052.7  599.43  5105.4  599.36  5115.9  599.85  5147.6  599.39  5169.7  599.64
  5214.3  600.24    5253  600.98  5274.1   602.3  5284.6  601.89  5317.1   602.8
  5358.4   604.7  5400.6  604.97  5421.6  605.53  5430.2  606.28  5474.3  607.01
#Mann= 8 ,-1 , 0
  4683.8     .07       0  4987.5     .05       0  4991.5     .07       0
  4994.7     .12       0  5169.7     .07       0  5214.3    .035       0
  5317.1     .07       0  5430.2    .035       0
Bank Sta=4987.5,4991.5
XS Rating Curve= 0 ,0
Exp/Cntr=0.3,0.1

Type RM Length L Ch R = 1 ,31118   ,437,437,437
BEGIN DESCRIPTION:
COTTONWOOD CREEK SOUTH 2 52.0
END DESCRIPTION:
XS GIS Cut Line= 3
      2261625.03     13749924.99        2261925.       13749875.
      2262525.03     13749724.99
#Sta/Elev= 30
  4691.3  608.33  4772.4  604.55  4863.6  599.55  4934.6  597.26  4975.1  597.35
  4985.3  596.81    4998  597.12  5005.7  596.81  5011.4  595.11  5011.7  594.61
  5015.2  594.61  5015.4  595.11  5026.3  596.67  5034.4  597.07  5077.9  597.03
  5137.1  596.43  5201.6   597.1  5224.8  597.88  5253.1  597.77  5294.3  598.64
  5325.3  600.03  5376.8  601.38  5397.4  602.75  5406.3  602.82  5419.5  602.95
    5467  604.36  5490.2  605.99  5521.1  606.17  5562.3  608.13  5613.9  608.94
#Mann= 7 ,-1 , 0
  4691.3     .07       0  5011.4     .05       0  5015.4     .07       0
  5034.4     .12       0  5077.9     .07       0  5406.3    .035       0
  5419.5     .07       0
Bank Sta=5011.4,5015.4
XS Rating Curve= 0 ,0
Exp/Cntr=0.3,0.1

Type RM Length L Ch R = 1 ,30681   ,448,448,448
BEGIN DESCRIPTION:
COTTONWOOD CREEK SOUTH 2 51.0
END DESCRIPTION:
XS GIS Cut Line= 3
      2261574.95     13750124.99        2262175.       13750225.
      2262474.97     13749975.02
#Sta/Elev= 30
  4397.2  606.25  4455.4  605.49  4559.5     603  4569.6  603.25  4607.6  602.36
  4612.7  602.76  4668.4   600.6  4681.1  600.71  4721.7  599.36  4729.3  599.35
  4734.3   600.1  4752.1  598.93  4790.1  597.75  4795.2  597.99  4850.9   596.6
  4904.1  595.92  4985.2  595.97    5001  594.23  5001.2  593.73  5004.7  593.73
    5005  594.23    5027  595.75  5055.6   595.9  5098.2  595.19  5154.6  596.78
  5183.2  598.17  5218.4   598.7  5287.1  601.32  5317.9  602.98    5396  605.43
#Mann= 7 ,-1 , 0
  4397.2    .035       0  4455.4     .07       0  4985.2    .045       0
    5001    .045       0    5005    .045       0  5098.2     .07       0
  5287.1    .035       0
Bank Sta=5001,5005
XS Rating Curve= 0 ,0
Exp/Cntr=0.3,0.1

Type RM Length L Ch R = 1 ,30233   ,442,442,442
BEGIN DESCRIPTION:
COTTONWOOD CREEK SOUTH 2 50.0
END DESCRIPTION:
XS GIS Cut Line= 3
      2261574.99       13750525.        2262425.       13750575.
        2262675.       13750275.
#Sta/Elev= 30
  4143.9  603.19  4189.6  602.56  4224.1     603  4281.2  602.06  4376.8   601.1
  4536.8  599.59  4553.6   599.3  4651.1  597.53  4694.9  597.24  4780.4  595.17
  4905.2   594.2  4945.3  596.74  4977.3  594.48  4992.9  593.34  5001.4   593.4
  5021.4  592.73  5021.6  592.23  5025.1  592.23  5025.4  592.73  5037.7  592.94
  5073.5  595.21  5098.9   595.4  5151.6  596.47  5173.1  597.63  5193.9  597.49
  5265.5  599.82  5294.1  601.39  5321.5  601.37  5357.9  603.25  5385.9  603.84
#Mann= 13 ,-1 , 0
  4143.9    .035       0  4189.6     .07       0  4281.2    .035       0
  4376.8     .07       0  4536.8    .045       0  4553.6     .07       0
  4651.1    .045       0  4780.4     .07       0  4977.3    .045       0
  5001.4     .07       0  5021.4    .045       0  5025.4     .07       0
  5098.9    .045       0
Bank Sta=5021.4,5025.4
XS Rating Curve= 0 ,0
Exp/Cntr=0.3,0.1

Type RM Length L Ch R = 1 ,29791   ,452,452,452
BEGIN DESCRIPTION:
COTTONWOOD CREEK SOUTH 2 49.0
END DESCRIPTION:
XS GIS Cut Line= 3
        2262825.     13751374.97        2262775.       13750825.
      2262875.01     13750274.95
#Sta/Elev= 30
  4443.7   600.1  4564.2   598.2  4654.5  596.37  4705.7  594.85  4719.8  594.33
  4754.9  594.31  4795.9  593.28  4835.3  593.57  4915.6  591.74  4945.7  592.59
  4998.5  592.56  5006.1  591.96  5014.3  590.27  5014.5  589.77    5018  589.77
  5018.3  590.27  5027.7  590.44  5070.6  592.82  5199.2  595.13  5242.9  596.54
  5260.2  596.81  5341.5  600.07  5363.1     600  5372.8  600.43  5416.5  602.02
  5443.1  603.85  5453.3  604.15  5474.9  603.78  5523.2  606.03    5555   606.9
#Mann= 8 ,-1 , 0
  4443.7    .045       0  4705.7     .07       0  4795.9    .045       0
  5014.3    .045       0  5018.3    .045       0  5070.6     .07       0
  5242.9    .035       0  5372.8    .045       0
Bank Sta=5014.3,5018.3
XS Rating Curve= 0 ,0
Exp/Cntr=0.3,0.1

Type RM Length L Ch R = 1 ,29339   ,448,448,448
BEGIN DESCRIPTION:
COTTONWOOD CREEK SOUTH 2 48.0
END DESCRIPTION:
XS GIS Cut Line= 3
        2263025.     13751375.01        2263175.       13750975.
      2262925.01     13750375.01
#Sta/Elev= 30
  4572.8  599.77  4844.3  593.71  4893.2  591.87  4914.6  590.63  4954.6  589.33
  4978.7  589.83  4984.9  589.15  5007.2  588.89  5007.5  588.39    5011  588.39
  5011.2  588.89  5038.5  589.48  5091.6  589.47  5120.8  590.64  5192.3   590.9
  5205.8  592.49  5216.1  592.93    5220  591.91  5227.5  591.07  5245.4  592.02
  5311.5  592.56  5351.6  593.26  5404.6  595.05  5433.9  596.52  5461.3     597
    5491  598.41    5520  599.18  5541.7  600.34  5563.9  600.54    5650  604.39
#Mann= 7 ,-1 , 0
  4572.8    .045       0  5007.2    .045       0  5011.2    .045       0
    5220     .07       0  5311.5    .035       0  5461.3    .045       0
    5491    .035       0
Bank Sta=5007.2,5011.2
XS Rating Curve= 0 ,0
Exp/Cntr=0.3,0.1

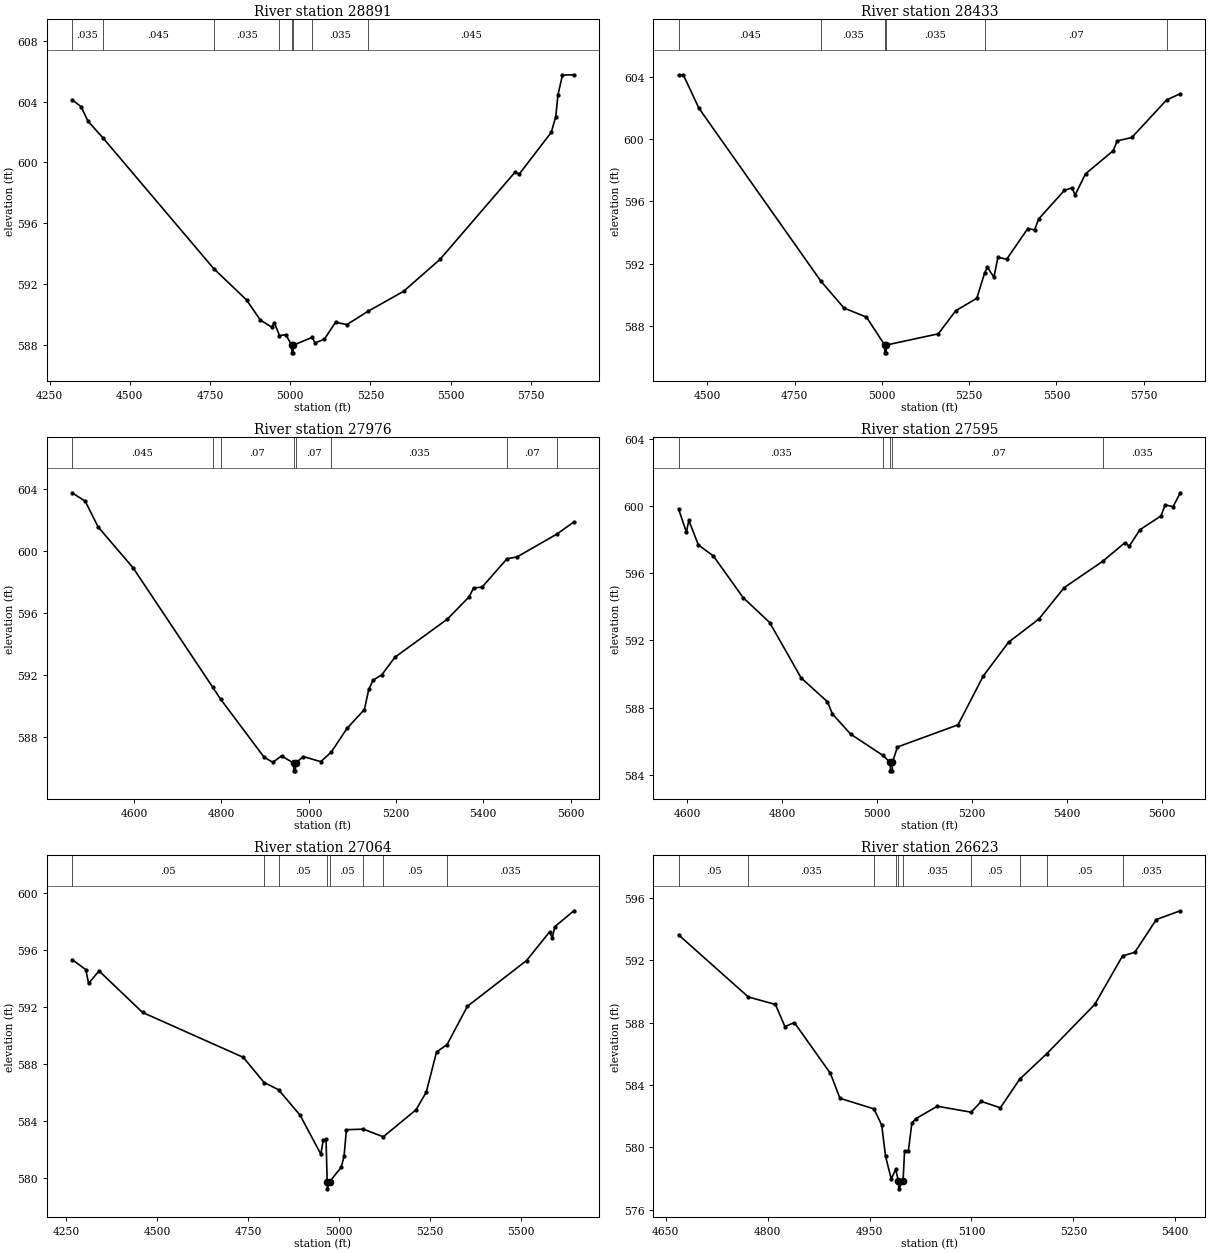
Type RM Length L Ch R = 1 ,28891   ,458,458,458
BEGIN DESCRIPTION:
COTTONWOOD CREEK SOUTH 2 47.0
END DESCRIPTION:
XS GIS Cut Line= 3
        2263175.       13751675.        2263575.       13751125.
      2264175.02     13750474.98
#Sta/Elev= 30
  4319.9  604.12  4348.1  603.66  4369.4  602.71  4415.8  601.62  4761.6  593.01
    4864  590.95  4906.9  589.63  4942.4  589.16  4950.5  589.45  4966.6  588.61
  4986.5  588.66  5004.9  587.97  5005.2  587.47  5008.9  587.47  5009.2  587.97
  5067.9  588.48  5077.9  588.13  5106.3  588.36  5141.5  589.48  5176.9  589.33
  5243.4  590.21  5353.8  591.52  5466.9  593.61  5700.6  599.34  5714.7  599.24
    5814  601.97  5828.1     603    5835  604.44  5849.1  605.74  5884.6  605.76
#Mann= 8 ,-1 , 0
  4319.9    .035       0  4415.8    .045       0  4761.6    .035       0
  4966.6    .045       0  5004.9    .045       0  5009.2    .045       0
  5067.9    .035       0  5243.4    .045       0
Bank Sta=5004.9,5009.2
XS Rating Curve= 0 ,0
Exp/Cntr=0.3,0.1

Type RM Length L Ch R = 1 ,28433   ,457,457,457
BEGIN DESCRIPTION:
COTTONWOOD CREEK SOUTH 2 46.0
END DESCRIPTION:
XS GIS Cut Line= 3
      2263275.02     13751774.99        2263775.       13751475.
      2264575.02     13751775.01
#Sta/Elev= 30
  4417.4   604.1    4431  604.12  4475.7  601.98  4825.4  590.88  4891.6  589.16
  4955.8  588.58  5008.1  586.79  5008.4  586.29  5012.2  586.29  5012.4  586.79
  5161.6  587.51  5211.4  588.99  5271.9  589.79    5294  591.39  5302.2  591.78
  5320.9  591.14  5332.4  592.42  5357.4  592.29  5417.9  594.26  5437.5  594.17
    5449  594.87  5522.9  596.71  5545.2  596.88  5553.2   596.4  5583.4  597.77
  5662.6  599.25  5674.2  599.88    5716   600.1  5815.3   602.5  5854.9  602.91
#Mann= 6 ,-1 , 0
  4417.4    .045       0  4825.4    .035       0  5008.1    .035       0
  5012.4    .035       0    5294     .07       0  5815.3    .035       0
Bank Sta=5008.1,5012.4
XS Rating Curve= 0 ,0
Exp/Cntr=0.3,0.1

Type RM Length L Ch R = 1 ,27976   ,381,381,381
BEGIN DESCRIPTION:
COTTONWOOD CREEK SOUTH 2 45.0
END DESCRIPTION:
XS GIS Cut Line= 3
      2263325.04       13751875.        2263875.       13751875.
      2264475.04       13751875.
#Sta/Elev= 30
  4457.6  603.76  4487.6  603.22  4517.6  601.55  4597.6  598.92  4779.8  591.24
  4798.2  590.46  4897.6  586.73  4917.6   586.4  4937.6  586.81  4965.3  586.35
  4965.6  585.85  4969.5  585.85  4969.9  586.35  4987.6  586.77  5027.6  586.44
  5051.7  587.06  5087.6  588.58  5127.6   589.8  5137.6   591.1  5147.6  591.69
  5167.6  592.04  5197.6  593.17  5317.6  595.62  5367.6  597.06  5377.6  597.62
  5397.6  597.69  5454.3  599.51  5477.6  599.63  5568.7   601.1  5607.6  601.88
#Mann= 8 ,-1 , 0
  4457.6    .045       0  4779.8    .035       0  4798.2     .07       0
  4965.3     .05       0  4969.9     .07       0  5051.7    .035       0
  5454.3     .07       0  5568.7    .035       0
Bank Sta=4965.3,4969.9
XS Rating Curve= 0 ,0
Exp/Cntr=0.3,0.1

Type RM Length L Ch R = 1 ,27595   ,531,531,531
BEGIN DESCRIPTION:
COTTONWOOD CREEK SOUTH 2 44.0
END DESCRIPTION:
XS GIS Cut Line= 3
      2263424.96     13752124.99      2263818.01     13752243.62
      2264424.98     13752025.01
#Sta/Elev= 30
  4582.2  599.83  4598.7  598.45  4603.9  599.14    4624  597.68  4655.4  597.03
    4718  594.55    4774  593.06    4840  589.77  4895.6  588.34  4905.9  587.62
  4944.1  586.42  5012.1  585.15  5027.6  584.73  5027.9  584.23  5031.8  584.23
  5032.2  584.73  5042.7  585.65  5170.2  586.97  5223.4  589.88  5276.5  591.89
  5340.3  593.27  5393.5  595.14  5474.6  596.71    5521  597.81  5530.5  597.61
  5552.9  598.59  5597.2  599.41    5606  600.07  5622.6  599.96  5637.9  600.79
#Mann= 5 ,-1 , 0
  4582.2    .035       0  5012.1     .07       0  5027.6    .035       0
  5032.2     .07       0  5474.6    .035       0
Bank Sta=5027.6,5032.2
XS Rating Curve= 0 ,0
Exp/Cntr=0.3,0.1

Type RM Length L Ch R = 1 ,27064   ,441,441,441
BEGIN DESCRIPTION:
COTTONWOOD CREEK SOUTH 2 43.0
END DESCRIPTION:
XS GIS Cut Line= 3
      2263539.16     13753272.96      2264039.47     13752674.23
      2264457.78     13752243.61
#Sta/Elev= 30
  4265.9  595.35  4303.6  594.64  4311.4  593.67  4340.1  594.55  4459.8  591.63
    4737  588.47  4794.3   586.7  4834.1  586.19  4893.2   584.4  4950.4  581.66
  4956.9  582.65  4964.7   582.7  4967.8  579.72  4968.3  579.22  4974.6  579.72
  5006.4  580.74  5014.2   581.5  5020.7  583.38  5067.3  583.42  5122.1  582.88
  5212.3  584.78  5240.4  586.02  5268.7  588.85  5297.5  589.36  5353.5  592.06
  5516.3  595.28  5579.9   597.3  5587.1  596.86    5594  597.66  5646.5  598.78
#Mann= 8 ,-1 , 0
  4265.9     .05       0  4794.3     .07       0  4834.1     .05       0
  4967.8     .05       0  4974.6     .05       0  5067.3     .07       0
  5122.1     .05       0  5297.5    .035       0
Bank Sta=4967.8,4974.6
XS Rating Curve= 0 ,0
Exp/Cntr=0.3,0.1

Type RM Length L Ch R = 1 ,26623   ,378,378,378
BEGIN DESCRIPTION:
COTTONWOOD CREEK SOUTH 2 42.0
END DESCRIPTION:
XS GIS Cut Line= 3
      2264174.98     13753275.04        2264325.       13752975.
      2264525.02     13752624.97
#Sta/Elev= 30
  4668.9  593.62  4771.6  589.64  4811.5  589.16  4825.5  587.74  4839.4     588
  4892.5  584.74  4906.5  583.15  4956.6  582.47    4968  581.42  4973.6  579.44
    4982  577.98  4988.5   578.6  4992.6  577.85  4993.1  577.35  4999.4  577.85
  5001.6  579.78  5007.2  579.78  5012.3  581.55    5018  581.84  5049.7  582.64
  5099.5  582.26  5114.5  582.95  5142.6  582.54    5171  584.37    5211  586.01
  5281.5  589.16  5322.5  592.27  5340.5   592.5  5372.2   594.6  5407.5  595.16
#Mann= 10 ,-1 , 0
  4668.9     .05       0  4771.6    .035       0  4956.6     .05       0
  4988.5    .035       0  4992.6    .035       0  4999.4    .035       0
  5099.5     .05       0    5171     .07       0    5211     .05       0
  5322.5    .035       0
Bank Sta=4992.6,4999.4
XS Rating Curve= 0 ,0
Exp/Cntr=0.3,0.1

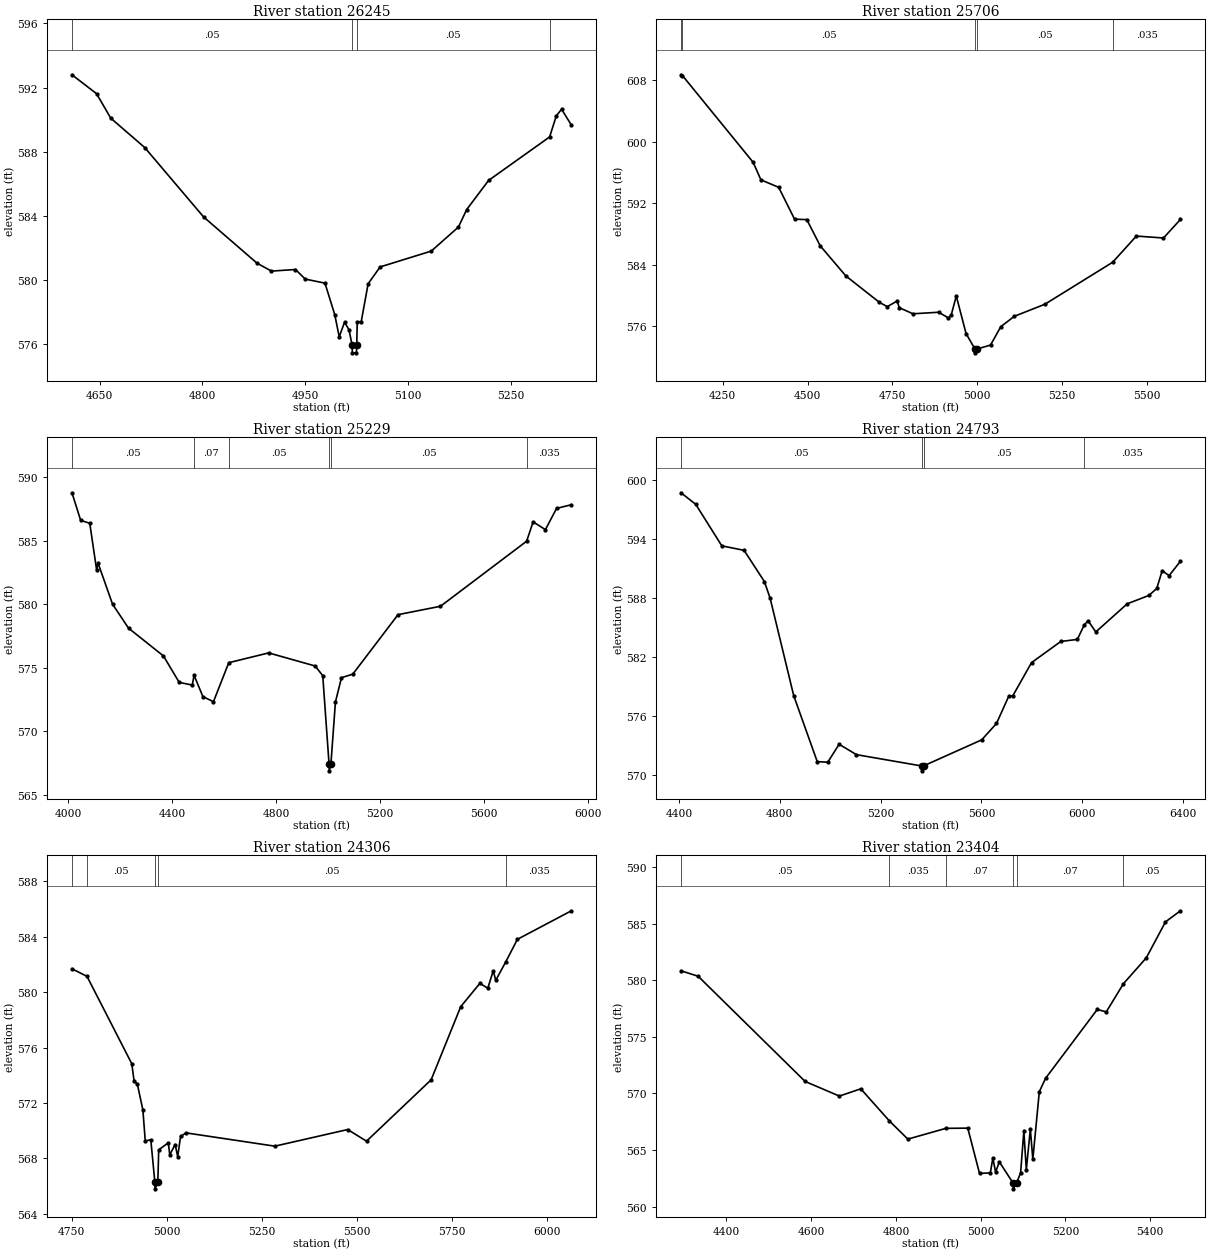
Type RM Length L Ch R = 1 ,26245   ,539,539,539
BEGIN DESCRIPTION:
COTTONWOOD CREEK SOUTH 2 41.0
END DESCRIPTION:
XS GIS Cut Line= 3
      2264324.97     13753425.03      2264646.42     13753158.15
      2264775.01     13752874.98
#Sta/Elev= 30
  4609.6   592.8  4645.5  591.62  4666.3  590.09  4715.8  588.26  4801.7  583.93
  4879.8  581.04  4900.7  580.55  4935.8  580.65  4950.1  580.05  4978.8   579.8
  4993.1  577.83  4999.6  576.45  5007.4  577.36  5013.9  576.89  5018.3  575.95
  5018.8  575.45  5024.7  575.45  5025.2  575.95  5025.9  577.39  5031.7  577.39
  5041.8  579.76  5059.3  580.81    5134   581.8  5173.6   583.3  5185.6  584.39
  5217.6  586.21  5306.6  588.92  5316.4  590.24  5324.1  590.65  5338.4  589.66
#Mann= 4 ,-1 , 0
  4609.6     .05       0  5018.3     .05       0  5025.2     .05       0
  5306.6    .035       0
Bank Sta=5018.3,5025.2
XS Rating Curve= 0 ,0
Exp/Cntr=0.3,0.1

Type RM Length L Ch R = 1 ,25706   ,477,477,477
BEGIN DESCRIPTION:
COTTONWOOD CREEK SOUTH 2 40.0
END DESCRIPTION:
XS GIS Cut Line= 3
        2264225.       13753875.        2265025.       13753525.
        2265025.     13752925.01
#Sta/Elev= 30
  4126.8  608.71  4131.2   608.6  4339.3  597.34  4362.6  595.04  4414.9  594.07
  4461.7  589.93  4497.9  589.87  4537.3  586.47  4612.9  582.55  4711.9  579.11
  4735.3  578.55  4764.2  579.28  4770.8  578.41  4810.9  577.62  4886.6  577.82
  4915.4  577.09  4923.6  577.42  4938.8  579.93  4967.7  575.04  4993.8  573.04
  4994.3  572.54  5000.7  573.04    5040  573.56    5070  575.94    5110  577.29
    5200  578.86    5400  584.32    5470  587.73    5550  587.48    5600  589.89
#Mann= 5 ,-1 , 0
  4126.8    .035       0  4131.2     .05       0  4993.8     .05       0
  5000.7     .05       0    5400    .035       0
Bank Sta=4993.8,5000.7
XS Rating Curve= 0 ,0
Exp/Cntr=0.3,0.1

Type RM Length L Ch R = 1 ,25229   ,436,436,436
BEGIN DESCRIPTION:
X18640
END DESCRIPTION:
XS GIS Cut Line= 4
      2264437.27     13754105.49      2265265.68     13753970.15
      2265388.71     13753785.61      2265077.03     13752981.81
#Sta/Elev= 30
  4013.6  588.77  4047.2   586.6  4082.2  586.37  4108.6   582.7  4113.7  583.26
    4170     580  4231.4  578.12  4365.9  575.93  4426.7  573.85  4477.1  573.64
  4483.8  574.41  4517.9  572.73  4558.5  572.33  4617.5   575.4  4771.2  576.17
  4950.1  575.14  4979.4  574.38  5003.8  567.39  5004.3  566.89  5010.7  567.39
  5028.2   572.3  5051.5  574.22  5095.2   574.5  5269.3  579.18  5432.8  579.84
  5764.6  584.96  5789.5  586.48  5836.9  585.87  5879.8  587.54  5936.9  587.83
#Mann= 6 ,-1 , 0
  4013.6     .05       0  4483.8     .07       0  4617.5     .05       0
  5003.8     .05       0  5010.7     .05       0  5764.6    .035       0
Bank Sta=5003.8,5010.7
XS Rating Curve= 0 ,0
Exp/Cntr=0.3,0.1

Type RM Length L Ch R = 1 ,24793   ,487,487,487
BEGIN DESCRIPTION:
COTTONWOOD CREEK SOUTH 2 39.0
END DESCRIPTION:
XS GIS Cut Line= 3
      2265786.51       13754614.        2265725.       13754025.
      2265024.98     13752824.96
#Sta/Elev= 30
  4408.2  598.73  4466.7  597.55  4570.1  593.32  4658.5  592.86    4739  589.68
  4761.9  587.97  4855.3  578.05  4948.7  571.32  4990.4  571.26  5035.6  573.09
  5104.2  572.03  5362.4  570.88  5362.9  570.38  5370.3  570.88  5601.2  573.54
  5659.9  575.21  5708.7     578  5724.4  578.02  5798.8  581.41    5915  583.57
  5980.7  583.78  6008.4  585.28  6023.7  585.67  6053.9  584.54  6178.4  587.41
  6264.4  588.26  6295.8  588.98  6317.3  590.79  6344.6  590.28  6389.7  591.75
#Mann= 4 ,-1 , 0
  4408.2     .05       0  5362.4     .05       0  5370.3     .05       0
  6008.4    .035       0
Bank Sta=5362.4,5370.3
XS Rating Curve= 0 ,0
Exp/Cntr=0.3,0.1

Type RM Length L Ch R = 1 ,24306   ,902,902,902
BEGIN DESCRIPTION:
COTTONWOOD CREEK SOUTH 2 38.0
END DESCRIPTION:
XS GIS Cut Line= 3
        2266175.       13753975.        2266025.       13753775.
      2265225.01     13753075.01
#Sta/Elev= 30
  4750.7  581.69  4790.2  581.15    4908  574.84  4914.2  573.57  4922.6  573.37
  4937.2   571.5  4943.4  569.27    4958  569.35  4968.6  566.31  4969.1  565.81
  4976.5  566.31  4978.8  568.63    5004  569.13  5007.8  568.27  5022.1  569.01
  5028.7  568.14  5036.3  569.59  5050.5  569.85    5284  568.89  5475.7  570.09
  5525.1  569.25    5695  573.68  5772.8  578.96  5823.1  580.64    5844  580.29
  5858.2  581.55  5864.9  580.86  5890.9  582.18  5921.8  583.82  6063.7  585.88
#Mann= 5 ,-1 , 0
  4750.7    .035       0  4790.2     .05       0  4968.6     .05       0
  4976.5     .05       0  5890.9    .035       0
Bank Sta=4968.6,4976.5
XS Rating Curve= 0 ,0
Exp/Cntr=0.3,0.1

Type RM Length L Ch R = 1 ,23404   ,429,429,429
BEGIN DESCRIPTION:
COTTONWOOD CREEK SOUTH 2 37.0
END DESCRIPTION:
XS GIS Cut Line= 3
      2266225.01     13753925.04        2266125.       13753225.
      2265875.03     13752825.04
#Sta/Elev= 30
  4292.7  580.83  4333.1  580.35  4585.7  571.06  4666.5  569.77    4717  570.41
  4784.7  567.57  4828.1  565.97  4917.8  566.92  4969.5  566.94  4997.3  562.94
  5022.8  562.99  5028.7  564.29  5035.2  563.07  5044.1  563.96  5076.6  562.08
  5077.1  561.58  5084.6  562.08  5094.2  562.99  5101.9  566.67  5107.7  563.27
  5117.2  566.84  5123.1  564.19  5138.4  570.16  5153.2  571.34  5275.2  577.42
  5296.4   577.2  5336.9  579.69  5390.8  581.97  5436.2  585.15  5471.5  586.13
#Mann= 6 ,-1 , 0
  4292.7     .05       0  4784.7    .035       0  4917.8     .07       0
  5076.6     .05       0  5084.6     .07       0  5336.9     .05       0
Bank Sta=5076.6,5084.6
XS Rating Curve= 0 ,0
Exp/Cntr=0.3,0.1

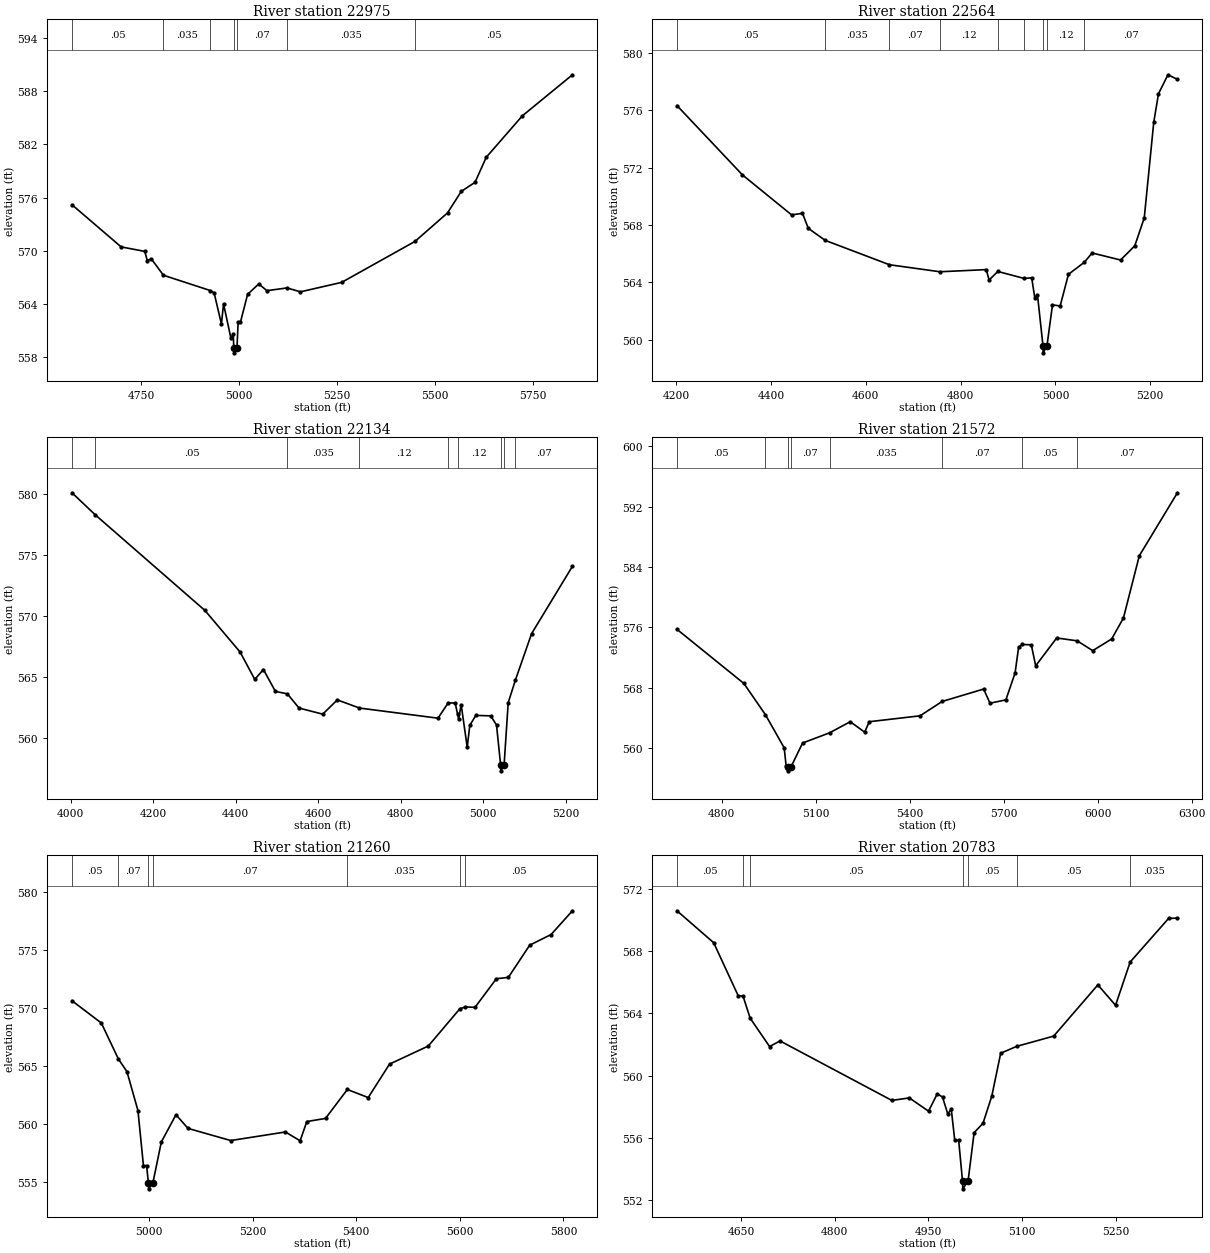
Type RM Length L Ch R = 1 ,22975   ,411,411,411
BEGIN DESCRIPTION:
COTTONWOOD CREEK SOUTH 2 36.0
END DESCRIPTION:
XS GIS Cut Line= 3
      2266324.99     13753725.02        2266475.       13753325.
      2265924.99     13752674.99
#Sta/Elev= 30
  4572.9   575.2  4698.4  570.45  4758.9  569.94  4765.2  568.91  4775.8  569.09
  4806.5  567.25  4926.7  565.52    4936  565.27  4954.7  561.75  4960.1  564.02
  4978.8  560.18    4985  560.62  4986.3     559  4986.8   558.5  4994.4     559
  4997.4  561.97  5003.4  561.97  5021.6   565.1  5050.1  566.27    5071  565.51
  5122.1  565.82  5156.7  565.38  5262.1  566.45  5449.4  571.07  5532.4  574.28
  5567.6  576.71  5602.7  577.73  5631.3  580.55  5723.6  585.23  5851.6  589.86
#Mann= 7 ,-1 , 0
  4572.9     .05       0  4806.5    .035       0  4926.7     .07       0
  4986.3     .05       0  4994.4     .07       0  5122.1    .035       0
  5449.4     .05       0
Bank Sta=4986.3,4994.4
XS Rating Curve= 0 ,0
Exp/Cntr=0.3,0.1

Type RM Length L Ch R = 1 ,22564   ,430,430,430
BEGIN DESCRIPTION:
COTTONWOOD CREEK SOUTH 2 35.0
END DESCRIPTION:
XS GIS Cut Line= 3
      2266424.98     13753825.03        2266825.       13753125.
        2266825.     13752874.96
#Sta/Elev= 30
  4201.3  576.33  4339.5  571.49  4443.2   568.7  4466.2  568.81  4478.5  567.76
  4514.2  566.92  4649.8  565.22  4756.3  564.73  4854.2  564.88    4860  564.15
  4878.5  564.75  4934.5  564.26    4950  564.31  4956.5  562.92  4962.2  563.12
  4973.8  559.57  4974.3  559.07  4982.3  559.57  4993.9  562.42  5010.1  562.34
  5027.6  564.55  5061.1  565.39  5077.6  566.04  5137.6  565.55  5167.6  566.54
  5187.6  568.49  5207.6  575.15  5217.6  577.15  5237.6  578.48  5257.6  578.16
#Mann= 9 ,-1 , 0
  4201.3     .05       0  4514.2    .035       0  4649.8     .07       0
  4756.3     .12       0  4878.5     .07       0  4934.5     .12       0
  4973.8     .05       0  4982.3     .12       0  5061.1     .07       0
Bank Sta=4973.8,4982.3
XS Rating Curve= 0 ,0
Exp/Cntr=0.3,0.1

Type RM Length L Ch R = 1 ,22134   ,562,562,562
BEGIN DESCRIPTION:
COTTONWOOD CREEK SOUTH 2 34.0
END DESCRIPTION:
XS GIS Cut Line= 3
      2266374.97     13753925.02        2267175.       13753325.
      2267325.02     13753174.98
#Sta/Elev= 30
  4003.6  580.11  4060.3  578.29  4325.5  570.46  4410.9  567.04  4446.3   564.8
  4467.2  565.61  4496.3  563.82  4525.4  563.61  4553.6  562.45  4610.9  561.95
  4646.3  563.12    4700  562.45  4890.1  561.62    4915  562.88  4931.8  562.86
  4937.7  561.93  4940.1  561.55  4946.3  562.73  4960.9  559.24  4967.2  561.03
  4981.8  561.85  5017.8  561.81  5031.9  561.06  5041.8   557.8  5042.3   557.3
  5050.3   557.8  5060.2  562.89  5077.8  564.76  5116.8  568.55  5215.8  574.08
#Mann= 9 ,-1 , 0
  4003.6     .07       0  4060.3     .05       0  4525.4    .035       0
    4700     .12       0    4915     .07       0  4937.7     .12       0
  5041.8     .05       0  5050.3     .12       0  5077.8     .07       0
Bank Sta=5041.8,5050.3
XS Rating Curve= 0 ,0
Exp/Cntr=0.3,0.1

Type RM Length L Ch R = 1 ,21572   ,312,312,312
BEGIN DESCRIPTION:
COTTONWOOD CREEK SOUTH 2 33.0
END DESCRIPTION:
XS GIS Cut Line= 3
      2266624.96     13753925.02      2266967.61     13753777.41
      2268174.97       13753575.
#Sta/Elev= 30
  4657.3  575.75  4870.9  568.59  4939.4  564.47  4999.4  560.08  5005.8  557.66
  5012.4  557.53  5012.9  557.03    5021  557.53  5058.2  560.71  5144.4  562.06
  5210.3  563.53  5256.3  562.15  5271.1  563.53  5433.2  564.31  5503.7  566.21
  5636.1  567.85  5656.4  565.98  5707.1  566.42  5736.5  569.99  5747.7  573.39
  5759.9  573.75  5788.2   573.7  5802.2  570.93  5869.3  574.61  5934.7  574.23
  5984.2  572.93  6044.8  574.48  6082.3  577.25    6133  585.49  6254.6  593.82
#Mann= 8 ,-1 , 0
  4657.3     .05       0  4939.4     .07       0  5012.4     .05       0
    5021     .07       0  5144.4    .035       0  5503.7     .07       0
  5759.9     .05       0  5934.7     .07       0
Bank Sta=5012.4,5021
XS Rating Curve= 0 ,0
Exp/Cntr=0.3,0.1

Type RM Length L Ch R = 1 ,21260   ,477,477,477
BEGIN DESCRIPTION:
COTTONWOOD CREEK SOUTH 2 32.0
END DESCRIPTION:
XS GIS Cut Line= 3
      2267024.97     13754125.03        2267125.       13754025.
      2267925.01       13753825.
#Sta/Elev= 30
  4851.2  570.62  4907.8   568.7  4940.8  565.59  4957.3   564.5  4978.5  561.14
  4989.1  556.39  4995.2  556.39  4998.7  554.88  4999.2  554.38  5007.3  554.88
  5023.6  558.42  5051.9  560.78  5075.1   559.6  5157.6  558.55  5263.2  559.29
  5291.6  558.53  5304.5  560.19  5340.6  560.46  5382.8  562.96    5423  562.26
  5464.2  565.15    5539  566.71    5600  569.93  5610.7  570.09  5629.2  570.05
  5670.4  572.52  5693.6  572.64  5734.8  575.42  5776.1  576.34  5817.3  578.39
#Mann= 7 ,-1 , 0
  4851.2     .05       0  4940.8     .07       0  4998.7     .05       0
  5007.3     .07       0  5382.8    .035       0    5600     .07       0
  5610.7     .05       0
Bank Sta=4998.7,5007.3
XS Rating Curve= 0 ,0
Exp/Cntr=0.3,0.1

Type RM Length L Ch R = 1 ,20783   ,445,445,445
BEGIN DESCRIPTION:
COTTONWOOD CREEK SOUTH 2 31.0
END DESCRIPTION:
XS GIS Cut Line= 3
      2267124.97     13754375.01        2267525.       13754175.
        2267775.       13753925.
#Sta/Elev= 30
  4547.7  570.59  4606.4  568.54  4645.6  565.14  4653.4  565.11  4664.8  563.69
  4695.9  561.87  4712.6  562.23  4891.5  558.41  4919.5  558.57  4950.2  557.72
  4964.2  558.83  4972.6  558.63    4981  557.54  4986.6  557.86  4992.2  555.84
  4998.5  555.84  5004.6  553.23  5005.1  552.73  5013.5  553.23  5023.2  556.34
  5037.4  556.94  5051.5  558.69  5065.7  561.44  5091.2  561.88  5150.5  562.54
  5221.2  565.83  5249.5  564.52  5272.9   567.3  5334.4   570.1  5348.5  570.12
#Mann= 7 ,-1 , 0
  4547.7     .05       0  4653.4     .07       0  4664.8     .05       0
  5004.6     .05       0  5013.5     .05       0  5091.2     .05       0
  5272.9    .035       0
Bank Sta=5004.6,5013.5
XS Rating Curve= 0 ,0
Exp/Cntr=0.3,0.1