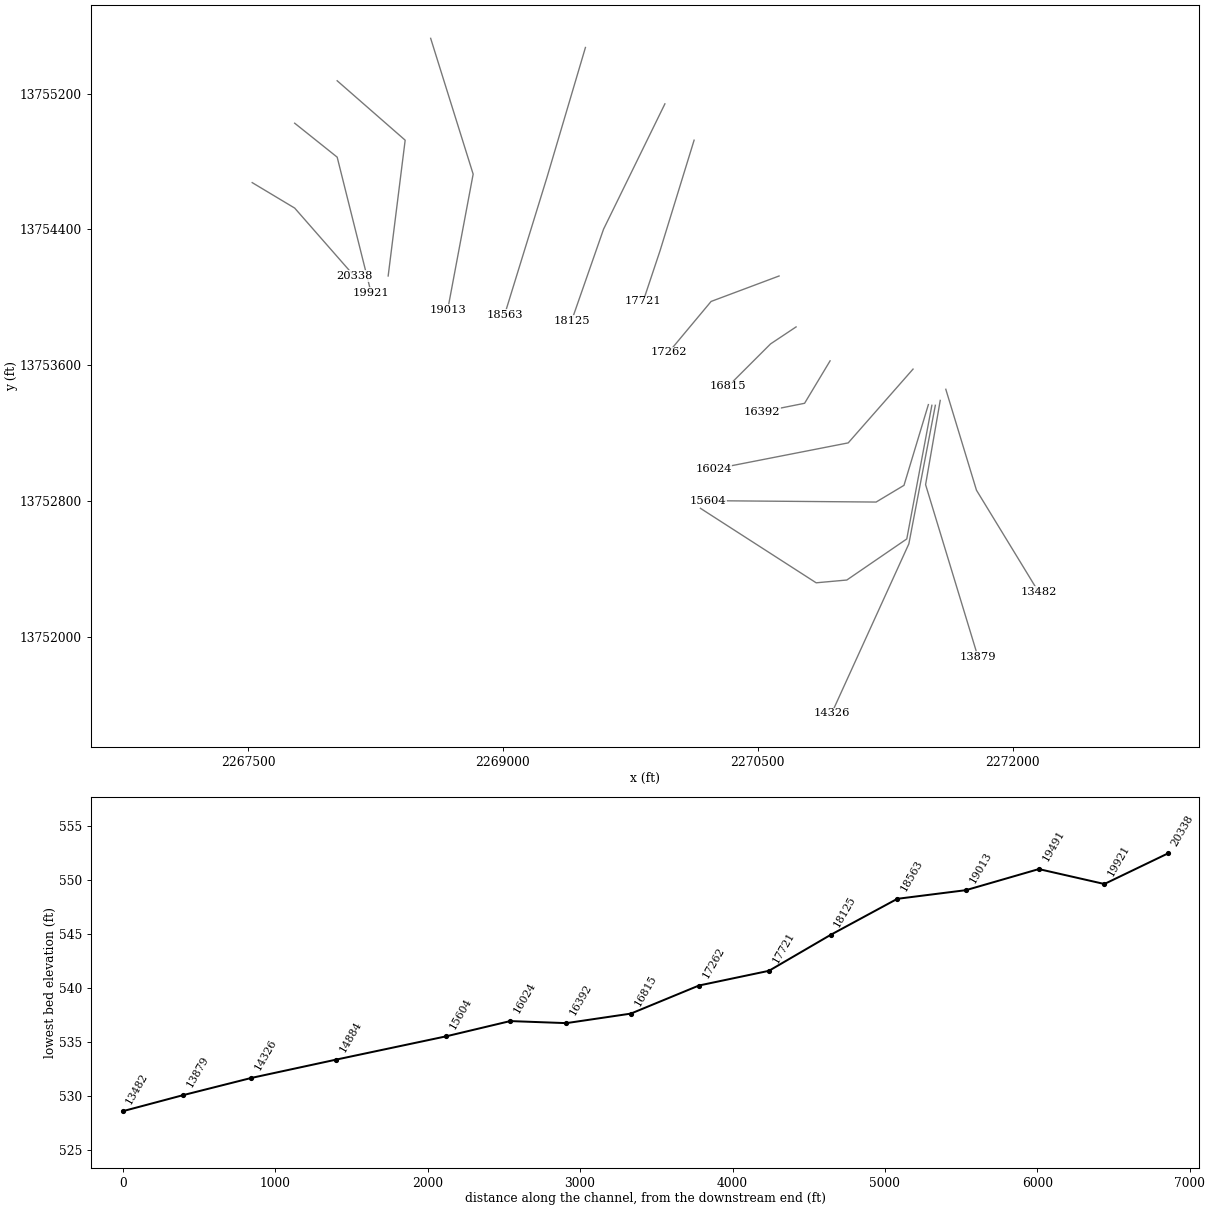
HEC-RAS study COTTONWOOD CREEK SOUTH 2.prj: COTTONWOOD CREEK SOUTH 2 Base Level Engineering

--- COTTONWOOD CREEK SOUTH 2.g01 (geometry) --- (continued)

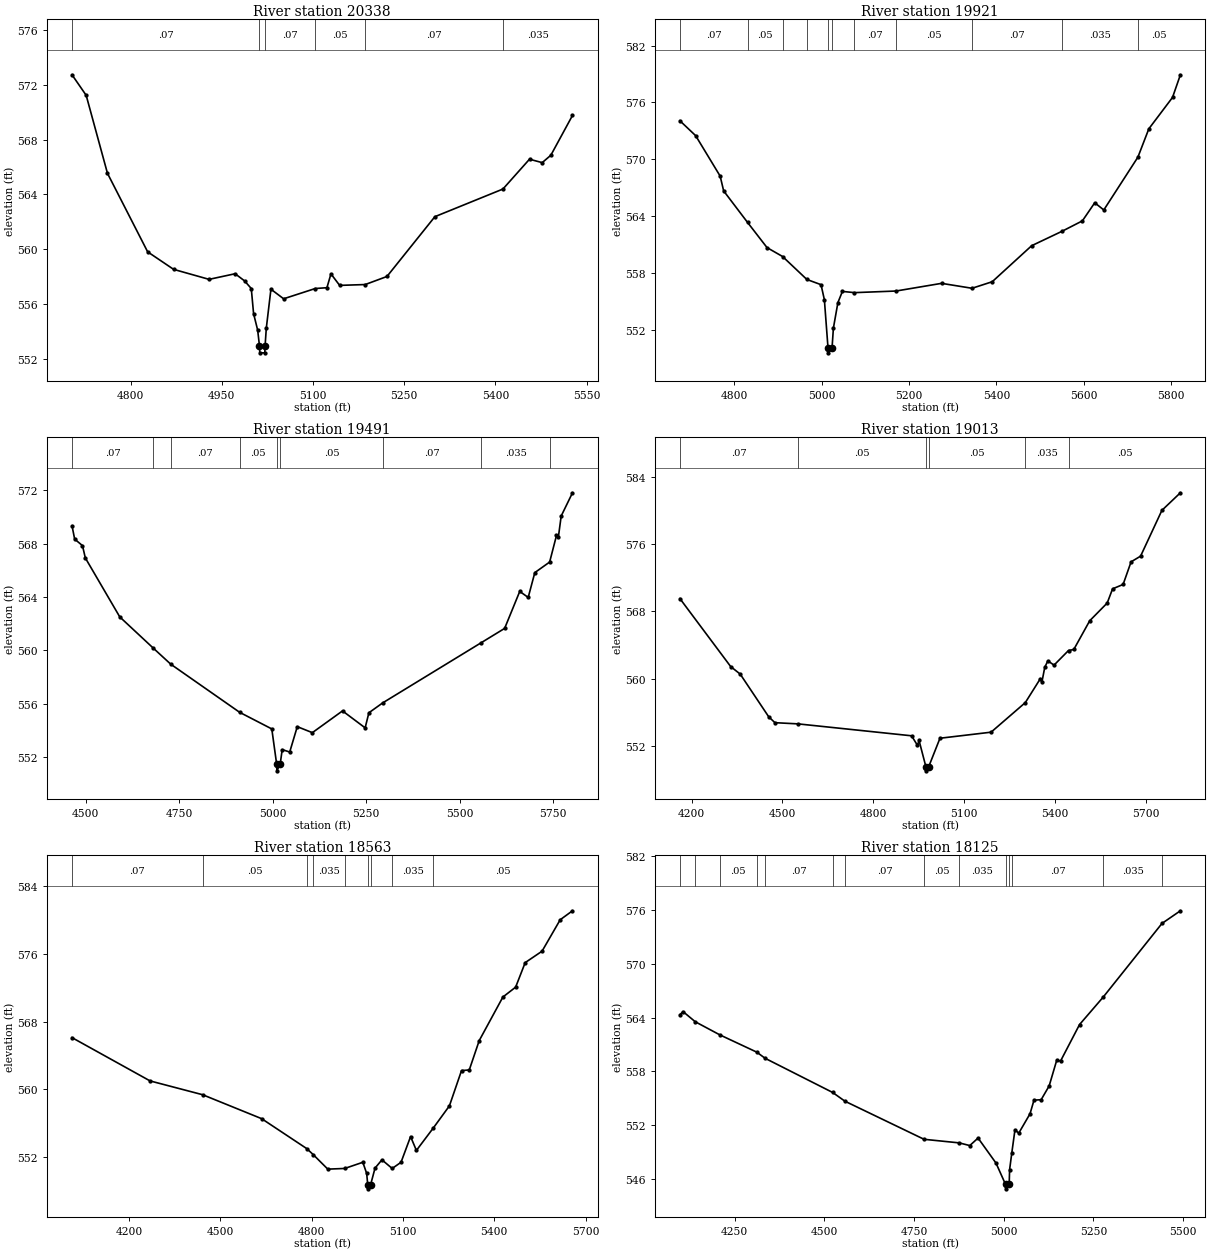
Type RM Length L Ch R = 1 ,20338   ,417,417,417
BEGIN DESCRIPTION:
COTTONWOOD CREEK SOUTH 2 30.0
END DESCRIPTION:
XS GIS Cut Line= 3
      2267525.02     13754674.99        2267775.       13754525.
      2268124.98     13754125.02
#Sta/Elev= 30
  4703.8  572.74  4727.1  571.24  4762.1  565.54  4828.2   559.8  4870.9  558.52
  4929.2  557.79    4972   558.2  4987.5  557.68  4998.6  557.12  5002.4  555.28
  5009.1  554.08  5012.1  552.92  5012.6  552.42  5020.8  552.42  5021.3  552.92
  5023.3  554.22  5030.9  557.07  5051.8  556.37  5103.8  557.12    5123  557.18
  5129.6  558.19  5143.9  557.35  5185.9  557.41  5221.7     558  5300.5  562.37
  5412.4  564.39  5456.1  566.57    5477  566.32  5491.2  566.86  5526.8  569.77
#Mann= 6 ,-1 , 0
  4703.8     .07       0  5012.1     .05       0  5021.3     .07       0
  5103.8     .05       0  5185.9     .07       0  5412.4    .035       0
Bank Sta=5012.1,5021.3
XS Rating Curve= 0 ,0
Exp/Cntr=0.3,0.1

Type RM Length L Ch R = 1 ,19921   ,430,430,430
BEGIN DESCRIPTION:
COTTONWOOD CREEK SOUTH 2 29.0
END DESCRIPTION:
XS GIS Cut Line= 3
      2267774.99     13755025.01        2268025.       13754825.
        2268225.     13754024.99
#Sta/Elev= 30
  4676.1  574.07  4712.1   572.5  4768.2  568.23  4776.2  566.67  4830.8  563.35
  4875.4  560.69    4911  559.75  4966.5  557.33  4998.9  556.78  5006.6  555.19
  5014.9  550.09  5015.4  549.59  5024.1  550.09  5027.2   552.2  5037.5  554.89
  5047.8  556.07  5075.4  555.94  5170.4  556.11  5274.6  556.92  5344.3   556.4
  5390.5  557.09  5480.7  560.89  5550.5  562.42  5596.7  563.51    5625  565.42
  5645.7  564.66  5723.7  570.23  5748.7  573.22  5802.9  576.53  5820.9  578.92
#Mann= 11 ,-1 , 0
  4676.1     .07       0  4830.8     .05       0    4911     .07       0
  4966.5     .05       0  5014.9     .05       0  5024.1     .05       0
  5075.4     .07       0  5170.4     .05       0  5344.3     .07       0
  5550.5    .035       0  5723.7     .05       0
Bank Sta=5014.9,5024.1
XS Rating Curve= 0 ,0
Exp/Cntr=0.3,0.1

Type RM Length L Ch R = 1 ,19491   ,478,478,478
BEGIN DESCRIPTION:
COTTONWOOD CREEK SOUTH 2 28.0
END DESCRIPTION:
XS GIS Cut Line= 3
      2268024.99     13755275.01        2268425.       13754925.
      2268325.01     13754125.04
#Sta/Elev= 30
  4463.9  569.33    4471  568.33  4491.9  567.84  4499.5  566.92  4591.6   562.5
  4681.2  560.16  4727.8  558.96  4912.2  555.35  4997.9  554.11  5010.9  551.47
  5011.4  550.97  5020.3  551.47  5025.7  552.56  5045.8  552.38    5066  554.28
  5106.3  553.83  5186.9  555.46  5247.4  554.19  5257.4  555.32  5294.3  556.06
  5558.3  560.58  5620.2  561.64  5660.6  564.41  5683.2  563.96  5700.9  565.82
  5740.5  566.61  5758.8   568.6  5763.9  568.49  5771.4  570.06  5801.6   571.8
#Mann= 9 ,-1 , 0
  4463.9     .07       0  4681.2     .05       0  4727.8     .07       0
  4912.2     .05       0  5010.9     .05       0  5020.3     .05       0
  5294.3     .07       0  5558.3    .035       0  5740.5     .05       0
Bank Sta=5010.9,5020.3
XS Rating Curve= 0 ,0
Exp/Cntr=0.3,0.1

Type RM Length L Ch R = 1 ,19013   ,450,450,450
BEGIN DESCRIPTION:
COTTONWOOD CREEK SOUTH 2 27.0
END DESCRIPTION:
XS GIS Cut Line= 3
        2268575.       13755525.        2268825.       13754725.
        2268675.       13753925.
#Sta/Elev= 30
  4161.5  569.52  4329.1  561.43  4360.6  560.53  4454.9  555.44  4475.3  554.75
  4550.9  554.61  4926.3  553.19  4945.7  552.05  4950.9  552.64  4973.4  549.52
  4973.9  549.02  4982.9  549.52    5020   552.9  5188.7  553.62  5301.7  557.14
  5351.5     560  5356.6  559.61  5365.9  561.34  5376.1  562.11  5396.5   561.6
  5444.3  563.34  5461.7  563.46  5514.3  566.88    5572  568.99  5589.8  570.68
  5624.5   571.2  5650.8  573.89  5682.2  574.57  5752.6  580.02  5813.6  582.11
#Mann= 6 ,-1 , 0
  4161.5     .07       0  4550.9     .05       0  4973.4     .05       0
  4982.9     .05       0  5301.7    .035       0  5444.3     .05       0
Bank Sta=4973.4,4982.9
XS Rating Curve= 0 ,0
Exp/Cntr=0.3,0.1

Type RM Length L Ch R = 1 ,18563   ,438,438,438
BEGIN DESCRIPTION:
COTTONWOOD CREEK SOUTH 2 26.0
END DESCRIPTION:
XS GIS Cut Line= 3
      2269485.65     13755471.15      2269260.09     13754708.34
      2269009.93     13753896.36
#Sta/Elev= 30
    4012   566.1  4268.7  560.98  4441.3  559.35  4635.2  556.52  4783.5  552.98
  4804.5  552.28  4852.8  550.55  4908.4  550.63  4967.9  551.36  4980.6  550.04
    4984  548.72  4984.5  548.22  4993.6  548.72    5008  550.67  5030.7  551.65
  5064.4  550.63  5093.5  551.36  5124.9   554.4    5144  552.76  5199.9  555.43
  5252.5  558.03  5292.3   562.2  5317.8  562.28  5350.5  565.75  5428.3   570.9
  5470.2  572.07  5501.6  574.97    5557  576.32  5616.7  580.04  5657.1   581.1
#Mann= 9 ,-1 , 0
    4012     .07       0  4441.3     .05       0  4783.5     .07       0
  4804.5    .035       0  4908.4     .05       0    4984     .05       0
  4993.6     .05       0  5064.4    .035       0  5199.9     .05       0
Bank Sta=4984,4993.6
XS Rating Curve= 0 ,0
Exp/Cntr=0.3,0.1

Type RM Length L Ch R = 1 ,18125   ,404,404,404
BEGIN DESCRIPTION:
X18641
END DESCRIPTION:
XS GIS Cut Line= 3
      2269953.17     13755138.97      2269592.27     13754400.76
      2269403.71     13753859.68
#Sta/Elev= 30
  4097.6  564.31  4106.2  564.67  4140.5  563.53  4208.8  562.07  4311.8  560.14
  4335.2  559.45  4523.2  555.64  4557.6  554.66    4778  550.41  4876.1  550.01
  4905.4  549.71  4928.5  550.55  4978.4  547.76    5005  545.38  5005.5  544.88
  5015.2  545.38  5016.4  547.03  5022.6  548.92  5031.3  551.47  5041.9   551.1
  5073.3  553.26  5084.3  554.78  5104.3  554.83  5126.6  556.37  5147.8  559.25
  5158.4  559.15  5211.3  563.22  5277.1  566.28  5441.1  574.51  5492.3  575.92
#Mann= 14 ,-1 , 0
  4097.6     .05       0  4140.5    .035       0  4208.8     .05       0
  4311.8    .035       0  4335.2     .07       0  4523.2     .05       0
  4557.6     .07       0    4778     .05       0  4876.1    .035       0
    5005    .035       0  5015.2    .035       0  5022.6     .07       0
  5277.1    .035       0  5441.1     .05       0
Bank Sta=5005,5015.2
XS Rating Curve= 0 ,0
Exp/Cntr=0.3,0.1

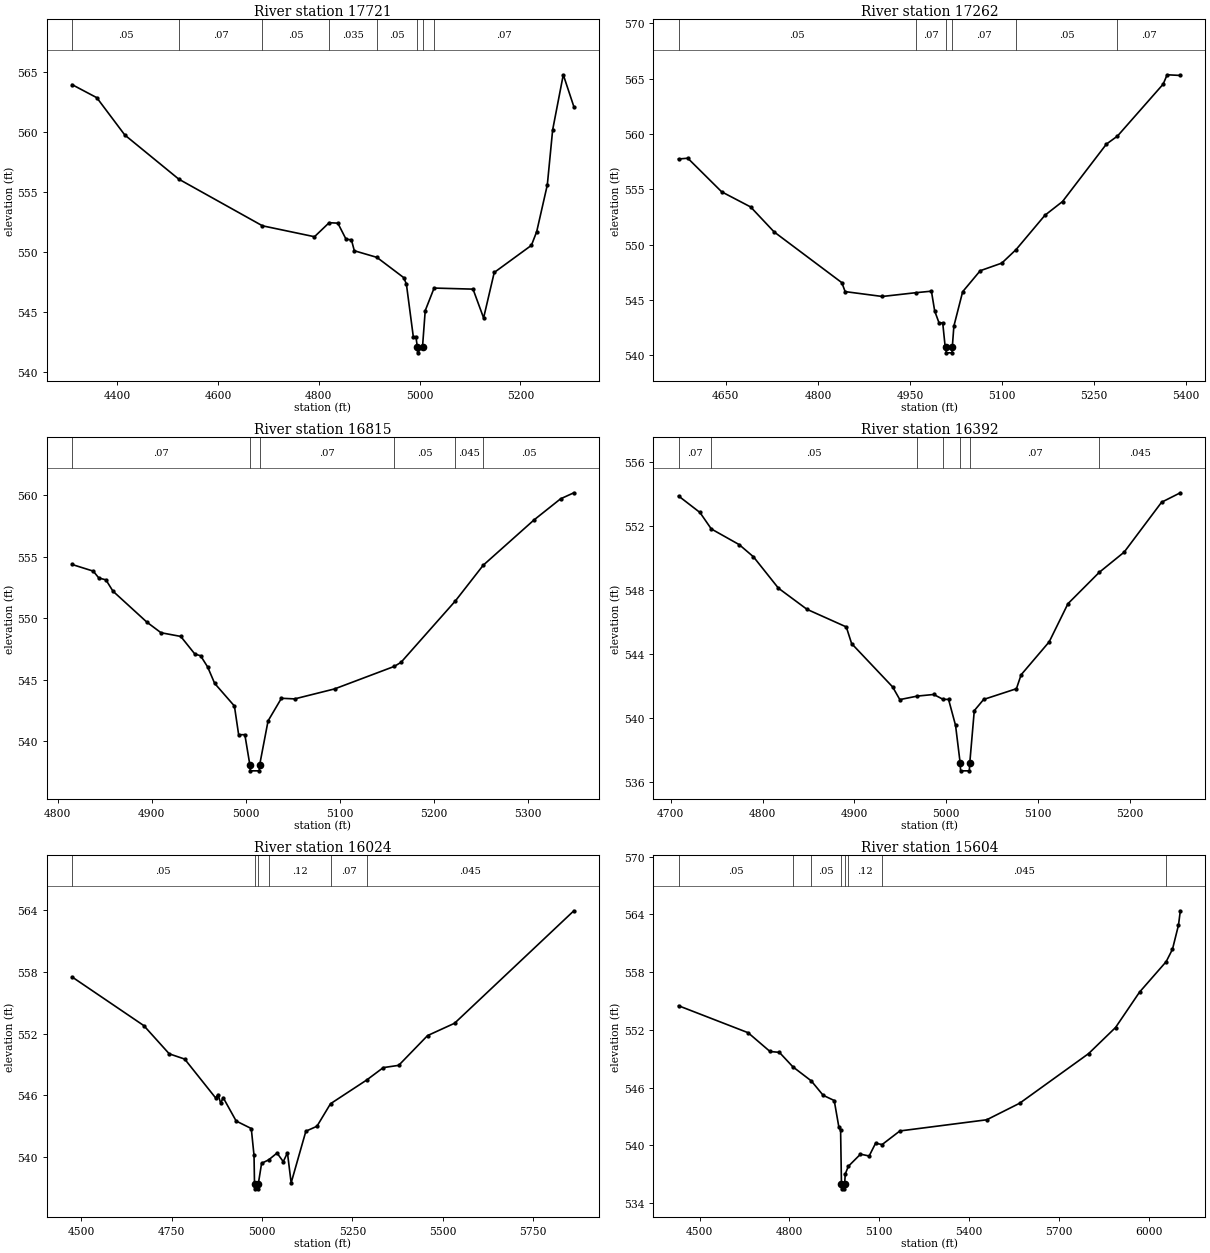
Type RM Length L Ch R = 1 ,17721   ,459,459,459
BEGIN DESCRIPTION:
COTTONWOOD CREEK SOUTH 2 25.0
END DESCRIPTION:
XS GIS Cut Line= 3
      2270125.01     13754925.03        2269925.       13754275.
      2269825.01     13753975.03
#Sta/Elev= 30
    4310  563.92  4359.1  562.83  4414.7  559.72  4521.9  556.04    4688  552.15
  4791.3  551.24  4820.5  552.41  4837.7  552.37  4854.1  551.02  4864.6  550.99
  4870.4  550.07  4915.2  549.52  4968.5  547.83  4973.8  547.29  4987.5  542.91
  4992.7  542.91  4995.5  542.06    4996  541.56  5005.8  542.06  5011.2  545.08
  5028.8  546.96  5106.1  546.87  5127.1  544.47  5148.2  548.26    5222  550.52
  5232.5  551.66  5253.6  555.56  5264.2  560.15  5285.3  564.74  5306.3  562.08
#Mann= 8 ,-1 , 0
    4310     .05       0  4521.9     .07       0    4688     .05       0
  4820.5    .035       0  4915.2     .05       0  4995.5     .05       0
  5005.8     .05       0  5028.8     .07       0
Bank Sta=4995.5,5005.8
XS Rating Curve= 0 ,0
Exp/Cntr=0.3,0.1

Type RM Length L Ch R = 1 ,17262   ,447,447,447
BEGIN DESCRIPTION:
COTTONWOOD CREEK SOUTH 2 24.0
END DESCRIPTION:
XS GIS Cut Line= 3
        2270625.       13754125.        2270225.       13753975.
      2269975.01     13753675.01
#Sta/Elev= 30
  4572.9  557.74    4588  557.81  4643.2  554.77  4690.4   553.4  4728.7  551.14
    4839  546.55  4844.4  545.74  4904.9   545.3  4959.3  545.64    4985  545.78
  4990.3  543.99  4997.4  542.91  5003.4  542.91  5007.3   540.8  5008.6   540.7
  5009.1   540.2  5018.5   540.2    5019   540.7  5021.6  542.62  5035.9  545.73
  5064.5  547.63  5099.7  548.32  5122.9  549.54    5170  552.65  5198.6  553.89
  5270.2  559.09  5288.1  559.81  5362.6  564.51  5369.1  565.36  5390.6   565.3
#Mann= 6 ,-1 , 0
  4572.9     .05       0  4959.3     .07       0  5008.6     .05       0
    5019     .07       0  5122.9     .05       0  5288.1     .07       0
Bank Sta=5008.6,5019
XS Rating Curve= 0 ,0
Exp/Cntr=0.3,0.1

Type RM Length L Ch R = 1 ,16815   ,423,423,423
BEGIN DESCRIPTION:
COTTONWOOD CREEK SOUTH 2 23.0
END DESCRIPTION:
XS GIS Cut Line= 3
      2270724.97     13753824.98        2270575.       13753725.
        2270325.       13753475.
#Sta/Elev= 30
  4815.4  554.38  4837.9  553.84  4843.9  553.28  4851.4  553.13  4858.9  552.21
    4895  549.69    4910  548.83    4931  548.53  4946.1  547.09  4952.1  546.96
  4959.6  546.05  4967.1  544.71  4988.1  542.87  4992.6  540.54  4999.2  540.54
  5004.5   538.1    5005   537.6  5014.5   537.6    5015   538.1  5023.9  541.66
  5038.1   543.5  5052.2  543.45  5094.6  544.26  5158.1  546.09  5165.3  546.42
  5223.1  551.41  5252.8  554.32  5306.8     558  5335.1  559.72  5349.2  560.21
#Mann= 6 ,-1 , 0
  4815.4     .07       0  5004.5     .05       0    5015     .07       0
  5158.1     .05       0  5223.1    .045       0  5252.8     .05       0
Bank Sta=5004.5,5015
XS Rating Curve= 0 ,0
Exp/Cntr=0.3,0.1

Type RM Length L Ch R = 1 ,16392   ,368,368,368
BEGIN DESCRIPTION:
COTTONWOOD CREEK SOUTH 2 22.0
END DESCRIPTION:
XS GIS Cut Line= 3
        2270925.       13753625.        2270775.       13753375.
        2270525.       13753325.
#Sta/Elev= 30
  4708.4  553.89  4731.7  552.86  4744.1  551.83  4774.5  550.85    4790  550.09
  4817.2  548.13  4848.3  546.81  4891.1  545.71  4896.9  544.67  4941.6  541.96
  4949.4  541.17  4968.5  541.39  4986.3  541.49  4996.4  541.19  5002.5  541.18
  5010.1  539.56  5015.1  537.22  5015.6  536.72  5025.1  536.72  5025.6  537.22
  5030.5  540.48  5040.7  541.18  5076.4  541.85  5081.5  542.72  5112.1  544.78
  5132.5  547.16  5166.6  549.12  5193.7  550.38  5234.5   553.5  5254.9  554.09
#Mann= 7 ,-1 , 0
  4708.4     .07       0  4744.1     .05       0  4968.5     .12       0
  4996.4     .07       0  5015.1     .05       0  5025.6     .07       0
  5166.6    .045       0
Bank Sta=5015.1,5025.6
XS Rating Curve= 0 ,0
Exp/Cntr=0.3,0.1

Type RM Length L Ch R = 1 ,16024   ,420,420,420
BEGIN DESCRIPTION:
X18642
END DESCRIPTION:
XS GIS Cut Line= 3
      2271413.15     13753576.48      2271031.73     13753141.75
      2270238.05     13752986.28
#Sta/Elev= 30
  4475.1   557.5  4673.5  552.77  4743.7  550.03  4786.4  549.52  4871.8  545.75
  4878.5  546.07    4886  545.23  4892.7  545.78  4928.7   543.5  4970.5  542.77
  4978.1  540.15  4979.4  537.41  4979.9  536.91  4989.5  536.91    4990  537.41
    4999  539.39  5018.7  539.73  5041.7  540.39  5058.9  539.55  5070.5  540.41
  5080.7  537.49  5121.4  542.51    5152  542.99  5189.5  545.18  5289.3  547.48
  5335.4  548.69    5378  548.91  5457.7   551.8  5532.4     553  5862.2  563.93
#Mann= 6 ,-1 , 0
  4475.1     .05       0  4979.4     .05       0    4990     .05       0
  5018.7     .12       0  5189.5     .07       0  5289.3    .045       0
Bank Sta=4979.4,4990
XS Rating Curve= 0 ,0
Exp/Cntr=0.3,0.1

Type RM Length L Ch R = 1 ,15604   ,720,720,720
BEGIN DESCRIPTION:
X18643
END DESCRIPTION:
XS GIS Cut Line= 4
      2271503.36     13753367.34      2271359.82     13752891.58
      2271195.77     13752793.16      2270208.75     13752801.35
#Sta/Elev= 30
  4429.7  554.51  4661.9  551.71  4735.1  549.76  4766.4  549.67  4811.4  548.17
  4872.8  546.71  4912.6  545.21  4949.5  544.67    4965  541.91  4970.8  541.57
  4973.6     536  4974.1   535.5  4983.7   535.5  4984.2     536  4986.4  537.05
  4996.7  537.84  5037.2   539.1  5066.1  538.91  5087.5  540.23  5109.5   540.1
  5168.7  541.51  5458.7  542.67  5568.7  544.39  5798.7  549.54  5888.7  552.25
  5968.7  555.92  6057.8  559.09  6078.8  560.38  6098.8  562.87    6105  564.37
#Mann= 8 ,-1 , 0
  4429.7     .05       0  4811.4     .07       0  4872.8     .05       0
  4973.6     .05       0  4984.2     .05       0  4996.7     .12       0
  5109.5    .045       0  6057.8     .07       0
Bank Sta=4973.6,4984.2
XS Rating Curve= 0 ,0
Exp/Cntr=0.3,0.1

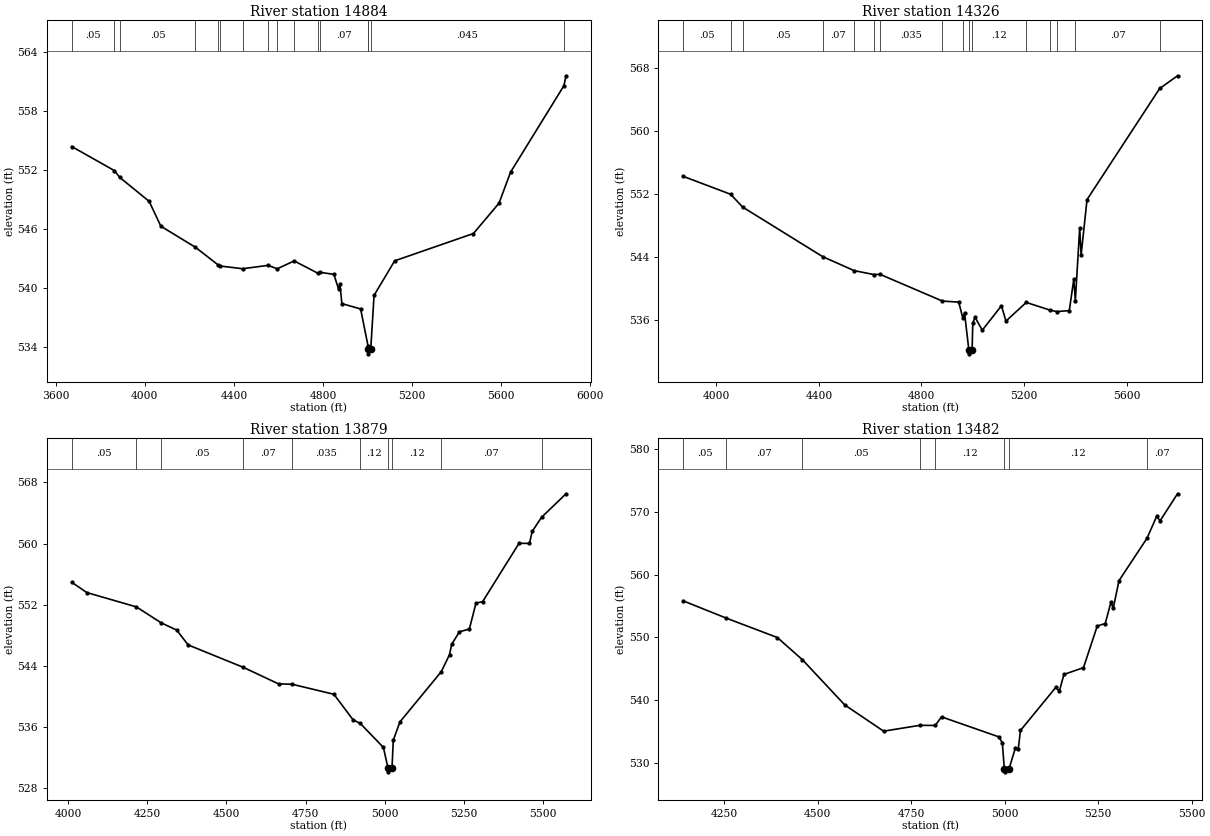
Type RM Length L Ch R = 1 ,14884   ,558,558,558
BEGIN DESCRIPTION:
X18644
END DESCRIPTION:
XS GIS Cut Line= 5
      2271523.86     13753363.19      2271376.22      13752575.8
      2271023.53     13752333.84      2270843.09     13752317.44
      2270162.27     13752756.27
#Sta/Elev= 30
  3671.4  554.37  3862.9  551.93  3887.5  551.23  4019.2  548.81  4071.8  546.29
  4226.6  544.16  4330.4  542.34  4338.6  542.25  4439.3  541.98  4553.5  542.32
  4594.4  541.97  4670.5  542.77  4776.3  541.53  4787.5  541.61  4848.9  541.41
  4869.9  539.91    4876   540.4  4884.8  538.44    4969   537.9  5002.5  534.12
  5003.8  533.85  5004.3  533.35  5014.5  533.85  5029.3  539.28  5121.9  542.78
  5475.7  545.55  5590.7  548.63  5642.1  551.76  5881.8  560.53  5891.4  561.54
#Mann= 16 ,-1 , 0
  3671.4     .05       0  3862.9     .07       0  3887.5     .05       0
  4226.6     .07       0  4330.4     .12       0  4338.6     .07       0
  4439.3    .035       0  4553.5     .07       0  4594.4    .035       0
  4670.5     .07       0  4776.3    .035       0  4787.5     .07       0
  5002.5    .045       0  5003.8     .05       0  5014.5    .045       0
  5881.8     .07       0
Bank Sta=5003.8,5014.5
XS Rating Curve= 0 ,0
Exp/Cntr=0.3,0.1

Type RM Length L Ch R = 1 ,14326   ,447,447,447
BEGIN DESCRIPTION:
X18645
END DESCRIPTION:
XS GIS Cut Line= 3
      2271544.36     13753363.17      2271388.52      13752547.1
      2270934.12     13751548.22
#Sta/Elev= 30
  3870.4  554.26  4055.2  551.98  4102.7  550.34  4414.6  544.03  4537.4  542.25
  4614.1  541.75  4638.2  541.78  4881.6  538.37  4945.2  538.24  4961.6  536.17
    4968  536.86  4984.7  532.15  4985.2  531.65  4997.4  532.15  5000.1  535.54
  5008.6  536.32  5037.2  534.66  5111.9  537.78  5129.4  535.82  5208.6   538.2
  5300.3  537.23  5328.1  537.03  5376.5  537.16  5394.1  541.15  5400.1  538.43
  5417.1  547.67  5422.6  544.22  5445.7   551.3    5729  565.45  5798.6  567.07
#Mann= 16 ,-1 , 0
  3870.4     .05       0  4055.2     .07       0  4102.7     .05       0
  4414.6     .07       0  4537.4    .035       0  4614.1     .07       0
  4638.2    .035       0  4881.6     .07       0  4961.6     .12       0
  4984.7     .05       0  4997.4     .12       0  5208.6    .035       0
  5300.3     .12       0  5328.1    .035       0  5400.1     .07       0
    5729    .045       0
Bank Sta=4984.7,4997.4
XS Rating Curve= 0 ,0
Exp/Cntr=0.3,0.1

Type RM Length L Ch R = 1 ,13879   ,397,397,397
BEGIN DESCRIPTION:
X18646
END DESCRIPTION:
XS GIS Cut Line= 3
      2271573.07     13753391.91      2271486.95     13752895.68
      2271794.54      13751882.7
#Sta/Elev= 30
  4010.8  554.92  4058.4  553.57  4215.2  551.69  4294.3  549.58  4342.6  548.65
  4378.9   546.7  4553.3  543.76  4664.7  541.59  4706.8  541.55  4839.5  540.23
  4900.1  536.88  4922.8  536.41  4995.9  533.26  5010.4  530.56  5010.9  530.06
  5023.1  530.56  5027.2  534.21  5048.2  536.61  5178.8  543.19  5204.9  545.43
  5211.7  546.79  5236.3  548.42  5267.6  548.79  5288.5  552.18  5309.4  552.37
  5424.7  560.03  5457.6  560.01  5466.2  561.58  5495.6  563.43  5573.1  566.52
#Mann= 10 ,-1 , 0
  4010.8     .05       0  4215.2     .07       0  4294.3     .05       0
  4553.3     .07       0  4706.8    .035       0  4922.8     .12       0
  5010.4     .05       0  5023.1     .12       0  5178.8     .07       0
  5495.6    .045       0
Bank Sta=5010.4,5023.1
XS Rating Curve= 0 ,0
Exp/Cntr=0.3,0.1

Type RM Length L Ch R = 1 ,13482   ,725,725,725
BEGIN DESCRIPTION:
X18647
END DESCRIPTION:
XS GIS Cut Line= 3
      2271605.88     13753457.51      2271786.32     13752862.88
      2272150.67     13752265.18
#Sta/Elev= 30
  4140.8  555.81  4256.4  553.05  4392.5  549.97  4459.6  546.43  4572.7  539.23
  4676.6  535.05  4773.5  535.98  4814.6  535.96  4831.4  537.33  4984.3  534.15
  4993.9  533.21  4999.3  529.07  4999.8  528.57    5012  529.07  5029.1  532.43
  5036.6  532.22  5042.4  535.16  5137.3  542.06  5146.2  541.38  5158.6  544.09
  5210.9  545.17  5247.7   551.8    5269   552.2  5284.4  555.62  5290.3   554.6
  5305.8  559.03  5380.8   565.8  5406.5  569.27  5415.6  568.56  5462.2  572.87
#Mann= 8 ,-1 , 0
  4140.8     .05       0  4256.4     .07       0  4459.6     .05       0
  4773.5     .07       0  4814.6     .12       0  4999.3     .05       0
    5012     .12       0  5380.8     .07       0
Bank Sta=4999.3,5012
XS Rating Curve= 0 ,0
Exp/Cntr=0.3,0.1