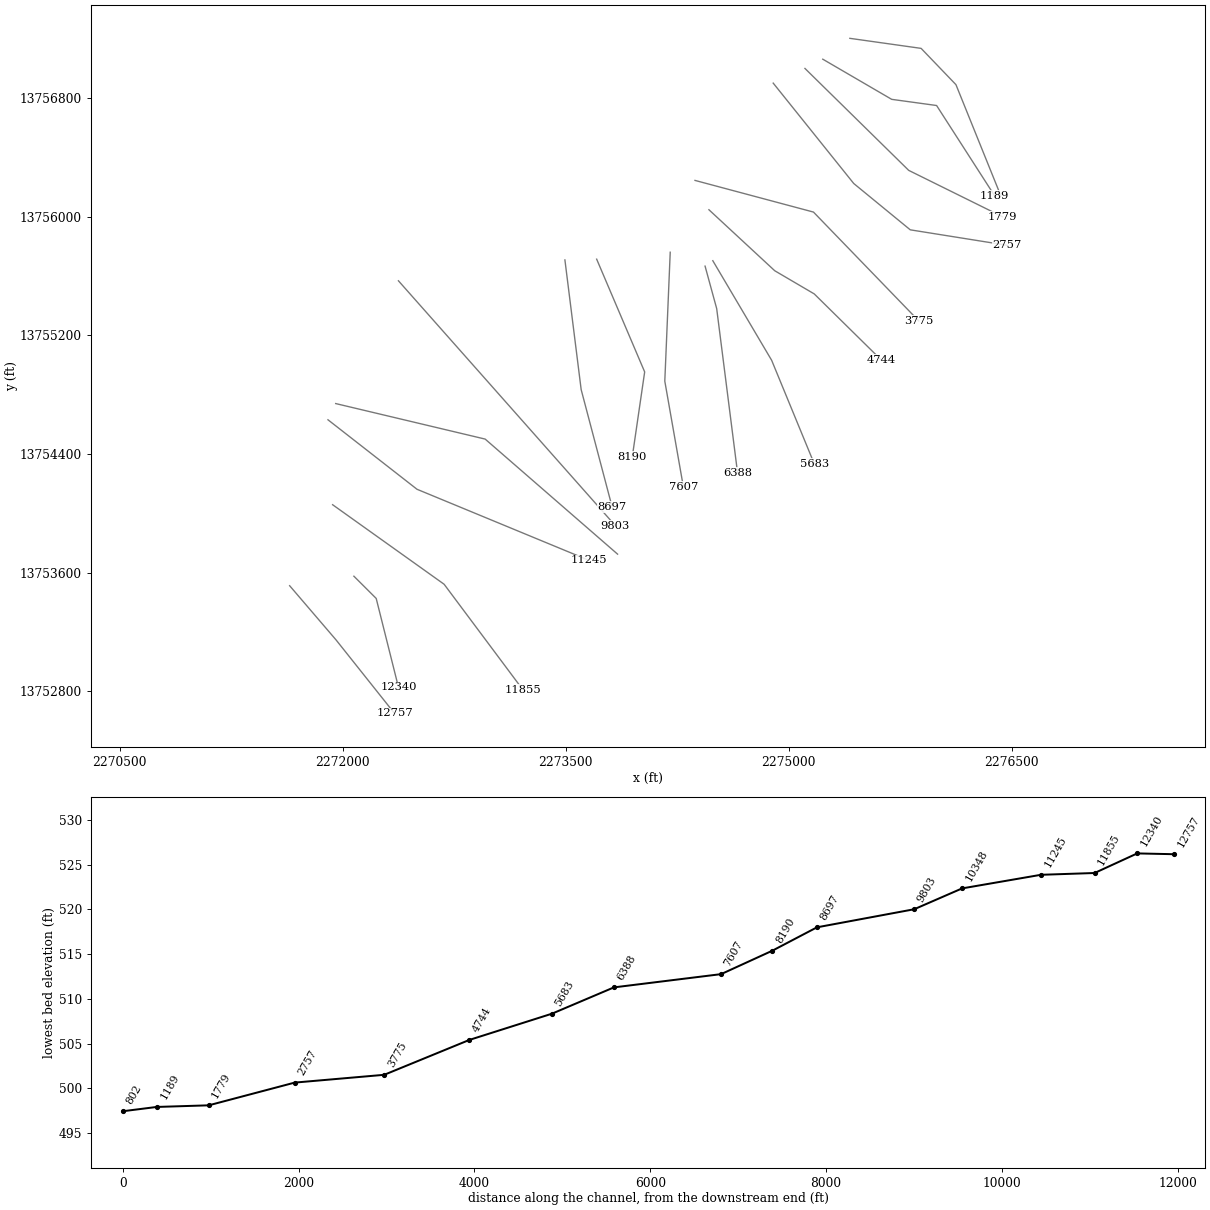
HEC-RAS study COTTONWOOD CREEK SOUTH 2.prj: COTTONWOOD CREEK SOUTH 2 Base Level Engineering

--- COTTONWOOD CREEK SOUTH 2.g01 (geometry) --- (continued)

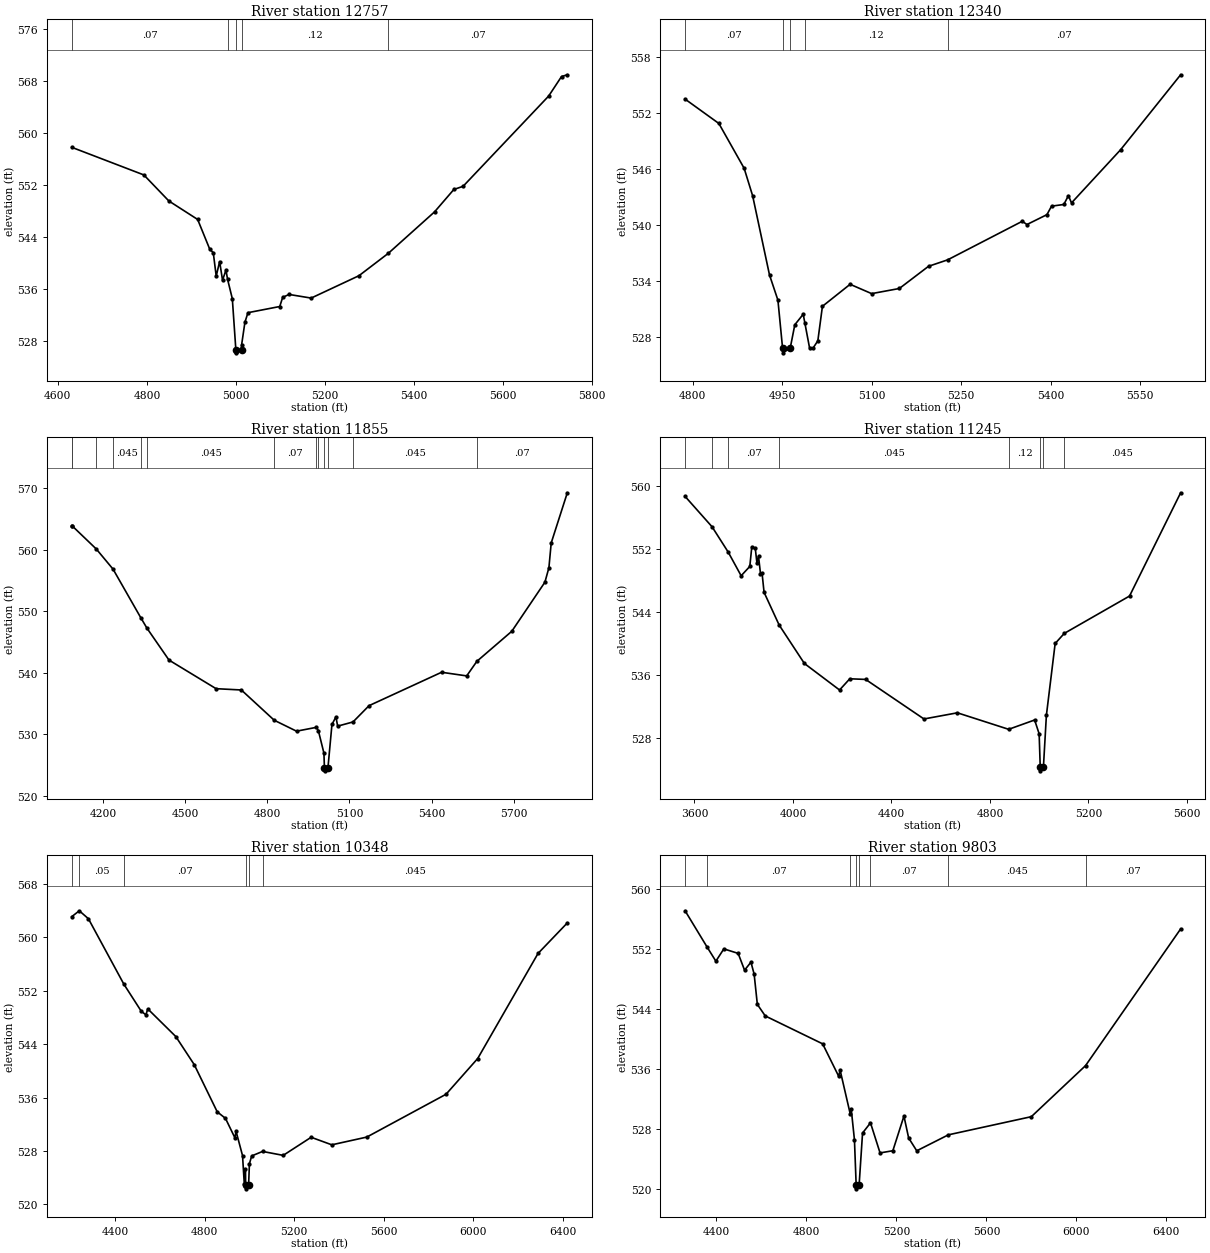
Type RM Length L Ch R = 1 ,12757   ,417,417,417
BEGIN DESCRIPTION:
X18648
END DESCRIPTION:
XS GIS Cut Line= 3
      2271642.79     13753510.84      2271954.47     13753145.85
      2272348.05     13752649.77
#Sta/Elev= 30
  4631.2  557.84  4793.2  553.58  4849.3  549.57    4914  546.72  4941.4   542.1
  4949.1   541.6  4955.7  537.99  4963.4  540.23  4969.9  537.35  4977.6  538.93
  4981.2   537.5  4991.9   534.5  4999.8  526.66  5000.3  526.16  5012.6  526.66
  5012.8  527.41  5020.2  530.88    5027  532.35  5098.4   533.3    5105  534.71
  5119.3  535.16    5169   534.6  5276.4  538.05  5342.5  541.51  5446.2  547.89
  5489.5  551.34  5510.3  551.83  5702.5  565.74  5731.4  568.75  5744.4  569.02
#Mann= 5 ,-1 , 0
  4631.2     .07       0  4981.2     .12       0  4999.8     .05       0
  5012.6     .12       0  5342.5     .07       0
Bank Sta=4999.8,5012.6
XS Rating Curve= 0 ,0
Exp/Cntr=0.3,0.1

Type RM Length L Ch R = 1 ,12340   ,485,485,485
BEGIN DESCRIPTION:
COTTONWOOD CREEK SOUTH 2 16.0
END DESCRIPTION:
XS GIS Cut Line= 3
      2272074.96     13753575.04        2272225.       13753425.
      2272374.99     13752825.05
#Sta/Elev= 30
  4787.5  553.46  4844.1  550.85  4886.5  546.04  4900.7   543.1    4929   534.6
  4943.1   531.9  4950.9  526.75  4951.4  526.25  4963.7  526.75  4971.4  529.26
  4985.5  530.39  4988.2  529.47  4996.1  526.79  5002.3  526.79    5010  527.54
  5017.7  531.24  5064.1   533.6  5100.2   532.6  5146.6  533.15  5195.5  535.53
  5227.5  536.22  5352.7  540.36  5360.5  540.01    5394  541.07  5401.7  541.98
  5422.3  542.16    5430  543.11  5435.2  542.33  5517.6  548.04  5618.1  556.07
#Mann= 5 ,-1 , 0
  4787.5     .07       0  4950.9     .05       0  4963.7     .07       0
  4988.2     .12       0  5227.5     .07       0
Bank Sta=4950.9,4963.7
XS Rating Curve= 0 ,0
Exp/Cntr=0.3,0.1

Type RM Length L Ch R = 1 ,11855   ,610,610,610
BEGIN DESCRIPTION:
X18649
END DESCRIPTION:
XS GIS Cut Line= 3
      2271931.81      13754057.2       2272681.8     13753520.74
      2273211.98     13752808.64
#Sta/Elev= 30
  4085.8  563.93  4086.5  563.93  4175.3  560.14  4236.6  556.86  4337.8  548.97
  4360.3  547.27    4441  542.07    4613  537.42  4705.2  537.21  4825.2  532.29
  4906.7  530.51  4978.8  531.13  4986.4  530.61  5006.8  526.94  5008.6  524.56
  5009.1  524.06  5021.5  524.56  5036.1   531.6  5050.7  532.84  5056.9  531.33
    5113  532.01  5171.6  534.66  5436.5  540.09  5528.2   539.5  5565.4  541.87
    5693  546.76  5813.9  554.74  5828.5   557.1  5836.9  561.12  5895.7  569.28
#Mann= 13 ,-1 , 0
  4085.8     .05       0  4086.5     .07       0  4175.3     .05       0
  4236.6    .045       0  4337.8     .05       0  4360.3    .045       0
  4825.2     .07       0  4978.8     .12       0  4986.4     .07       0
  5008.6     .05       0  5021.5     .07       0    5113    .045       0
  5565.4     .07       0
Bank Sta=5008.6,5021.5
XS Rating Curve= 0 ,0
Exp/Cntr=0.3,0.1

Type RM Length L Ch R = 1 ,11245   ,897,897,897
BEGIN DESCRIPTION:
X18650
END DESCRIPTION:
XS GIS Cut Line= 3
      2271900.59     13754630.09      2272499.51     13754161.37
      2273655.73     13753682.21
#Sta/Elev= 30
  3562.1  558.62  3671.7  554.77  3736.9  551.58  3789.7  548.57  3824.9  549.75
    3833  552.25  3847.1  552.04  3853.9  550.17  3860.2  551.04  3868.3  548.84
  3874.7  548.88  3882.8  546.47    3944  542.33  4046.5  537.46  4189.3   534.1
  4230.9  535.52  4295.1  535.44    4532  530.43  4667.7  531.21  4875.9  529.12
  4981.3   530.3  4999.7  528.55  5004.1  524.36  5004.6  523.86  5017.1  524.36
  5029.1  530.89  5064.7  539.99  5101.8  541.27  5366.7     546  5574.2  559.08
#Mann= 8 ,-1 , 0
  3562.1     .07       0  3671.7     .05       0  3736.9     .07       0
    3944    .045       0  4875.9     .12       0  5004.1     .05       0
  5017.1     .12       0  5101.8    .045       0
Bank Sta=5004.1,5017.1
XS Rating Curve= 0 ,0
Exp/Cntr=0.3,0.1

Type RM Length L Ch R = 1 ,10348   ,545,545,545
BEGIN DESCRIPTION:
X18651
END DESCRIPTION:
XS GIS Cut Line= 3
      2271952.63     13754739.49      2272957.84     13754499.91
      2273848.49     13753723.84
#Sta/Elev= 30
  4206.3  563.09    4240  563.97  4280.7  562.78  4439.2  552.98  4517.1  548.92
  4537.7  548.39    4546  549.28  4671.3  545.14  4753.6  540.94  4856.4  533.87
  4893.3  532.89  4935.4  529.98  4940.6  530.95  4969.5  527.32  4977.5  523.03
  4982.7  525.35  4983.5  522.84    4984  522.34  4996.6  522.84  5000.3  526.11
  5010.6  527.27  5059.1  527.94  5151.2  527.35  5276.2  530.06  5368.5  528.93
  5524.9  530.09    5879   536.5  6020.5  541.85  6290.1  557.58    6421  562.15
#Mann= 6 ,-1 , 0
  4206.3     .07       0    4240     .05       0  4439.2     .07       0
  4983.5     .05       0  4996.6     .07       0  5059.1    .045       0
Bank Sta=4983.5,4996.6
XS Rating Curve= 0 ,0
Exp/Cntr=0.3,0.1

Type RM Length L Ch R = 1 ,9803    ,1106,1106,1106
BEGIN DESCRIPTION:
X18652
END DESCRIPTION:
XS GIS Cut Line= 2
      2272374.53      13755567.6      2273832.87     13753916.54
#Sta/Elev= 30
  4260.4  557.08  4357.7  552.27  4397.3  550.36  4432.7     552  4496.3   551.4
  4524.8  549.16  4553.2  550.23  4567.4  548.63  4581.6   544.6  4616.8  543.06
  4871.9  539.34    4943  535.03  4949.7  535.82  4994.5     530  4999.1   530.6
  5013.3  526.54  5020.9  520.51  5021.4  520.01    5034  520.51  5049.3  527.45
  5084.6  528.81  5127.1   524.8    5184  525.09  5233.3  529.71  5254.2  526.79
  5290.2  525.08  5430.8  527.21  5799.6  529.63  6040.4  536.43  6463.3  554.66
#Mann= 8 ,-1 , 0
  4260.4     .05       0  4357.7     .07       0  4994.5     .12       0
  5020.9     .05       0    5034     .12       0  5084.6     .07       0
  5430.8    .045       0  6040.4     .07       0
Bank Sta=5020.9,5034
XS Rating Curve= 0 ,0
Exp/Cntr=0.3,0.1

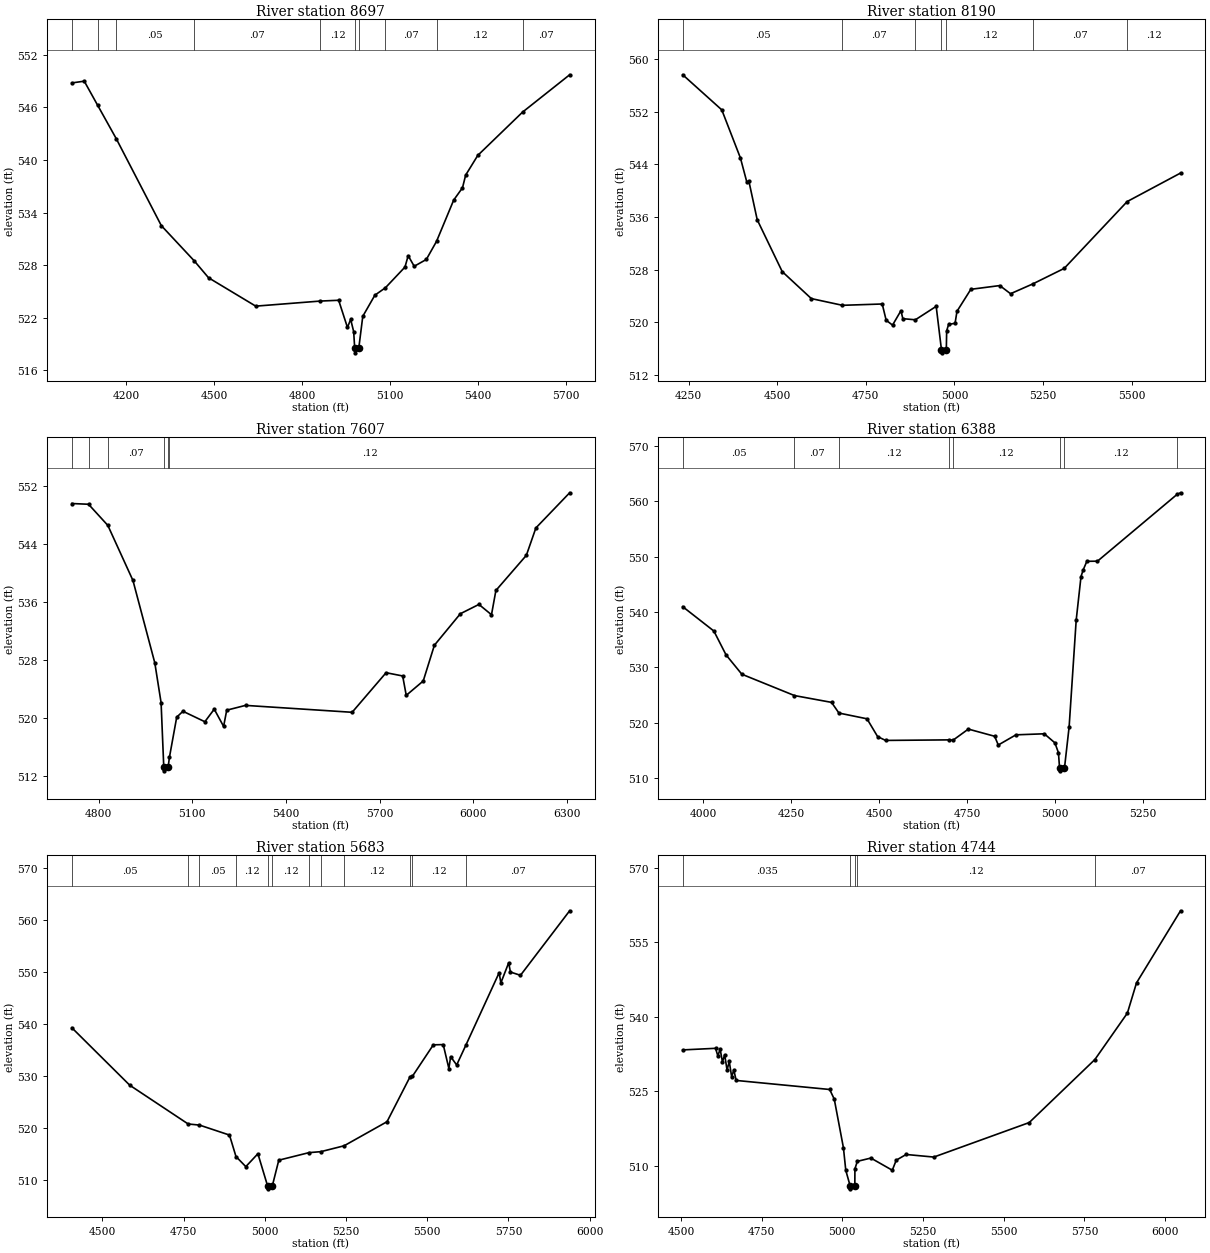
Type RM Length L Ch R = 1 ,8697    ,507,507,507
BEGIN DESCRIPTION:
X18653
END DESCRIPTION:
XS GIS Cut Line= 3
       2273494.3     13755708.26      2273603.68     13754833.24
      2273812.02     13754041.53
#Sta/Elev= 30
  4013.5   548.8  4055.8     549  4101.7  546.24  4165.2  542.43  4319.1  532.51
  4431.8  528.48  4480.4  526.56  4641.6  523.32    4862   523.9  4924.9  523.99
  4954.9  520.89  4965.9  521.81  4976.2  520.41  4979.7  518.49  4980.2  517.99
  4993.5  518.49  5007.3  522.16  5048.6  524.57  5084.7  525.42  5151.4  527.78
  5162.4  529.08    5183  527.87  5224.4  528.65  5259.3  530.72  5317.9  535.43
  5347.9  536.83  5358.8  538.28  5400.2  540.53  5553.2  545.47    5714  549.73
#Mann= 10 ,-1 , 0
  4013.5     .05       0  4101.7     .07       0  4165.2     .05       0
  4431.8     .07       0    4862     .12       0  4979.7     .05       0
  4993.5     .12       0  5084.7     .07       0  5259.3     .12       0
  5553.2     .07       0
Bank Sta=4979.7,4993.5
XS Rating Curve= 0 ,0
Exp/Cntr=0.3,0.1

Type RM Length L Ch R = 1 ,8190    ,583,583,583
BEGIN DESCRIPTION:
X18654
END DESCRIPTION:
XS GIS Cut Line= 3
      2273707.83     13755713.49      2274030.76     13754953.03
      2273947.43     13754380.15
#Sta/Elev= 30
  4233.2  557.62  4343.4  552.29  4396.1  544.97  4414.3  541.28  4419.8  541.48
  4443.4   535.6    4514  527.72  4596.2  523.62    4684   522.6  4796.3   522.8
  4807.4  520.33  4825.4  519.59  4849.1  521.78  4854.5  520.57  4889.8   520.4
  4948.6  522.44  4963.4  515.88  4963.9  515.38  4977.2  515.88  4978.2  518.73
  4983.7   519.7  5001.9  519.87  5007.3  521.69  5046.4  525.03  5128.1   525.6
  5158.5  524.36  5221.3  525.85    5310  528.21  5487.7  538.36  5638.3  542.69
#Mann= 7 ,-1 , 0
  4233.2     .05       0    4684     .07       0  4889.8     .12       0
  4963.4     .05       0  4977.2     .12       0  5221.3     .07       0
  5487.7     .12       0
Bank Sta=4963.4,4977.2
XS Rating Curve= 0 ,0
Exp/Cntr=0.3,0.1

Type RM Length L Ch R = 1 ,7607    ,1219,1219,1219
BEGIN DESCRIPTION:
X18655
END DESCRIPTION:
XS GIS Cut Line= 3
      2274202.64      13755760.3      2274166.18     13754890.53
      2274290.91     13754178.51
#Sta/Elev= 30
  4714.7  549.56    4768  549.46  4829.8  546.55  4910.2  538.97  4980.2  527.62
  5000.3  522.14  5008.9  513.26  5009.4  512.76  5022.8  513.26  5027.1  514.65
  5050.3  520.15  5070.3  520.96  5140.4  519.52  5170.4  521.25  5200.4  518.88
  5210.4  521.11  5270.5  521.77  5611.8  520.82  5720.5  526.27  5773.6  525.82
    5785  523.15  5839.4  525.13  5875.1  530.05  5958.3  534.39  6017.7  535.67
  6057.9  534.25    6072  537.59  6169.5  542.43    6200   546.2  6308.1  551.04
#Mann= 6 ,-1 , 0
  4714.7     .05       0    4768    .035       0  4829.8     .07       0
  5008.9     .05       0  5022.8     .07       0  5027.1     .12       0
Bank Sta=5008.9,5022.8
XS Rating Curve= 0 ,0
Exp/Cntr=0.3,0.1

Type RM Length L Ch R = 1 ,6388    ,705,705,705
BEGIN DESCRIPTION:
X18656
END DESCRIPTION:
XS GIS Cut Line= 3
      2274437.02     13755666.54      2274515.14     13755380.12
      2274655.76     13754270.78
#Sta/Elev= 30
  3941.5  540.96    4030  536.56  4064.6  532.25  4109.5  528.75  4259.2  524.89
  4364.5  523.66  4385.5  521.73  4465.3  520.69  4495.5  517.47  4518.2  516.78
  4698.5  516.88  4710.1  516.83  4753.4  518.83  4828.2  517.53  4838.5  515.95
  4888.7  517.79  4969.3  517.98  4999.5  516.34  5009.6  514.54  5012.7  511.78
  5013.2  511.28  5026.7  511.78  5039.9  519.22    5060  538.53  5073.7  546.42
  5080.2  547.66  5090.3  549.17  5120.5  549.19  5346.6  561.26  5356.6  561.56
#Mann= 8 ,-1 , 0
  3941.5     .05       0  4259.2     .07       0  4385.5     .12       0
  4698.5      .1       0  4710.1     .12       0  5012.7     .05       0
  5026.7     .12       0  5346.6    .035       0
Bank Sta=5012.7,5026.7
XS Rating Curve= 0 ,0
Exp/Cntr=0.3,0.1

Type RM Length L Ch R = 1 ,5683    ,939,939,939
BEGIN DESCRIPTION:
X18657
END DESCRIPTION:
XS GIS Cut Line= 3
       2274489.1     13755703.02      2274884.93     13755031.16
       2275170.7     13754334.92
#Sta/Elev= 30
  4406.2  539.31  4584.5  528.26  4764.2  520.81  4799.1   520.6  4891.4  518.68
  4911.4  514.55  4941.7  512.61  4978.9  515.09    5009  508.84  5009.5  508.34
    5023  508.84  5043.2  513.85    5136   515.3  5172.8  515.49  5244.3  516.62
  5376.4  521.25  5447.4   529.9  5454.5  529.98  5518.9  536.03  5549.4  536.08
  5566.8  531.48  5572.2  533.76  5590.8  532.16  5619.4  536.01  5721.5  549.89
  5726.9  547.95  5750.9  551.81  5756.3  550.03  5787.2   549.4  5938.6  561.81
#Mann= 12 ,-1 , 0
  4406.2     .05       0  4764.2     .07       0  4799.1     .05       0
  4911.4     .12       0    5009     .05       0    5023     .12       0
    5136      .1       0  5172.8     .07       0  5244.3     .12       0
  5447.4     .07       0  5454.5     .12       0  5619.4     .07       0
Bank Sta=5009,5023
XS Rating Curve= 0 ,0
Exp/Cntr=0.3,0.1

Type RM Length L Ch R = 1 ,4744    ,969,969,969
BEGIN DESCRIPTION:
X18658
END DESCRIPTION:
XS GIS Cut Line= 4
      2274463.03      13756046.8      2274905.76     13755635.32
      2275171.39     13755479.07      2275619.32     13755036.34
#Sta/Elev= 30
  4505.5  533.35  4607.1  533.67  4614.4  532.13  4621.3  533.53  4628.6  530.92
  4635.4  532.38  4642.8   529.3  4649.6  531.02    4657  527.98  4663.8  529.28
  4671.1  527.21  4960.8  525.39    4975  523.45  5003.4  513.67  5010.7  509.13
  5024.6  505.91  5025.1  505.41  5038.7  505.91    5039  509.44  5046.5  510.94
  5088.4   511.6  5154.8  509.15    5167  511.17  5197.7  512.32  5283.5   511.8
  5579.1  518.74  5782.6  531.42  5883.2  540.75  5911.5  546.83  6047.9  561.33
#Mann= 5 ,-1 , 0
  4505.5    .035       0  5024.6    .035       0  5038.7    .035       0
  5046.5     .12       0  5782.6     .07       0
Bank Sta=5024.6,5038.7
XS Rating Curve= 0 ,0
Exp/Cntr=0.3,0.1

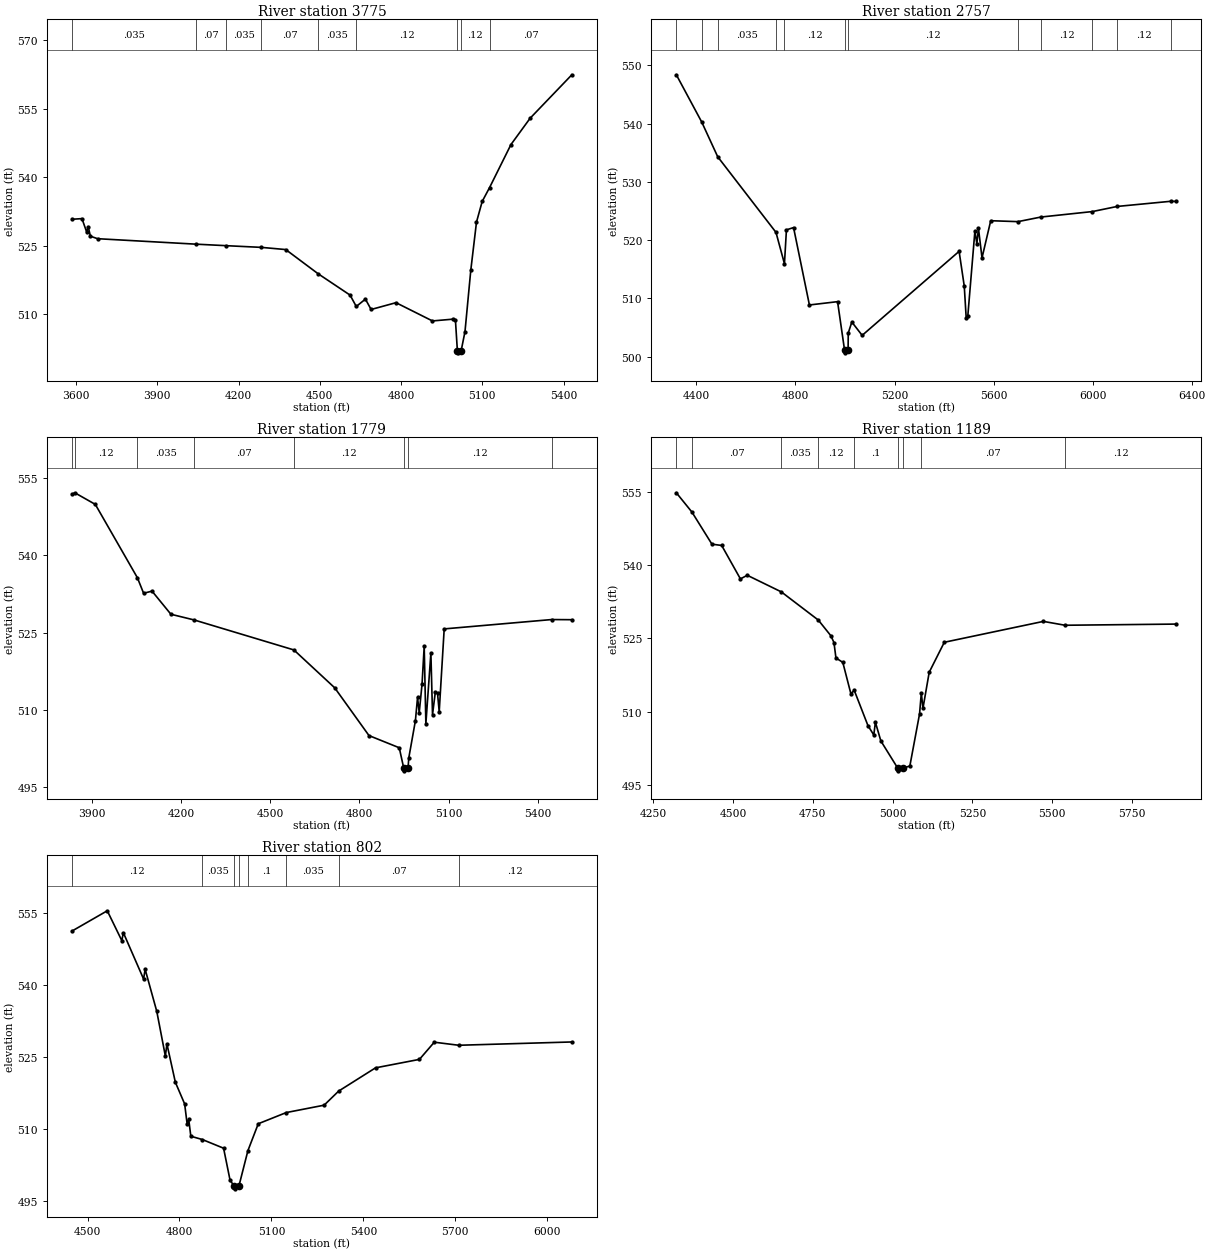
Type RM Length L Ch R = 1 ,3775    ,1018,1018,1018
BEGIN DESCRIPTION:
X18663
END DESCRIPTION:
XS GIS Cut Line= 3
      2274369.34     13756244.69      2275166.18     13756031.16
      2275874.54     13755296.76
#Sta/Elev= 30
  3585.1  530.78    3622  530.92  3639.7  527.92  3644.9  529.17  3653.1  527.07
  3679.7  526.52  4043.9  525.32  4154.9  524.99  4284.4  524.62  4374.2  524.14
  4493.5  518.85  4611.7  514.16  4634.6  511.67  4668.3  513.28  4689.4  511.01
  4781.2   512.5  4915.8   508.5  4993.5   508.9  5000.7  508.62  5007.8  502.01
  5008.3  501.51  5021.9  502.01  5035.9  506.15  5057.3   519.6  5078.4  530.16
  5099.4  534.68  5126.8  537.74  5205.7  547.16  5276.4  552.92  5430.4  562.44
#Mann= 9 ,-1 , 0
  3585.1    .035       0  4043.9     .07       0  4154.9    .035       0
  4284.4     .07       0  4493.5    .035       0  4634.6     .12       0
  5007.8     .05       0  5021.9     .12       0  5126.8     .07       0
Bank Sta=5007.8,5021.9
XS Rating Curve= 0 ,0
Exp/Cntr=0.3,0.1

Type RM Length L Ch R = 1 ,2757    ,978,978,978
BEGIN DESCRIPTION:
X18662
END DESCRIPTION:
XS GIS Cut Line= 4
      2274895.34     13756900.96      2275437.01     13756223.87
      2275817.22     13755911.37      2276468.29     13755807.19
#Sta/Elev= 30
  4318.8  548.39  4421.4  540.27  4485.9  534.31  4721.2  521.33  4755.4  515.94
  4763.4  521.76  4792.2  522.15  4856.2  508.86  4969.9  509.43    4998  501.14
  4998.5  500.64  5012.4  501.14  5013.1  504.05  5027.5  505.93  5069.2  503.64
  5460.7  518.07  5481.5  512.11  5489.4  506.58  5495.8  506.95  5524.5  521.57
  5532.4  519.37  5538.9  522.01  5553.2  516.95  5588.4  523.33  5698.3  523.17
    5791  523.96  5998.9   524.9  6099.1  525.78  6316.6  526.67  6337.4  526.64
#Mann= 12 ,-1 , 0
  4318.8     .07       0  4421.4     .12       0  4485.9    .035       0
  4721.2     .07       0  4755.4     .12       0    4998     .05       0
  5012.4     .12       0  5698.3     .07       0    5791     .12       0
  5998.9     .07       0  6099.1     .12       0  6316.6     .07       0
Bank Sta=4998,5012.4
XS Rating Curve= 0 ,0
Exp/Cntr=0.3,0.1

Type RM Length L Ch R = 1 ,1779    ,590,590,590
BEGIN DESCRIPTION:
X18661
END DESCRIPTION:
XS GIS Cut Line= 3
      2275108.87     13756999.93       2275806.8     13756312.41
       2276436.9     13755999.96
#Sta/Elev= 30
  3832.1   551.9  3841.7  552.19  3910.7  549.93  4052.3  535.67  4073.3  532.64
  4101.6  533.06  4165.2  528.56  4243.5  527.45  4579.2  521.62  4716.7  514.25
  4832.1  504.96    4934  502.59  4949.2   498.6  4949.7   498.1  4963.6   498.6
    4966  500.58  4988.4  507.86  4995.6  512.39  5001.2  509.41  5010.7  514.94
    5018  522.32  5023.6  507.25  5040.5  521.02    5046  509.03  5055.3  513.36
  5062.9  513.16  5068.5   509.6  5085.3  525.71  5447.3  527.53  5515.1   527.5
#Mann= 8 ,-1 , 0
  3832.1     .07       0  3841.7     .12       0  4052.3    .035       0
  4243.5     .07       0  4579.2     .12       0  4949.2     .05       0
  4963.6     .12       0  5447.3     .07       0
Bank Sta=4949.2,4963.6
XS Rating Curve= 0 ,0
Exp/Cntr=0.3,0.1

Type RM Length L Ch R = 1 ,1189    ,387,387,387
BEGIN DESCRIPTION:
X18660
END DESCRIPTION:
XS GIS Cut Line= 4
      2275228.71     13757062.39      2275692.22     13756791.57
       2275994.3     13756749.91      2276384.93     13756140.53
#Sta/Elev= 30
  4322.7  554.78  4371.6  550.83  4434.2  544.27  4464.7  544.01  4523.4  537.17
  4544.9  537.91  4651.4  534.52  4767.4  528.75  4806.9  525.53  4816.4  524.15
  4822.6     521  4844.1   520.1  4869.2  513.73  4880.1  514.35  4922.9  507.16
  4941.1  505.26  4946.2  507.85  4963.3  504.03  5016.6  498.42  5017.1  497.92
  5031.1  498.42  5054.1  498.92  5084.4  509.53    5090  513.83  5095.1   510.7
  5114.7  518.08    5162  524.21  5472.3  528.48  5540.1  527.69  5888.3  527.93
#Mann= 9 ,-1 , 0
  4322.7     .12       0  4371.6     .07       0  4651.4    .035       0
  4767.4     .12       0  4880.1      .1       0  5016.6     .05       0
  5031.1      .1       0    5090     .07       0  5540.1     .12       0
Bank Sta=5016.6,5031.1
XS Rating Curve= 0 ,0
Exp/Cntr=0.3,0.1

Type RM Length L Ch R = 1 ,802     ,0,0,0
BEGIN DESCRIPTION:
X18659
END DESCRIPTION:
XS GIS Cut Line= 4
      2275410.92     13757203.04      2275890.14     13757135.32
      2276124.51     13756890.53      2276426.58     13756140.56
#Sta/Elev= 30
  4449.1   551.3  4564.3  555.54  4611.8   549.3  4616.8  550.96  4682.8  541.28
  4687.9  543.31  4725.9  534.51  4753.9  525.18    4759   527.7  4786.5  519.71
  4816.8  515.19    4825  510.97  4830.1  511.95    4837  508.43  4874.7  507.74
  4943.9  505.93    4965  499.26  4979.1  497.94  4979.6  497.44  4993.6  497.94
  5023.3  505.42  5057.1  511.04  5148.6  513.38    5272  514.92  5319.6  517.87
  5439.7  522.72  5583.1  524.49  5631.5  528.08  5711.4  527.44  6080.5  528.13
#Mann= 8 ,-1 , 0
  4449.1     .12       0  4874.7    .035       0  4979.1    .035       0
  4993.6    .035       0  5023.3      .1       0  5148.6    .035       0
  5319.6     .07       0  5711.4     .12       0
Bank Sta=4979.1,4993.6
XS Rating Curve= 0 ,0
Exp/Cntr=0.3,0.1

Chan Stop Cuts=-1
Use User Specified Reach Order=0
Composite Channel Slope=5