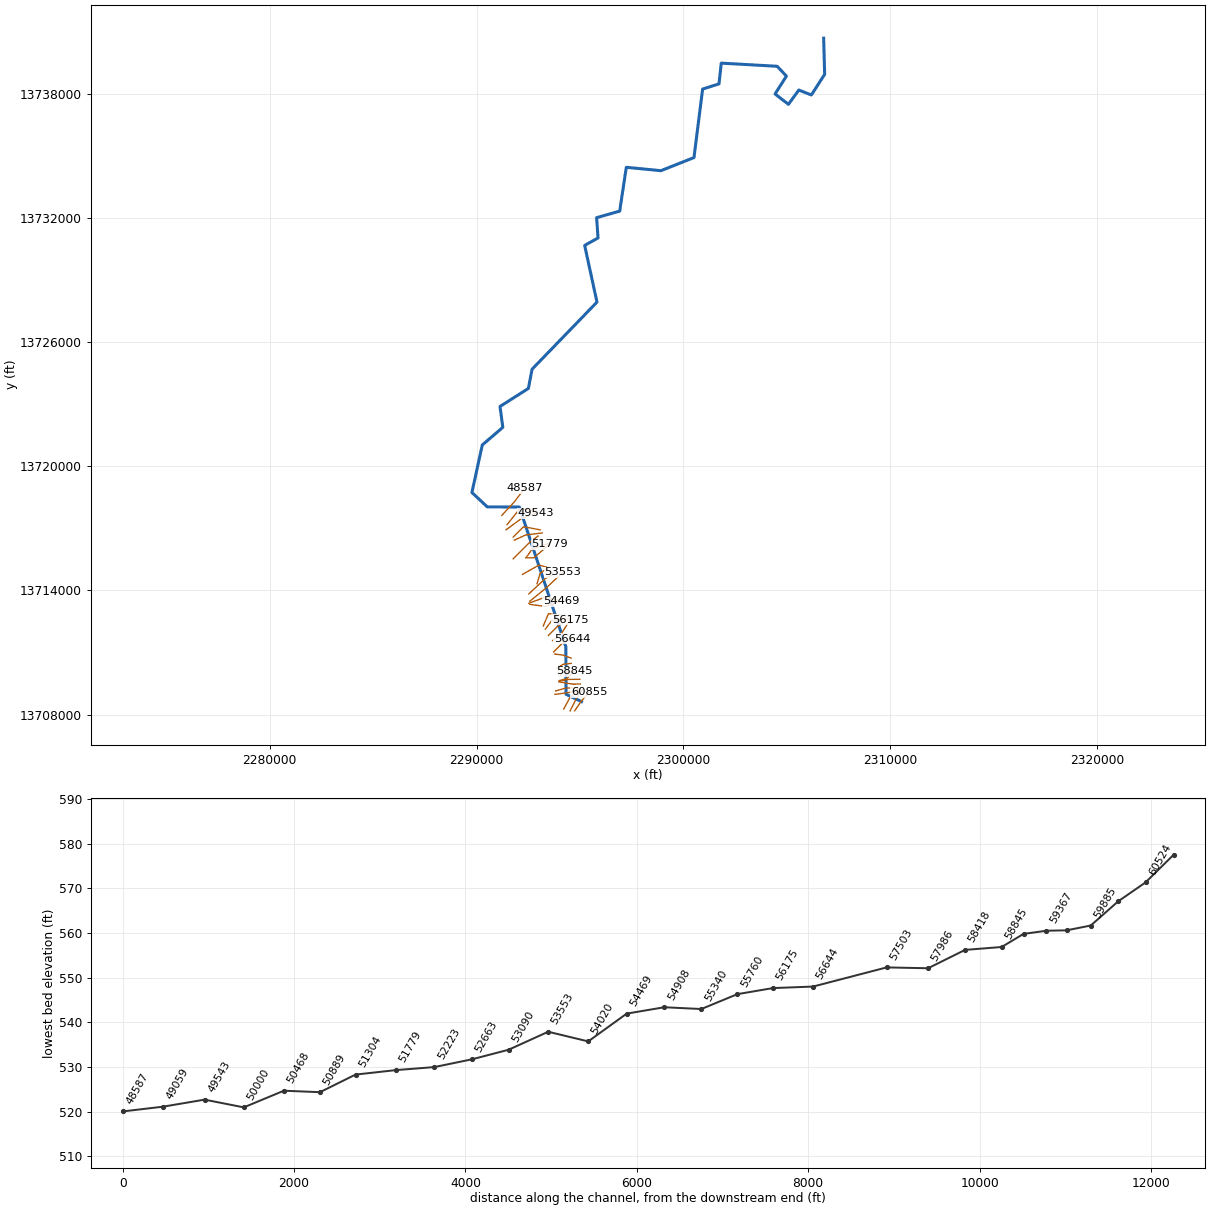
--- COTTONWOOD CREEK SOUTH.prj (project) ---

Proj Title=COTTONWOOD CREEK SOUTH Base Level Engineering
Current Plan=p01
Default Exp/Contr=0.3,0.1
English Units
Geom File=g01
Flow File=f01
Plan File=p01
Y Axis Title=Elevation
X Axis Title(PF)=Main Channel Distance
X Axis Title(XS)=Station
BEGIN DESCRIPTION:
COTTONWOOD CREEK SOUTH
END DESCRIPTION:
DSS Export Rating Curves= 0
DSS Export Rating Curve Sorted= 0
DSS Export Volume Flow Curves= 0
DXF OffsetX= 0
DXF OffsetY= 0
DXF ScaleX= 1
DXF ScaleY= 10

--- COTTONWOOD CREEK SOUTH.p01 (plan) ---

Plan Title=Multiple Run
Program Version=4.10
Short Identifier=Multiple
Geom File=g01
Flow File=f01
Subcritical Flow
K Sum by GR= 0
Std Step Tol= 0.01
Critical Tol= 0.01
Num of Std Step Trials= 20
Max Error Tol= 0.3
Flow Tol Ratio= 0.001
Split Flow NTrial= 30
Split Flow Tol= 0.02
Split Flow Ratio= 0.02
Log Output Level= 0
Friction Slope Method= 1
Unsteady Friction Slope Method= 2
Unsteady Bridges Friction Slope Method= 1
Parabolic Critical Depth
Global Vel Dist= 1 , 1 , 1
Global Log Level= 0
CheckData=True
Encroach Param=-1 ,0,0, 0
BEGIN DESCRIPTION:
Multiple Run
END DESCRIPTION:
Computation Interval=1HOUR
Output Interval=1HOUR
Run HTab= 0
Run UNet= 0
Run PostProcess= 0
Run WQNet= 0
UNET Theta= 1
UNET Theta Warmup= 1
UNET ZTol= 0.02
UNET ZSATol= 0.05
UNET MxIter= 20
UNET MaxInSteps= 0
UNET DtIC= 0
UNET DtMin= 0
UNET MaxCRTS= 20
UNET WFStab= 2
UNET SFStab= 1
UNET WFX= 1
UNET SFX= 1
UNET DSS MLevel= 4
UNET DZMax Abort= 100
UNET Convert EG Bridges= 0
UNET Use Existing IB Tables=-1
UNET Froude Reduction=False
UNET Froude Limit= 1
UNET Froude Power= 10
UNET Time Slicing=0,0, 5
UNET Junction Losses=0
Instantaneous Interval=1HOUR
Write IC File= 0
Write IC File at Sim End=0
Echo Input=False
Echo Parameters=False
Echo Output=False
Write Detailed= 0
WQ AD Non Conservative
WQ ULTIMATE=-1
WQ Max Comp Step=1HOUR
WQ Output Interval=15MIN
WQ Output Selected Increments= 0
WQ Output face flow=0
WQ Output face velocity=0
WQ Output face area=0
WQ Output face dispersion=0
WQ Output cell volume=0
WQ Output cell surface area=0
WQ Output cell continuity=0
WQ Output cumulative cell continuity=0
WQ Output face conc=0
WQ Output face dconc_dx=0
WQ Output face courant=0
WQ Output face peclet=0
WQ Output face adv mass=0
WQ Output face disp mass=0
WQ Output cell mass=0
WQ Output cell source sink temp=0
WQ Output cell source sink nsm=0
WQ Output MaxMinRange=-1
WQ Daily Max Min Mean=-1
WQ Daily Range=0
WQ Daily Time=0
WQ Create Restart=0
WQ Fixed Restart=0
WQ System Summary=0
WQ Use Fixed Temperature=0
Sorting and Armoring Iterations= 10
XS Update Threshold= 0.02
Hydraulics Update Threshold= 0.02
Energy Slope Method= 1
Volume Change Method= 0
XS Weighting Method= 0
Number of US Weighted Cross Sections= 1
Number of DS Weighted Cross Sections= 1
Upstream XS Weight=0.25
Main XS Weight=0.5
Downstream XS Weight=0.25
Number of DS XS's Weighted with US Boundary= 1
Upstream Boundary Weight= 1
Weight of XSs Associated with US Boundary= 0
Number of US XS's Weighted with DS Boundary= 1
Downstream Boundary Weight= 0.5
Weight of XSs Associated with DS Boundary= 0.5
Sediment Output Level= 4
Mass or Volume Output= 0
Output Increment Type= 1
Profile and TS Output Increment= 10
XS Output Flag= 0
XS Output Increment= 10
Disregard all LS=0
Disregard all Conn=0
Disregard all Breaches=0
Disregard all Pumps=0

--- COTTONWOOD CREEK SOUTH.f01 (steady flow) ---

Flow Title=Multiple
Number of Profiles=7
Profile Names=10-year,25-year,50-year,1pct_min,100-year,1pct_plu,500-year
River Rch & RM= COTTONWOOD CREEK,Reach-1,60855
     767    1270    1736    1150    2294    4578    3973
River Rch & RM= COTTONWOOD CREEK,Reach-1,56644
    1097    1845    2549    1703    3398    6780    5990
River Rch & RM= COTTONWOOD CREEK,Reach-1,54020
    1349    2281    3161    2115    4221    8422    7469
River Rch & RM= COTTONWOOD CREEK,Reach-1,49059
    1343    2264    3130    2090    4170    8320    7345
River Rch & RM= COTTONWOOD CREEK,Reach-1,46529
    1523    2581    3581    2398    4785    9547    8477
River Rch & RM= COTTONWOOD CREEK,Reach-1,46016
    2059    3497    4860    3255    6494   12958   11508
River Rch & RM= COTTONWOOD CREEK,Reach-1,37394
    2190    3721    5171    3462    6908   13783   12231
River Rch & RM= COTTONWOOD CREEK,Reach-1,31393
    4198    7384   10508    7198   14363   28658   26623
River Rch & RM= COTTONWOOD CREEK,Reach-1,29704
    5906   10447   14925   10254   20459   40821   38126
River Rch & RM= COTTONWOOD CREEK,Reach-1,20189
    5877   10373   14796   10148   20248   40400   37607
River Rch & RM= COTTONWOOD CREEK,Reach-1,15853
    5860   10305   14662   10028   20009   39924   36958
River Rch & RM= COTTONWOOD CREEK,Reach-1,10422
    6125   10740   15251   10408   20768   41437   38185
Boundary for River Rch & Prof#=COTTONWOOD CREEK,Reach-1,1
Up Type=0
Dn Type=3
Dn Slope=0.0015
Boundary for River Rch & Prof#=COTTONWOOD CREEK,Reach-1,2
Up Type=0
Dn Type=3
Dn Slope=0.0015
Boundary for River Rch & Prof#=COTTONWOOD CREEK,Reach-1,3
Up Type=0
Dn Type=3
Dn Slope=0.0015
Boundary for River Rch & Prof#=COTTONWOOD CREEK,Reach-1,4
Up Type=0
Dn Type=3
Dn Slope=0.0015
Boundary for River Rch & Prof#=COTTONWOOD CREEK,Reach-1,5
Up Type=0
Dn Type=3
Dn Slope=0.0015
Boundary for River Rch & Prof#=COTTONWOOD CREEK,Reach-1,6
Up Type=0
Dn Type=3
Dn Slope=0.0015
Boundary for River Rch & Prof#=COTTONWOOD CREEK,Reach-1,7
Up Type=0
Dn Type=3
Dn Slope=0.0015

--- COTTONWOOD CREEK SOUTH.g01 (geometry) ---

Geom Title=Existing Conditions
Program Version=4.10

River Reach=COTTONWOOD CREEK,Reach-1
Reach XY= 30
        2295075.       13708625.      2294326.98     13708980.67
      2294317.42     13711278.33      2292069.53     13718027.45
      2290521.71     13718033.05      2289778.69     13718726.53
      2290278.55     13721023.53      2291271.46     13721876.46
      2291135.75      13722884.7      2292505.55     13723754.23
      2292685.35     13724685.12      2295821.71     13727926.36
      2295226.03     13730664.57      2295871.49     13731026.25
      2295804.53     13732005.38      2296919.55     13732322.53
      2297238.22     13734438.67      2298909.73     13734275.38
      2300508.61     13734908.21      2300927.06     13738219.15
      2301717.33     13738468.48      2301826.58     13739471.18
      2304527.45     13739319.54      2304975.39     13738845.28
      2304426.74     13737981.16      2305071.87      13737482.5
      2305576.73     13738171.69      2306181.06     13737933.14
      2306823.02     13738930.67        2306775.       13740675.

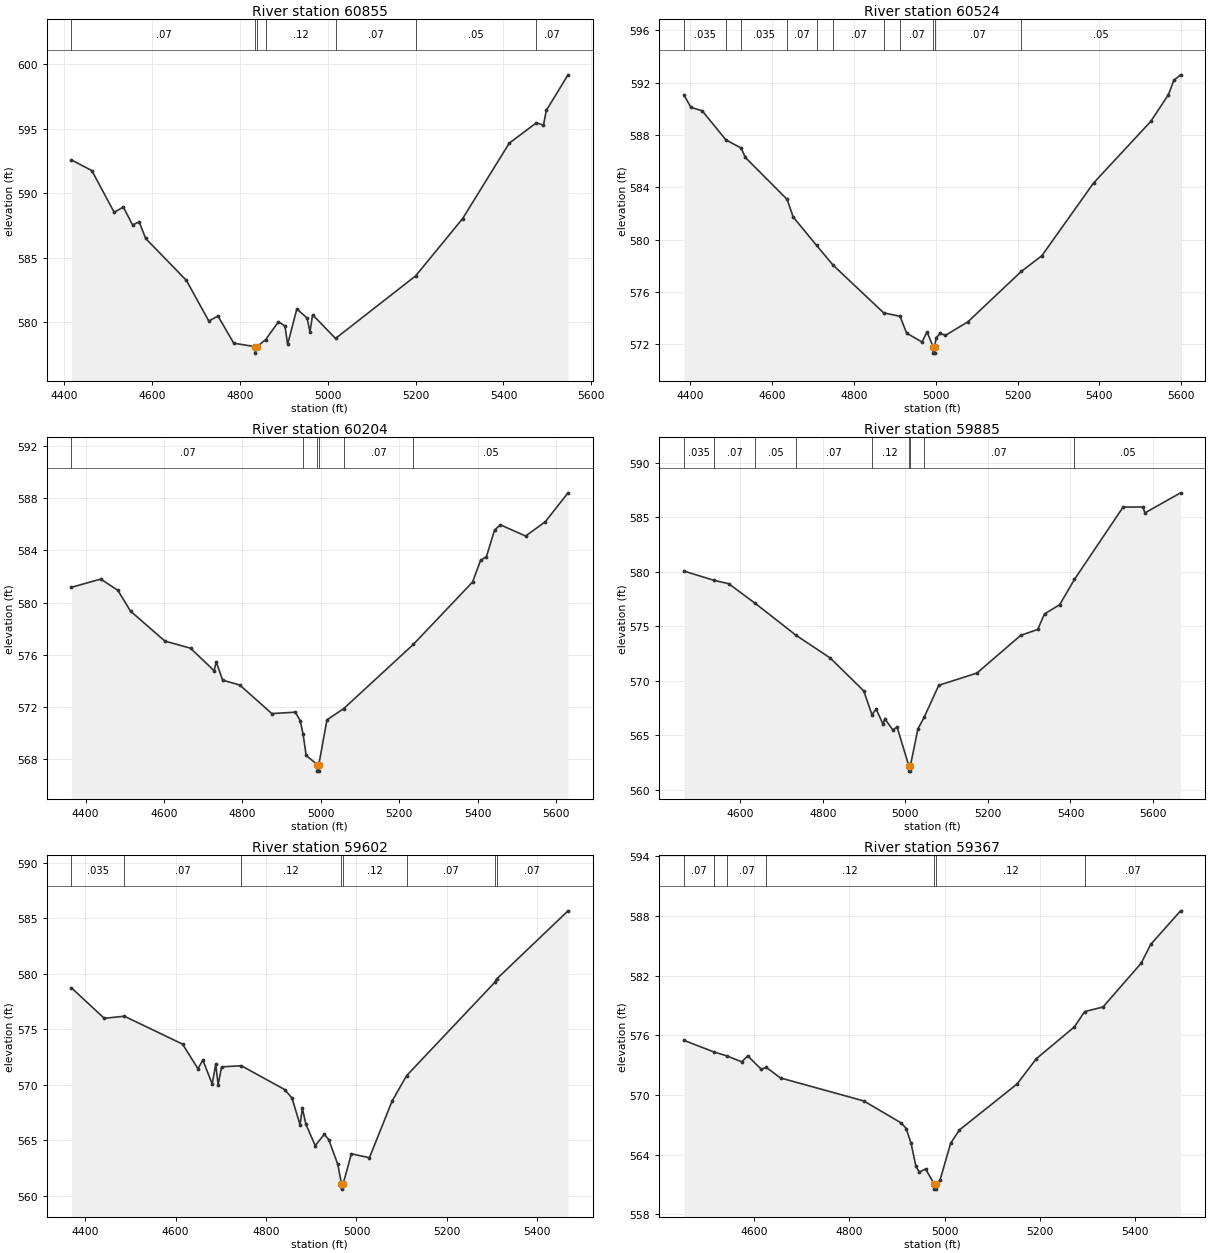
Type RM Length L Ch R = 1 ,60855   ,331,331,331
BEGIN DESCRIPTION:
X18639
END DESCRIPTION:
XS GIS Cut Line= 3
      2294744.03     13708181.61      2295060.74     13708646.89
      2295436.12     13709073.11
#Sta/Elev= 30
  4416.2  592.58  4462.5  591.76  4513.4  588.52  4534.3  588.93  4555.3  587.54
  4570.3  587.78  4585.2  586.49    4678  583.23  4728.9  580.08  4749.8  580.47
  4785.8  578.36  4834.6  578.09  4834.9  577.59  4838.6  578.09  4858.4  578.64
  4887.5  580.02  4902.4   579.7  4908.4  578.27  4929.4  581.02  4952.6  580.32
  4959.3  579.25  4965.3  580.57  5017.5  578.73  5199.8  583.58  5306.9  588.03
  5413.2  593.89  5475.2  595.47    5491  595.28  5497.6  596.43    5547  599.19
#Mann= 7 ,-1 , 0
  4416.2     .07       0  4834.6     .05       0  4838.6     .07       0
  4858.4     .12       0  5017.5     .07       0  5199.8     .05       0
  5475.2     .07       0
Bank Sta=4834.6,4838.6
XS Rating Curve= 0 ,0
Exp/Cntr=0.3,0.1

Type RM Length L Ch R = 1 ,60524   ,320,320,320
BEGIN DESCRIPTION:
X18638
END DESCRIPTION:
XS GIS Cut Line= 3
      2294521.15     13708177.71      2294919.97     13708955.79
      2295135.04     13709217.79
#Sta/Elev= 30
    4385  591.05  4401.6  590.12  4429.4  589.85  4487.6  587.62  4524.5  587.01
  4534.8  586.29  4636.8  583.09  4651.6  581.74  4708.8  579.57  4749.2  578.06
  4872.7  574.42  4912.9  574.15  4928.8  572.87  4966.3  572.19  4978.8  572.96
  4993.4  571.84  4993.6  571.34  4997.1  571.34  4997.4  571.84    5001  572.51
  5011.2  572.86  5023.2  572.69  5078.5  573.73    5209  577.58  5259.3  578.78
  5385.5  584.33  5525.4  589.04  5568.5  591.08  5581.8  592.18  5598.3   592.6
#Mann= 11 ,-1 , 0
    4385    .035       0  4487.6     .07       0  4524.5    .035       0
  4636.8     .07       0  4708.8    .035       0  4749.2     .07       0
  4872.7     .12       0  4912.9     .07       0  4993.4     .05       0
  4997.4     .07       0    5209     .05       0
Bank Sta=4993.4,4997.4
XS Rating Curve= 0 ,0
Exp/Cntr=0.3,0.1

Type RM Length L Ch R = 1 ,60204   ,319,319,319
BEGIN DESCRIPTION:
X18637
END DESCRIPTION:
XS GIS Cut Line= 3
      2294216.16     13708271.55      2294528.96     13708850.22
      2295017.72     13709213.86
#Sta/Elev= 30
  4363.9  581.18  4438.4  581.81  4482.2  580.95  4514.6  579.35  4602.1  577.06
  4667.7  576.51  4727.7  574.79  4733.4  575.46  4749.6  574.06  4793.3  573.69
  4875.2   571.5  4935.1  571.61  4947.6  570.96    4955   569.9  4962.7  568.29
    4991  567.59  4991.3  567.09  4994.8  567.09    4995  567.59  5015.8  571.02
  5058.4  571.88  5236.1   576.8  5387.2  581.58    5408  583.26  5422.6  583.52
  5443.5  585.57  5458.1  585.97  5522.7  585.11  5572.8   586.2  5630.9  588.42
#Mann= 6 ,-1 , 0
  4363.9     .07       0    4955     .12       0    4991     .05       0
    4995     .12       0  5058.4     .07       0  5236.1     .05       0
Bank Sta=4991,4995
XS Rating Curve= 0 ,0
Exp/Cntr=0.3,0.1

Type RM Length L Ch R = 1 ,59885   ,283,283,283
BEGIN DESCRIPTION:
X18636
END DESCRIPTION:
XS GIS Cut Line= 3
      2293793.87     13708975.35      2294603.25     13709084.83
      2294959.03      13709233.4
#Sta/Elev= 30
  4464.3  580.06  4537.1  579.21  4572.5   578.9    4636  577.12    4735  574.18
  4818.6  572.07  4899.4  569.06  4919.2  566.88  4929.6  567.38  4945.7  566.03
  4950.7  566.48    4970  565.47  4980.1  565.75  5008.4  562.19  5008.6  561.69
  5012.1  561.69  5012.4  562.19  5030.5  565.56  5045.7  566.64    5081  569.57
  5173.6   570.7  5279.4  574.16  5320.6   574.7  5337.1  576.13  5373.7  576.97
  5409.6   579.3  5527.4  585.94    5575  585.95  5580.4  585.41  5666.6  587.25
#Mann= 9 ,-1 , 0
  4464.3    .035       0  4537.1     .07       0    4636     .05       0
    4735     .07       0  4919.2     .12       0  5008.4     .05       0
  5012.4     .12       0  5045.7     .07       0  5409.6     .05       0
Bank Sta=5008.4,5012.4
XS Rating Curve= 0 ,0
Exp/Cntr=0.3,0.1

Type RM Length L Ch R = 1 ,59602   ,235,235,235
BEGIN DESCRIPTION:
X18635
END DESCRIPTION:
XS GIS Cut Line= 3
      2293825.12     13709143.48      2294329.54     13709284.25
      2294904.29     13709292.07
#Sta/Elev= 30
  4369.6  578.73  4442.2  575.99  4486.5  576.18  4615.3  573.67  4649.4  571.45
  4660.2  572.23  4680.9  570.08  4688.8  571.87    4694  569.99  4701.7  571.62
  4745.3  571.72  4841.1  569.58  4857.4  568.81  4875.2  566.42  4880.4  567.88
  4888.3  566.44  4908.8  564.53  4928.8  565.54  4938.8  565.07  4958.8  562.83
  4966.8  561.11    4967  560.61  4970.8  561.11  4988.8  563.79  5028.8  563.44
  5078.8  568.53  5110.8  570.82  5306.5  579.25  5309.9  579.52  5468.1  585.67
#Mann= 8 ,-1 , 0
  4369.6    .035       0  4486.5     .07       0  4745.3     .12       0
  4966.8     .05       0  4970.8     .12       0  5110.8     .07       0
  5306.5     .05       0  5309.9     .07       0
Bank Sta=4966.8,4970.8
XS Rating Curve= 0 ,0
Exp/Cntr=0.3,0.1

Type RM Length L Ch R = 1 ,59367   ,267,267,267
BEGIN DESCRIPTION:
X18634
END DESCRIPTION:
XS GIS Cut Line= 3
      2293985.42     13709581.42      2294642.35     13709471.93
      2295017.73     13709475.85
#Sta/Elev= 30
  4453.4  575.49  4516.4  574.32  4542.5  573.94  4574.6  573.33  4586.8  573.94
  4615.2  572.59    4626  572.77  4655.7  571.71  4830.1   569.4  4909.2  567.17
  4919.3  566.62  4929.5  565.13  4939.6  562.85  4946.7  562.23  4959.9  562.55
  4978.2  561.02  4978.4  560.52  4981.9  560.52  4982.2  561.02  4990.3  561.44
  5012.6  565.15  5030.8  566.47    5152  571.11  5192.1  573.64  5272.1  576.85
  5293.7  578.39  5332.1  578.85  5412.1  583.26  5432.1  585.15  5494.8  588.53
#Mann= 7 ,-1 , 0
  4453.4     .07       0  4516.4     .12       0  4542.5     .07       0
    4626     .12       0  4978.2     .05       0  4982.2     .12       0
  5293.7     .07       0
Bank Sta=4978.2,4982.2
XS Rating Curve= 0 ,0
Exp/Cntr=0.3,0.1

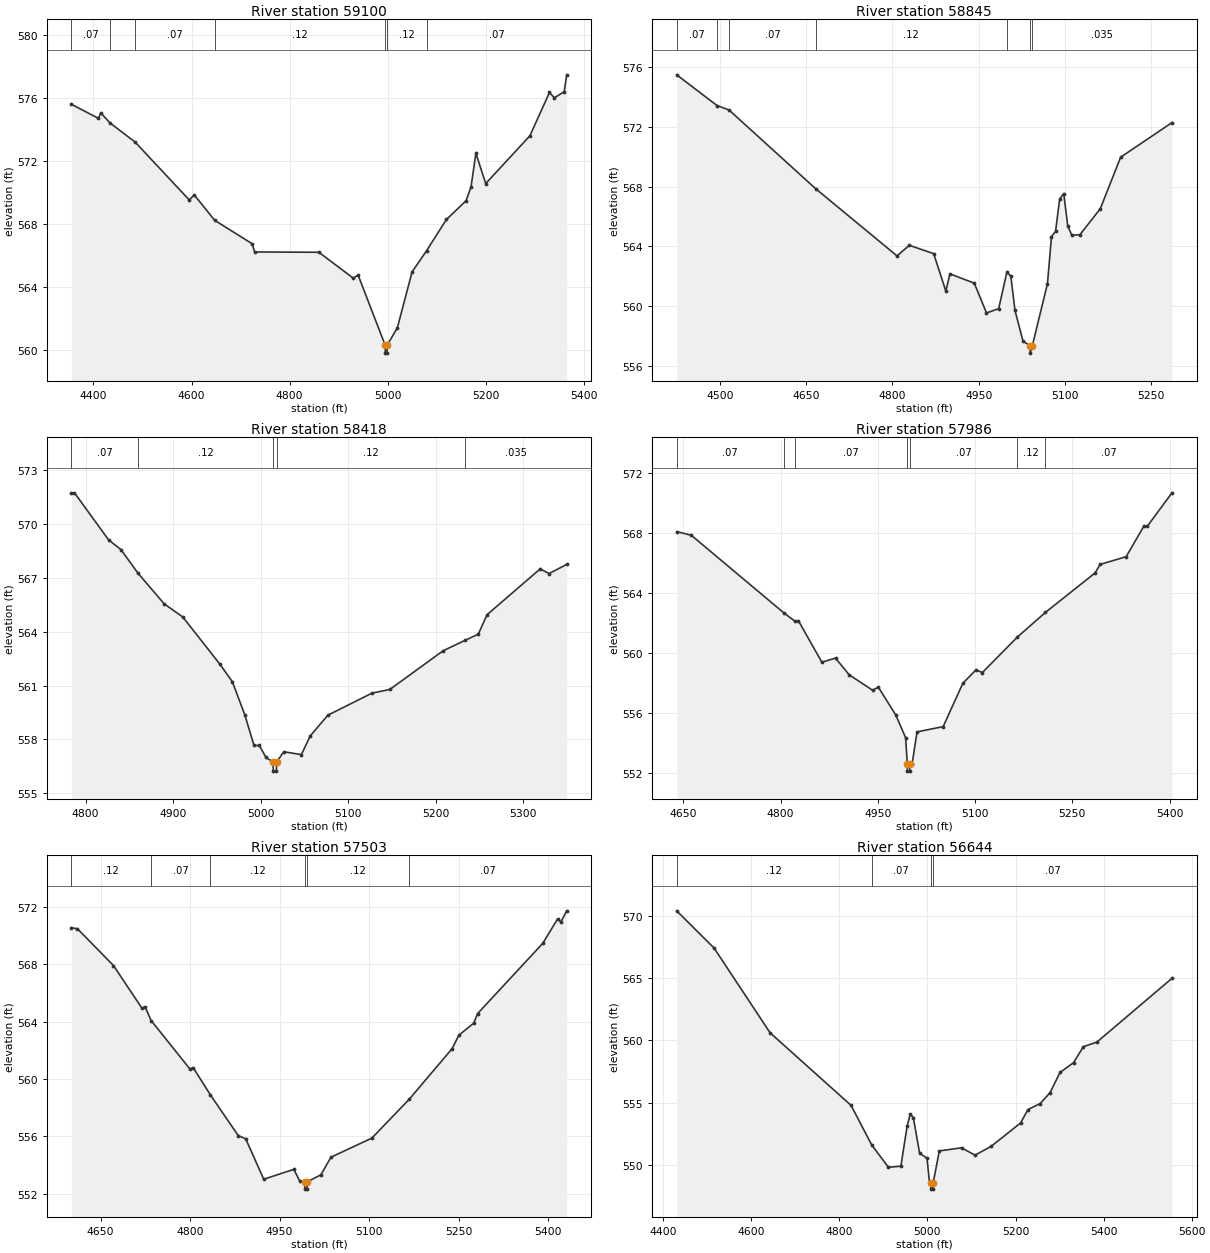
Type RM Length L Ch R = 1 ,59100   ,255,255,255
BEGIN DESCRIPTION:
X18633
END DESCRIPTION:
XS GIS Cut Line= 3
      2293989.31     13709608.78      2294446.84     13709698.72
      2294990.14     13709702.63
#Sta/Elev= 30
  4355.2   575.6  4410.1  574.71  4415.2  575.05  4433.7  574.42  4484.8  573.21
  4595.4  569.53  4605.6  569.85  4647.1  568.24  4723.6  566.75  4728.7  566.23
  4859.6  566.21  4929.6  564.57  4939.6  564.76  4994.8  560.31    4995  559.81
  4998.5  559.81  4998.8  560.31  5019.6  561.42  5049.6  564.96  5079.4  566.32
  5119.6  568.29  5159.7  569.48  5169.7  570.35  5179.7  572.49  5199.7  570.57
  5289.7   573.6  5329.7  576.35  5339.7  576.01  5359.7   576.4  5364.8  577.47
#Mann= 7 ,-1 , 0
  4355.2     .07       0  4433.7     .12       0  4484.8     .07       0
  4647.1     .12       0  4994.8     .05       0  4998.8     .12       0
  5079.4     .07       0
Bank Sta=4994.8,4998.8
XS Rating Curve= 0 ,0
Exp/Cntr=0.3,0.1

Type RM Length L Ch R = 1 ,58845   ,427,427,427
BEGIN DESCRIPTION:
X18632
END DESCRIPTION:
XS GIS Cut Line= 3
      2294012.79     13709647.89      2294360.82     13709733.92
      2294716.63     13710089.73
#Sta/Elev= 30
  4424.6  575.46  4494.8  573.41  4515.7  573.11  4666.3  567.86    4808  563.37
  4829.3  564.08  4871.7  563.52  4892.9  561.02    4900  562.17  4942.4  561.55
  4963.6  559.56  4984.8  559.85  4999.1  562.29    5006  562.01  5013.1  559.74
  5027.2  557.67  5039.4  557.38  5039.6  556.88  5043.4  557.38  5069.7  561.52
  5076.7  564.66  5083.8  565.01  5090.9  567.17    5098  567.53    5105  565.37
  5112.1  564.74  5126.2  564.79  5161.6  566.52    5197  569.96  5286.3  572.27
#Mann= 7 ,-1 , 0
  4424.6     .07       0  4494.8     .12       0  4515.7     .07       0
  4666.3     .12       0  4999.1    .035       0  5039.4    .035       0
  5043.4    .035       0
Bank Sta=5039.4,5043.4
XS Rating Curve= 0 ,0
Exp/Cntr=0.3,0.1

Type RM Length L Ch R = 1 ,58418   ,432,432,432
BEGIN DESCRIPTION:
COTTONWOOD CREEK SOUTH 109.0
END DESCRIPTION:
XS GIS Cut Line= 3
      2294025.03     13709875.03        2294175.       13710025.
      2294524.96     13710074.99
#Sta/Elev= 30
  4783.9  571.74  4787.4  571.74  4826.3  569.12  4840.4  568.58  4859.9  567.26
  4889.9  565.55  4911.1  564.82  4953.6  562.18  4967.7  561.21  4981.8  559.38
  4992.4  557.66  4998.5  557.66  5006.1  556.99  5014.2  556.73  5014.4  556.23
  5017.9  556.23  5018.2  556.73  5026.3  557.31  5046.5  557.15  5056.6  558.19
  5076.8  559.35  5127.3  560.58  5147.5  560.78  5208.1  562.93  5233.4  563.52
  5248.5  563.86  5258.6  564.95  5319.2   567.5  5329.3  567.24  5349.5  567.75
#Mann= 5 ,-1 , 0
  4783.9     .07       0  4859.9     .12       0  5014.2     .05       0
  5018.2     .12       0  5233.4    .035       0
Bank Sta=5014.2,5018.2
XS Rating Curve= 0 ,0
Exp/Cntr=0.3,0.1

Type RM Length L Ch R = 1 ,57986   ,483,483,483
BEGIN DESCRIPTION:
COTTONWOOD CREEK SOUTH 108.0
END DESCRIPTION:
XS GIS Cut Line= 3
        2293875.       13710225.        2294175.       13710425.
      2294575.03       13710475.
#Sta/Elev= 30
  4639.9   568.1  4662.4  567.86  4805.1  562.68  4822.1  562.13  4827.7  562.15
  4863.7  559.39  4884.8  559.66  4905.8  558.55  4941.9  557.52  4950.9  557.72
  4977.9  555.85  4992.9  554.35  4995.5  552.62  4995.7  552.12  4999.2  552.12
  4999.5  552.62    5003  552.62  5010.5  554.74  5050.8  555.09  5081.1  557.98
  5101.2  558.87  5111.3   558.7  5165.1  561.06  5208.5  562.71  5285.2  565.35
  5292.7  565.91    5333  566.43  5360.7   568.5  5365.8  568.47  5403.6  570.69
#Mann= 7 ,-1 , 0
  4639.9     .07       0  4805.1     .12       0  4822.1     .07       0
  4995.5     .05       0  4999.5     .07       0  5165.1     .12       0
  5208.5     .07       0
Bank Sta=4995.5,4999.5
XS Rating Curve= 0 ,0
Exp/Cntr=0.3,0.1

Type RM Length L Ch R = 1 ,57503   ,859,859,859
BEGIN DESCRIPTION:
COTTONWOOD CREEK SOUTH 107.0
END DESCRIPTION:
XS GIS Cut Line= 3
      2293775.04     13710924.99        2294175.       13710875.
      2294575.03     13710724.99
#Sta/Elev= 30
    4601  570.56    4611  570.49  4671.5  567.92  4719.4  564.93  4724.4  565.05
  4734.6  564.08    4800  560.68    4805   560.8  4834.1  558.88  4880.6  556.05
  4893.2  555.82  4923.4     553  4973.8  553.69  4983.9  552.86  4991.9  552.81
  4992.2  552.31  4995.8  552.31    4996  552.81  5019.2  553.31  5036.1  554.54
  5104.6  555.87  5167.2  558.58    5239  562.11  5250.6  563.06  5275.5   563.9
  5281.8  564.56  5391.2  569.47  5416.1  571.18  5421.5  570.96  5431.3  571.74
#Mann= 6 ,-1 , 0
    4601     .12       0  4734.6     .07       0  4834.1     .12       0
  4991.9     .05       0    4996     .12       0  5167.2     .07       0
Bank Sta=4991.9,4996
XS Rating Curve= 0 ,0
Exp/Cntr=0.3,0.1

Type RM Length L Ch R = 1 ,56644   ,469,469,469
BEGIN DESCRIPTION:
COTTONWOOD CREEK SOUTH 106.0
END DESCRIPTION:
XS GIS Cut Line= 3
      2293724.99     13711024.99        2294125.       13711425.
      2294624.99     13711674.99
#Sta/Elev= 30
  4430.6  570.45  4515.5  567.45  4642.7  560.62  4826.6  554.77  4873.5  551.58
  4911.4  549.78  4939.7  549.87  4953.9   553.1  4960.9  554.06    4968  553.79
  4982.2  550.92  4999.1   550.5  5004.7  548.53  5007.5  548.52    5008  548.02
  5012.6  548.02    5013  548.52    5027   551.1  5077.4  551.35  5108.1  550.76
  5144.4  551.46  5211.5  553.35  5228.3  554.43  5256.2  554.92  5278.6   555.8
    5301  557.42  5331.7  558.21  5354.1   559.5  5384.8  559.87  5555.3  565.01
#Mann= 4 ,-1 , 0
  4430.6     .12       0  4873.5     .07       0  5007.5     .05       0
    5013     .07       0
Bank Sta=5007.5,5013
XS Rating Curve= 0 ,0
Exp/Cntr=0.3,0.1

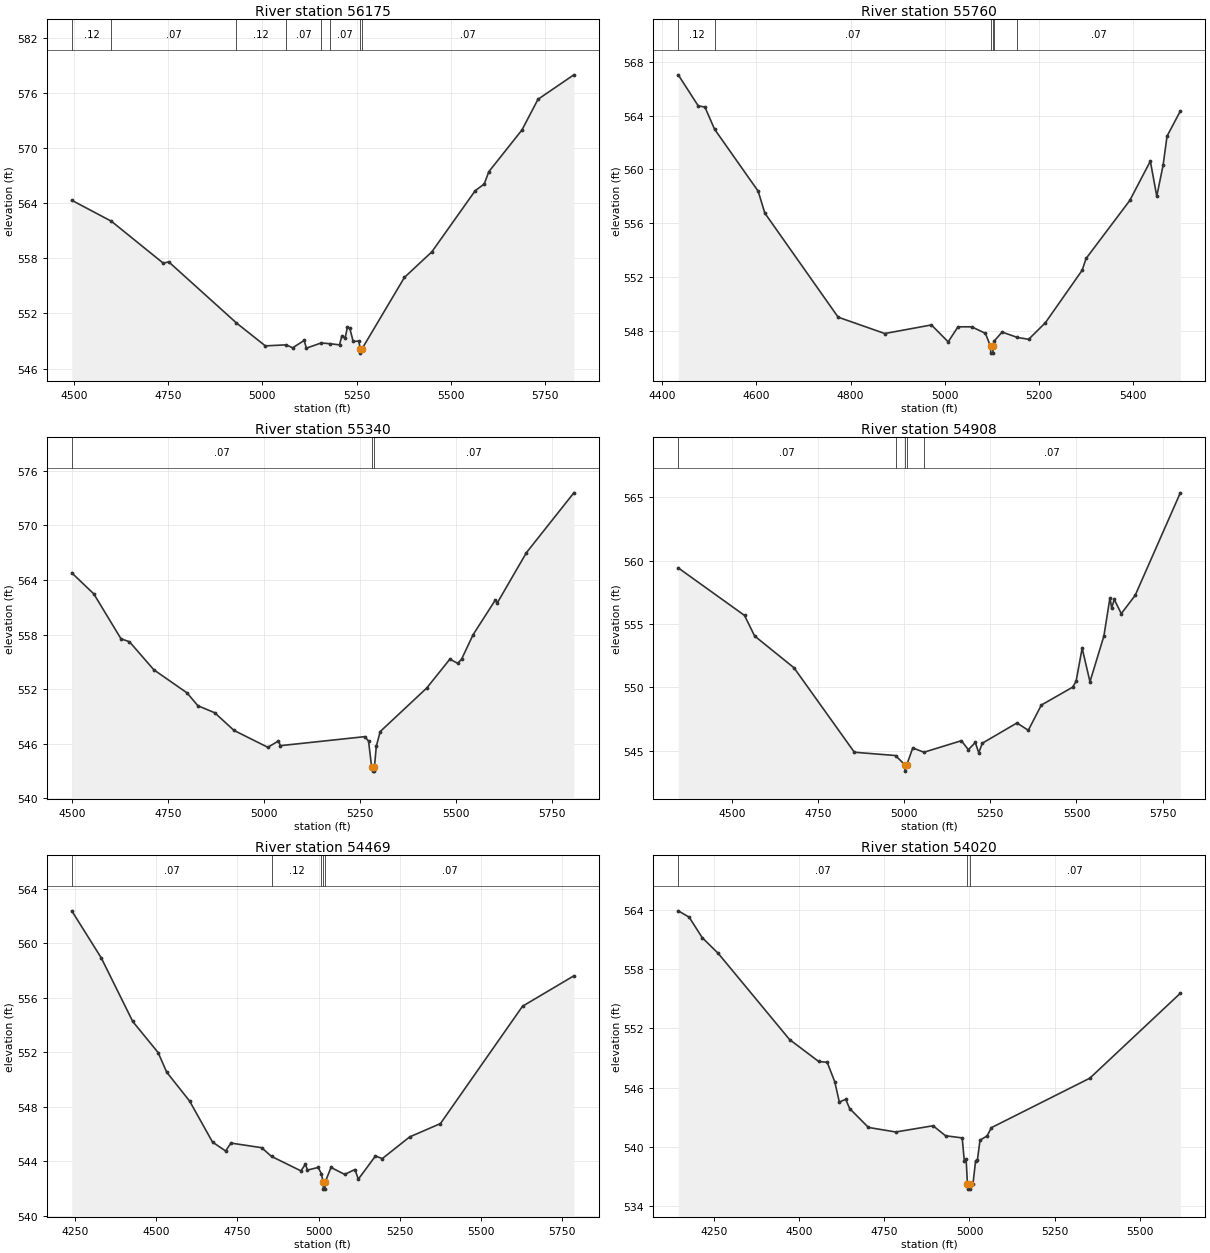
Type RM Length L Ch R = 1 ,56175   ,415,415,415
BEGIN DESCRIPTION:
COTTONWOOD CREEK SOUTH 105.0
END DESCRIPTION:
XS GIS Cut Line= 3
      2293674.99     13711574.99        2294075.       13711875.
      2294525.01     13712575.02
#Sta/Elev= 30
  4494.2  564.31  4599.3  562.03  4736.9  557.47  4751.5  557.61  4931.2  550.96
  5007.8  548.47  5062.7  548.58  5080.4  548.26  5110.8  549.06  5116.7  548.22
  5156.1  548.79  5180.2   548.7  5204.6  548.58  5210.5   549.5  5219.8  549.38
  5225.7  550.51    5232  550.36  5240.9  548.95  5255.8  548.99  5259.3  548.18
  5259.7  547.68  5264.8  548.18  5376.9  555.92  5449.6   558.7  5564.8  565.36
  5588.6  566.08  5600.8  567.42  5688.7  571.96  5731.3   575.3  5826.4  577.96
#Mann= 8 ,-1 , 0
  4494.2     .12       0  4599.3     .07       0  4931.2     .12       0
  5062.7     .07       0  5156.1     .12       0  5180.2     .07       0
  5259.3     .05       0  5264.8     .07       0
Bank Sta=5259.3,5264.8
XS Rating Curve= 0 ,0
Exp/Cntr=0.3,0.1

Type RM Length L Ch R = 1 ,55760   ,420,420,420
BEGIN DESCRIPTION:
COTTONWOOD CREEK SOUTH 104.0
END DESCRIPTION:
XS GIS Cut Line= 3
      2293475.01     13711825.01        2293875.       13712225.
      2294275.02     13712525.02
#Sta/Elev= 30
  4434.3  567.05  4476.7  564.74  4490.9  564.65  4511.4     563    4604  558.38
  4618.1  556.75  4773.7     549  4872.7  547.78  4971.7  548.42  5007.3  547.16
  5028.1  548.28  5057.3  548.28  5086.4  547.79  5097.2  546.82  5097.7  546.32
  5102.3  546.32  5102.7  546.82  5105.4  547.24  5121.8  547.89  5153.9  547.49
  5178.1  547.35  5213.5  548.58  5291.6  552.49    5300  553.37  5392.7  557.69
  5436.4  560.62    5450  558.01  5463.5  560.32  5471.8  562.48    5500  564.35
#Mann= 6 ,-1 , 0
  4434.3     .12       0  4511.4     .07       0  5097.2     .05       0
  5102.7     .07       0  5105.4     .12       0  5153.9     .07       0
Bank Sta=5097.2,5102.7
XS Rating Curve= 0 ,0
Exp/Cntr=0.3,0.1

Type RM Length L Ch R = 1 ,55340   ,432,432,432
BEGIN DESCRIPTION:
COTTONWOOD CREEK SOUTH 103.0
END DESCRIPTION:
XS GIS Cut Line= 3
      2293324.99     13712124.99        2293625.       13712525.
      2294424.96     13712624.99
#Sta/Elev= 30
  4500.2  564.79  4557.5  562.48  4628.3  557.54  4650.2  557.22  4713.8  554.13
  4800.2  551.59  4828.3  550.18  4872.1  549.41  4922.1  547.47  5010.3  545.61
    5038  546.31    5043  545.79  5262.2  546.78  5272.3   546.3  5279.9   543.6
  5282.1  543.49  5282.6  542.99  5287.3  542.99  5287.7  543.49  5292.5  545.72
  5302.6  547.34  5423.5  552.12    5484  555.31  5504.1  554.84  5514.2  555.29
  5544.4     558  5602.4  561.82  5607.4   561.5    5683  567.01  5806.4  573.59
#Mann= 3 ,-1 , 0
  4500.2     .07       0  5282.1     .05       0  5287.7     .07       0
Bank Sta=5282.1,5287.7
XS Rating Curve= 0 ,0
Exp/Cntr=0.3,0.1

Type RM Length L Ch R = 1 ,54908   ,439,439,439
BEGIN DESCRIPTION:
COTTONWOOD CREEK SOUTH 102.0
END DESCRIPTION:
XS GIS Cut Line= 3
      2293225.01     13712275.03        2293475.       13712875.
      2294275.01       13712775.
#Sta/Elev= 30
  4344.9  559.42  4537.2  555.67  4566.4  554.05  4680.7  551.54  4855.7  544.88
  4975.1  544.62  5002.1  543.89  5002.6  543.39  5007.7  543.89  5025.1  545.22
  5057.5  544.88  5166.2  545.79  5186.3  545.08  5206.5  545.65  5216.6  544.83
  5226.7  545.59  5327.4  547.19  5360.2  546.61    5398   548.6  5488.7  550.01
  5498.8  550.47  5516.4  553.09  5539.1  550.44  5579.4  554.04    5597  557.05
  5602.1  556.27  5609.6  556.93  5629.8  555.81  5670.1  557.25  5801.1  565.34
#Mann= 5 ,-1 , 0
  4344.9     .07       0  4975.1     .12       0  5002.1     .05       0
  5007.7     .12       0  5057.5     .07       0
Bank Sta=5002.1,5007.7
XS Rating Curve= 0 ,0
Exp/Cntr=0.3,0.1

Type RM Length L Ch R = 1 ,54469   ,449,449,449
BEGIN DESCRIPTION:
COTTONWOOD CREEK SOUTH 101.0
END DESCRIPTION:
XS GIS Cut Line= 3
      2292575.01       13713325.        2293325.       13713225.
      2294075.01       13713475.
#Sta/Elev= 30
  4239.5  562.38  4330.3  558.93  4427.4  554.26  4505.6  551.98  4532.1  550.54
  4602.7  548.42  4673.3  545.41  4713.6  544.76    4730  545.34  4824.6     545
  4855.1  544.36  4945.7   543.3  4959.6  543.79  4965.9  543.36  4998.8  543.55
  5008.6   543.1  5014.3  542.46  5014.8  541.96  5019.7  541.96  5020.2  542.46
  5038.3  543.55  5080.5  543.04  5112.1   543.4  5122.6  542.69  5175.3  544.39
  5196.4   544.2  5280.7  545.79  5375.6  546.77  5628.6  555.38  5786.7  557.61
#Mann= 5 ,-1 , 0
  4239.5     .07       0  4855.1     .12       0  5008.6     .07       0
  5014.3     .05       0  5020.2     .07       0
Bank Sta=5014.3,5020.2
XS Rating Curve= 0 ,0
Exp/Cntr=0.3,0.1

Type RM Length L Ch R = 1 ,54020   ,467,467,467
BEGIN DESCRIPTION:
COTTONWOOD CREEK SOUTH 100.0
END DESCRIPTION:
XS GIS Cut Line= 3
      2292524.99       13713375.        2293325.       13713675.
      2293925.03     13713524.99
#Sta/Elev= 30
  4145.6  563.89  4177.6  563.25  4215.9  561.18  4263.1  559.58  4472.2  550.87
  4557.7  548.65  4582.6  548.57  4604.8   546.6  4618.2  544.55  4636.9  544.83
  4648.5  543.89  4703.6  541.98  4783.7  541.52  4893.2  542.15  4929.7  541.14
  4978.6  540.92  4984.9  538.56  4990.2  538.75  4994.1  536.24  4994.6  535.74
  5000.1  535.74  5000.6  536.24  5010.3  536.29    5018  538.61  5023.2  538.68
  5030.9  540.69  5051.5  541.12  5064.4  541.96    5353  546.96  5618.5  555.55
#Mann= 3 ,-1 , 0
  4145.6     .07       0  4994.1     .05       0  5000.6     .07       0
Bank Sta=4994.1,5000.6
XS Rating Curve= 0 ,0
Exp/Cntr=0.3,0.1

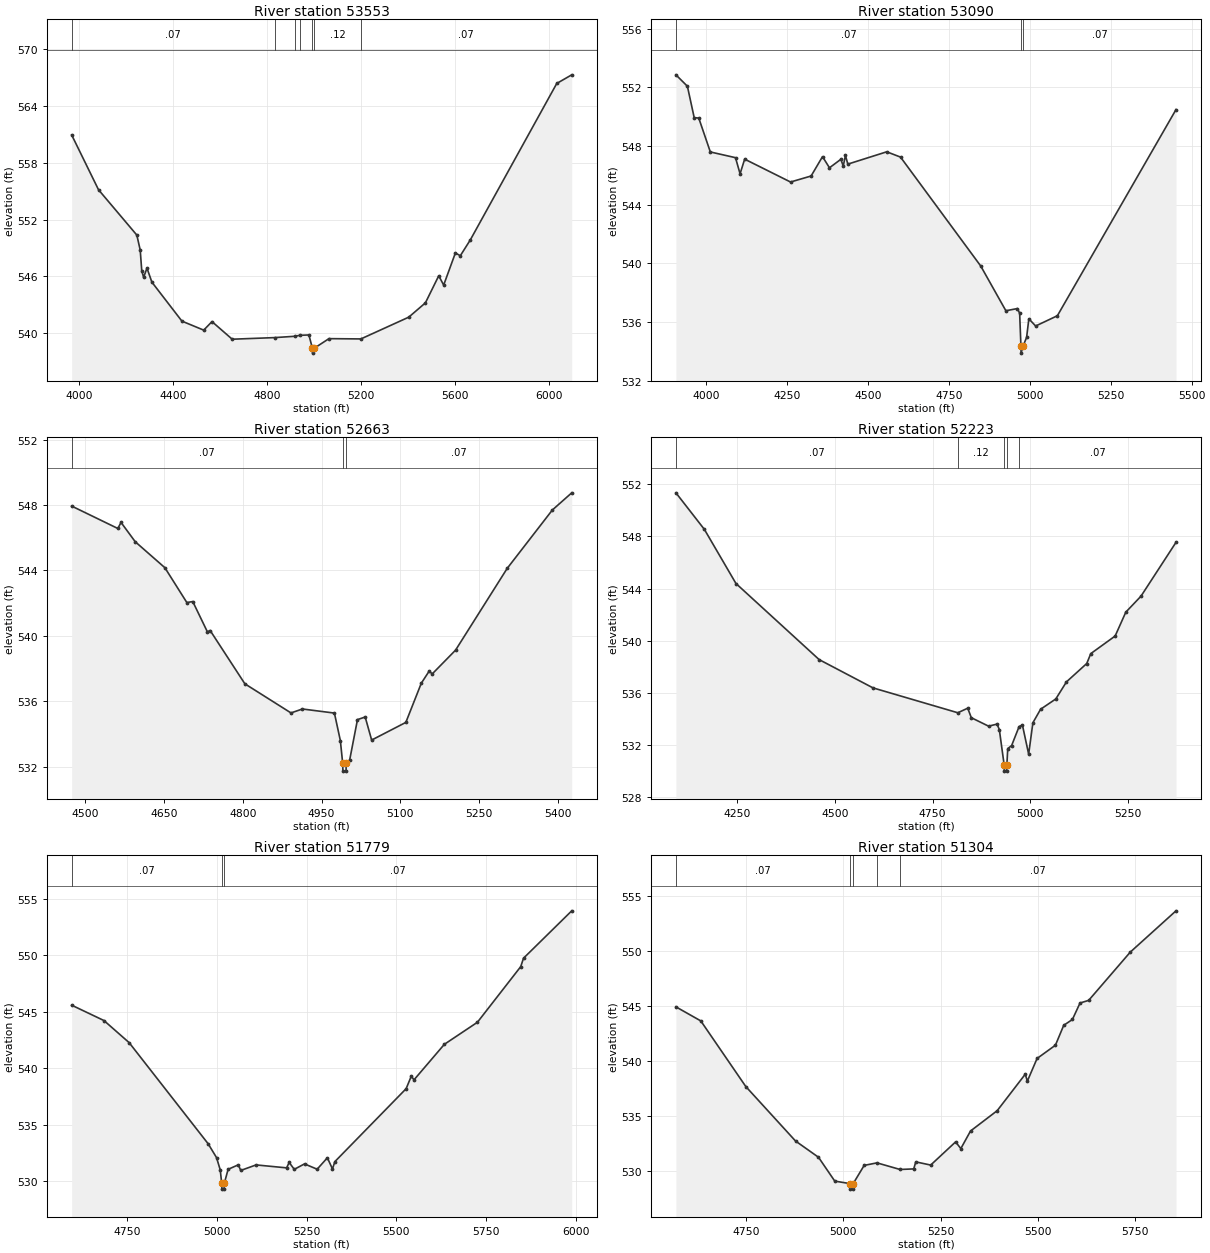
Type RM Length L Ch R = 1 ,53553   ,463,463,463
BEGIN DESCRIPTION:
COTTONWOOD CREEK SOUTH 99.0
END DESCRIPTION:
XS GIS Cut Line= 3
      2292575.02     13713475.02        2293375.       13714125.
      2294174.97     13714874.97
#Sta/Elev= 30
  3968.6  560.95  4082.8  555.16  4245.8  550.37  4260.2  548.79  4266.7  546.61
  4274.6  545.91    4289  546.88  4309.8   545.4  4437.6  541.28  4530.3  540.33
  4565.5  541.23  4651.5  539.37  4832.2  539.54    4918  539.68  4938.2  539.78
  4977.8  539.82  4992.8   538.4  4993.3   537.9  4999.4   538.4  5063.1  539.43
  5198.9   539.4  5402.6   541.7  5473.4  543.21  5530.1  546.07  5551.1  545.09
  5600.9  548.48  5621.9  548.19  5664.4  549.86  6032.2  566.39  6095.9   567.3
#Mann= 7 ,-1 , 0
  3968.6     .07       0  4832.2     .12       0    4918     .07       0
  4938.2     .12       0  4992.8     .05       0  4999.4     .12       0
  5198.9     .07       0
Bank Sta=4992.8,4999.4
XS Rating Curve= 0 ,0
Exp/Cntr=0.3,0.1

Type RM Length L Ch R = 1 ,53090   ,427,427,427
BEGIN DESCRIPTION:
COTTONWOOD CREEK SOUTH 98.0
END DESCRIPTION:
XS GIS Cut Line= 3
      2292525.03     13713825.03        2293325.       13714575.
      2293725.04     13714775.02
#Sta/Elev= 30
  3907.9  552.85  3943.3  552.07  3964.3  549.93  3978.4   549.9  4014.1  547.59
  4091.8   547.2  4105.9   546.1  4120.1   547.1  4261.7  545.54  4325.2  545.95
  4360.4  547.27  4381.9  546.51  4417.1  547.09  4424.4  546.63  4431.2  547.35
  4438.6  546.76  4558.7   547.6  4601.2  547.24  4848.9  539.81  4926.5  536.76
  4962.2  536.91    4969  536.59  4972.9  534.37  4973.4  533.87  4979.8  534.37
  4990.5  534.94  4997.4  536.21  5018.4  535.72  5085.5  536.42  5451.7  550.48
#Mann= 3 ,-1 , 0
  3907.9     .07       0  4972.9     .05       0  4979.8     .07       0
Bank Sta=4972.9,4979.8
XS Rating Curve= 0 ,0
Exp/Cntr=0.3,0.1

Type RM Length L Ch R = 1 ,52663   ,440,440,440
BEGIN DESCRIPTION:
COTTONWOOD CREEK SOUTH 97.0
END DESCRIPTION:
XS GIS Cut Line= 3
      2292924.99     13714324.97        2293075.       13714825.
      2293425.03     13715075.02
#Sta/Elev= 30
  4474.1  547.94    4562  546.57  4568.1  546.94  4595.1  545.76  4651.6  544.17
  4693.4  542.04  4704.7   542.1  4732.5  540.25  4737.8  540.33  4803.9  537.07
  4891.7  535.29  4913.5  535.53  4974.4  535.28  4985.7   533.6  4990.1  532.23
  4990.6  531.73  4996.5  531.73    4997  532.23  5003.5  532.42  5018.3  534.88
    5033  535.04  5045.3  533.63  5110.4  534.71  5139.9  537.11  5154.7  537.84
  5160.8  537.68  5205.1  539.13  5303.4  544.13  5389.4   547.7  5426.3  548.75
#Mann= 3 ,-1 , 0
  4474.1     .07       0  4990.1     .05       0    4997     .07       0
Bank Sta=4990.1,4997
XS Rating Curve= 0 ,0
Exp/Cntr=0.3,0.1

Type RM Length L Ch R = 1 ,52223   ,444,444,444
BEGIN DESCRIPTION:
COTTONWOOD CREEK SOUTH 96.0
END DESCRIPTION:
XS GIS Cut Line= 3
        2292225.       13714775.        2293025.       13715225.
      2293375.02     13715124.99
#Sta/Elev= 30
  4092.2  551.35  4165.2  548.54  4246.1  544.39  4459.3  538.55  4597.3  536.38
  4814.8  534.47  4840.2  534.82  4849.4  534.09  4893.7  533.44  4915.4   533.6
  4921.2  533.18  4933.5  530.49    4934  529.99  4940.1  529.99  4940.6  530.49
  4942.8  531.72  4952.7  531.95  4971.9  533.41  4980.4  533.53  4996.4  531.29
  5007.2   533.7    5027  534.74    5066  535.53  5093.3  536.84  5145.3  538.25
  5155.7  539.01  5218.1  540.36  5245.4  542.19  5284.4  543.42  5374.1  547.55
#Mann= 5 ,-1 , 0
  4092.2     .07       0  4814.8     .12       0  4933.5     .05       0
  4940.6     .12       0  4971.9     .07       0
Bank Sta=4933.5,4940.6
XS Rating Curve= 0 ,0
Exp/Cntr=0.3,0.1

Type RM Length L Ch R = 1 ,51779   ,475,475,475
BEGIN DESCRIPTION:
COTTONWOOD CREEK SOUTH 95.0
END DESCRIPTION:
XS GIS Cut Line= 3
      2292375.03       13715575.        2292775.       13715575.
      2293524.97     13716224.97
#Sta/Elev= 30
  4595.9  545.58  4685.9  544.22  4755.9  542.27  4975.9  533.33  4999.2  532.11
  5009.6  531.02  5013.7  529.82  5014.2  529.32  5020.3  529.32  5020.8  529.82
  5031.5  531.07    5060  531.47  5066.6  530.97  5109.4  531.46  5194.4   531.2
  5201.5  531.68  5215.7  531.07  5244.2  531.55  5279.4  531.08  5307.9  532.09
  5322.1   531.1  5328.7  531.75  5527.2   538.2  5541.5   539.3  5549.1  538.98
  5633.6  542.12  5725.7  544.07  5846.3  548.99    5854  549.73  5988.3  553.92
#Mann= 3 ,-1 , 0
  4595.9     .07       0  5013.7     .05       0  5020.8     .07       0
Bank Sta=5013.7,5020.8
XS Rating Curve= 0 ,0
Exp/Cntr=0.3,0.1

Type RM Length L Ch R = 1 ,51304   ,415,415,415
BEGIN DESCRIPTION:
COTTONWOOD CREEK SOUTH 94.0
END DESCRIPTION:
XS GIS Cut Line= 3
      2292425.02     13715625.02        2292675.       13715975.
      2293475.01       13716275.
#Sta/Elev= 30
  4570.2   544.9  4634.1  543.62  4749.6  537.65  4877.4  532.69  4936.4  531.21
  4978.2  529.04  5017.8  528.81  5018.3  528.31    5025  528.31  5025.5  528.81
  5053.7  530.47  5086.7   530.7  5145.7   530.1    5181  530.15  5186.3  530.79
  5224.6   530.5  5288.6  532.61    5302     532  5326.9   533.6  5395.4  535.45
  5467.5  538.77  5472.9  538.14  5497.8   540.2    5545  541.41  5566.3  543.22
  5588.6  543.75  5608.2  545.25  5630.4  545.49  5737.2  549.88  5854.7  553.64
#Mann= 5 ,-1 , 0
  4570.2     .07       0  5017.8     .05       0  5025.5     .07       0
  5086.7     .12       0  5145.7     .07       0
Bank Sta=5017.8,5025.5
XS Rating Curve= 0 ,0
Exp/Cntr=0.3,0.1

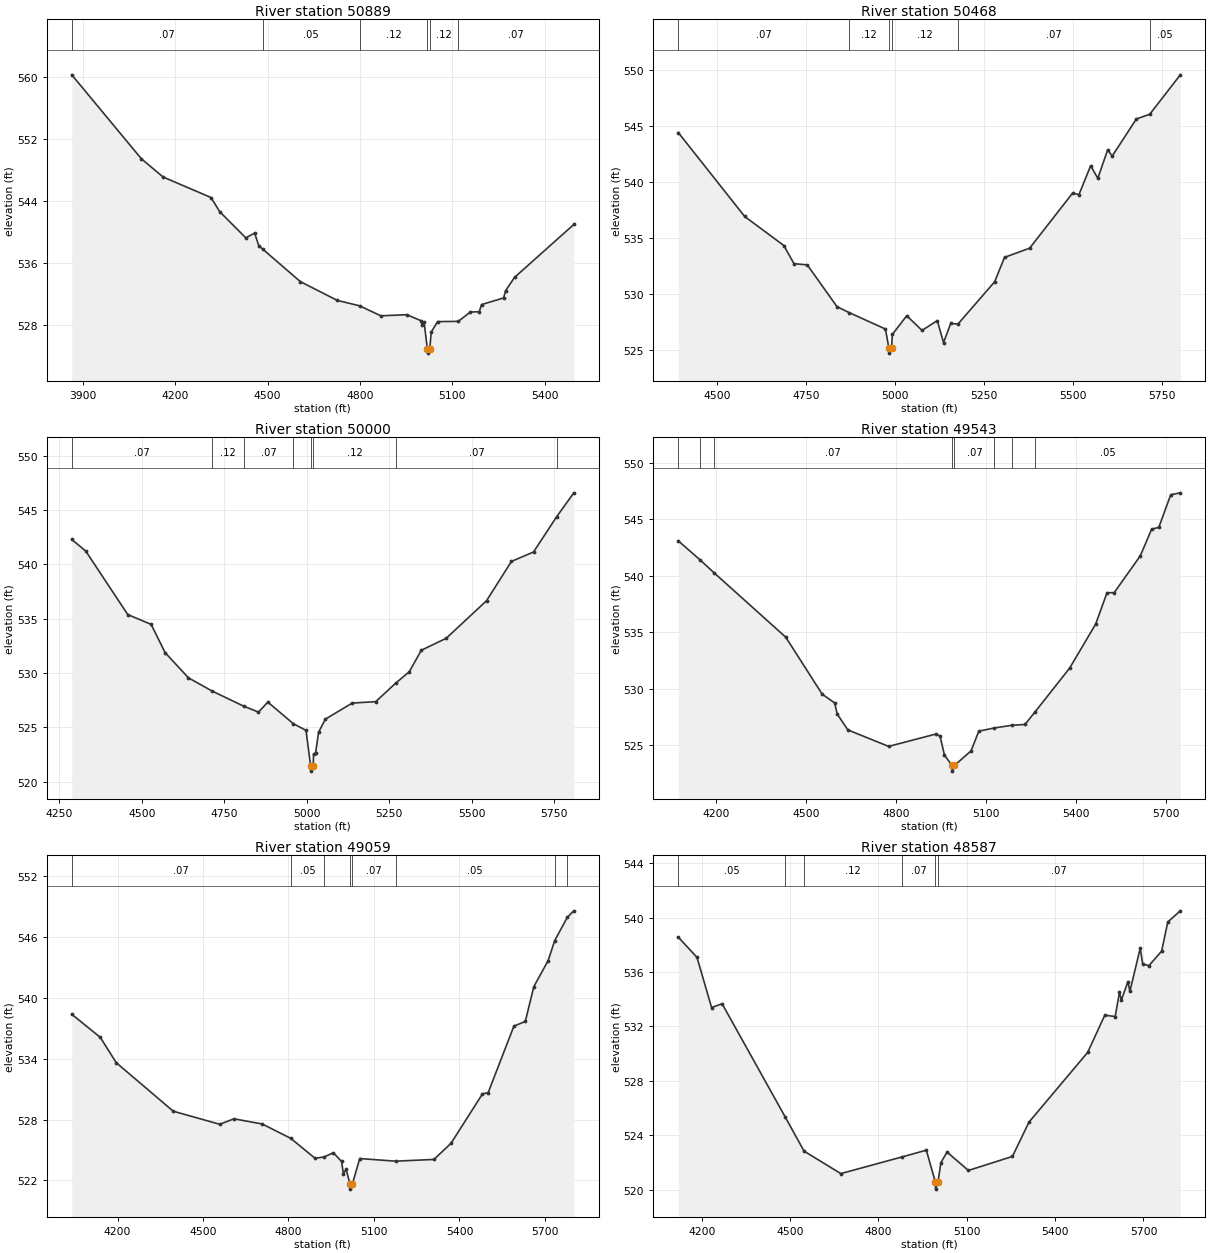
Type RM Length L Ch R = 1 ,50889   ,421,421,421
BEGIN DESCRIPTION:
COTTONWOOD CREEK SOUTH 93.0
END DESCRIPTION:
XS GIS Cut Line= 3
        2291775.       13715525.        2292575.       13716325.
      2292975.02     13716625.01
#Sta/Elev= 30
  3863.8  560.31  4090.1  549.46  4160.8  547.11  4316.4  544.46  4344.6  542.63
  4429.5  539.25  4457.8  539.87  4471.9  538.21  4484.6  537.79  4606.3  533.61
  4726.5  531.18  4799.1  530.48  4867.9  529.19  4952.8  529.33  4998.3  528.56
  5002.5  527.98  5008.7  528.35  5019.4  524.87  5019.9  524.37  5027.2  524.87
  5031.6  527.08  5052.5  528.44  5119.6  528.47  5158.7  529.67  5187.9  529.72
  5195.2  530.64  5267.1   531.5  5273.3  532.43  5302.5  534.15  5495.2  540.99
#Mann= 6 ,-1 , 0
  3863.8     .07       0  4484.6     .05       0  4799.1     .12       0
  5019.4     .05       0  5027.2     .12       0  5119.6     .07       0
Bank Sta=5019.4,5027.2
XS Rating Curve= 0 ,0
Exp/Cntr=0.3,0.1

Type RM Length L Ch R = 1 ,50468   ,468,468,468
BEGIN DESCRIPTION:
COTTONWOOD CREEK SOUTH 92.0
END DESCRIPTION:
XS GIS Cut Line= 3
      2291825.03     13716425.01        2292375.       13716675.
      2293174.96     13716774.99
#Sta/Elev= 30
  4391.1   544.4  4577.8   536.9  4687.6  534.31  4716.2  532.69  4753.6  532.58
    4837  528.85  4871.1  528.32  4973.2  526.85  4982.5   525.2    4983   524.7
  4990.4   525.2  4992.5  526.37    5033  528.04  5075.8  526.73  5118.7   527.6
  5136.3  525.64  5156.5  527.35  5176.7  527.29  5279.9  531.07  5307.6  533.25
  5378.2  534.07  5499.1     539  5516.7  538.85  5549.5  541.43  5569.7  540.31
  5597.4  542.86    5610  542.29    5678  545.61  5715.6  546.03  5801.4  549.55
#Mann= 6 ,-1 , 0
  4391.1     .07       0  4871.1     .12       0  4982.5     .05       0
  4990.4     .12       0  5176.7     .07       0  5715.6     .05       0
Bank Sta=4982.5,4990.4
XS Rating Curve= 0 ,0
Exp/Cntr=0.3,0.1

Type RM Length L Ch R = 1 ,50000   ,457,457,457
BEGIN DESCRIPTION:
COTTONWOOD CREEK SOUTH 91.0
END DESCRIPTION:
XS GIS Cut Line= 3
        2291775.       13716575.        2292275.       13717075.
      2293075.05     13716924.99
#Sta/Elev= 30
  4288.1  542.28  4330.5  541.21  4457.8  535.37  4528.5  534.47  4570.9  531.87
  4641.7  529.55  4713.1  528.34  4809.2  526.94  4853.8   526.4  4882.1  527.32
    4959  525.34  4997.8  524.72  5011.6  521.47  5012.1  520.97  5019.6  521.47
  5020.6  522.55  5026.6  522.62  5035.9  524.55  5056.3  525.75  5137.7  527.23
  5208.9  527.36  5270.4  529.09  5310.6  530.11  5347.1  532.09  5422.5  533.19
  5544.6  536.64  5620.1  540.26  5687.1  541.13  5757.5  544.39  5809.2  546.57
#Mann= 8 ,-1 , 0
  4288.1     .07       0  4713.1     .12       0  4809.2     .07       0
    4959     .12       0  5011.6     .05       0  5019.6     .12       0
  5270.4     .07       0  5757.5     .05       0
Bank Sta=5011.6,5019.6
XS Rating Curve= 0 ,0
Exp/Cntr=0.3,0.1

Type RM Length L Ch R = 1 ,49543   ,484,484,484
BEGIN DESCRIPTION:
COTTONWOOD CREEK SOUTH 90.0
END DESCRIPTION:
XS GIS Cut Line= 3
        2291425.       13716925.        2292175.       13717475.
      2292875.04     13717725.02
#Sta/Elev= 30
  4074.2   543.1    4147  541.41  4194.4  540.25  4432.7  534.56  4553.9  529.52
  4595.6  528.74    4604  527.76  4639.6  526.35  4775.4  524.89  4932.1  525.98
  4946.8  525.81  4961.4  524.13  4986.6   523.2  4987.1   522.7  4994.9   523.2
  5050.4   524.5  5075.9  526.24  5127.2  526.52  5185.8  526.76  5229.9  526.83
  5262.4  527.91  5378.6  531.82  5465.6  535.73  5503.3   538.5  5527.2  538.51
  5614.3  541.77    5652  544.13  5675.9  544.29  5715.7  547.18  5747.6  547.35
#Mann= 8 ,-1 , 0
  4074.2     .07       0    4147     .05       0  4194.4     .07       0
  4986.6     .05       0  4994.9     .07       0  5127.2     .05       0
  5185.8     .07       0  5262.4     .05       0
Bank Sta=4986.6,4994.9
XS Rating Curve= 0 ,0
Exp/Cntr=0.3,0.1

Type RM Length L Ch R = 1 ,49059   ,472,472,472
BEGIN DESCRIPTION:
COTTONWOOD CREEK SOUTH 89.0
END DESCRIPTION:
XS GIS Cut Line= 3
      2291474.98     13717174.97        2292075.       13717925.
      2292875.04       13717875.
#Sta/Elev= 30
  4039.4  538.39  4139.5  536.11  4195.5  533.61  4395.6  528.82  4558.9  527.53
  4608.5  528.07  4707.8  527.56  4808.1  526.14  4893.4  524.17  4925.2  524.31
  4957.5  524.72  4986.3  523.86  4992.7  522.65  5002.4  523.09  5015.7  521.63
  5016.2  521.13  5024.2  521.63    5050  524.15  5175.6  523.89  5310.5  524.06
  5370.6  525.66  5480.8  530.53  5500.9  530.66  5591.1  537.22  5631.1  537.68
  5661.2  541.13  5711.3  543.68  5734.4  545.67  5778.8  547.97  5801.5   548.6
#Mann= 8 ,-1 , 0
  4039.4     .07       0  4808.1     .05       0  4925.2     .07       0
  5015.7     .05       0  5024.2     .07       0  5175.6     .05       0
  5734.4     .07       0  5778.8     .05       0
Bank Sta=5015.7,5024.2
XS Rating Curve= 0 ,0
Exp/Cntr=0.3,0.1

Type RM Length L Ch R = 1 ,48587   ,605,605,605
BEGIN DESCRIPTION:
COTTONWOOD CREEK SOUTH 88.0
END DESCRIPTION:
XS GIS Cut Line= 3
      2291224.98     13717624.98        2291825.       13718275.
      2292325.01     13718925.02
#Sta/Elev= 30
  4120.3  538.56  4184.1  537.07  4233.5  533.39  4269.2  533.67  4482.9  525.38
  4547.5  522.85  4672.3   521.2  4879.5  522.42  4962.7  522.92  4993.5  520.56
    4994  520.06  5002.1  520.56  5012.2  522.01    5033  522.78  5105.5  521.43
    5255  522.46  5311.2  524.98  5510.5   530.1  5568.6  532.83  5603.9  532.73
  5618.4  534.51  5624.7  533.93  5647.4   535.3  5653.7  534.57    5689  537.75
  5697.2   536.6  5718.1  536.46  5761.6  537.53  5782.4  539.67    5825  540.49
#Mann= 6 ,-1 , 0
  4120.3     .05       0  4482.9     .07       0  4547.5     .12       0
  4879.5     .07       0  4993.5     .05       0  5002.1     .07       0
Bank Sta=4993.5,5002.1
XS Rating Curve= 0 ,0
Exp/Cntr=0.3,0.1