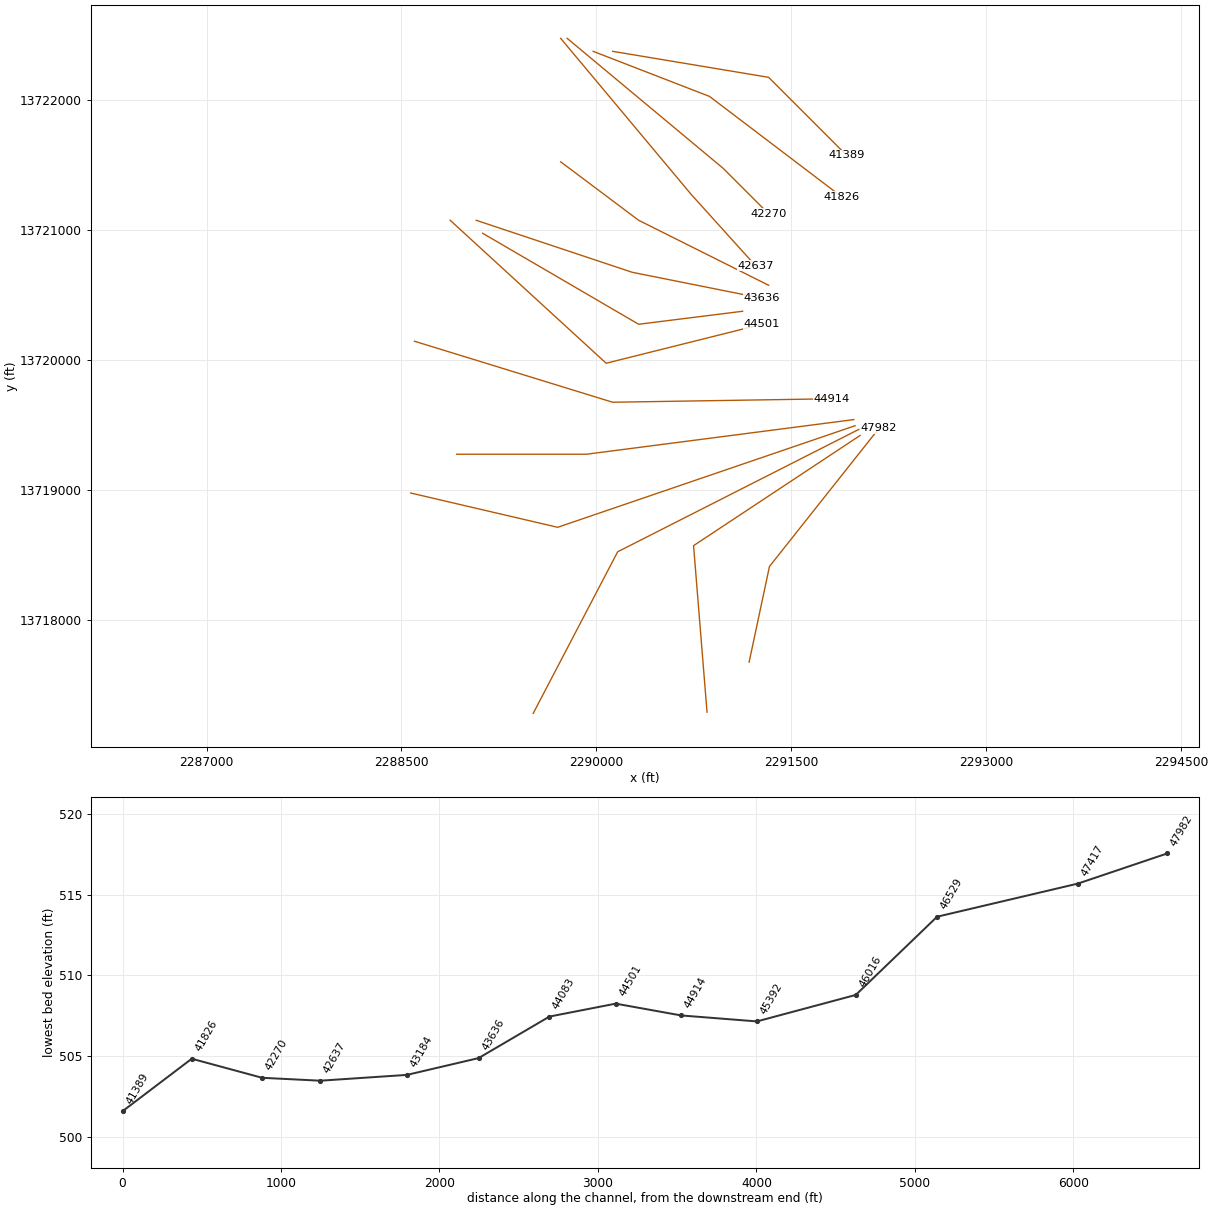
HEC-RAS study COTTONWOOD CREEK SOUTH.prj: COTTONWOOD CREEK SOUTH Base Level Engineering

--- COTTONWOOD CREEK SOUTH.g01 (geometry) --- (continued)

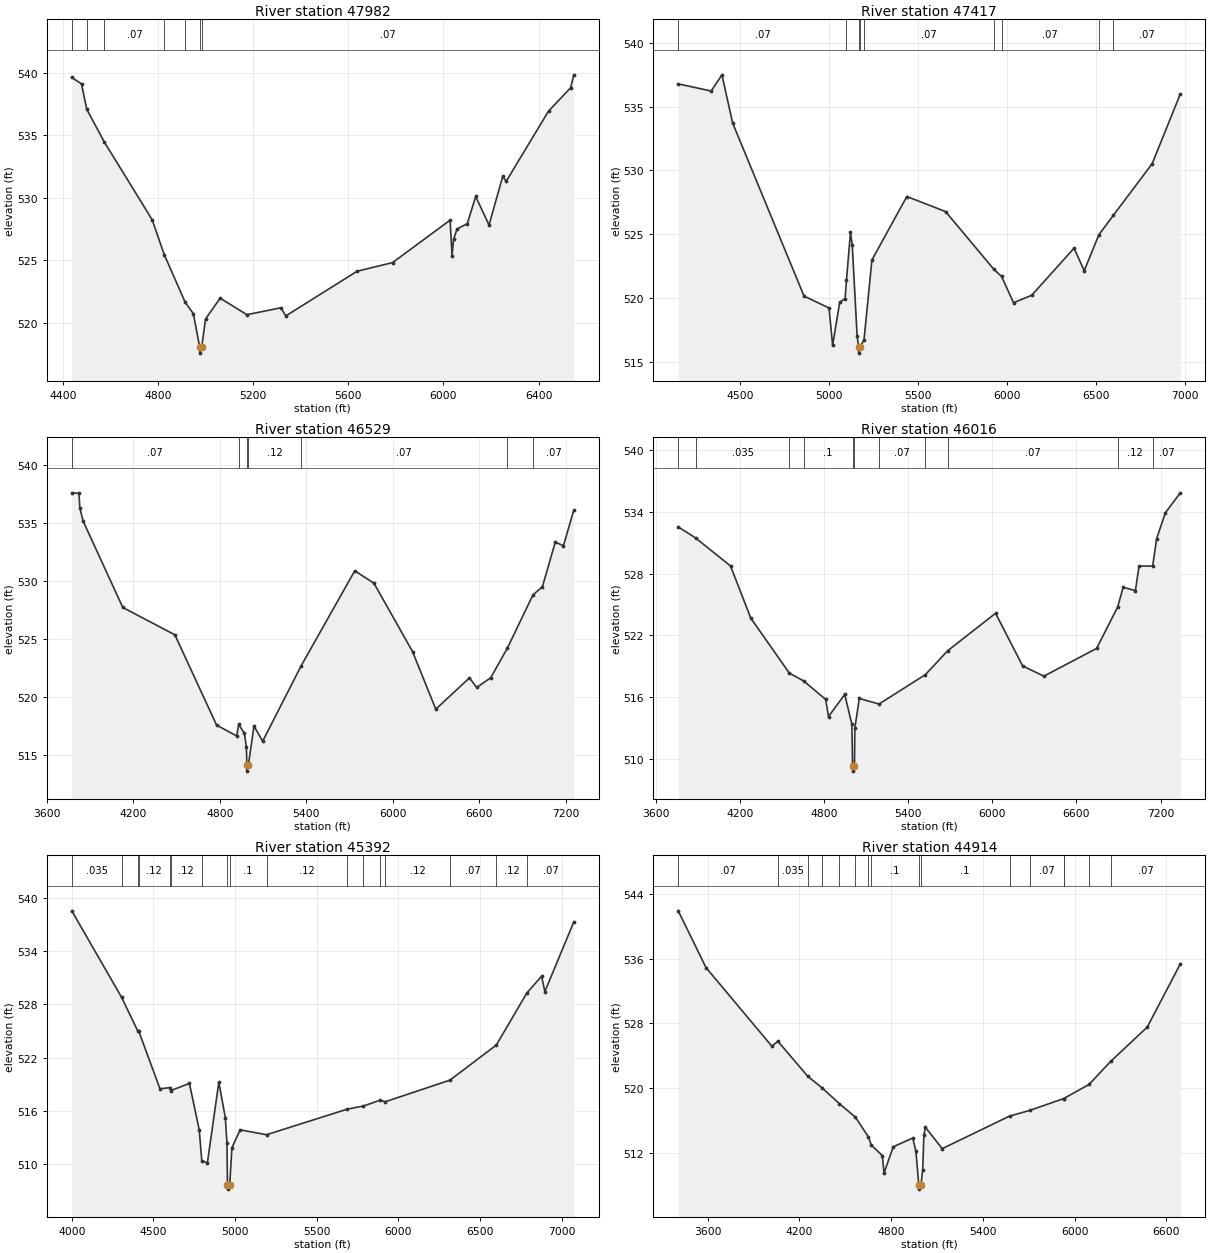
Type RM Length L Ch R = 1 ,47982   ,565,565,565
BEGIN DESCRIPTION:
COTTONWOOD CREEK SOUTH 87.0
END DESCRIPTION:
XS GIS Cut Line= 3
        2291175.     13717675.01      2291331.61      13718411.2
      2292174.98     13719474.98
#Sta/Elev= 30
  4438.1  539.63    4479  539.11  4501.1  537.08  4575.4  534.44  4775.5  528.25
    4827  525.43  4914.1  521.65  4949.3   520.7  4975.6  518.05  4976.1  517.55
  4984.3  518.05  5000.4  520.29  5061.7  521.95  5174.2  520.63  5316.9  521.18
  5337.7  520.53  5637.4  524.11  5786.4   524.8  6028.3   528.2  6036.4  525.35
  6042.8  526.66  6057.2  527.49  6100.5  527.92  6135.7   530.1  6191.8  527.81
  6249.5  531.71  6263.9  531.31  6441.8  536.93  6534.7   538.8  6548.3  539.84
#Mann= 7 ,-1 , 0
  4438.1     .07       0  4501.1     .05       0  4575.4     .07       0
    4827     .12       0  4914.1     .07       0  4975.6     .05       0
  4984.3     .07       0
Bank Sta=4975.6,4984.3
XS Rating Curve= 0 ,0
Exp/Cntr=0.3,0.1

Type RM Length L Ch R = 1 ,47417   ,888,888,888
BEGIN DESCRIPTION:
X18631
END DESCRIPTION:
XS GIS Cut Line= 3
      2290851.22     13717290.28      2290747.61     13718571.32
      2292028.67     13719419.08
#Sta/Elev= 30
  4153.6  536.79  4338.9  536.23  4399.1   537.5  4459.3  533.72  4860.6  520.15
  5001.1  519.22  5021.1   516.3  5061.3  519.68  5091.4  519.96    5099   521.4
  5121.5  525.14  5131.5  524.17  5158.8  517.01  5167.3  516.18  5167.8  515.68
    5176  516.18  5197.6  516.72  5241.9  522.98  5438.2  527.96  5655.7  526.78
    5928  522.24  5970.3   521.7  6037.8  519.63  6140.2  520.22  6377.9  523.91
    6435  522.14  6517.7  524.97  6599.1  526.49  6817.1  530.54    6975     536
#Mann= 9 ,-1 , 0
  4153.6     .07       0    5099     .12       0  5167.3     .05       0
    5176     .12       0  5197.6     .07       0    5928     .12       0
  5970.3     .07       0  6517.7     .12       0  6599.1     .07       0
Bank Sta=5167.3,5176
XS Rating Curve= 0 ,0
Exp/Cntr=0.3,0.1

Type RM Length L Ch R = 1 ,46529   ,513,513,513
BEGIN DESCRIPTION:
X18630
END DESCRIPTION:
XS GIS Cut Line= 3
      2289513.68     13717280.89       2290163.6     13718524.23
      2292019.26     13719466.18
#Sta/Elev= 30
  3773.4  537.62  3823.2  537.58  3829.5  536.32  3851.6   535.2  4127.3  527.74
  4488.9  525.38  4778.3   517.6  4917.7  516.66  4931.9  517.65  4971.4  516.88
  4985.4  515.67  4988.3  514.13  4988.8  513.63  4998.7  514.13  5037.6  517.52
  5098.2  516.21    5366  522.73  5737.2   530.9  5870.8  529.82  6137.9  523.94
  6299.4  518.97    6533  521.67  6583.2  520.84  6680.7  521.68  6795.9  524.23
  6973.7  528.82  7039.4  529.53  7128.5  533.37  7185.3  533.06  7257.4  536.14
#Mann= 7 ,-1 , 0
  3773.4     .07       0  4931.9     .12       0  4988.3     .05       0
  4998.7     .12       0    5366     .07       0  6795.9     .12       0
  6973.7     .07       0
Bank Sta=4988.3,4998.7
XS Rating Curve= 0 ,0
Exp/Cntr=0.3,0.1

Type RM Length L Ch R = 1 ,46016   ,624,624,624
BEGIN DESCRIPTION:
X18629
END DESCRIPTION:
XS GIS Cut Line= 3
      2288571.77     13718976.35      2289702.05     13718712.62
       2291990.5     13719494.27
#Sta/Elev= 30
  3761.3  532.55  3885.2  531.48  4134.3  528.75  4278.3  523.68    4553  518.33
  4654.8  517.57    4812  515.77  4832.6   514.1  4948.1  516.25    4999  513.36
    5004  509.29  5004.5  508.79  5017.5  509.29  5020.2  512.97  5051.9  515.86
  5192.7  515.32  5523.1  518.18  5681.5   520.5  6023.2  524.15  6216.4  519.03
  6367.7  518.03  6743.5  520.73    6893  524.74  6932.8  526.67  7020.1  526.36
  7046.2  528.75    7143  528.74  7171.5  531.42  7234.1  533.94  7340.2  535.87
#Mann= 11 ,-1 , 0
  3761.3     .07       0  3885.2    .035       0    4553     .12       0
  4654.8      .1       0    5004     .05       0  5017.5      .1       0
  5192.7     .07       0  5523.1     .12       0  5681.5     .07       0
    6893     .12       0    7143     .07       0
Bank Sta=5004,5017.5
XS Rating Curve= 0 ,0
Exp/Cntr=0.3,0.1

Type RM Length L Ch R = 1 ,45392   ,478,478,478
BEGIN DESCRIPTION:
COTTONWOOD CREEK SOUTH 81.0
END DESCRIPTION:
XS GIS Cut Line= 3
      2288924.97       13719275.        2289925.       13719275.
      2291980.78     13719541.42
#Sta/Elev= 30
  4000.3  538.56  4305.5  528.79  4403.9  525.01  4408.9  525.04  4540.3  518.47
  4600.8  518.61  4606.2  518.27  4720.3  519.08  4780.3  513.86  4795.9  510.37
  4830.3  510.11  4900.3  519.21  4940.3   515.2  4950.3   512.3  4953.4  507.65
  4953.9  507.15  4967.2  507.65  4980.3  511.81  5030.6  513.84  5192.4  513.29
  5686.8  516.18  5785.7  516.53  5884.6  517.17  5920.2  517.02  6315.1  519.45
  6598.7  523.41  6785.9  529.29  6875.9  531.18    6896  529.45  7073.3  537.32
#Mann= 17 ,-1 , 0
  4000.3    .035       0  4305.5     .12       0  4403.9      .1       0
  4408.9     .12       0  4600.8      .1       0  4606.2     .12       0
  4795.9      .1       0  4953.4     .05       0  4967.2      .1       0
  5192.4     .12       0  5686.8      .1       0  5785.7     .12       0
  5884.6     .07       0  5920.2     .12       0  6315.1     .07       0
  6598.7     .12       0  6785.9     .07       0
Bank Sta=4953.4,4967.2
XS Rating Curve= 0 ,0
Exp/Cntr=0.3,0.1

Type RM Length L Ch R = 1 ,44914   ,413,413,413
BEGIN DESCRIPTION:
COTTONWOOD CREEK SOUTH 80.0
END DESCRIPTION:
XS GIS Cut Line= 3
      2288599.97     13720144.37        2290125.       13719675.
      2291810.97     13719701.64
#Sta/Elev= 30
  3408.7   541.9  3590.1  534.89  4020.8  525.17  4059.9  525.79  4254.8  521.47
  4346.1  520.07  4462.7  518.07  4566.7  516.41  4651.5  513.98  4670.6  512.96
  4742.7  511.67  4753.9  509.51  4814.1  512.75  4941.5  513.83  4962.5  512.17
  4981.1  508.02  4981.6  507.52  4994.9  508.02  5006.8  509.94  5014.3  514.15
  5024.3  515.16  5134.3  512.52  5574.1  516.54  5705.5  517.24  5927.2   518.7
  5928.2  518.71  6094.1  520.45  6234.7  523.29  6474.5  527.54  6690.5  535.34
#Mann= 16 ,-1 , 0
  3408.7     .07       0  4059.9    .035       0  4254.8     .12       0
  4346.1      .1       0  4462.7     .12       0  4566.7      .1       0
  4651.5     .12       0  4670.6      .1       0  4981.1     .05       0
  4994.9      .1       0  5574.1     .12       0  5705.5     .07       0
  5927.2     .12       0  5928.2     .07       0  6094.1     .12       0
  6234.7     .07       0
Bank Sta=4981.1,4994.9
XS Rating Curve= 0 ,0
Exp/Cntr=0.3,0.1

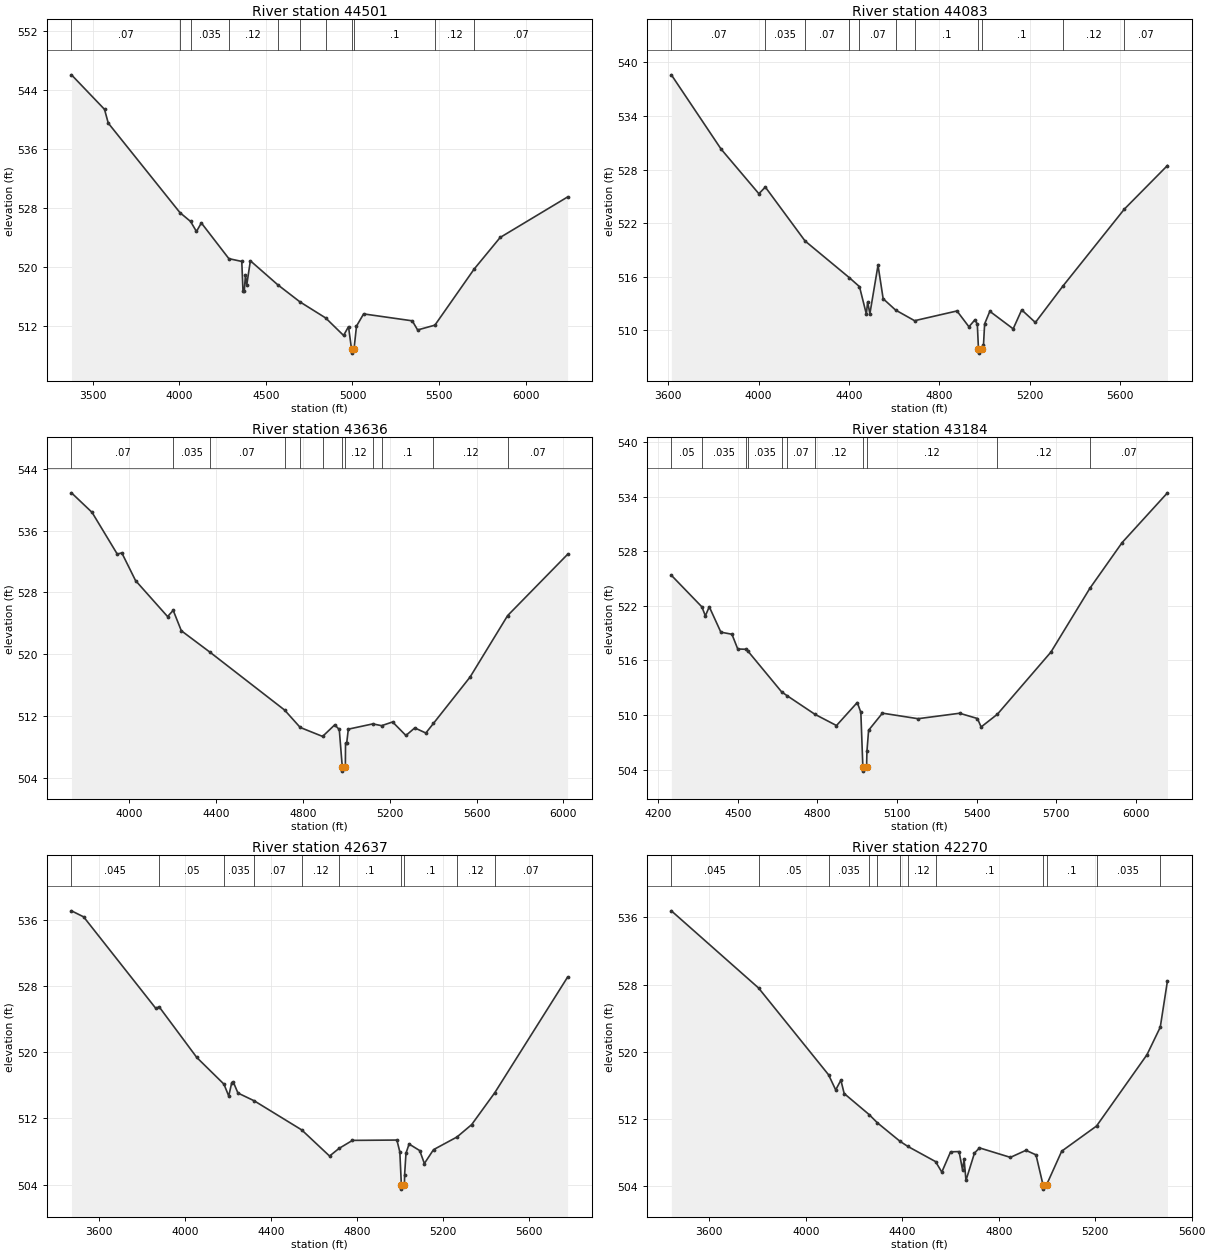
Type RM Length L Ch R = 1 ,44501   ,418,418,418
BEGIN DESCRIPTION:
COTTONWOOD CREEK SOUTH 79.0
END DESCRIPTION:
XS GIS Cut Line= 3
      2288875.02     13721074.98        2290075.       13719975.
      2291275.02       13720275.
#Sta/Elev= 30
  3377.3  546.07  3568.1  541.38  3589.7  539.51  4003.9  527.34  4065.2  526.14
    4099  524.78  4127.4  525.94  4286.2  521.09  4360.8  520.71  4367.9  516.65
  4375.3  516.74  4382.1  518.87  4389.5  517.52  4410.4   520.8  4568.5  517.54
    4697  515.21  4845.2  513.03  4948.7  510.65  4977.1  511.85  4994.8  508.75
  4995.3  508.25  5008.7  508.75  5023.2  511.92  5064.4  513.58  5345.3  512.64
  5376.2   511.4  5475.9  512.05  5702.2  519.66    5853  523.97  6242.1  529.47
#Mann= 11 ,-1 , 0
  3377.3     .07       0  4003.9     .12       0  4065.2    .035       0
  4286.2     .12       0  4568.5    .035       0    4697     .12       0
  4845.2      .1       0  4994.8     .05       0  5008.7      .1       0
  5475.9     .12       0  5702.2     .07       0
Bank Sta=4994.8,5008.7
XS Rating Curve= 0 ,0
Exp/Cntr=0.3,0.1

Type RM Length L Ch R = 1 ,44083   ,447,447,447
BEGIN DESCRIPTION:
COTTONWOOD CREEK SOUTH 78.0
END DESCRIPTION:
XS GIS Cut Line= 3
        2289125.       13720975.        2290325.       13720275.
      2291125.02       13720375.
#Sta/Elev= 30
  3614.3   538.6  3834.3  530.29  4001.7  525.29  4030.1  526.04  4206.1     520
  4402.2  515.89  4446.9  514.89  4477.2  511.83    4483  513.18  4492.9  511.86
  4528.9  517.29  4551.6  513.54  4606.7  512.27  4690.8  511.08  4878.3  512.17
  4931.2   510.4  4958.5   511.2  4968.4  510.66  4973.4  507.95  4973.9  507.45
  4987.3  507.95  4995.7  508.36  5000.7  510.72  5023.7  512.13    5127  510.17
  5164.8  512.29  5225.3  510.88    5347  514.95  5619.1  523.57  5809.8  528.45
#Mann= 11 ,-1 , 0
  3614.3     .07       0  4030.1    .035       0  4206.1     .07       0
  4402.2     .12       0  4446.9     .07       0  4606.7     .12       0
  4690.8      .1       0  4973.4     .05       0  4987.3      .1       0
    5347     .12       0  5619.1     .07       0
Bank Sta=4973.4,4987.3
XS Rating Curve= 0 ,0
Exp/Cntr=0.3,0.1

Type RM Length L Ch R = 1 ,43636   ,452,452,452
BEGIN DESCRIPTION:
COTTONWOOD CREEK SOUTH 77.0
END DESCRIPTION:
XS GIS Cut Line= 3
      2289075.03     13721074.99        2290275.       13720675.
      2291275.02       13720475.
#Sta/Elev= 30
  3734.3  540.88  3829.1  538.35  3945.1  532.96  3966.2  533.11  4029.4  529.53
    4177  524.87  4202.8  525.68  4240.2  523.04  4371.5  520.28  4715.9  512.78
  4787.7  510.53  4890.8  509.37  4946.5  510.86  4967.6  510.27  4981.6  505.38
  4982.1  504.88  4995.6  505.38  4996.5   508.5  5001.7   508.5  5009.4  510.31
  5122.1  510.99  5162.6  510.76  5213.3  511.24  5274.5  509.49  5315.3  510.47
  5366.3  509.81  5401.5  511.06  5570.3  517.06    5743     525    6019  532.92
#Mann= 12 ,-1 , 0
  3734.3     .07       0  4202.8    .035       0  4371.5     .07       0
  4715.9    .035       0  4787.7     .07       0  4890.8     .12       0
  4981.6     .05       0  4995.6     .12       0  5122.1     .12       0
  5162.6      .1       0  5401.5     .12       0    5743     .07       0
Bank Sta=4981.6,4995.6
XS Rating Curve= 0 ,0
Exp/Cntr=0.3,0.1

Type RM Length L Ch R = 1 ,43184   ,547,547,547
BEGIN DESCRIPTION:
COTTONWOOD CREEK SOUTH 76.0
END DESCRIPTION:
XS GIS Cut Line= 3
      2289725.03     13721524.98        2290325.       13721075.
      2291325.01       13720575.
#Sta/Elev= 30
  4250.1  525.36    4365  521.89  4378.2   520.9  4392.8   521.9  4436.5  519.11
  4478.2  518.88  4500.1  517.26    4531  517.23  4539.2     517    4665  512.56
  4684.8  512.15  4790.9  510.08  4871.9  508.85  4950.1  511.38  4963.6   510.3
  4971.1  504.34  4971.6  503.84  4985.2  504.34  4986.5     506  4992.8  508.33
  5044.8  510.21  5178.9   509.6  5335.5   510.2  5402.6  509.62  5416.5  508.69
    5478   510.1  5679.3  516.92  5825.8  523.92  5947.6  528.96  6118.1  534.42
#Mann= 11 ,-1 , 0
  4250.1     .05       0    4365    .035       0    4531     .07       0
  4539.2    .035       0    4665     .12       0  4684.8     .07       0
  4790.9     .12       0  4971.1     .05       0  4985.2     .12       0
    5478     .12       0  5825.8     .07       0
Bank Sta=4971.1,4985.2
XS Rating Curve= 0 ,0
Exp/Cntr=0.3,0.1

Type RM Length L Ch R = 1 ,42637   ,367,367,367
BEGIN DESCRIPTION:
COTTONWOOD CREEK SOUTH 75.0
END DESCRIPTION:
XS GIS Cut Line= 3
      2289725.01     13722474.99      2290728.77     13721274.69
      2291224.98     13720725.02
#Sta/Elev= 30
  3473.3  537.05  3529.9  536.32  3864.3  525.31  3881.3  525.45  4055.6  519.36
  4181.9  516.14    4204  514.71  4218.3  516.34  4226.1  516.35  4246.9  515.07
  4322.7  514.13  4543.3  510.62  4672.6  507.47  4716.6  508.39  4779.1  509.36
  4985.4   509.4  4999.1  507.97  5006.2  503.98  5006.7  503.48  5020.5  503.98
  5021.2  505.17  5027.7  507.81  5042.1  508.92  5091.5  508.13  5113.1  506.57
  5155.6  508.24  5264.7  509.77  5332.8  511.26  5440.3  515.11  5778.5  529.05
#Mann= 10 ,-1 , 0
  3473.3    .045       0  3881.3     .05       0  4181.9    .035       0
  4322.7     .07       0  4543.3     .12       0  4716.6      .1       0
  5006.2     .05       0  5020.5      .1       0  5264.7     .12       0
  5440.3     .07       0
Bank Sta=5006.2,5020.5
XS Rating Curve= 0 ,0
Exp/Cntr=0.3,0.1

Type RM Length L Ch R = 1 ,42270   ,444,444,444
BEGIN DESCRIPTION:
COTTONWOOD CREEK SOUTH 74.0
END DESCRIPTION:
XS GIS Cut Line= 3
      2289775.03     13722474.98        2290975.       13721475.
      2291325.01     13721124.99
#Sta/Elev= 30
  3442.6  536.79    3804  527.61  4094.5  517.27    4124  515.47  4145.5  516.63
  4159.2  515.04  4262.5  512.54  4297.1  511.55  4391.3  509.34  4422.9  508.75
  4537.9  506.94    4564  505.69  4600.4   508.1  4635.6  508.13  4649.9  505.96
  4656.4  507.22  4664.2   504.7  4699.4  507.95  4720.2  508.57  4848.4  507.44
  4912.8  508.28  4954.5  507.74  4983.7  504.16  4984.2  503.66  4998.2  504.16
  5061.2  508.18  5205.5  511.17  5414.7  519.66  5469.8  522.94  5499.6  528.45
#Mann= 12 ,-1 , 0
  3442.6    .045       0    3804     .05       0  4094.5    .035       0
  4262.5     .07       0  4297.1    .035       0  4391.3     .07       0
  4422.9     .12       0  4537.9      .1       0  4983.7     .05       0
  4998.2      .1       0  5205.5    .035       0  5469.8     .07       0
Bank Sta=4983.7,4998.2
XS Rating Curve= 0 ,0
Exp/Cntr=0.3,0.1

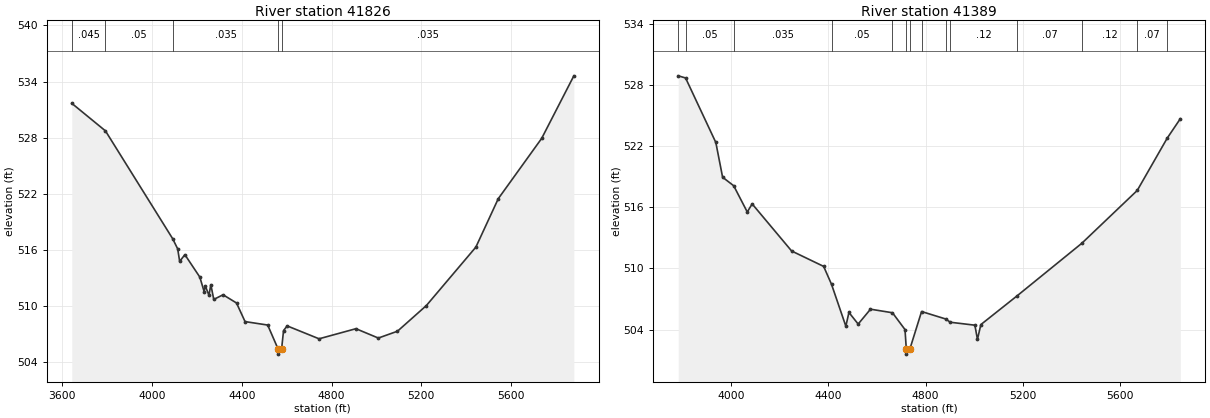
Type RM Length L Ch R = 1 ,41826   ,437,437,437
BEGIN DESCRIPTION:
COTTONWOOD CREEK SOUTH 73.0
END DESCRIPTION:
XS GIS Cut Line= 3
      2289975.01       13722375.      2290870.06     13722028.24
      2291887.38     13721255.83
#Sta/Elev= 30
  3642.2  531.67  3792.3  528.72  4091.7  517.19  4114.1   516.1    4123  514.76
  4146.2  515.48  4212.8  513.08    4232  511.53  4237.4  512.13  4253.5  511.13
  4261.9  512.27  4274.9  510.69  4316.4  511.19  4376.3  510.31  4414.3  508.32
  4515.2  507.95  4562.4  505.34  4562.9  504.84  4576.9  505.34  4585.9  507.36
    4602  507.86  4744.1  506.48  4908.4  507.56  5008.2  506.56  5093.5  507.29
  5222.4  510.04  5442.9  516.29  5542.7  521.47  5736.1  527.92  5879.4  534.61
#Mann= 5 ,-1 , 0
  3642.2    .045       0  3792.3     .05       0  4091.7    .035       0
  4562.4    .035       0  4576.9    .035       0
Bank Sta=4562.4,4576.9
XS Rating Curve= 0 ,0
Exp/Cntr=0.3,0.1

Type RM Length L Ch R = 1 ,41389   ,926,926,926
BEGIN DESCRIPTION:
COTTONWOOD CREEK SOUTH 72.0
END DESCRIPTION:
XS GIS Cut Line= 3
      2290124.99       13722375.        2291325.       13722175.
      2291925.01     13721574.99
#Sta/Elev= 30
  3782.7   528.9  3812.9  528.69  3937.3  522.36  3965.2  518.95  4010.9  518.11
  4066.6  515.54  4086.8  516.33  4249.1  511.71  4380.8   510.2  4413.2  508.44
  4472.1  504.33  4484.8  505.68  4522.8  504.54  4573.5     506  4663.9  505.65
  4715.4     504  4720.8  502.09  4721.3  501.59  4735.4  502.09  4783.6  505.77
  4883.9  505.03  4901.3  504.72  5002.8  504.43  5013.4  503.04  5027.5  504.49
  5176.5  507.31  5442.3  512.46  5670.6  517.65  5793.8  522.78  5847.8  524.69
#Mann= 14 ,-1 , 0
  3782.7    .045       0  3812.9     .05       0  4010.9    .035       0
  4413.2     .05       0  4663.9     .07       0  4720.8     .05       0
  4735.4     .07       0  4783.6     .12       0  4883.9     .07       0
  4901.3     .12       0  5176.5     .07       0  5442.3     .12       0
  5670.6     .07       0  5793.8     .12       0
Bank Sta=4720.8,4735.4
XS Rating Curve= 0 ,0
Exp/Cntr=0.3,0.1