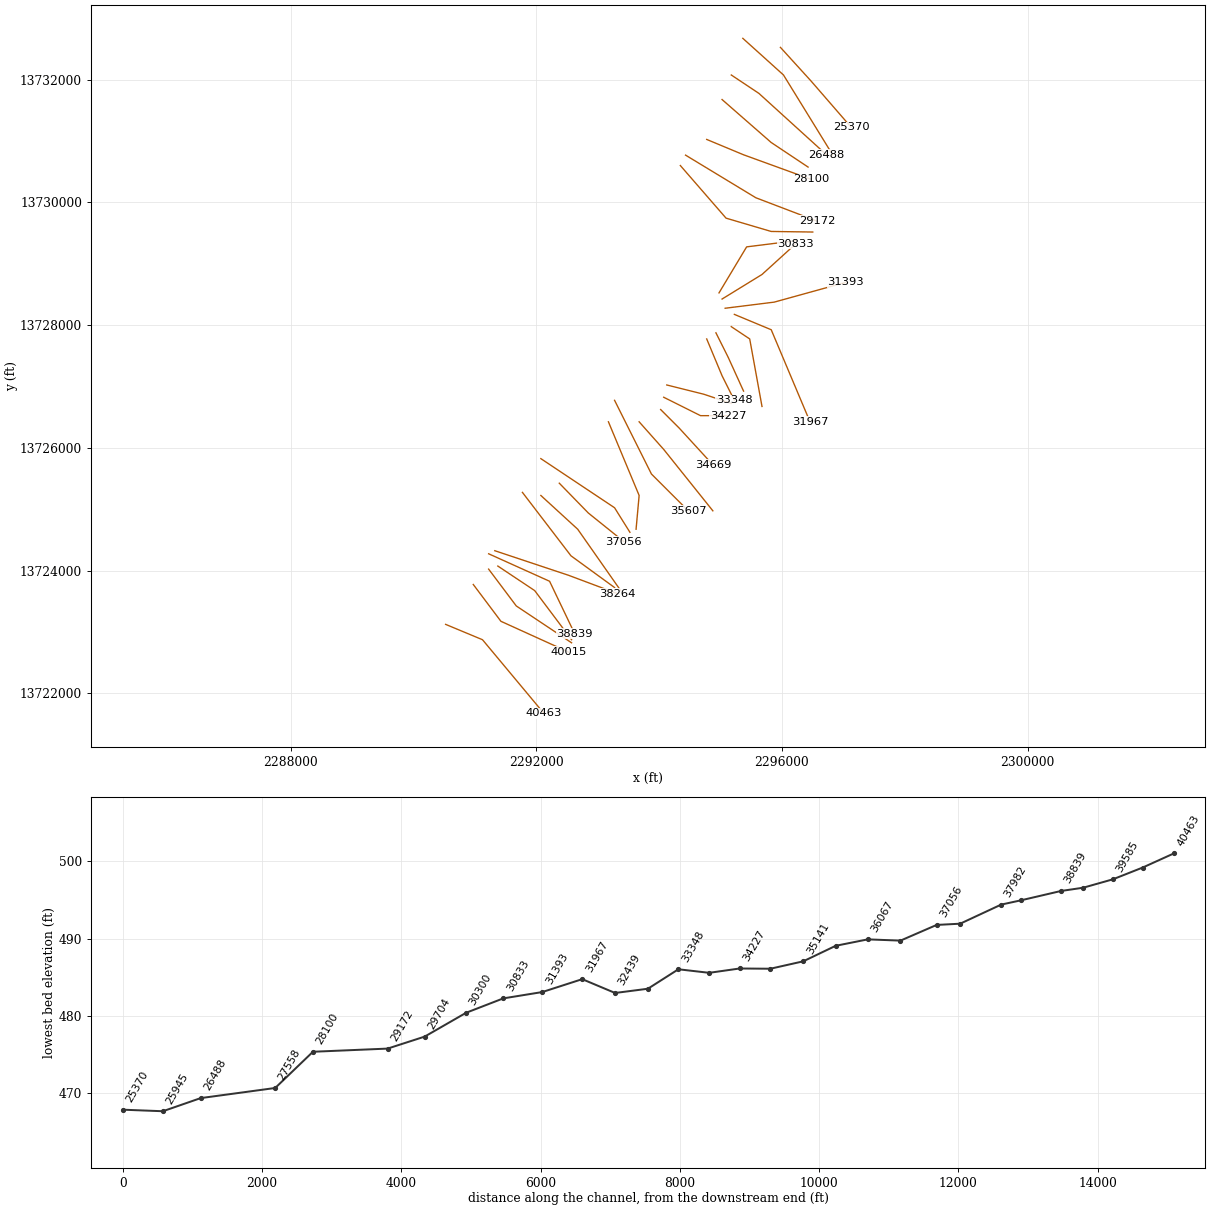
HEC-RAS study COTTONWOOD CREEK SOUTH.prj: COTTONWOOD CREEK SOUTH Base Level Engineering

--- COTTONWOOD CREEK SOUTH.g01 (geometry) --- (continued)

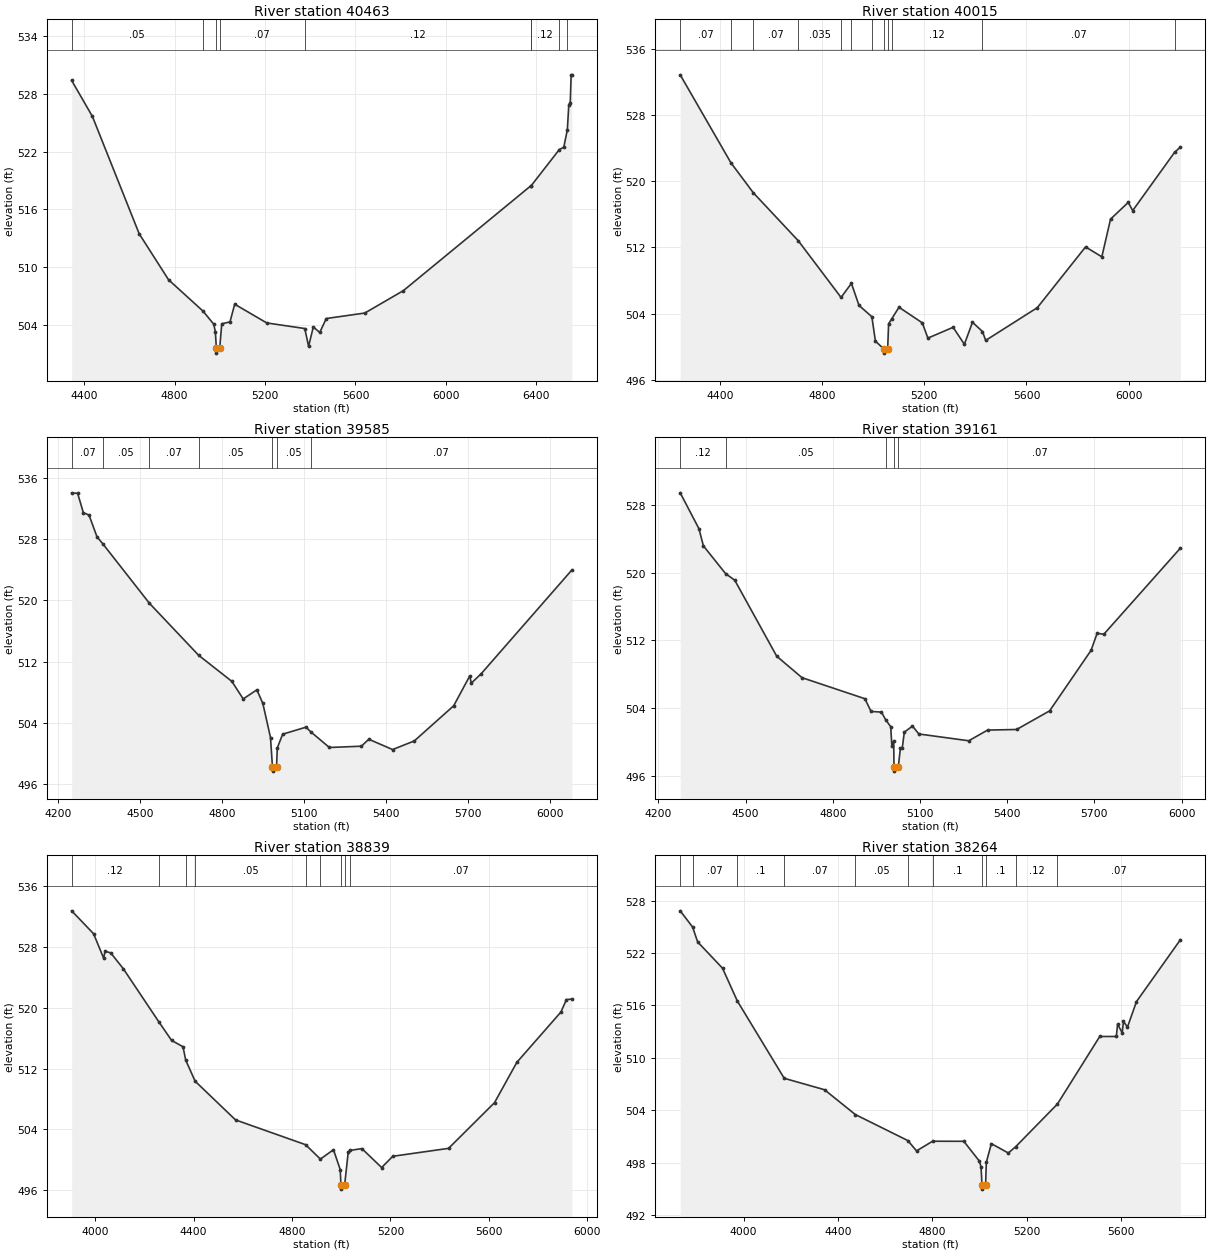
Type RM Length L Ch R = 1 ,40463   ,448,448,448
BEGIN DESCRIPTION:
COTTONWOOD CREEK SOUTH 71.0
END DESCRIPTION:
XS GIS Cut Line= 3
      2290525.01       13723125.        2291125.       13722875.
      2292124.97     13721675.03
#Sta/Elev= 30
    4345  529.39  4436.5  525.66  4643.5  513.45  4773.5  508.66  4925.5  505.41
  4973.3  504.04  4980.4  503.25  4984.9  501.53  4985.4  501.03  4999.6  501.53
  5008.7  504.08  5045.1  504.28  5065.9  506.12  5207.8  504.17  5375.8  503.59
  5392.7  501.74  5413.5  503.75  5442.1  503.18  5470.8  504.63  5641.3   505.2
  5811.8  507.53  6376.8  518.46  6377.5  518.46  6501.6  522.21  6521.2  522.45
    6537  524.27  6543.4  526.85  6549.9  527.09  6553.8  529.98    6557  529.98
#Mann= 9 ,-1 , 0
    4345     .05       0  4925.5     .07       0  4984.9     .05       0
  4999.6     .07       0  5375.8     .12       0  6376.8     .07       0
  6377.5     .12       0  6501.6     .07       0    6537     .12       0
Bank Sta=4984.9,4999.6
XS Rating Curve= 0 ,0
Exp/Cntr=0.3,0.1

Type RM Length L Ch R = 1 ,40015   ,430,430,430
BEGIN DESCRIPTION:
COTTONWOOD CREEK SOUTH 70.0
END DESCRIPTION:
XS GIS Cut Line= 3
      2290975.02     13723774.98        2291425.       13723175.
      2292525.02     13722674.99
#Sta/Elev= 30
  4244.3  532.92  4442.7  522.27  4530.8  518.62  4706.7  512.81    4874  505.95
  4914.6  507.65  4944.3  504.98  4994.6  503.61  5008.6  500.65  5041.8   499.7
  5042.3   499.2  5056.5   499.7  5060.2  502.76    5072  503.33  5100.8  504.76
    5192  502.87    5214  501.02  5312.8  502.33  5356.8  500.27  5388.6  502.94
  5427.7  501.82  5440.2  500.74  5642.4  504.71  5831.3  512.07    5895  510.87
  5929.1  515.44  5998.3  517.46  6015.8  516.47  6180.1  523.54  6202.6  524.17
#Mann= 12 ,-1 , 0
  4244.3     .07       0  4442.7     .05       0  4530.8     .07       0
  4706.7    .035       0    4874     .05       0  4914.6    .035       0
  4994.6      .1       0  5041.8     .05       0  5056.5      .1       0
    5072     .12       0  5427.7     .07       0  6180.1     .12       0
Bank Sta=5041.8,5056.5
XS Rating Curve= 0 ,0
Exp/Cntr=0.3,0.1

Type RM Length L Ch R = 1 ,39585   ,424,424,424
BEGIN DESCRIPTION:
COTTONWOOD CREEK SOUTH 69.0
END DESCRIPTION:
XS GIS Cut Line= 3
      2291224.99     13724025.01        2291675.       13723425.
      2292575.02     13722824.99
#Sta/Elev= 30
  4250.1  534.06    4272  533.99  4292.8  531.47  4313.7  531.15  4342.8  528.31
  4365.8  527.32  4534.5  519.63  4715.3  512.81  4836.6  509.41  4878.2  507.11
  4928.2   508.3  4950.1  506.53  4978.2  502.06  4985.5  498.17    4986  497.67
  5000.2  498.17  5003.1   500.7  5022.7   502.5  5108.3  503.42  5125.3  502.82
  5193.9  500.76  5311.1  500.93  5338.1  501.84  5425.3  500.49  5504.9  501.62
  5649.1  506.22  5707.7  510.11  5713.7  509.18  5749.8  510.41  6081.8  523.97
#Mann= 7 ,-1 , 0
  4250.1     .07       0  4365.8     .05       0  4534.5     .07       0
  4715.3     .05       0  4985.5     .05       0  5000.2     .05       0
  5125.3     .07       0
Bank Sta=4985.5,5000.2
XS Rating Curve= 0 ,0
Exp/Cntr=0.3,0.1

Type RM Length L Ch R = 1 ,39161   ,322,322,322
BEGIN DESCRIPTION:
COTTONWOOD CREEK SOUTH 68.0
END DESCRIPTION:
XS GIS Cut Line= 3
      2291374.97     13724075.02        2291975.       13723675.
      2292575.03     13722874.96
#Sta/Elev= 30
  4274.8  529.41  4339.4  525.17  4354.5  523.16  4430.8  519.89  4462.6   519.1
  4606.9  510.14    4694  507.61  4910.3  505.13  4931.4  503.63  4967.4  503.55
  4981.4  502.67  4999.1  501.83  5003.2   499.5  5009.5  500.17  5010.4  497.09
  5010.9  496.59  5025.2  497.09  5032.4  499.26  5038.7  499.27    5046  501.19
  5074.1   501.9    5096  500.97  5267.8  500.17  5332.4  501.43  5432.4   501.5
    5546   503.7  5688.7  510.84  5709.5  512.85  5732.4  512.73    5996  522.89
#Mann= 5 ,-1 , 0
  4274.8     .12       0  4430.8     .05       0  4981.4     .07       0
  5010.4     .05       0  5025.2     .07       0
Bank Sta=5010.4,5025.2
XS Rating Curve= 0 ,0
Exp/Cntr=0.3,0.1

Type RM Length L Ch R = 1 ,38839   ,575,575,575
BEGIN DESCRIPTION:
COTTONWOOD CREEK SOUTH 67.0
END DESCRIPTION:
XS GIS Cut Line= 3
      2291224.96     13724275.02      2292217.03     13723827.35
      2292625.02     13722974.96
#Sta/Elev= 30
  3904.1  532.75  3993.3  529.73  4034.1  526.52  4039.6  527.43  4062.7  527.23
  4114.4  525.12  4258.3  518.16  4310.4  515.71  4356.7  514.88  4367.7  513.12
  4405.9  510.35  4570.3  505.26  4855.2     502  4915.1  500.11  4968.3  501.34
  4995.9  498.73  4998.8  496.66  4999.3  496.16  5013.6  496.66  5028.4  501.06
  5034.4  501.24  5083.8  501.49  5164.2     499  5209.6  500.48  5436.2  501.52
  5623.1  507.53  5713.8  512.83  5893.1  519.45  5915.3  521.08  5937.5  521.15
#Mann= 9 ,-1 , 0
  3904.1     .12       0  4258.3      .1       0  4367.7     .07       0
  4405.9     .05       0  4855.2     .07       0  4915.1     .12       0
  4998.8     .05       0  5013.6     .12       0  5034.4     .07       0
Bank Sta=4998.8,5013.6
XS Rating Curve= 0 ,0
Exp/Cntr=0.3,0.1

Type RM Length L Ch R = 1 ,38264   ,282,282,282
BEGIN DESCRIPTION:
COTTONWOOD CREEK SOUTH 66.0
END DESCRIPTION:
XS GIS Cut Line= 3
      2291324.96     13724325.01        2292525.       13723925.
      2293325.04     13723624.98
#Sta/Elev= 30
  3731.2  526.84  3783.8  524.98    3805  523.28  3910.4  520.27    3973  516.52
  4171.9  507.65  4342.6  506.34    4473   503.5  4695.9  500.51  4732.6  499.33
  4800.7  500.44  4932.9  500.43  4998.8  498.16  5005.9  497.49  5009.9  495.45
  5010.4  494.95  5025.1  495.45  5028.2  498.01  5049.6  500.16  5121.6  499.09
  5153.3  499.83  5329.5   504.7  5508.8  512.44  5579.1  512.44  5584.4  513.86
    5604  512.86  5609.4  514.17  5626.3  513.52  5664.5  516.44  5850.6  523.53
#Mann= 11 ,-1 , 0
  3731.2     .12       0  3783.8     .07       0    3973      .1       0
  4171.9     .07       0    4473     .05       0  4695.9     .12       0
  4800.7      .1       0  5009.9     .05       0  5025.1      .1       0
  5153.3     .12       0  5329.5     .07       0
Bank Sta=5009.9,5025.1
XS Rating Curve= 0 ,0
Exp/Cntr=0.3,0.1

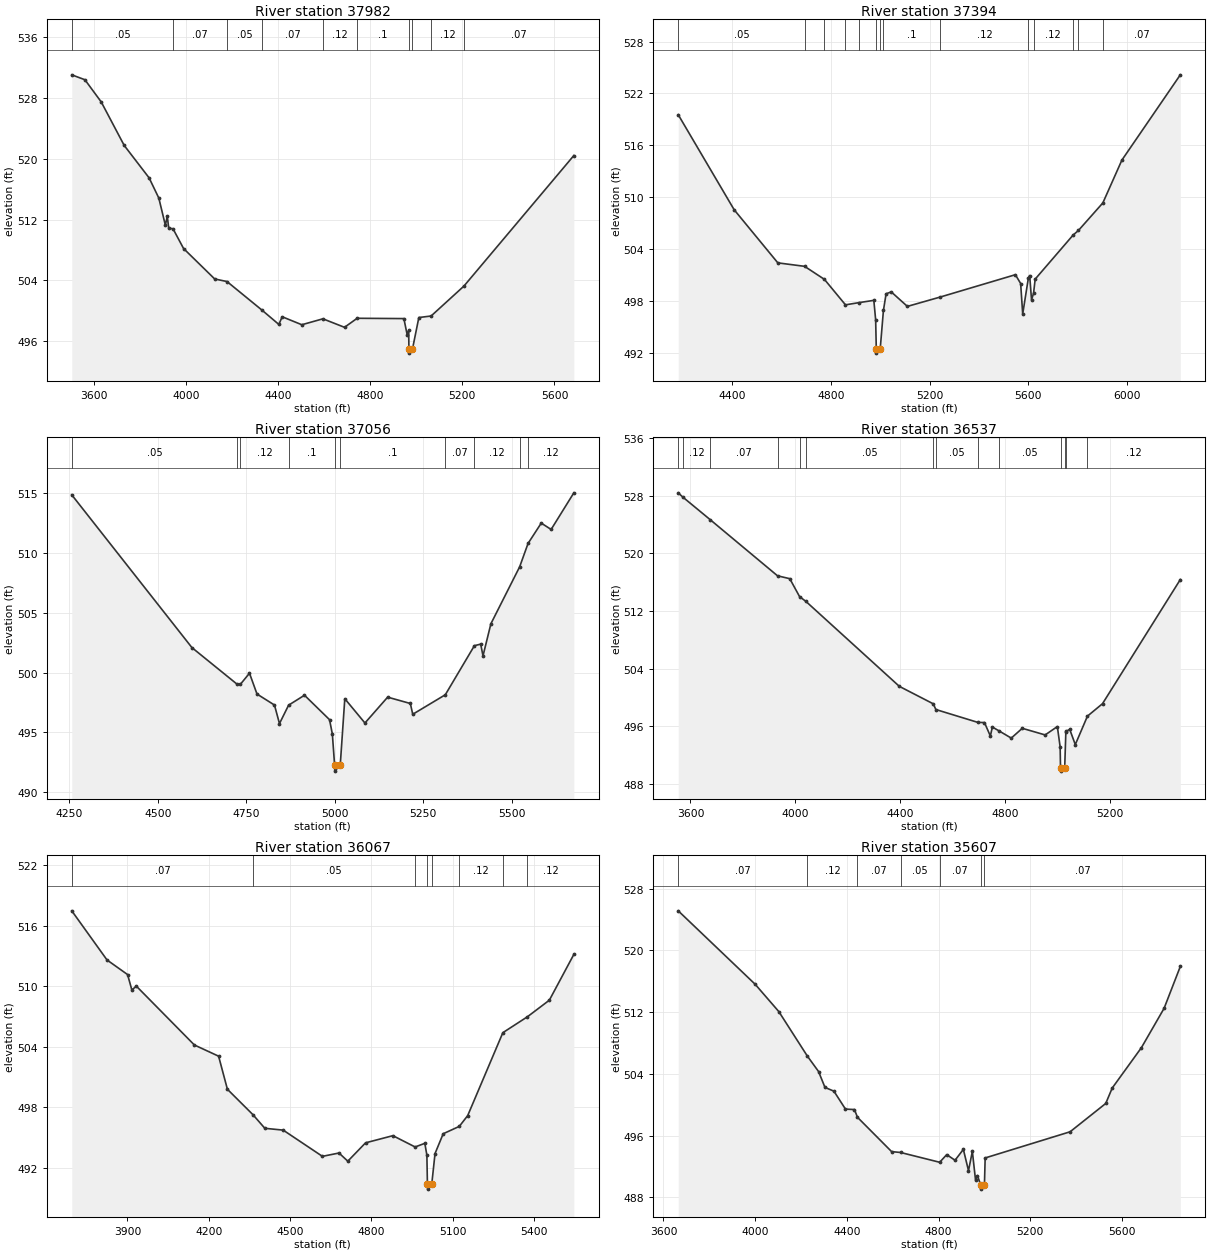
Type RM Length L Ch R = 1 ,37982   ,588,588,588
BEGIN DESCRIPTION:
COTTONWOOD CREEK SOUTH 65.0
END DESCRIPTION:
XS GIS Cut Line= 3
        2291775.       13725275.      2292565.55      13724241.8
      2293275.02     13723724.98
#Sta/Elev= 30
  3505.5  531.06  3562.6  530.41  3633.3  527.49    3733  521.76    3841  517.49
  3883.2  514.83  3911.7  511.24  3919.9  512.43  3926.2  510.86  3944.9  510.78
  3990.6  508.18  4125.7  504.17  4179.1  503.83  4330.3  500.08  4404.1  498.18
  4418.6  499.19  4503.8  498.14  4595.3  498.92  4689.1   497.8  4743.8  498.99
  4946.7  498.95  4961.4  496.75  4967.6  497.39  4968.5   494.9    4969   494.4
  4983.7   494.9  5011.6  499.09  5064.8  499.29  5207.2  503.23  5684.2  520.43
#Mann= 10 ,-1 , 0
  3505.5     .05       0  3944.9     .07       0  4179.1     .05       0
  4330.3     .07       0  4595.3     .12       0  4743.8      .1       0
  4968.5     .05       0  4983.7      .1       0  5064.8     .12       0
  5207.2     .07       0
Bank Sta=4968.5,4983.7
XS Rating Curve= 0 ,0
Exp/Cntr=0.3,0.1

Type RM Length L Ch R = 1 ,37394   ,338,338,338
BEGIN DESCRIPTION:
COTTONWOOD CREEK SOUTH 64.0
END DESCRIPTION:
XS GIS Cut Line= 3
      2292075.02     13725224.98        2292675.       13724675.
      2293375.02     13723674.98
#Sta/Elev= 30
  4181.5  519.53  4408.1  508.53  4585.1  502.38  4693.4  501.98  4773.9  500.47
  4859.2  497.52  4912.5  497.77  4974.1  498.04  4981.5  495.79  4984.1  492.43
  4984.6  491.93    5000  492.43    5013  496.87  5023.8   498.8  5044.7  499.02
  5110.1  497.34    5244  498.43  5547.8  501.01  5569.1  499.99  5577.4  496.46
  5600.4  500.63  5605.7  500.91  5613.2  498.09  5621.4  498.86    5628   500.5
  5781.7   505.6  5803.2  506.13  5902.2  509.32  5979.4  514.28  6216.1  524.15
#Mann= 14 ,-1 , 0
  4181.5     .05       0  4693.4     .07       0  4773.9     .12       0
  4859.2     .07       0  4912.5     .12       0  4984.1     .05       0
    5000     .12       0    5013      .1       0    5244     .12       0
  5600.4      .1       0  5621.4     .12       0  5781.7     .07       0
  5803.2     .12       0  5902.2     .07       0
Bank Sta=4984.1,5000
XS Rating Curve= 0 ,0
Exp/Cntr=0.3,0.1

Type RM Length L Ch R = 1 ,37056   ,519,519,519
BEGIN DESCRIPTION:
COTTONWOOD CREEK SOUTH 63.0
END DESCRIPTION:
XS GIS Cut Line= 3
      2292374.97     13725425.03      2292848.13     13724938.83
      2293425.04     13724474.97
#Sta/Elev= 30
  4257.2  514.85  4596.7  502.09  4724.4  499.03  4733.8  499.03  4759.4  499.95
  4780.6  498.21    4830  497.29  4844.1  495.74  4869.9  497.28  4914.8  498.11
  4985.5  496.07  4993.5  494.88  4999.9  492.27  5000.4  491.77  5015.8  492.27
  5028.7  497.82  5085.6  495.79  5149.8  497.95  5213.9  497.42  5220.7  496.52
  5312.7  498.15  5394.9  502.25  5412.7  502.38  5419.2   501.4  5441.5  504.08
  5522.8  508.84  5546.5  510.79  5583.8  512.49  5611.7  511.96  5675.9  515.02
#Mann= 10 ,-1 , 0
  4257.2     .05       0  4724.4      .1       0  4733.8     .12       0
  4869.9      .1       0  4999.9     .05       0  5015.8      .1       0
  5312.7     .07       0  5394.9     .12       0  5522.8     .07       0
  5546.5     .12       0
Bank Sta=4999.9,5015.8
XS Rating Curve= 0 ,0
Exp/Cntr=0.3,0.1

Type RM Length L Ch R = 1 ,36537   ,470,470,470
BEGIN DESCRIPTION:
COTTONWOOD CREEK SOUTH 62.0
END DESCRIPTION:
XS GIS Cut Line= 3
      2292074.99     13725825.01        2293275.       13725025.
      2293524.98     13724625.02
#Sta/Elev= 30
  3553.5  528.41  3569.9  527.85    3676  524.66    3932  516.88  3978.7  516.48
    4016  513.99  4040.3  513.32  4396.3  501.52  4525.8  499.09  4535.5   498.3
  4695.8  496.51  4720.8  496.49  4743.3  494.62  4750.9  495.87  4776.9  495.32
    4823  494.33    4865  495.69  4952.2  494.77  4998.7  495.93  5009.3  493.11
  5010.7  490.24  5011.2  489.74  5026.7  490.24  5031.1  495.21  5032.2  495.27
  5045.8  495.54  5067.1  493.43  5113.4  497.38  5170.8  499.11  5467.4  516.36
#Mann= 14 ,-1 , 0
  3553.5     .07       0  3569.9     .12       0    3676     .07       0
    3932     .12       0    4016     .07       0  4040.3     .05       0
  4525.8      .1       0  4535.5     .05       0  4695.8     .12       0
  4776.9     .05       0  5010.7     .05       0  5026.7     .05       0
  5032.2     .07       0  5113.4     .12       0
Bank Sta=5010.7,5026.7
XS Rating Curve= 0 ,0
Exp/Cntr=0.3,0.1

Type RM Length L Ch R = 1 ,36067   ,460,460,460
BEGIN DESCRIPTION:
COTTONWOOD CREEK SOUTH 61.0
END DESCRIPTION:
XS GIS Cut Line= 3
      2293174.99     13726425.03        2293675.       13725225.
        2293625.       13724675.
#Sta/Elev= 30
  3694.6  517.49  3824.6  512.62  3900.5  511.17  3916.2  509.65    3933  510.02
  4146.9  504.19  4236.3  503.08  4268.8   499.8    4363  497.28  4406.9  495.93
  4474.6  495.75  4619.3  493.15  4680.5  493.48    4713  492.67  4778.5  494.49
  4879.3   495.2  4961.3  494.08  4997.1  494.44  5004.7  493.27  5006.7   490.4
  5007.2   489.9  5022.7   490.4  5034.8  493.43  5064.9  495.39  5124.3  496.12
  5155.3  497.19    5285  505.41  5375.8  506.99  5456.5  508.63  5546.9  513.17
#Mann= 8 ,-1 , 0
  3694.6     .07       0    4363     .05       0  4961.3     .07       0
  5006.7     .05       0  5022.7     .07       0  5124.3     .12       0
    5285     .07       0  5375.8     .12       0
Bank Sta=5006.7,5022.7
XS Rating Curve= 0 ,0
Exp/Cntr=0.3,0.1

Type RM Length L Ch R = 1 ,35607   ,466,466,466
BEGIN DESCRIPTION:
COTTONWOOD CREEK SOUTH 60.0
END DESCRIPTION:
XS GIS Cut Line= 3
      2293274.99     13726775.02        2293875.       13725575.
      2294475.01     13724974.99
#Sta/Elev= 30
  3664.4  525.13  3999.8  515.62  4103.3  512.07  4227.6  506.31  4276.5  504.31
  4304.5  502.25  4343.6  501.76  4393.9  499.44  4433.1  499.38  4446.2  498.38
  4595.2  493.93  4634.1  493.82  4804.9  492.55  4835.6  493.54  4871.9  492.81
  4908.2  494.22  4930.6  491.46  4947.4  493.96  4961.3  490.25  4969.7  490.83
  4984.1  489.57  4984.6  489.07  5000.1  489.57  5003.3  493.11  5373.8   496.5
  5529.3  500.17  5557.6  502.17  5684.9   507.4  5783.9   512.5  5854.6  517.92
#Mann= 7 ,-1 , 0
  3664.4     .07       0  4227.6     .12       0  4446.2     .07       0
  4634.1     .05       0  4804.9     .07       0  4984.1     .05       0
  5000.1     .07       0
Bank Sta=4984.1,5000.1
XS Rating Curve= 0 ,0
Exp/Cntr=0.3,0.1

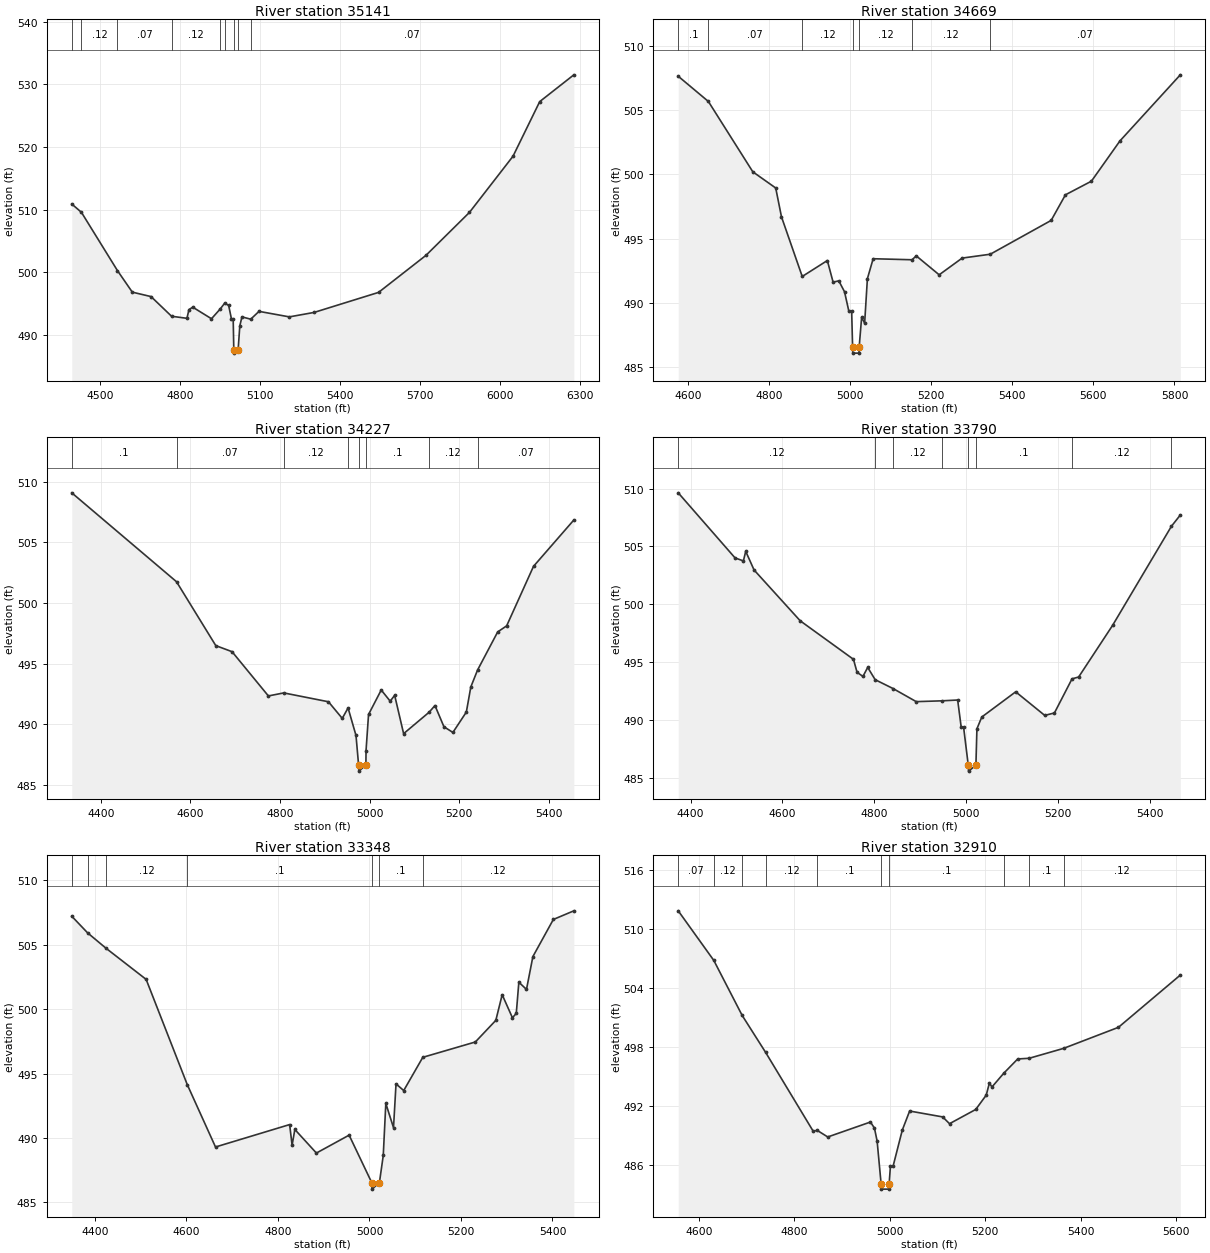
Type RM Length L Ch R = 1 ,35141   ,472,472,472
BEGIN DESCRIPTION:
COTTONWOOD CREEK SOUTH 59.0
END DESCRIPTION:
XS GIS Cut Line= 3
      2293674.99     13726425.01        2294075.       13725975.
      2294874.99     13724975.01
#Sta/Elev= 30
  4393.5  510.88  4429.7  509.55  4564.8  500.24  4620.5   496.8  4690.8  496.09
  4767.7  492.95  4825.4  492.62  4832.9  494.01  4847.2   494.4  4917.4  492.55
  4949.9   494.1    4967  495.04  4981.8  494.68  4992.2  492.53  4998.8  492.53
  5001.1  487.56  5001.6  487.06  5017.3  487.56  5023.6  491.41  5031.6  492.85
  5064.6  492.48  5095.6  493.73  5209.3  492.85  5302.1  493.56  5543.9  496.76
  5721.5  502.67  5884.8  509.54  6048.1  518.51  6148.2  527.23  6276.2  531.51
#Mann= 9 ,-1 , 0
  4393.5     .07       0  4429.7     .12       0  4564.8     .07       0
  4767.7     .12       0  4949.9     .07       0    4967     .12       0
  5001.1     .05       0  5017.3     .12       0  5064.6     .07       0
Bank Sta=5001.1,5017.3
XS Rating Curve= 0 ,0
Exp/Cntr=0.3,0.1

Type RM Length L Ch R = 1 ,34669   ,442,442,442
BEGIN DESCRIPTION:
COTTONWOOD CREEK SOUTH 58.0
END DESCRIPTION:
XS GIS Cut Line= 3
      2294024.99     13726625.01        2294325.       13726325.
      2294874.99     13725725.02
#Sta/Elev= 30
  4576.2  507.63  4650.5  505.67  4760.1   500.2  4816.6  498.94  4830.8   496.7
    4882  492.06  4943.9   493.3  4958.1  491.62  4972.2  491.72  4986.3  490.87
  4996.9  489.37  5003.9  489.37  5006.2   486.6  5006.7   486.1    5022   486.1
  5022.5   486.6  5028.5  488.89  5035.9  488.43  5042.7  491.89  5056.9  493.44
  5152.7  493.36  5163.3  493.66  5219.7  492.19  5276.4  493.49  5345.7  493.79
  5495.9  496.42  5531.1  498.41  5595.2  499.47  5665.5   502.6  5814.4  507.74
#Mann= 7 ,-1 , 0
  4576.2      .1       0  4650.5     .07       0    4882     .12       0
  5006.2     .05       0  5022.5     .12       0  5152.7     .12       0
  5345.7     .07       0
Bank Sta=5006.2,5022.5
XS Rating Curve= 0 ,0
Exp/Cntr=0.3,0.1

Type RM Length L Ch R = 1 ,34227   ,437,437,437
BEGIN DESCRIPTION:
COTTONWOOD CREEK SOUTH 57.0
END DESCRIPTION:
XS GIS Cut Line= 3
      2294074.98     13726825.01        2294675.       13726525.
      2295124.95       13726525.
#Sta/Elev= 30
  4335.2  509.08    4569  501.75  4656.7  496.48    4693  495.98  4774.1  492.33
  4808.5  492.58  4908.2  491.85    4939  490.48    4952  491.34  4969.7  489.07
  4975.5  486.63    4976  486.13  4991.8  486.63  4992.1  487.82  4997.7   490.8
    5026  492.82    5046   491.9    5056  492.38    5076  489.22    5133  490.99
    5146  491.54    5166  489.79    5186  489.32    5216     491    5226  493.07
  5241.1  494.47    5286  497.61    5306  498.11    5366  503.02    5456  506.84
#Mann= 8 ,-1 , 0
  4335.2      .1       0    4569     .07       0  4808.5     .12       0
    4952      .1       0  4975.5     .05       0  4991.8      .1       0
    5133     .12       0  5241.1     .07       0
Bank Sta=4975.5,4991.8
XS Rating Curve= 0 ,0
Exp/Cntr=0.3,0.1

Type RM Length L Ch R = 1 ,33790   ,442,442,442
BEGIN DESCRIPTION:
COTTONWOOD CREEK SOUTH 56.0
END DESCRIPTION:
XS GIS Cut Line= 3
      2294124.96     13727025.01        2294725.       13726875.
      2295174.95     13726725.02
#Sta/Elev= 30
  4373.3  509.64    4497  504.01  4515.1  503.75  4520.2  504.58  4538.3  502.97
  4638.8  498.57  4754.7  495.24  4762.5  494.12  4775.3  493.76  4785.7  494.54
  4801.9  493.48    4841  492.71  4891.3  491.58  4947.2  491.65  4981.5  491.72
  4989.2  489.37  4994.4  489.37  5004.6  486.07  5005.1  485.57  5021.2  486.07
  5023.4  489.23    5034  490.25  5107.8  492.43    5171  490.39  5192.1   490.6
  5230.4  493.55  5244.8  493.71  5318.6  498.17  5446.8  506.75  5466.1  507.72
#Mann= 8 ,-1 , 0
  4373.3     .12       0  4801.9     .07       0    4841     .12       0
  4947.2      .1       0  5004.6     .05       0  5021.2      .1       0
  5230.4     .12       0  5446.8     .07       0
Bank Sta=5004.6,5021.2
XS Rating Curve= 0 ,0
Exp/Cntr=0.3,0.1

Type RM Length L Ch R = 1 ,33348   ,438,438,438
BEGIN DESCRIPTION:
COTTONWOOD CREEK SOUTH 55.0
END DESCRIPTION:
XS GIS Cut Line= 3
      2294775.02     13727774.95        2295025.       13727175.
      2295225.02     13726774.97
#Sta/Elev= 30
  4349.5  507.21  4384.1  505.92  4424.9  504.71    4512  502.31  4601.8  494.15
  4663.6   489.3  4825.6  491.04    4831  489.44    4837  490.66  4884.1  488.83
  4955.6  490.22  5005.1  486.53  5005.6  486.03  5021.8  486.53  5030.2  488.64
  5035.8  492.68  5052.6   490.8  5058.1   494.2  5074.9  493.68  5116.6  496.26
  5231.4  497.45  5276.2  499.13  5290.1  501.12  5312.5  499.33  5320.9  499.67
  5326.5  502.09  5343.2  501.53  5357.2  504.08  5401.9  506.96  5446.7  507.63
#Mann= 7 ,-1 , 0
  4349.5     .12       0  4384.1     .07       0  4424.9     .12       0
  4601.8      .1       0  5005.1     .05       0  5021.8      .1       0
  5116.6     .12       0
Bank Sta=5005.1,5021.8
XS Rating Curve= 0 ,0
Exp/Cntr=0.3,0.1

Type RM Length L Ch R = 1 ,32910   ,471,471,471
BEGIN DESCRIPTION:
COTTONWOOD CREEK SOUTH 54.0
END DESCRIPTION:
XS GIS Cut Line= 3
      2294924.99     13727875.02        2295125.       13727475.
        2295375.     13726924.99
#Sta/Elev= 30
  4557.1  511.84  4631.6  506.79    4691  501.19  4740.1  497.43  4839.4  489.43
  4848.5  489.48  4870.2  488.82  4959.6  490.34    4968  489.72  4973.6   488.4
    4982  484.01  4982.5  483.51  4998.2  483.51  4998.7  484.01  5001.5  485.86
  5007.1  485.86  5026.3  489.52  5041.7  491.46  5110.9  490.86  5125.2  490.17
  5180.1  491.62  5202.1  493.08  5208.7  494.31  5214.1  493.91    5239  495.32
    5268  496.76    5292  496.83  5364.2  497.84  5478.9  499.98  5608.5   505.3
#Mann= 10 ,-1 , 0
  4557.1     .07       0  4631.6     .12       0    4691      .1       0
  4740.1     .12       0  4848.5      .1       0    4982     .05       0
  4998.7      .1       0    5239     .12       0    5292      .1       0
  5364.2     .12       0
Bank Sta=4982,4998.7
XS Rating Curve= 0 ,0
Exp/Cntr=0.3,0.1

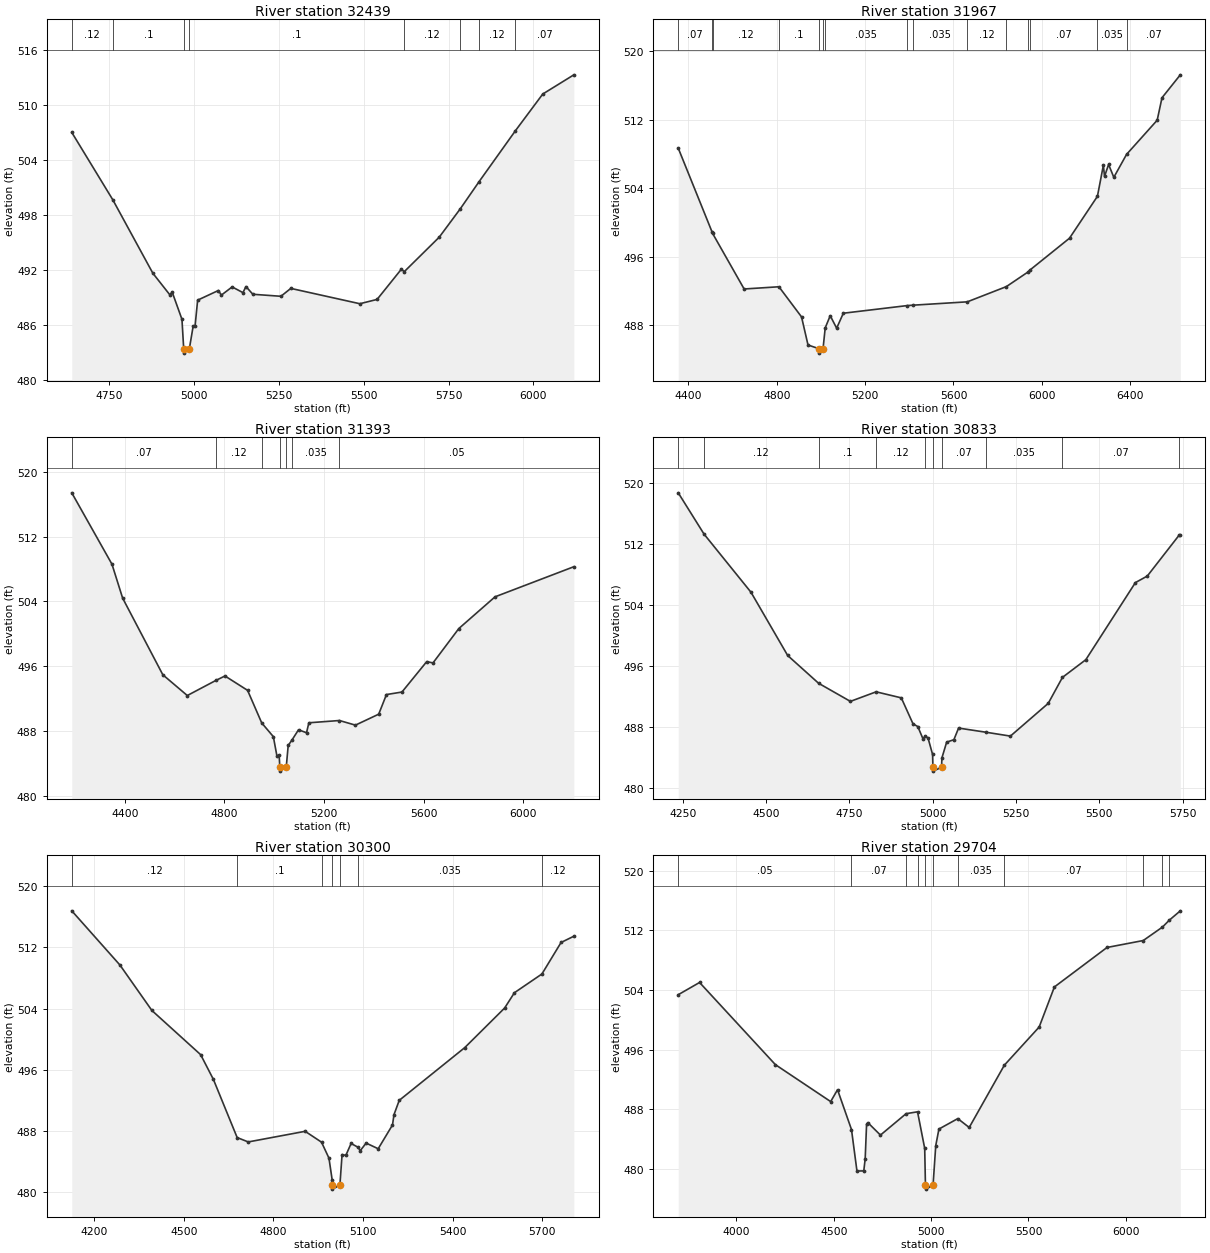
Type RM Length L Ch R = 1 ,32439   ,472,472,472
BEGIN DESCRIPTION:
COTTONWOOD CREEK SOUTH 53.0
END DESCRIPTION:
XS GIS Cut Line= 3
      2295175.03     13727974.98        2295475.       13727775.
      2295675.01     13726674.96
#Sta/Elev= 30
  4640.4     507  4761.4  499.65  4879.2  491.66  4928.8  489.33  4936.3  489.59
  4964.9  486.64    4970  483.46  4970.5  482.96  4986.8  483.46  4997.9   485.9
  5003.5   485.9  5011.1  488.73  5072.1  489.78    5081  489.28  5112.7  490.17
  5144.5  489.55  5153.4  490.21  5173.7  489.37  5256.3  489.15  5285.5  490.01
  5488.8  488.34  5539.6  488.81  5610.8  492.09  5619.8  491.84  5722.6  495.59
  5784.8  498.69  5840.2  501.65  5947.1  507.19  6027.5  511.18    6119  513.27
#Mann= 8 ,-1 , 0
  4640.4     .12       0  4761.4      .1       0    4970     .05       0
  4986.8      .1       0  5619.8     .12       0  5784.8     .07       0
  5840.2     .12       0  5947.1     .07       0
Bank Sta=4970,4986.8
XS Rating Curve= 0 ,0
Exp/Cntr=0.3,0.1

Type RM Length L Ch R = 1 ,31967   ,574,574,574
BEGIN DESCRIPTION:
COTTONWOOD CREEK SOUTH 52.0
END DESCRIPTION:
XS GIS Cut Line= 3
      2295225.04     13728174.98        2295825.       13727925.
      2296455.16     13726428.53
#Sta/Elev= 30
  4353.6  508.69  4507.4  498.86  4509.2  498.73    4652  492.24  4809.6   492.5
    4912  488.98  4941.3   485.7  4992.5  485.25    4993  484.75  5009.3  485.25
  5019.2   487.7  5041.9  489.12    5071  487.66  5101.2  489.41  5389.8   490.3
  5417.6  490.35  5662.6  490.74  5839.7  492.52  5935.5  494.19  5947.6  494.48
  6125.5  498.17  6251.9  503.06  6278.8  506.68  6284.2  505.39  6302.5  506.78
  6326.2  505.28  6383.9  507.96  6522.6  511.95  6544.3  514.57  6627.3  517.25
#Mann= 15 ,-1 , 0
  4353.6     .07       0  4507.4      .1       0  4509.2     .12       0
  4809.6      .1       0  4992.5     .05       0  5009.3      .1       0
  5019.2    .035       0  5389.8     .12       0  5417.6    .035       0
  5662.6     .12       0  5839.7    .035       0  5935.5     .05       0
  5947.6     .07       0  6251.9    .035       0  6383.9     .07       0
Bank Sta=4992.5,5009.3
XS Rating Curve= 0 ,0
Exp/Cntr=0.3,0.1

Type RM Length L Ch R = 1 ,31393   ,560,560,560
BEGIN DESCRIPTION:
COTTONWOOD CREEK SOUTH 51.0
END DESCRIPTION:
XS GIS Cut Line= 3
      2295074.95     13728274.99        2295875.       13728375.
      2297039.79     13728697.18
#Sta/Elev= 30
  4187.6  517.39  4348.9  508.59  4391.7  504.41    4553  494.96  4651.2   492.4
  4765.8  494.26  4802.4  494.81  4893.1  493.04  4949.9  489.02  4996.5  487.33
    5011  484.93  5019.8  485.05  5022.5  483.58    5023  483.08  5048.3  483.58
  5056.1  486.24  5072.2  486.96  5097.6  488.18  5129.6  487.81  5139.1  489.04
  5261.8  489.32  5325.9  488.75  5419.3   490.1  5450.4  492.52  5512.6  492.83
    5612  496.58  5637.2  496.42  5740.9  500.66  5886.2  504.57  6202.4  508.28
#Mann= 7 ,-1 , 0
  4187.6     .07       0  4765.8     .12       0  4949.9      .1       0
  5022.5     .05       0  5048.3      .1       0  5072.2    .035       0
  5261.8     .05       0
Bank Sta=5022.5,5048.3
XS Rating Curve= 0 ,0
Exp/Cntr=0.3,0.1

Type RM Length L Ch R = 1 ,30833   ,533,533,533
BEGIN DESCRIPTION:
COTTONWOOD CREEK SOUTH 50.0
END DESCRIPTION:
XS GIS Cut Line= 3
      2295025.01     13728425.01        2295675.       13728825.
        2296225.       13729325.
#Sta/Elev= 30
  4236.8  518.65  4314.3  513.25  4455.1  505.65  4565.2  497.38  4657.9  493.75
  4753.4  491.38  4830.6  492.63  4906.1  491.84  4941.3  488.44  4955.6  488.09
    4971   486.5  4978.2  486.86  4986.4  486.58    5000  484.44    5001  482.76
  5001.5  482.26  5026.8  482.76    5028  483.99  5042.2  486.05  5063.9  486.37
    5078  487.89  5159.6  487.35  5233.5  486.84    5347  491.12  5389.7  494.52
  5459.8  496.83  5608.5  506.91  5644.3  507.77  5739.7  513.11  5743.3  513.14
#Mann= 10 ,-1 , 0
  4236.8     .07       0  4314.3     .12       0  4657.9      .1       0
  4830.6     .12       0  4978.2     .07       0    5001     .05       0
  5026.8     .07       0  5159.6    .035       0  5389.7     .07       0
  5739.7     .12       0
Bank Sta=5001,5026.8
XS Rating Curve= 0 ,0
Exp/Cntr=0.3,0.1

Type RM Length L Ch R = 1 ,30300   ,596,596,596
BEGIN DESCRIPTION:
COTTONWOOD CREEK SOUTH 49.0
END DESCRIPTION:
XS GIS Cut Line= 3
      2294975.01     13728525.02        2295425.       13729275.
      2296224.95     13729374.99
#Sta/Elev= 30
  4125.1  516.79  4286.4   509.7  4393.3  503.76  4556.6  497.98  4599.3  494.74
  4678.8  487.14  4715.9  486.57  4906.4  487.96  4961.2  486.54  4986.1  484.45
  4996.8  481.62  4996.9   480.9  4997.4   480.4  5022.7   480.9    5030  484.92
  5042.6  484.81  5060.2  486.37  5084.6  485.85  5090.4  485.41  5110.6  486.42
  5150.9  485.68  5198.8  488.79  5203.8  490.14  5221.4  492.01  5440.6   498.9
  5574.2  504.08  5606.9  506.08    5699  508.53  5763.1  512.65  5805.9  513.47
#Mann= 7 ,-1 , 0
  4125.1     .12       0  4678.8      .1       0  4961.2     .07       0
  4996.9     .05       0  5022.7     .07       0  5084.6    .035       0
    5699     .12       0
Bank Sta=4996.9,5022.7
XS Rating Curve= 0 ,0
Exp/Cntr=0.3,0.1

Type RM Length L Ch R = 1 ,29704   ,532,532,532
BEGIN DESCRIPTION:
X18628
END DESCRIPTION:
XS GIS Cut Line= 4
      2294345.82     13730599.88      2295089.95     13729742.72
      2295824.66     13729526.08      2296501.41     13729516.68
#Sta/Elev= 30
  3701.7  503.36  3811.2     505  4200.5  493.99  4484.4  489.04  4519.6  490.63
  4591.3  485.29  4619.3  479.74  4654.4  479.75  4661.6  481.37  4668.7  485.97
  4675.3  486.22  4739.9  484.55  4871.6  487.42  4930.4  487.67  4967.2  482.77
    4971  477.81    4972  477.31    5010  477.81  5023.9  483.14  5040.2  485.36
  5137.1  486.76  5195.7  485.57  5376.2  493.92  5554.9  499.03  5633.1   504.4
  5903.2  509.69  6089.3  510.62  6187.8  512.42  6222.8  513.34  6279.6   514.6
#Mann= 11 ,-1 , 0
  3701.7     .05       0  4591.3     .07       0  4871.6     .12       0
  4930.4      .1       0    4971     .05       0    5010      .1       0
  5137.1    .035       0  5376.2     .07       0  6089.3     .12       0
  6187.8     .07       0  6222.8     .12       0
Bank Sta=4971,5010
XS Rating Curve= 0 ,0
Exp/Cntr=0.3,0.1

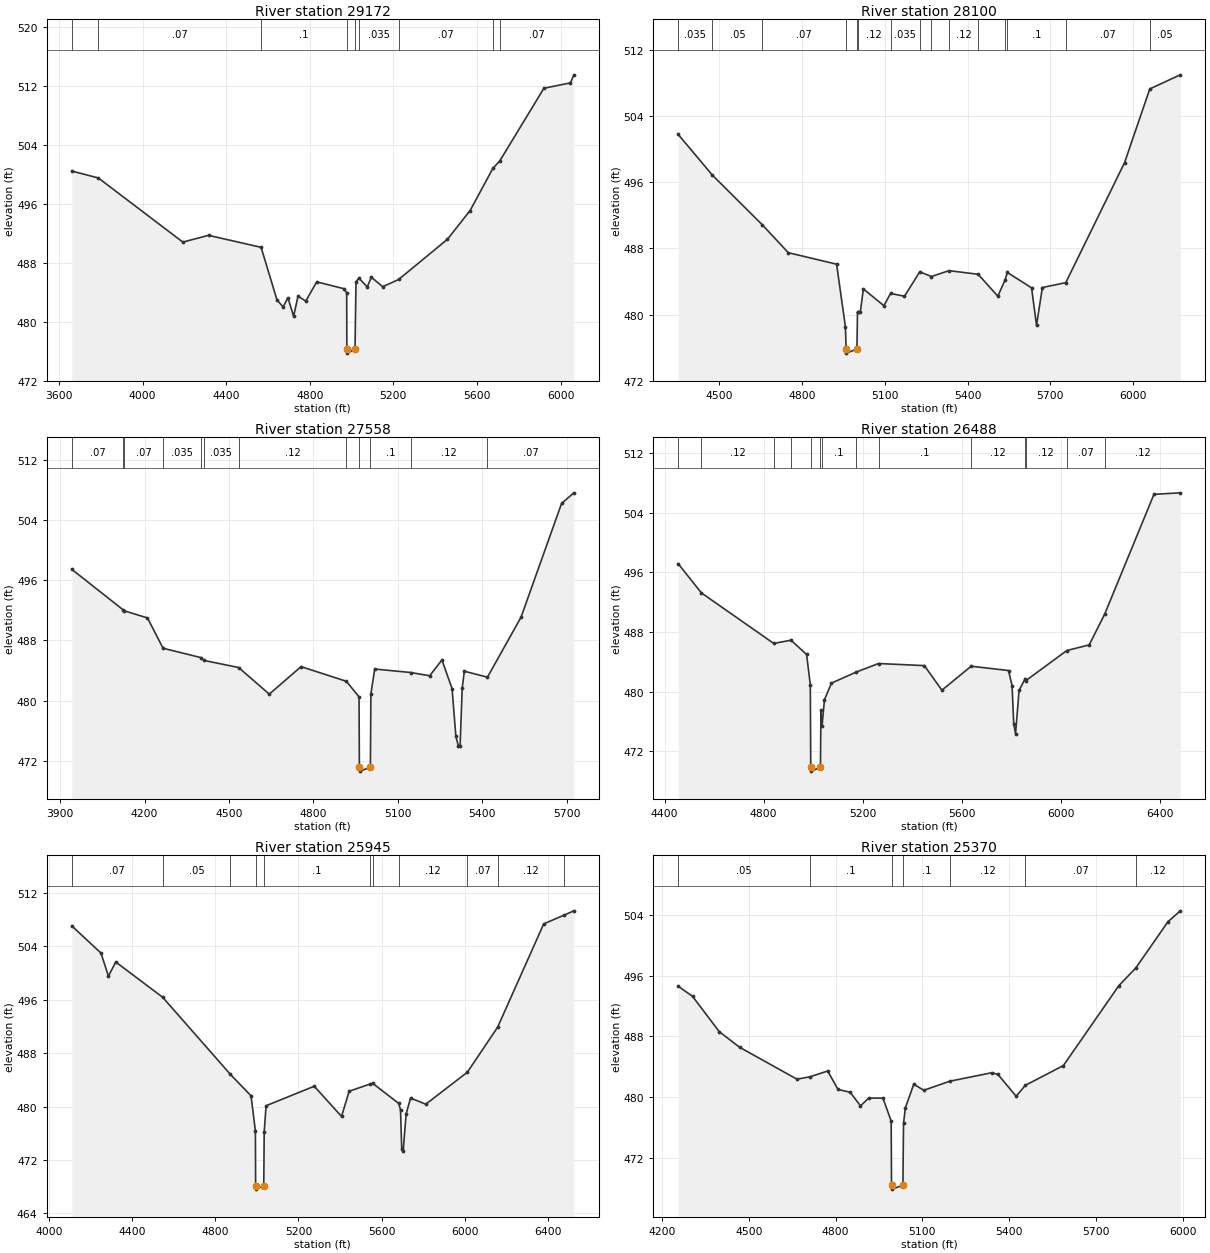
Type RM Length L Ch R = 1 ,29172   ,1072,1072,1072
BEGIN DESCRIPTION:
COTTONWOOD CREEK SOUTH 48.0
END DESCRIPTION:
XS GIS Cut Line= 3
      2294430.61     13730769.43        2295575.       13730075.
      2296568.75     13729695.64
#Sta/Elev= 30
  3661.3  500.46  3788.4  499.52  4192.8  490.82  4315.6  491.74  4567.2  490.11
  4643.2  482.98  4672.4  482.02  4695.5  483.28  4722.7  480.76    4744  483.49
  4780.9  482.82  4833.2  485.43  4964.8  484.49  4976.7  483.93  4977.5  476.26
  4978.5  475.76  5016.5  476.26  5021.3  485.44  5035.3  485.93  5075.1  484.74
  5094.5  486.06  5149.3  484.77  5225.3  485.75  5458.7   491.2  5567.2   495.1
  5676.6  500.84  5708.9  501.82  5920.4  511.69  6047.5  512.42  6063.6  513.51
#Mann= 9 ,-1 , 0
  3661.3     .05       0  3788.4     .07       0  4567.2      .1       0
  4977.5     .05       0  5016.5      .1       0  5035.3    .035       0
  5225.3     .07       0  5676.6     .12       0  5708.9     .07       0
Bank Sta=4977.5,5016.5
XS Rating Curve= 0 ,0
Exp/Cntr=0.3,0.1

Type RM Length L Ch R = 1 ,28100   ,542,542,542
BEGIN DESCRIPTION:
COTTONWOOD CREEK SOUTH 47.0
END DESCRIPTION:
XS GIS Cut Line= 3
      2294774.97     13731025.01        2295375.       13730775.
      2296474.99       13730375.
#Sta/Elev= 30
  4351.1  501.78  4475.3  496.85  4655.4  490.88  4750.3  487.49  4925.3   486.1
  4957.3  478.53  4959.9  475.85  4960.9  475.35    4999  475.85  5001.1  480.31
  5002.8   480.3  5011.1  480.27  5022.4  483.11  5096.9  481.08  5120.9  482.57
  5171.4  482.22  5226.8  485.18  5269.2  484.61  5332.7  485.32  5438.6  484.88
  5509.9  482.23  5535.7  484.15  5544.5   485.1  5632.3  483.24  5650.2  478.72
  5671.5  483.28  5756.3  483.87  5969.4  498.37    6061  507.29  6171.6  508.99
#Mann= 15 ,-1 , 0
  4351.1    .035       0  4475.3     .05       0  4655.4     .07       0
  4959.9     .05       0    4999     .07       0  5002.8     .12       0
  5120.9    .035       0  5226.8      .1       0  5269.2    .035       0
  5332.7     .12       0  5438.6      .1       0  5535.7     .07       0
  5544.5      .1       0  5756.3     .07       0    6061     .05       0
Bank Sta=4959.9,4999
XS Rating Curve= 0 ,0
Exp/Cntr=0.3,0.1

Type RM Length L Ch R = 1 ,27558   ,1070,1070,1070
BEGIN DESCRIPTION:
COTTONWOOD CREEK SOUTH 46.0
END DESCRIPTION:
XS GIS Cut Line= 3
      2295024.98     13731675.02        2295825.       13730975.
      2296425.04     13730574.97
#Sta/Elev= 30
  3941.3  497.45  4124.4  492.05    4128  491.94  4210.4  490.99  4265.8  486.97
  4400.1  485.73  4411.7  485.35  4534.4  484.41  4643.2  480.88  4756.1  484.53
  4917.4  482.58  4962.1  480.51  4963.4  471.16  4964.4  470.66  5002.5  471.16
  5004.3  480.92  5017.9  484.21  5145.8  483.75  5213.2  483.32  5256.7  485.41
  5292.8  481.61  5306.3  475.28  5315.3  473.97  5321.3  474.04  5328.8  481.72
  5336.4  483.92  5418.5  483.13  5537.7  491.08  5681.9  506.19  5725.5   507.6
#Mann= 12 ,-1 , 0
  3941.3     .07       0  4124.4     .05       0    4128     .07       0
  4265.8    .035       0  4400.1     .12       0  4411.7    .035       0
  4534.4     .12       0  4917.4      .1       0  4963.4     .05       0
  5002.5      .1       0  5145.8     .12       0  5418.5     .07       0
Bank Sta=4963.4,5002.5
XS Rating Curve= 0 ,0
Exp/Cntr=0.3,0.1

Type RM Length L Ch R = 1 ,26488   ,543,543,543
BEGIN DESCRIPTION:
COTTONWOOD CREEK SOUTH 45.0
END DESCRIPTION:
XS GIS Cut Line= 3
      2295175.03     13732074.98        2295625.       13731775.
        2296725.       13730775.
#Sta/Elev= 30
  4455.4  497.16  4548.6  493.26  4841.2  486.47  4910.7  486.91  4973.7  484.99
  4988.7  480.94  4990.5  469.85  4991.5  469.35  5029.6  469.85  5031.7   477.5
  5036.1  475.43  5045.9  478.93  5074.2  481.15  5172.8  482.62  5264.3  483.78
  5449.3   483.5  5520.2   480.2  5638.2  483.42  5789.2  482.84  5803.4  480.82
  5810.1  475.72  5817.5  474.36  5831.7  480.18  5856.5  481.75  5859.2  481.49
  6024.5  485.52  6114.9  486.28    6177  490.37  6376.4  506.47  6482.8  506.67
#Mann= 14 ,-1 , 0
  4455.4    .035       0  4548.6     .12       0  4841.2     .07       0
  4910.7     .12       0  4990.5     .05       0  5029.6     .12       0
  5036.1      .1       0  5172.8     .12       0  5264.3      .1       0
  5638.2     .12       0  5856.5     .07       0  5859.2     .12       0
  6024.5     .07       0    6177     .12       0
Bank Sta=4990.5,5029.6
XS Rating Curve= 0 ,0
Exp/Cntr=0.3,0.1

Type RM Length L Ch R = 1 ,25945   ,575,575,575
BEGIN DESCRIPTION:
COTTONWOOD CREEK SOUTH 44.0
END DESCRIPTION:
XS GIS Cut Line= 3
      2295363.12     13732672.14        2296025.       13732075.
      2296825.02     13730774.97
#Sta/Elev= 30
  4108.2  507.08  4248.9     503  4284.8  499.55  4319.9  501.67  4545.8  496.39
  4872.6  484.82  4971.6  481.62  4992.5  476.36  4993.6  468.15  4994.6  467.65
  5032.8  468.15  5034.9  476.22    5044  480.14  5275.9  483.06  5407.3  478.54
    5444  482.31  5546.8  483.41  5558.5  483.47  5682.6  480.49  5691.3  479.54
  5697.2  473.72  5704.1  473.36  5718.5  478.92  5739.7  481.29  5813.1  480.37
  6013.7  485.17  6159.1  491.91  6381.1  507.38  6477.4  508.66  6526.1  509.33
#Mann= 11 ,-1 , 0
  4108.2     .07       0  4545.8     .05       0  4872.6      .1       0
  4993.6     .05       0  5032.8      .1       0  5546.8     .12       0
  5558.5      .1       0  5682.6     .12       0  6013.7     .07       0
  6159.1     .12       0  6477.4     .07       0
Bank Sta=4993.6,5032.8
XS Rating Curve= 0 ,0
Exp/Cntr=0.3,0.1

Type RM Length L Ch R = 1 ,25370   ,542,542,542
BEGIN DESCRIPTION:
COTTONWOOD CREEK SOUTH 43.0
END DESCRIPTION:
XS GIS Cut Line= 3
      2295974.99     13732525.01        2296475.       13731975.
      2297125.01     13731224.99
#Sta/Elev= 30
  4256.1  494.59  4305.8  493.25  4397.7  488.61  4468.6  486.54  4666.6  482.34
  4712.1  482.66  4772.7  483.42  4808.5  480.99  4850.8  480.61  4886.2  478.82
  4914.6  479.85  4963.9  479.85  4992.3  476.81  4993.5  468.35  4994.5  467.85
  5032.8  468.35    5035  476.56  5041.7  478.59  5070.2  481.67  5105.3  480.88
  5194.5  482.07  5339.9  483.19  5360.8  482.99  5424.4  480.09  5456.1  481.53
  5587.8  484.14  5779.6  494.68    5838     497  5949.6  503.11  5991.9  504.53
#Mann= 7 ,-1 , 0
  4256.1     .05       0  4712.1      .1       0  4993.5     .05       0
  5032.8      .1       0  5194.5     .12       0  5456.1     .07       0
    5838     .12       0
Bank Sta=4993.5,5032.8
XS Rating Curve= 0 ,0
Exp/Cntr=0.3,0.1