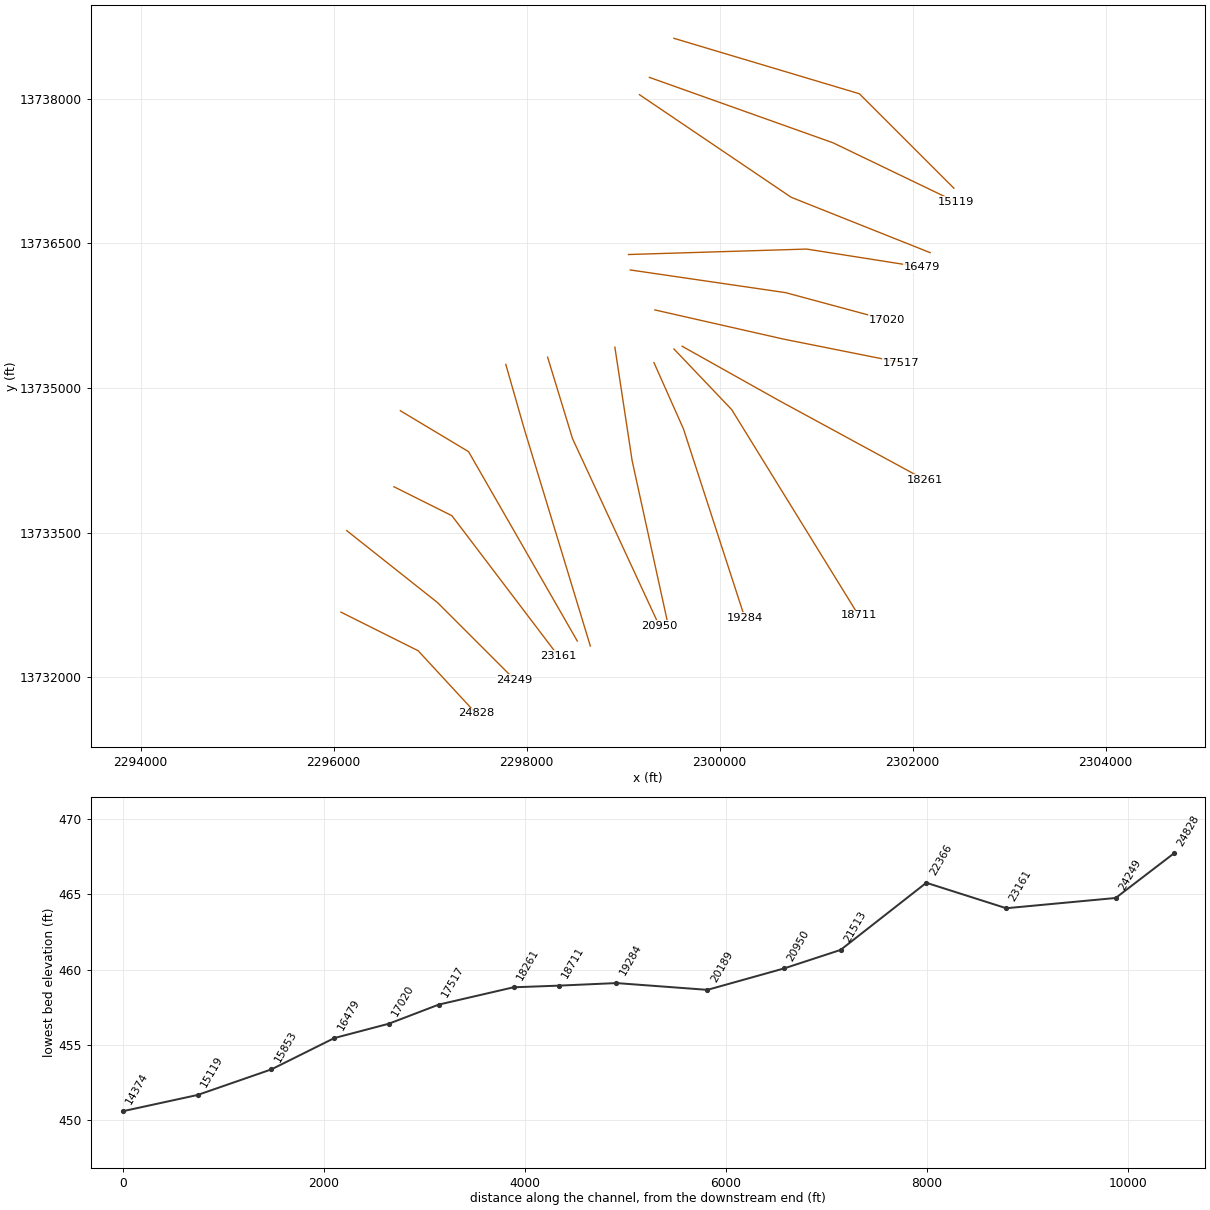
HEC-RAS study COTTONWOOD CREEK SOUTH.prj: COTTONWOOD CREEK SOUTH Base Level Engineering

--- COTTONWOOD CREEK SOUTH.g01 (geometry) --- (continued)

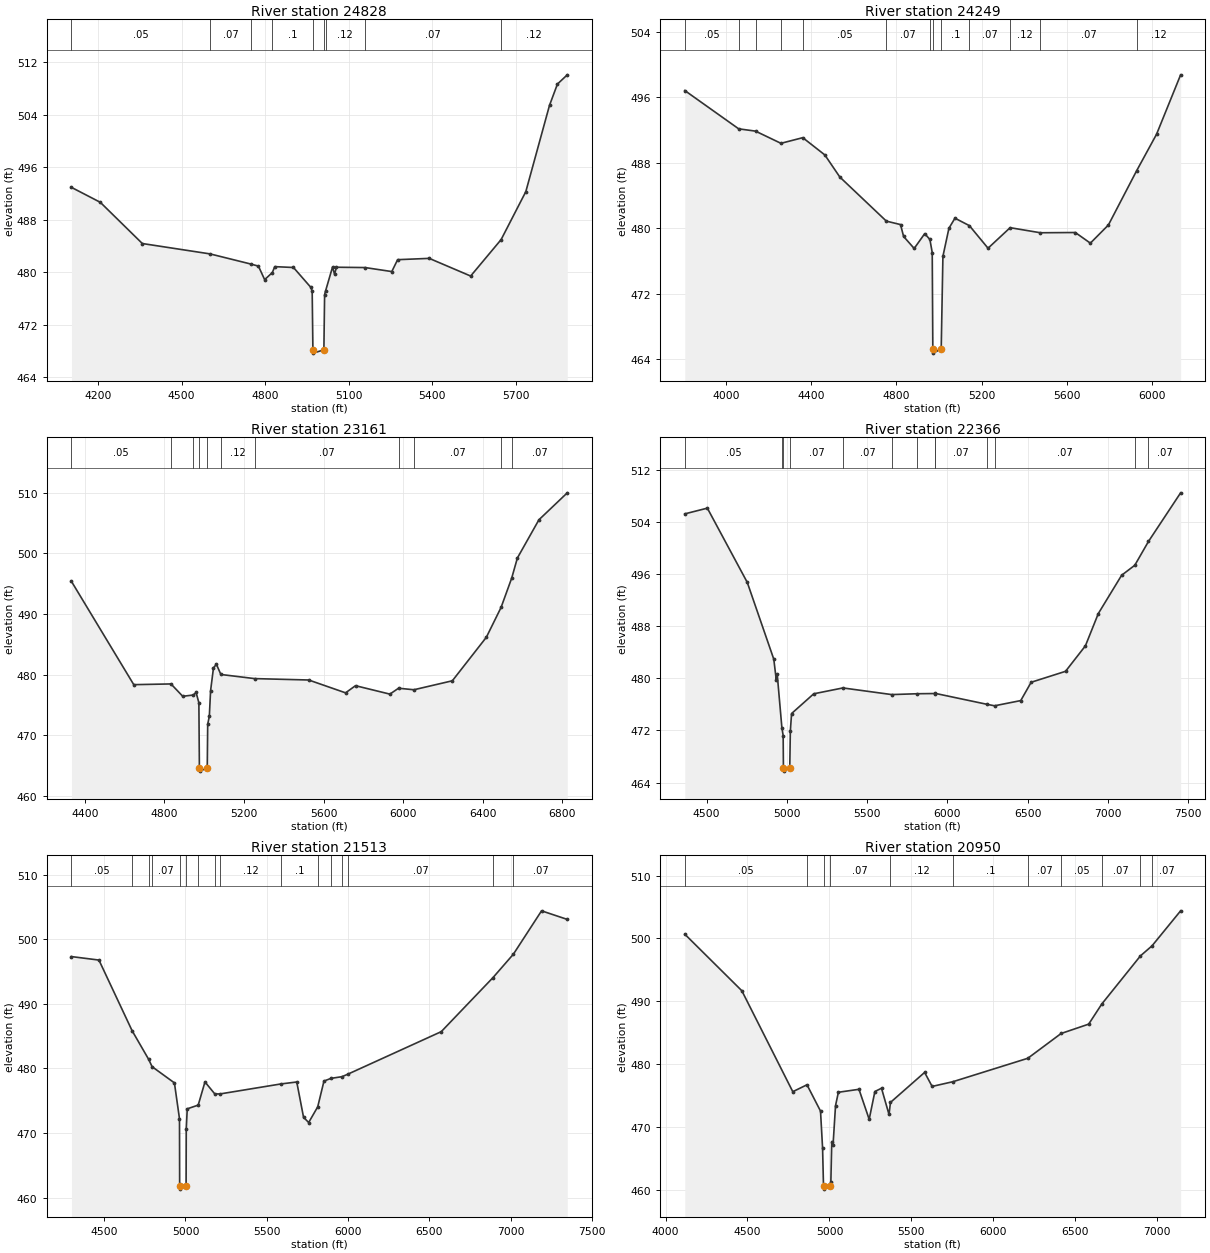
Type RM Length L Ch R = 1 ,24828   ,579,579,579
BEGIN DESCRIPTION:
COTTONWOOD CREEK SOUTH 42.0
END DESCRIPTION:
XS GIS Cut Line= 3
      2296075.01     13732674.99        2296875.       13732275.
        2297475.       13731625.
#Sta/Elev= 30
  4105.1  492.95  4208.5  490.68  4359.4   484.4  4602.4  482.82  4748.3  481.28
  4775.9  480.96  4798.3   478.9  4825.8  479.98  4834.6  480.88  4901.7  480.75
  4963.2  477.76  4968.8  477.18  4971.4  468.21  4972.4  467.71  5010.8  468.21
  5013.4  476.62  5016.9  477.19  5041.8  480.82  5049.1  479.73  5055.9  480.79
  5158.8  480.74  5254.4  480.13  5275.4  481.94  5388.8  482.14  5537.4  479.45
  5646.7     485  5735.3   492.3  5820.3  505.44  5848.7  508.68  5884.1  510.09
#Mann= 9 ,-1 , 0
  4105.1     .05       0  4602.4     .07       0  4748.3     .12       0
  4825.8      .1       0  4971.4     .05       0  5010.8      .1       0
  5016.9     .12       0  5158.8     .07       0  5646.7     .12       0
Bank Sta=4971.4,5010.8
XS Rating Curve= 0 ,0
Exp/Cntr=0.3,0.1

Type RM Length L Ch R = 1 ,24249   ,1088,1088,1088
BEGIN DESCRIPTION:
COTTONWOOD CREEK SOUTH 41.0
END DESCRIPTION:
XS GIS Cut Line= 3
      2296135.52     13733519.89        2297075.       13732775.
      2297874.99     13731975.01
#Sta/Elev= 30
  3805.2  496.84  4058.5  492.16  4137.5  491.88  4257.1  490.39  4359.7  491.08
  4463.4  488.97  4533.8  486.27  4752.6  480.88  4819.1  480.46  4833.5  479.01
  4883.2  477.54  4932.8  479.35  4957.1  478.64  4968.1  477.04  4970.9  465.25
  4971.9  464.75  5010.3  465.25  5018.3  476.58  5046.6  480.01  5074.9  481.24
  5142.7  480.33  5230.4  477.57  5334.2  480.08  5476.4  479.46  5640.5  479.49
  5711.3  478.19  5796.1  480.41  5928.8  487.04  6022.4   491.5  6135.5  498.76
#Mann= 13 ,-1 , 0
  3805.2     .05       0  4058.5     .07       0  4137.5     .05       0
  4257.1     .07       0  4359.7     .05       0  4752.6     .07       0
  4957.1      .1       0  4970.9     .05       0  5010.3      .1       0
  5142.7     .07       0  5334.2     .12       0  5476.4     .07       0
  5928.8     .12       0
Bank Sta=4970.9,5010.3
XS Rating Curve= 0 ,0
Exp/Cntr=0.3,0.1

Type RM Length L Ch R = 1 ,23161   ,795,795,795
BEGIN DESCRIPTION:
COTTONWOOD CREEK SOUTH 40.0
END DESCRIPTION:
XS GIS Cut Line= 3
      2296625.02     13733974.99        2297225.       13733675.
      2298324.98     13732225.02
#Sta/Elev= 30
  4333.4  495.38  4646.4  478.34  4833.3  478.46  4892.4  476.42  4945.1  476.63
  4959.5  477.05  4973.5  475.35  4976.1  464.57  4977.1  464.07  5015.6  464.57
  5017.8  471.82    5026   473.1  5032.3  477.34  5046.8   481.1  5061.4  481.71
    5084  480.02  5253.5  479.34  5525.2  479.11  5710.4  476.99  5760.3  478.17
  5932.9  476.78  5976.6  477.75  6053.8   477.5  6246.8  478.98  6417.6  486.16
  6491.5  491.08    6545  495.93  6573.6  499.25  6681.7  505.55  6824.2     510
#Mann= 11 ,-1 , 0
  4333.4     .05       0  4833.3     .07       0  4945.1     .12       0
  4976.1     .05       0  5015.6     .12       0    5084     .12       0
  5253.5     .07       0  5976.6    .035       0  6053.8     .07       0
  6491.5     .12       0    6545     .07       0
Bank Sta=4976.1,5015.6
XS Rating Curve= 0 ,0
Exp/Cntr=0.3,0.1

Type RM Length L Ch R = 1 ,22366   ,853,853,853
BEGIN DESCRIPTION:
COTTONWOOD CREEK SOUTH 39.0
END DESCRIPTION:
XS GIS Cut Line= 3
      2296691.24     13734763.26       2297397.7     13734339.39
      2298524.98     13732375.03
#Sta/Elev= 30
  4364.4  505.25  4504.9  506.13  4753.6  494.73  4918.8  482.94  4934.4  479.73
  4940.2  480.61  4969.1  472.45  4977.2  471.22  4978.8  466.26  4979.8  465.76
  5018.3  466.26  5021.9  471.92  5029.6   474.6  5167.6  477.63  5349.4  478.53
  5653.5  477.51  5813.7  477.64  5921.8  477.67  5925.3  477.69    6248  476.01
  6294.2  475.79  6457.2  476.59    6522   479.4  6736.2  481.08  6859.9  484.99
  6940.4  489.95  7085.7  495.83  7167.6  497.36  7252.9  501.02  7453.1  508.48
#Mann= 13 ,-1 , 0
  4364.4     .05       0  4969.1     .07       0  4978.8     .05       0
  5018.3     .07       0  5349.4     .07       0  5653.5     .12       0
  5813.7     .07       0  5921.8     .12       0  5925.3     .07       0
    6248     .12       0  6294.2     .07       0  7167.6     .12       0
  7252.9     .07       0
Bank Sta=4978.8,5018.3
XS Rating Curve= 0 ,0
Exp/Cntr=0.3,0.1

Type RM Length L Ch R = 1 ,21513   ,563,563,563
BEGIN DESCRIPTION:
COTTONWOOD CREEK SOUTH 38.0
END DESCRIPTION:
XS GIS Cut Line= 3
      2297783.88     13735243.69        2297975.       13734575.
      2298659.89     13732323.64
#Sta/Elev= 30
  4298.9  497.33  4467.9  496.79  4671.7  485.85  4773.3  481.42  4794.8  480.27
    4932  477.76  4963.2   472.2  4964.2   461.8  4965.2   461.3  5003.8   461.8
  5004.8   470.6  5010.8  473.74  5078.3  474.32  5119.8  477.91  5180.3  476.05
  5212.8  476.05  5587.5   477.6  5684.2   477.9    5726  472.43  5757.4  471.62
  5813.1  474.05  5851.5  478.04  5894.2  478.46  5962.1  478.72  5997.4   479.1
  6572.7   485.7    6891  494.08  7016.1   497.7  7189.4  504.42  7347.6  503.09
#Mann= 16 ,-1 , 0
  4298.9     .05       0  4671.7     .07       0  4773.3     .05       0
  4794.8     .07       0  4964.2     .05       0  5003.8     .07       0
  5078.3     .12       0  5180.3     .07       0  5212.8     .12       0
  5587.5      .1       0  5813.1     .12       0  5894.2      .1       0
  5962.1     .12       0  5997.4     .07       0    6891     .12       0
  7016.1     .07       0
Bank Sta=4964.2,5003.8
XS Rating Curve= 0 ,0
Exp/Cntr=0.3,0.1

Type RM Length L Ch R = 1 ,20950   ,761,761,761
BEGIN DESCRIPTION:
COTTONWOOD CREEK SOUTH 37.0
END DESCRIPTION:
XS GIS Cut Line= 3
      2298217.18     13735319.04        2298475.       13734475.
      2299375.77     13732530.87
#Sta/Elev= 30
  4117.5  500.68  4465.5  491.67  4776.4  475.59    4863  476.69  4945.6   472.5
  4958.2  466.59  4963.8  460.57  4964.8  460.07  5003.4  460.57  5008.7  461.23
  5014.2  467.64  5022.1  467.13  5037.2  473.38  5054.6   475.5  5180.2  475.97
  5242.5  471.19  5277.3  475.62  5317.7  476.14  5363.5  471.96  5372.3  473.88
  5580.7  478.66  5626.6  476.43  5753.3  477.18  6210.2  480.91  6413.5  484.86
  6581.7  486.35  6661.8  489.56  6897.8  497.23  6968.1  498.82  7142.7   504.4
#Mann= 11 ,-1 , 0
  4117.5     .05       0    4863     .07       0  4963.8     .05       0
  5003.4     .07       0  5372.3     .12       0  5753.3      .1       0
  6210.2     .07       0  6413.5     .05       0  6661.8     .07       0
  6897.8     .12       0  6968.1     .07       0
Bank Sta=4963.8,5003.4
XS Rating Curve= 0 ,0
Exp/Cntr=0.3,0.1

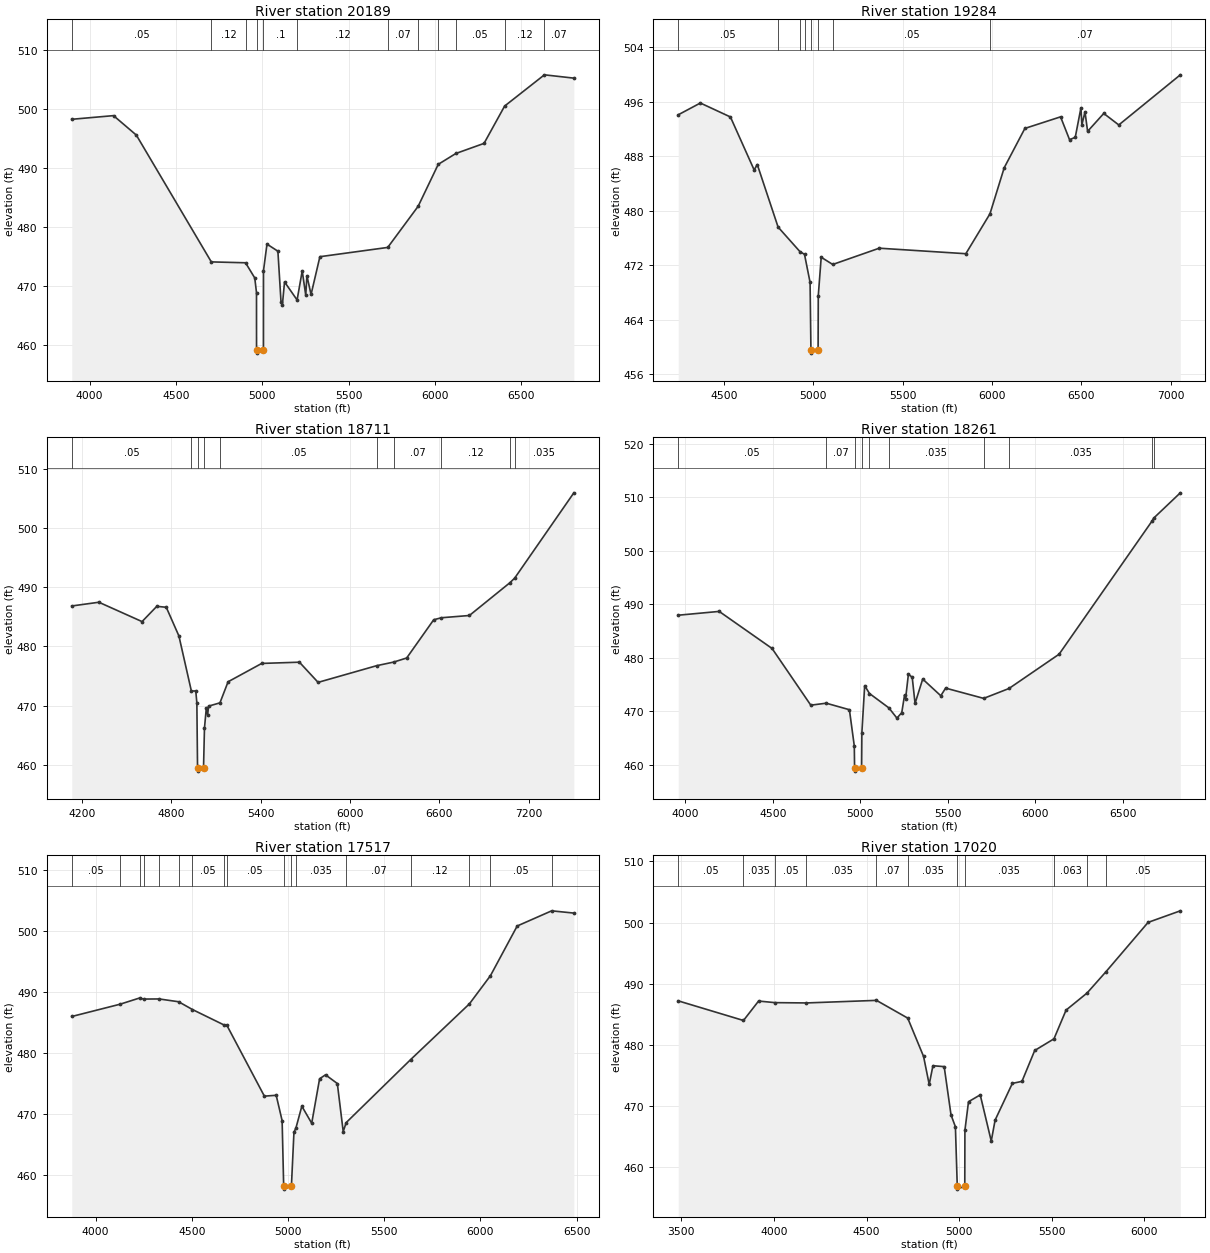
Type RM Length L Ch R = 1 ,20189   ,905,905,905
BEGIN DESCRIPTION:
COTTONWOOD CREEK SOUTH 36.0
END DESCRIPTION:
XS GIS Cut Line= 3
      2298914.23     13735422.57      2299093.19     13734245.19
      2299460.54     13732568.57
#Sta/Elev= 30
    3897  498.25  4138.7  498.87    4271  495.57    4705   474.1  4903.3  473.95
  4956.6  471.38  4966.7  468.88  4966.9  459.15  4967.9  458.65    5007  459.15
  5007.2  472.62  5027.4  477.11  5090.6  475.91  5108.6  467.35  5116.7  466.87
  5129.1  470.71  5201.8  467.65  5231.4  472.57  5251.9  468.46  5258.5  471.76
  5282.6  468.58  5333.8  474.98  5726.6  476.55  5902.8  483.52  6019.1  490.62
  6121.1  492.46  6284.3  494.17  6403.5  500.49  6633.8  505.78  6804.3  505.22
#Mann= 12 ,-1 , 0
    3897     .05       0    4705     .12       0  4903.3      .1       0
  4966.9     .05       0    5007      .1       0  5201.8     .12       0
  5726.6     .07       0  5902.8     .05       0  6019.1     .07       0
  6121.1     .05       0  6403.5     .12       0  6633.8     .07       0
Bank Sta=4966.9,5007
XS Rating Curve= 0 ,0
Exp/Cntr=0.3,0.1

Type RM Length L Ch R = 1 ,19284   ,573,573,573
BEGIN DESCRIPTION:
COTTONWOOD CREEK SOUTH 34.0
END DESCRIPTION:
XS GIS Cut Line= 3
      2299319.27     13735262.45        2299625.       13734575.
       2300260.6     13732617.47
#Sta/Elev= 30
  4243.4   494.1  4367.3  495.83  4535.6  493.78  4668.2  486.01    4686  486.79
  4802.4  477.61  4924.3  474.02  4950.2  473.61  4981.4  469.49  4986.2   459.6
  4987.2   459.1  5026.3   459.6  5027.3  467.52  5043.7  473.18  5108.3  472.12
  5368.6  474.51  5853.3   473.7  5988.4  479.56  6068.2  486.33  6183.8   492.1
  6383.6   493.8  6433.8  490.45  6465.8  490.79  6497.7  495.13    6503  492.63
  6520.3  494.53    6535  491.67  6625.4   494.3  6709.5  492.61  7053.9  499.97
#Mann= 8 ,-1 , 0
  4243.4     .05       0  4802.4     .07       0  4924.3     .12       0
  4950.2     .07       0  4986.2     .05       0  5026.3     .07       0
  5108.3     .05       0  5988.4     .07       0
Bank Sta=4986.2,5026.3
XS Rating Curve= 0 ,0
Exp/Cntr=0.3,0.1

Type RM Length L Ch R = 1 ,18711   ,450,450,450
BEGIN DESCRIPTION:
COTTONWOOD CREEK SOUTH 33.0
END DESCRIPTION:
XS GIS Cut Line= 3
      2299526.46      13735403.8        2300125.       13734775.
      2301438.64     13732643.86
#Sta/Elev= 30
    4132  486.84    4314  487.47    4604   484.2    4703  486.78  4766.6  486.62
  4851.5  481.77  4935.1  472.47  4964.7  472.48    4972  470.46  4976.6  459.43
  4977.6  458.93  5016.7  459.43  5023.2  466.22  5035.4  469.55  5044.5  468.44
  5050.4  469.91  5127.1  470.47  5181.7  474.03  5407.6  477.13  5660.7  477.34
  5786.2  473.93  6179.7  476.75    6294  477.36  6381.1  478.05  6562.5  484.51
  6614.1  484.85  6802.2  485.23  7073.3  490.75  7106.1  491.54  7503.6  505.96
#Mann= 10 ,-1 , 0
    4132     .05       0  4935.1     .07       0  4976.6     .05       0
  5016.7     .07       0  5127.1     .05       0  6179.7    .035       0
    6294     .07       0  6614.1     .12       0  7073.3     .07       0
  7106.1    .035       0
Bank Sta=4976.6,5016.7
XS Rating Curve= 0 ,0
Exp/Cntr=0.3,0.1

Type RM Length L Ch R = 1 ,18261   ,744,744,744
BEGIN DESCRIPTION:
X18627
END DESCRIPTION:
XS GIS Cut Line= 3
      2299611.23     13735432.05      2300619.13     13734866.87
       2302126.2      13734047.4
#Sta/Elev= 30
  3958.5  487.97  4192.7  488.68  4495.1  481.75  4716.5  471.15  4804.8  471.52
  4937.3   470.3  4965.3  463.52  4966.9  459.32  4967.9  458.82  5007.1  459.32
  5008.6  466.02  5024.6   474.8  5052.1  473.33  5162.8  470.65  5209.1  468.73
  5236.7  469.76  5252.8  473.07  5258.5  472.36  5274.7  476.95  5296.5  476.35
  5312.7  471.47  5356.4  476.03  5459.9  472.91  5487.5  474.34  5705.2  472.42
  5849.9  474.27  6136.4  480.68  6668.2  505.59  6676.9  506.11  6829.5  510.85
#Mann= 10 ,-1 , 0
  3958.5     .05       0  4804.8     .07       0  4966.9     .05       0
  5007.1     .07       0  5052.1     .05       0  5162.8    .035       0
  5705.2    .063       0  5849.9    .035       0  6668.2     .05       0
  6676.9     .07       0
Bank Sta=4966.9,5007.1
XS Rating Curve= 0 ,0
Exp/Cntr=0.3,0.1

Type RM Length L Ch R = 1 ,17517   ,497,497,497
BEGIN DESCRIPTION:
X18626
END DESCRIPTION:
XS GIS Cut Line= 3
      2299328.65     13735808.82      2300656.81     13735507.39
      2301880.64     13735262.63
#Sta/Elev= 30
  3875.9     486  4126.4  488.01    4228  489.03  4249.4  488.86  4329.7  488.88
  4431.3  488.42  4503.4  487.14  4664.7  484.65  4681.7  484.58  4877.1  472.93
  4938.6  473.07  4969.4  468.91  4977.5  458.17  4978.5  457.67  5017.7  458.17
  5030.9  466.99  5041.5  467.74  5071.9  471.28  5123.2  468.48  5164.2  475.78
    5195  476.43  5256.4     475    5287  467.12  5302.5  468.59  5637.9  478.94
  5942.9  488.07  6052.4   492.7  6191.4  500.85  6370.6  503.34  6485.9  502.97
#Mann= 17 ,-1 , 0
  3875.9     .05       0  4126.4    .035       0    4228     .05       0
  4249.4    .035       0  4329.7     .05       0  4431.3     .07       0
  4503.4     .05       0  4664.7     .07       0  4681.7     .05       0
  4977.5     .05       0  5017.7     .05       0  5041.5    .035       0
  5302.5     .07       0  5637.9     .12       0  5942.9     .07       0
  6052.4     .05       0  6370.6    .035       0
Bank Sta=4977.5,5017.7
XS Rating Curve= 0 ,0
Exp/Cntr=0.3,0.1

Type RM Length L Ch R = 1 ,17020   ,541,541,541
BEGIN DESCRIPTION:
X18625
END DESCRIPTION:
XS GIS Cut Line= 3
      2299074.34     13736223.27      2300685.07     13735987.78
      2301730.31     13735705.28
#Sta/Elev= 30
  3483.4   487.2  3835.6  483.99  3917.2  487.17  4005.7  486.91  4175.3  486.86
  4553.7  487.28  4722.3  484.38    4808   478.1  4838.3  473.53  4858.5  476.59
  4919.2  476.44  4956.1  468.54  4979.8   466.6  4989.8   456.9  4990.8   456.4
  5030.4   456.9  5031.1  466.02  5050.5   470.7  5113.8  471.82  5173.3  464.26
  5194.1  467.69  5287.3   473.7  5339.1  474.03  5407.9  479.08  5511.9  480.99
  5577.3  485.69  5690.5  488.48  5793.3  491.99  6020.1  500.04    6194  501.93
#Mann= 11 ,-1 , 0
  3483.4     .05       0  3835.6    .035       0  4005.7     .05       0
  4175.3    .035       0  4553.7     .07       0  4722.3    .035       0
  4989.8     .05       0  5030.4    .035       0  5511.9    .063       0
  5690.5     .07       0  5793.3     .05       0
Bank Sta=4989.8,5030.4
XS Rating Curve= 0 ,0
Exp/Cntr=0.3,0.1

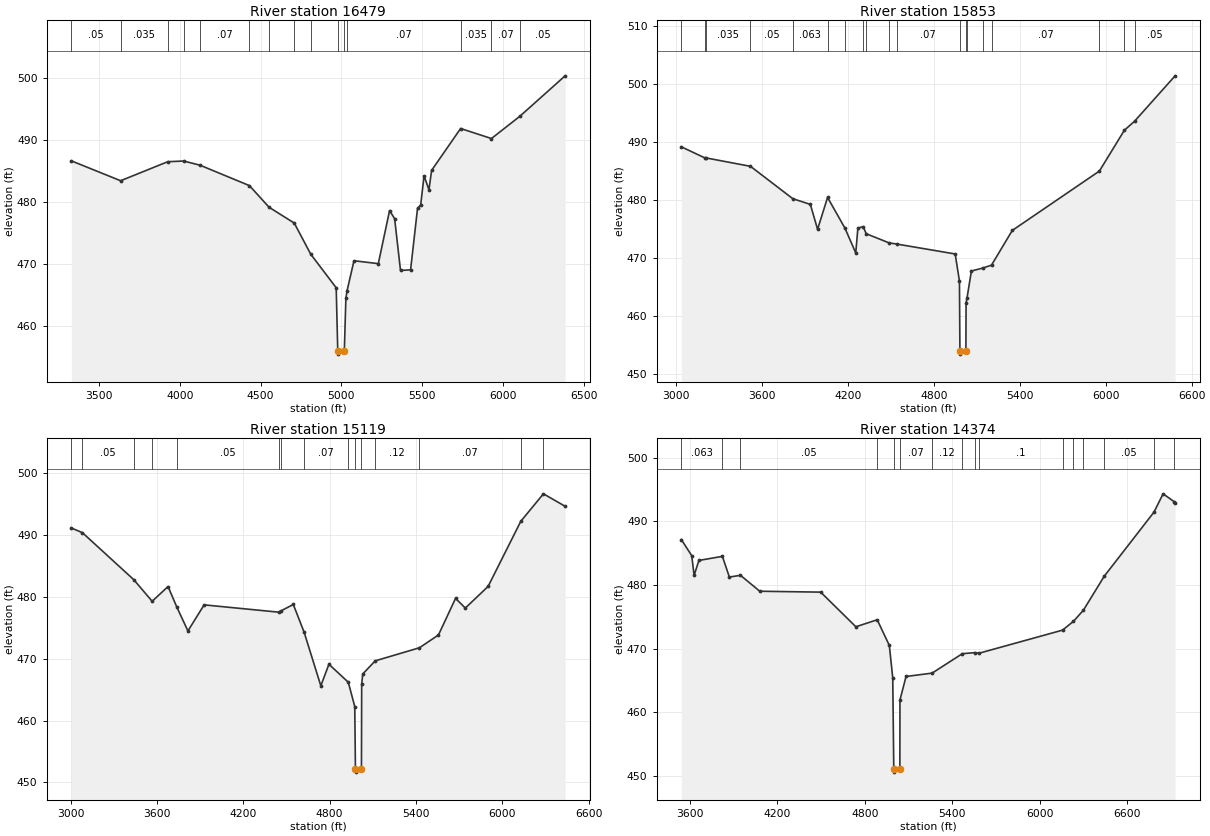
Type RM Length L Ch R = 1 ,16479   ,626,626,626
BEGIN DESCRIPTION:
X18624
END DESCRIPTION:
XS GIS Cut Line= 3
      2299055.46     13736383.39      2300901.71     13736439.91
      2302097.95     13736251.53
#Sta/Elev= 30
  3327.6  486.64  3632.6  483.43  3924.7   486.5  4023.1  486.61  4125.4  485.93
  4430.7  482.64  4552.2  479.15  4708.2   476.6  4810.4  471.57  4967.9  466.16
  4977.6  455.95  4978.6  455.45  5018.2  455.95  5027.9  464.45  5035.3  465.68
    5078  470.52  5228.7  470.05  5298.6  478.62  5329.9   477.3  5366.2  468.95
  5428.7  469.05  5471.6  478.97  5491.2  479.53  5512.1  484.22  5542.5  481.97
  5558.8   485.1  5738.5  491.86  5929.4  490.24  6105.8  493.84  6385.7  500.36
#Mann= 15 ,-1 , 0
  3327.6     .05       0  3632.6    .035       0  3924.7     .07       0
  4023.1    .035       0  4125.4     .07       0  4430.7    .035       0
  4552.2    .094       0  4708.2    .035       0  4810.4      .1       0
  4977.6     .05       0  5018.2      .1       0  5035.3     .07       0
  5738.5    .035       0  5929.4     .07       0  6105.8     .05       0
Bank Sta=4977.6,5018.2
XS Rating Curve= 0 ,0
Exp/Cntr=0.3,0.1

Type RM Length L Ch R = 1 ,15853   ,734,734,734
BEGIN DESCRIPTION:
X18623
END DESCRIPTION:
XS GIS Cut Line= 3
      2299168.58     13738041.19      2300741.58     13736976.82
       2302181.4     13736402.77
#Sta/Elev= 30
  3035.1   489.2  3199.7  487.28  3209.9  487.27  3518.2  485.83    3814  480.23
  3936.3  479.25  3986.8  474.94  4056.6  480.45  4177.9  475.15  4253.5  470.86
  4268.4  475.15  4305.2  475.41  4326.5  474.18    4486   472.6    4539   472.4
  4948.1  470.68  4977.8  466.01  4981.2  453.87  4982.2  453.37  5022.9  453.87
  5024.2  462.25  5030.7  463.05  5061.3  467.73  5142.4  468.26  5201.8  468.75
  5347.1  474.75  5955.6  485.01  6130.2  492.07  6201.5  493.63  6484.4  501.47
#Mann= 19 ,-1 , 0
  3035.1    .035       0  3199.7     .05       0  3209.9    .035       0
  3518.2     .05       0    3814    .063       0  4056.6    .035       0
  4177.9     .07       0  4305.2    .035       0  4326.5     .07       0
    4486     .05       0    4539     .07       0  4981.2     .05       0
  5022.9     .07       0  5030.7     .07       0  5142.4     .12       0
  5201.8     .07       0  5955.6    .035       0  6130.2     .07       0
  6201.5     .05       0
Bank Sta=4981.2,5022.9
XS Rating Curve= 0 ,0
Exp/Cntr=0.3,0.1

Type RM Length L Ch R = 1 ,15119   ,745,745,745
BEGIN DESCRIPTION:
X18622
END DESCRIPTION:
XS GIS Cut Line= 3
      2299272.13     13738220.19      2301174.87     13737541.98
      2302446.19     13736929.87
#Sta/Elev= 30
    3005  491.09  3081.7  490.34  3438.6  482.75  3566.5  479.26  3676.9  481.64
  3738.1  478.31    3815  474.47  3927.6  478.68  4445.4   477.5    4463  477.73
  4547.4  478.74  4622.9  474.23  4738.5  465.61  4794.8  469.09  4929.3  466.19
  4974.3  462.26    4979  452.17    4980  451.67  5020.8  452.17  5022.4  465.89
  5030.1  467.53  5116.6  469.64  5423.7  471.75    5556  473.82  5674.7  479.73
  5742.6  478.16  5900.9  481.66  6128.2  492.18  6285.3  496.61    6436   494.6
#Mann= 15 ,-1 , 0
    3005    .035       0  3081.7     .05       0  3438.6    .063       0
  3566.5    .094       0  3738.1     .05       0  4445.4     .07       0
    4463     .05       0  4622.9     .07       0  4929.3      .1       0
    4979     .05       0  5020.8      .1       0  5116.6     .12       0
  5423.7     .07       0  6128.2    .035       0  6285.3     .05       0
Bank Sta=4979,5020.8
XS Rating Curve= 0 ,0
Exp/Cntr=0.3,0.1

Type RM Length L Ch R = 1 ,14374   ,880,880,880
BEGIN DESCRIPTION:
X18621
END DESCRIPTION:
XS GIS Cut Line= 3
      2299526.52      13738625.2      2301448.04     13738050.63
      2302427.67     13737070.99
#Sta/Elev= 30
  3540.2  487.12  3611.7  484.58  3627.8  481.49  3660.9  483.84  3822.2  484.48
    3870  481.23  3946.4   481.5    4079     479  4497.2  478.86  4738.9  473.42
  4885.3  474.52  4968.6  470.49  4992.1  465.38  4999.1  451.09  5000.1  450.59
  5040.9  451.09  5041.6  461.93  5083.4  465.61  5262.4  466.14  5469.7  469.19
  5557.2  469.36    5584  469.26  6157.9  472.89  6233.4  474.28  6301.4  476.02
  6444.9  481.37  6786.3  491.43  6848.7   494.3  6924.6  493.07  6931.2  492.88
#Mann= 16 ,-1 , 0
  3540.2    .063       0  3822.2     .07       0  3946.4     .05       0
  4885.3     .07       0  4999.1     .05       0  5040.9     .07       0
  5262.4     .12       0  5469.7      .1       0  5557.2     .12       0
    5584      .1       0  6157.9     .12       0  6233.4     .07       0
  6301.4     .12       0  6444.9     .05       0  6786.3    .035       0
  6924.6     .05       0
Bank Sta=4999.1,5040.9
XS Rating Curve= 0 ,0
Exp/Cntr=0.3,0.1