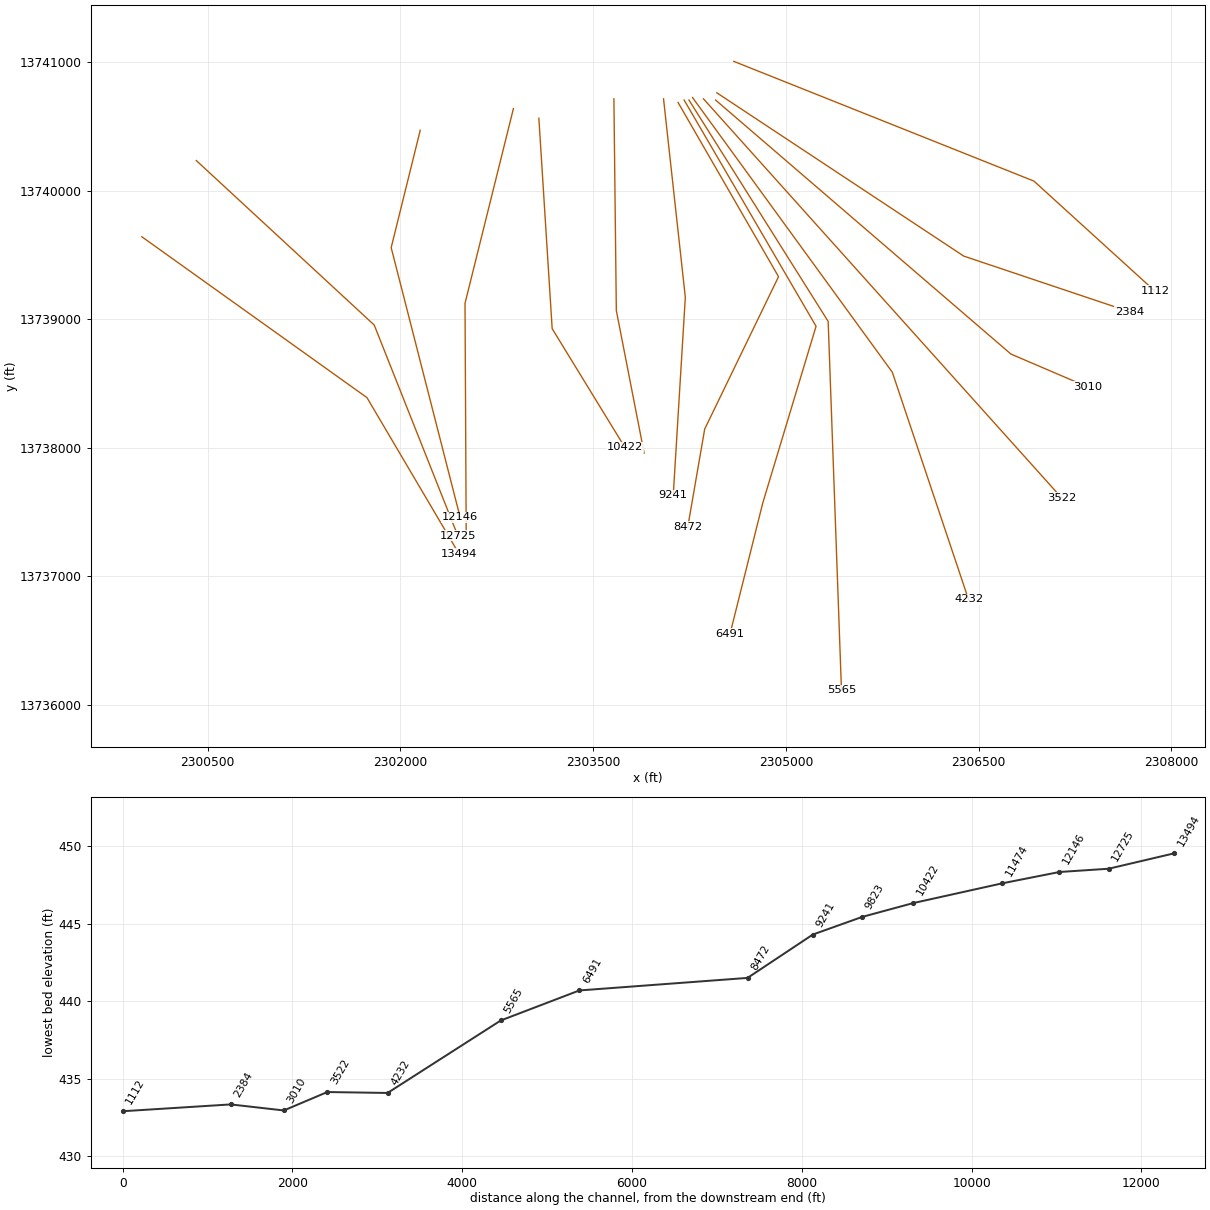
HEC-RAS study COTTONWOOD CREEK SOUTH.prj: COTTONWOOD CREEK SOUTH Base Level Engineering

--- COTTONWOOD CREEK SOUTH.g01 (geometry) --- (continued)

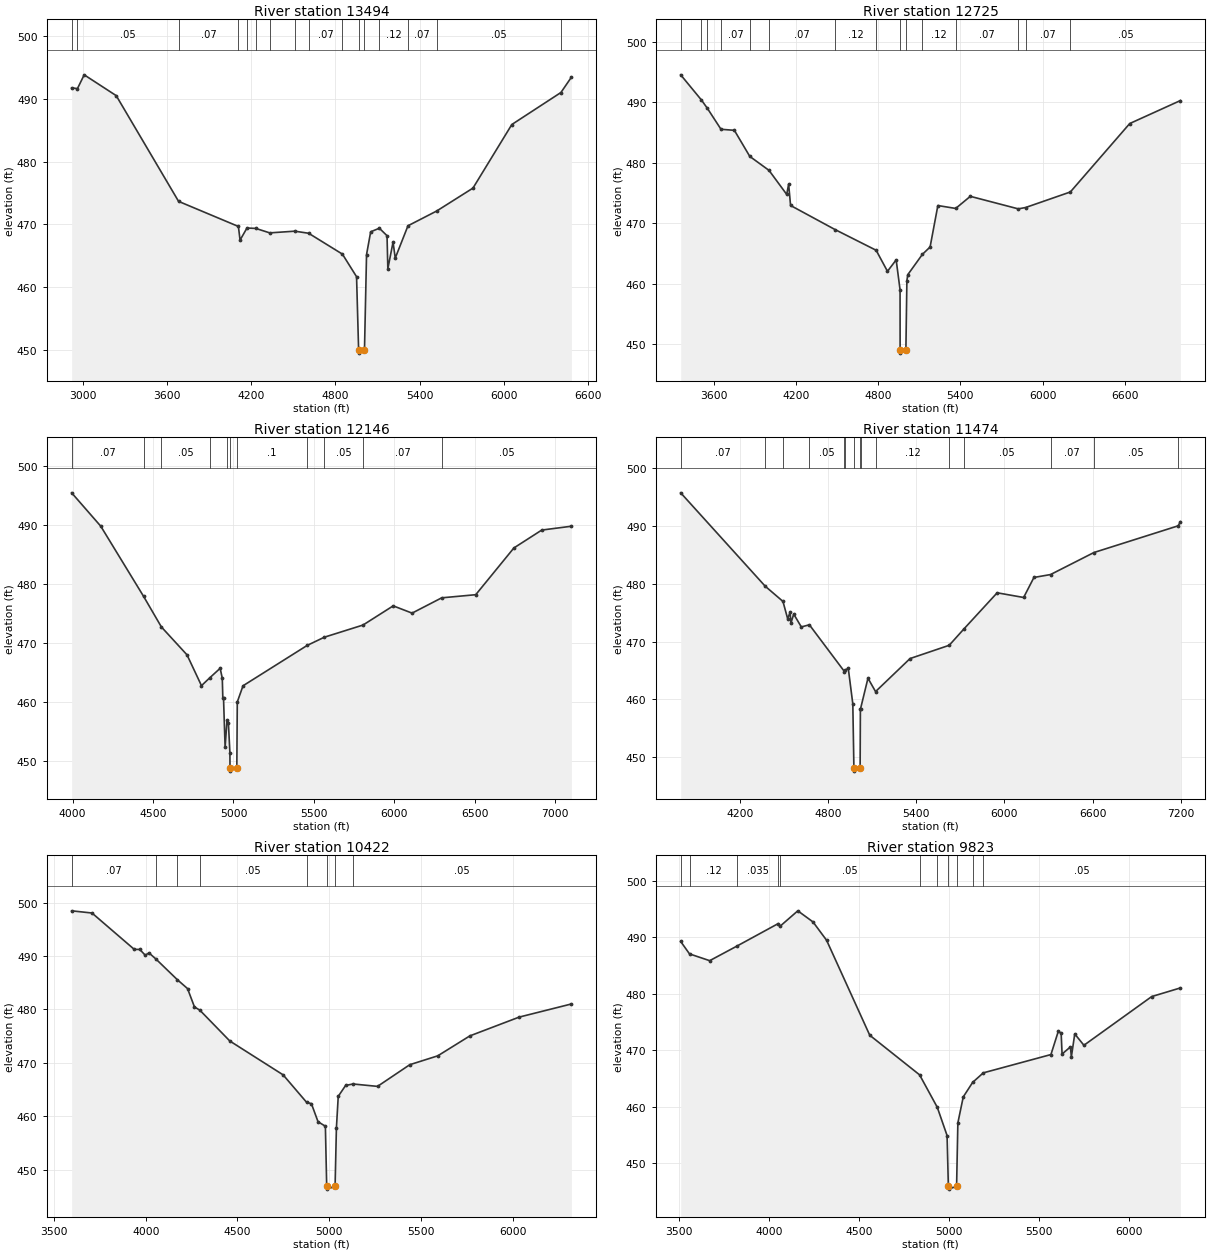
Type RM Length L Ch R = 1 ,13494   ,769,769,769
BEGIN DESCRIPTION:
X18620
END DESCRIPTION:
XS GIS Cut Line= 3
      2299988.01     13739642.52      2301740.04     13738389.73
      2302455.94     13737174.58
#Sta/Elev= 30
  2919.1  491.72  2960.4   491.6  3008.5  493.79    3237  490.48  3681.7  473.67
  4108.4  469.68  4120.2  467.51  4169.4  469.43    4232  469.37  4331.9  468.66
  4510.6  468.93  4609.1   468.6  4850.3  465.28  4951.1  461.69  4965.8  450.04
  4966.8  449.54  5007.6  450.04  5022.3  465.21  5051.8  468.83  5113.6   469.4
  5168.4  468.21  5174.2  462.95  5211.3  467.19    5227  464.65  5317.8  469.79
    5522  472.13  5781.4  475.78  6058.5  485.89  6408.7  490.98  6483.3  493.41
#Mann= 16 ,-1 , 0
  2919.1     .07       0  2960.4     .05       0  3681.7     .07       0
  4108.4      .1       0  4169.4     .07       0    4232     .12       0
  4331.9     .07       0  4510.6     .05       0  4609.1     .07       0
  4850.3     .12       0  4965.8     .05       0  5007.6     .12       0
  5113.6     .12       0  5317.8     .07       0    5522     .05       0
  6408.7    .035       0
Bank Sta=4965.8,5007.6
XS Rating Curve= 0 ,0
Exp/Cntr=0.3,0.1

Type RM Length L Ch R = 1 ,12725   ,579,579,579
BEGIN DESCRIPTION:
X18619
END DESCRIPTION:
XS GIS Cut Line= 3
      2300411.92     13740235.92      2301796.55     13738954.89
       2302446.5     13737315.89
#Sta/Elev= 30
  3357.3  494.54    3508   490.4  3552.6  488.99  3651.7  485.54  3749.3  485.37
  3861.9  481.06  4002.4  478.75  4131.5  474.78  4145.6  476.46  4159.8  472.95
  4484.6  468.97  4784.5  465.55  4867.4  462.07  4930.9  463.96  4959.3  459.03
  4959.8  449.05  4960.8  448.55  5001.9  449.05  5009.2  460.54    5016  461.52
  5122.7  464.88  5178.7  466.09  5235.4  472.94  5365.6  472.46  5472.4  474.46
  5822.5  472.39  5875.8  472.61  6202.9  475.18  6636.6  486.49  7006.8  490.29
#Mann= 15 ,-1 , 0
  3357.3     .05       0    3508     .07       0  3552.6     .05       0
  3651.7     .07       0  3861.9    .035       0  4002.4     .07       0
  4484.6     .12       0  4784.5      .1       0  4959.8     .05       0
  5001.9      .1       0  5122.7     .12       0  5365.6     .07       0
  5822.5     .05       0  5875.8     .07       0  6202.9     .05       0
Bank Sta=4959.8,5001.9
XS Rating Curve= 0 ,0
Exp/Cntr=0.3,0.1

Type RM Length L Ch R = 1 ,12146   ,672,672,672
BEGIN DESCRIPTION:
X18618
END DESCRIPTION:
XS GIS Cut Line= 3
       2302154.5     13740471.44      2301928.43     13739557.73
      2302464.98     13737458.58
#Sta/Elev= 30
  3993.7  495.49  4174.6  489.84  4440.6  477.97  4551.7  472.77  4711.1  468.04
  4801.1  462.82  4852.2  464.14  4917.2  465.76  4930.5  464.08  4933.8  460.75
  4938.1  460.75  4948.1   452.4    4960  456.98  4968.7  456.43  4977.8  451.48
  4978.6  448.84  4979.6  448.34  5020.9  448.84  5023.8  460.06  5059.5   462.8
  5458.5  469.64  5565.2  471.03  5805.7  473.09  5993.5  476.34  6110.8  475.11
    6295   477.7  6506.7  478.23    6744  486.15  6917.2  489.18  7101.6  489.83
#Mann= 11 ,-1 , 0
  3993.7     .07       0  4440.6    .035       0  4551.7     .05       0
  4852.2     .07       0    4960      .1       0  4978.6     .05       0
  5020.9      .1       0  5458.5     .12       0  5565.2     .05       0
  5805.7     .07       0    6295     .05       0
Bank Sta=4978.6,5020.9
XS Rating Curve= 0 ,0
Exp/Cntr=0.3,0.1

Type RM Length L Ch R = 1 ,11474   ,1052,1052,1052
BEGIN DESCRIPTION:
X18617
END DESCRIPTION:
XS GIS Cut Line= 3
      2302879.79     13740640.97      2302503.01     13739124.44
      2302512.42      13737288.8
#Sta/Elev= 30
    3799  495.69  4373.6  479.56  4494.4  476.93  4526.4  473.94  4543.3  475.08
  4548.4  473.17  4567.7  474.74  4619.2  472.52  4674.1  472.89  4912.7  464.81
  4919.7  465.09  4938.6  465.37  4969.5  459.22  4976.9  448.11  4977.9  447.61
  5019.2  448.11    5021   458.3  5021.9  458.37  5072.5  463.66  5124.1  461.35
  5358.8  467.06    5625  469.35  5723.4  472.13  5951.1  478.42  6131.1  477.61
  6201.1  481.07    6314  481.57  6609.4  485.38  7181.9  489.99  7197.3   490.7
#Mann= 15 ,-1 , 0
    3799     .07       0  4373.6    .035       0  4494.4     .07       0
  4674.1     .05       0  4912.7     .07       0  4919.7     .12       0
  4976.9     .05       0  5019.2     .12       0  5021.9      .1       0
  5124.1     .12       0    5625     .07       0  5723.4     .05       0
    6314     .07       0  6609.4     .05       0  7181.9    .035       0
Bank Sta=4976.9,5019.2
XS Rating Curve= 0 ,0
Exp/Cntr=0.3,0.1

Type RM Length L Ch R = 1 ,10422   ,599,599,599
BEGIN DESCRIPTION:
X18616
END DESCRIPTION:
XS GIS Cut Line= 3
      2303077.59     13740565.65       2303181.2     13738926.63
      2303746.39      13738003.5
#Sta/Elev= 30
    3596  498.47  3706.9  498.06  3937.3  491.25  3967.4  491.23  3997.4  490.15
  4017.5  490.59  4055.2  489.45  4172.1  485.57  4227.9   483.9  4265.6  480.46
  4294.8  479.86  4458.4  474.08  4748.9  467.74  4877.1  462.59  4903.2  462.34
  4939.3  458.96  4979.4  458.11  4986.6  446.83  4987.6  446.33  5032.3  446.83
  5039.5  457.77  5049.5  463.71  5089.6  465.75  5129.9  466.03  5263.7  465.58
  5439.5  469.64    5592   471.3  5767.1  475.04    6036  478.56  6320.7  481.02
#Mann= 8 ,-1 , 0
    3596     .07       0  4055.2    .035       0  4172.1     .07       0
  4294.8     .05       0  4877.1     .07       0  4986.6     .05       0
  5032.3     .07       0  5129.9     .05       0
Bank Sta=4986.6,5032.3
XS Rating Curve= 0 ,0
Exp/Cntr=0.3,0.1

Type RM Length L Ch R = 1 ,9823    ,582,582,582
BEGIN DESCRIPTION:
X18615
END DESCRIPTION:
XS GIS Cut Line= 3
      2303661.59     13740716.31      2303680.43     13739067.92
      2303896.73      13737958.2
#Sta/Elev= 30
  3508.6  489.26  3557.6  487.06  3669.9  485.86  3823.6  488.48  4051.4  492.43
  4060.8  491.94  4159.9  494.68  4244.6  492.71    4320  489.47    4560  472.67
  4837.1  465.66  4935.5  459.92    4990  454.92  4997.2  445.94  4998.2  445.44
  5042.9  445.94    5050  457.16    5080  461.76  5132.3  464.33  5191.3  466.01
  5567.6  469.25  5608.3  473.34  5624.4  473.04  5629.5  469.34  5676.1  470.61
  5681.1  468.81    5700   472.9    5751  470.89  6127.9  479.51  6287.7  481.04
#Mann= 11 ,-1 , 0
  3508.6     .07       0  3557.6     .12       0  3823.6    .035       0
  4051.4     .07       0  4060.8     .05       0  4837.1      .1       0
  4935.5     .12       0  4997.2     .05       0  5042.9     .12       0
  5132.3      .1       0  5191.3     .05       0
Bank Sta=4997.2,5042.9
XS Rating Curve= 0 ,0
Exp/Cntr=0.3,0.1

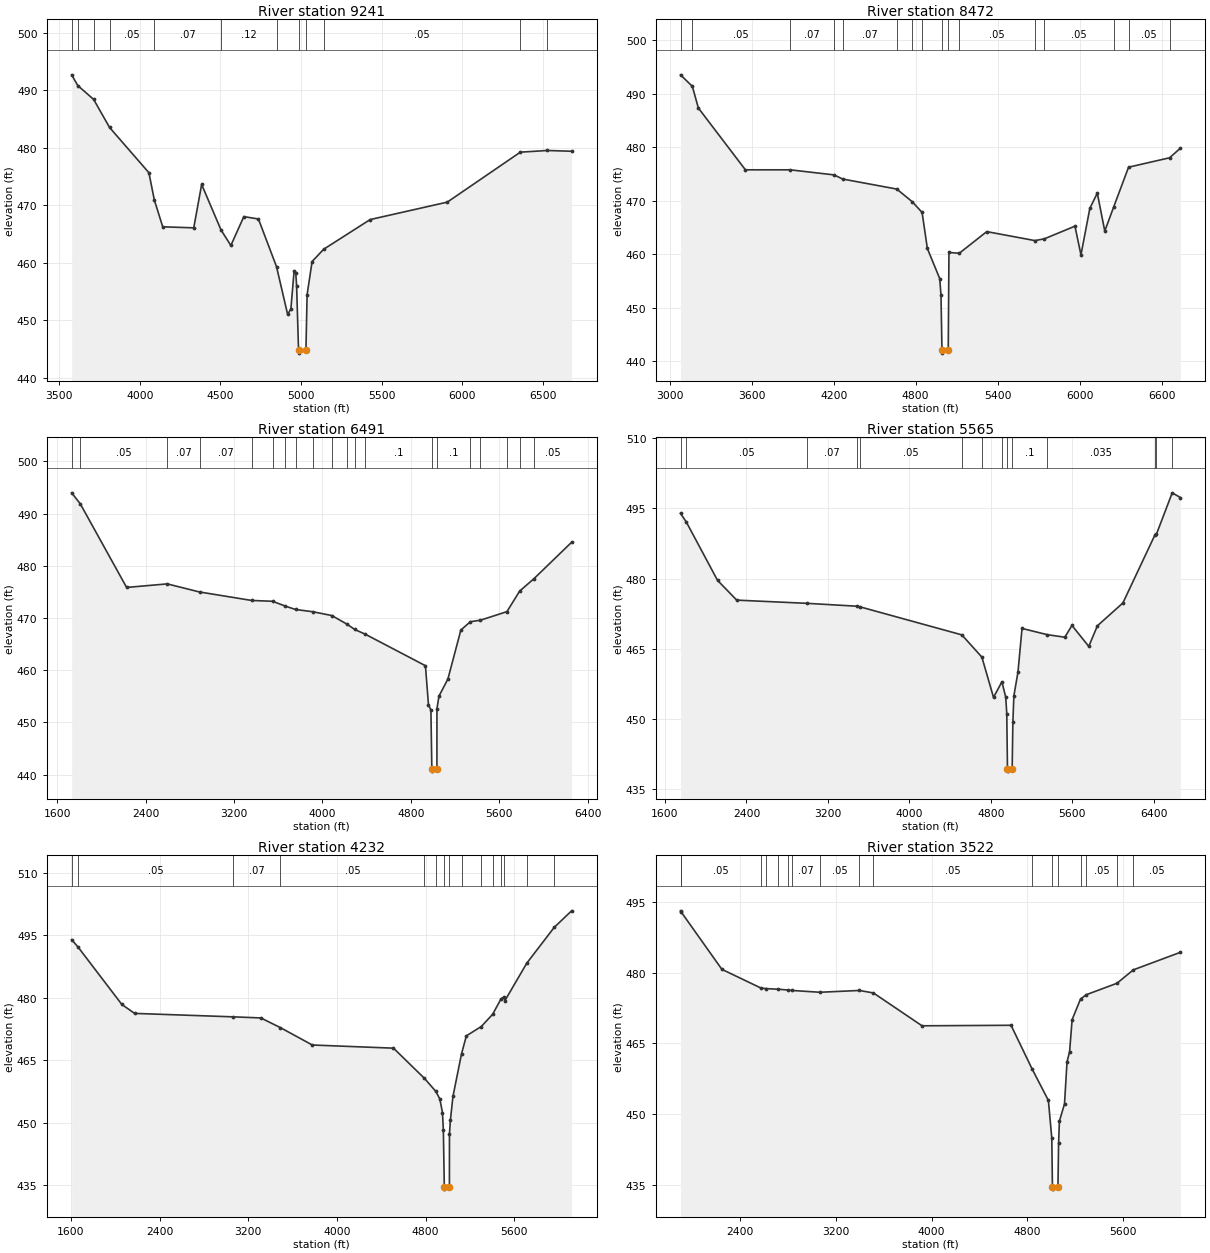
Type RM Length L Ch R = 1 ,9241    ,769,769,769
BEGIN DESCRIPTION:
X18614
END DESCRIPTION:
XS GIS Cut Line= 3
      2304047.79     13740716.33      2304217.34     13739171.54
      2304123.24     13737628.37
#Sta/Elev= 30
    3578   492.7  3615.7  490.84  3714.4  488.42  3813.2  483.54  4056.9  475.68
  4090.6  470.94  4142.7  466.27  4335.2  466.09  4384.1  473.64  4504.2  465.72
  4565.2  463.02  4645.7  468.04  4736.2  467.63  4848.3  459.34  4917.3  451.04
  4937.4  451.99  4957.6  458.64  4967.6  458.28  4972.9  456.04    4985   444.8
    4986   444.3  5030.8   444.8    5038  454.46    5069  460.23  5140.5  462.36
  5429.2  467.53  5907.4  470.56  6360.3  479.25  6526.9  479.54  6678.1  479.41
#Mann= 12 ,-1 , 0
    3578     .07       0  3615.7    .035       0  3714.4     .07       0
  3813.2     .05       0  4090.6     .07       0  4504.2     .12       0
  4848.3      .1       0    4985     .05       0  5030.8      .1       0
  5140.5     .05       0  6360.3     .07       0  6526.9     .05       0
Bank Sta=4985,5030.8
XS Rating Curve= 0 ,0
Exp/Cntr=0.3,0.1

Type RM Length L Ch R = 1 ,8472    ,1981,1981,1981
BEGIN DESCRIPTION:
X18613
END DESCRIPTION:
XS GIS Cut Line= 4
       2304160.8     13740688.09      2304942.63     13739331.67
      2304368.05     13738144.82      2304236.18     13737381.86
#Sta/Elev= 30
  3078.9  493.56  3165.7   491.4  3209.4  487.36  3553.9  475.79  3881.1  475.79
  4203.1  474.84    4265  474.07  4661.8  472.19  4774.4  469.83  4846.9  467.82
  4885.4  461.08  4975.8  455.45  4985.2  452.39  4992.4     442  4993.4   441.5
  5038.3     442  5043.5  460.33  5118.9  460.18  5320.1  464.23    5673  462.55
  5742.6  462.89  5965.6  465.25  6009.5  459.88  6074.6  468.59  6129.1  471.43
  6183.8  464.34  6248.6  468.81  6357.9  476.28  6657.9  478.04  6737.4  479.84
#Mann= 16 ,-1 , 0
  3078.9    .035       0  3165.7     .05       0  3881.1     .07       0
  4203.1     .05       0    4265     .07       0  4661.8    .035       0
  4774.4     .07       0  4846.9      .1       0  4992.4     .05       0
  5038.3      .1       0  5118.9     .05       0    5673      .1       0
  5742.6     .05       0  6248.6     .07       0  6357.9     .05       0
  6657.9    .035       0
Bank Sta=4992.4,5038.3
XS Rating Curve= 0 ,0
Exp/Cntr=0.3,0.1

Type RM Length L Ch R = 1 ,6491    ,926,926,926
BEGIN DESCRIPTION:
X18612
END DESCRIPTION:
XS GIS Cut Line= 4
      2304207.92     13740706.89      2305234.63     13738945.47
      2304820.18     13737570.24      2304565.86     13736552.98
#Sta/Elev= 30
  1731.7  493.96  1809.8  491.85    2229  475.85  2596.7  476.53  2888.9  474.98
  3359.9  473.36  3550.8   473.2  3662.9  472.29  3757.5  471.63  3913.5   471.2
  4085.8  470.47  4224.3  468.81  4293.3   467.8  4390.4  466.88  4932.9  460.87
  4960.6  453.38  4982.5  452.38  4990.9  441.19  4991.9  440.69  5036.8  441.19
  5037.1  452.64  5055.6  455.06  5136.1  458.31  5253.7   467.7  5339.6  469.29
  5431.2  469.58  5670.6  471.22  5785.4  475.15  5915.6  477.54  6255.4  484.49
#Mann= 20 ,-1 , 0
  1731.7    .035       0  1809.8     .05       0  2596.7     .07       0
  2888.9     .07       0  3359.9    .035       0  3550.8     .07       0
  3662.9    .035       0  3757.5     .05       0  3913.5     .07       0
  4085.8     .05       0  4224.3     .07       0  4293.3     .05       0
  4390.4      .1       0  4990.9     .05       0  5036.8      .1       0
  5339.6    .035       0  5431.2     .07       0  5670.6     .05       0
  5785.4     .07       0  5915.6     .05       0
Bank Sta=4990.9,5036.8
XS Rating Curve= 0 ,0
Exp/Cntr=0.3,0.1

Type RM Length L Ch R = 1 ,5565    ,1333,1333,1333
BEGIN DESCRIPTION:
X18611
END DESCRIPTION:
XS GIS Cut Line= 3
       2304245.6     13740706.89      2305328.83     13738983.15
      2305432.44     13736110.26
#Sta/Elev= 30
  1752.3  493.96  1810.6  492.05  2116.2   479.6  2304.7  475.37  2999.2  474.68
  3482.2  474.07  3510.9  473.96  4515.7  467.93  4712.6  463.17    4827  454.54
  4909.4  457.88    4947  454.57  4957.1  451.09  4964.1  439.25  4965.1  438.75
  5010.1  439.25  5017.1  449.28  5027.1  454.88  5067.1  459.96  5107.1  469.31
  5355.4  467.97  5527.4  467.43  5597.5  469.95  5762.7  465.46  5847.6  469.88
  6097.8  474.76  6413.5  489.38  6427.7  489.51  6582.4  498.35  6662.9  497.34
#Mann= 14 ,-1 , 0
  1752.3    .035       0  1810.6     .05       0  2999.2     .07       0
  3482.2    .035       0  3510.9     .05       0  4515.7      .1       0
  4712.6     .12       0  4909.4      .1       0  4964.1     .05       0
  5010.1      .1       0  5355.4    .035       0  6413.5     .07       0
  6427.7    .035       0  6582.4     .07       0
Bank Sta=4964.1,5010.1
XS Rating Curve= 0 ,0
Exp/Cntr=0.3,0.1

Type RM Length L Ch R = 1 ,4232    ,710,710,710
BEGIN DESCRIPTION:
X18610
END DESCRIPTION:
XS GIS Cut Line= 3
      2304273.82     13740725.78      2305828.05     13738587.53
      2306420.92     13736818.36
#Sta/Elev= 30
  1606.8  493.98  1666.5  492.13  2059.3  478.42  2174.4  476.27  3065.3  475.44
  3312.9  475.18  3490.5  472.84  3777.4  468.68  4509.7  467.92  4787.5  460.71
  4892.3  457.52  4927.9  455.69  4951.5  452.47  4959.5  448.34  4968.1  434.57
  4969.1  434.07  5014.2  434.57  5014.6  447.31  5022.8  450.57  5046.2  456.34
  5123.4  466.56  5167.1  470.88  5301.6  473.12  5404.4  476.06  5480.3  479.79
  5507.2   480.2  5514.2  479.31  5712.8  488.36  5959.4  496.92  6116.1   500.9
#Mann= 15 ,-1 , 0
  1606.8    .035       0  1666.5     .05       0  3065.3     .07       0
  3490.5     .05       0  4787.5     .07       0  4892.3      .1       0
  4968.1     .05       0  5014.2      .1       0  5123.4     .07       0
  5301.6    .035       0  5404.4     .07       0  5480.3     .05       0
  5507.2     .07       0  5712.8     .05       0  5959.4     .07       0
Bank Sta=4968.1,5014.2
XS Rating Curve= 0 ,0
Exp/Cntr=0.3,0.1

Type RM Length L Ch R = 1 ,3522    ,512,512,512
BEGIN DESCRIPTION:
X18609
END DESCRIPTION:
XS GIS Cut Line= 2
      2304358.62     13740716.33       2307145.8     13737608.99
#Sta/Elev= 30
  1904.1  493.12  1911.2  492.83  2249.5  480.72  2576.9  476.74  2621.3  476.63
  2714.4  476.51  2804.7  476.33  2835.6  476.24  3067.7  475.86  3398.6  476.24
  3515.1  475.71  3920.9  468.75  4664.1  468.86  4838.5  459.67  4975.9  452.93
  5004.3  444.93  5009.6  434.63  5010.6  434.13  5055.7  434.63  5061.1  443.84
  5067.8  448.54  5110.4  452.19  5131.4  461.09    5153  463.29    5174  470.05
  5244.2  474.42  5291.3  475.33    5549  477.77  5685.2  480.61  6078.3  484.33
#Mann= 17 ,-1 , 0
  1904.1    .035       0  1911.2     .05       0  2576.9     .07       0
  2621.3     .05       0  2714.4     .07       0  2804.7     .05       0
  2835.6     .07       0  3067.7     .05       0  3398.6     .07       0
  3515.1     .05       0  4838.5      .1       0  5009.6     .05       0
  5055.7      .1       0  5244.2     .07       0  5291.3     .05       0
    5549    .035       0  5685.2     .05       0
Bank Sta=5009.6,5055.7
XS Rating Curve= 0 ,0
Exp/Cntr=0.3,0.1

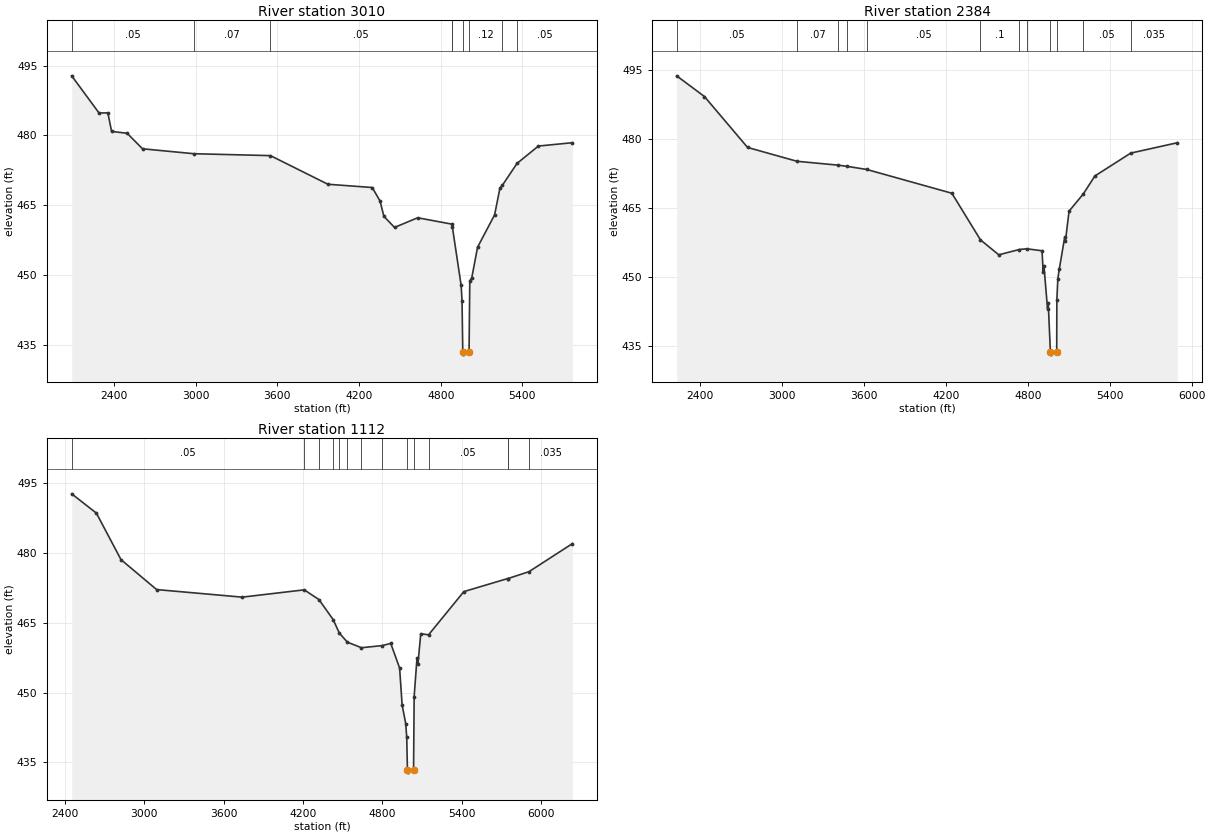
Type RM Length L Ch R = 1 ,3010    ,626,626,626
BEGIN DESCRIPTION:
X18608
END DESCRIPTION:
XS GIS Cut Line= 3
      2304452.84     13740706.88      2306751.15     13738728.83
      2307344.54     13738474.52
#Sta/Elev= 30
  2089.6  492.82  2290.5  484.82  2355.2  484.85  2382.7  480.86  2496.8  480.46
  2609.8  477.12  2987.9  476.06  3549.5  475.65  3971.5  469.49  4297.3  468.79
  4354.4  465.88  4382.9  462.59  4460.8   460.2  4630.9  462.28  4882.3  460.91
  4886.2  460.22  4950.2  447.74  4956.8  444.38  4962.2  433.44  4963.2  432.94
  5008.4  433.44  5013.8   448.7  5028.1  449.33  5070.9  455.95    5196   462.9
  5234.9  468.61  5252.4  469.24  5360.9  473.98  5517.8  477.71  5767.5  478.43
#Mann= 9 ,-1 , 0
  2089.6     .05       0  2987.9     .07       0  3549.5     .05       0
  4882.3     .07       0  4886.2     .12       0  4962.2     .05       0
  5008.4     .12       0  5252.4     .07       0  5360.9     .05       0
Bank Sta=4962.2,5008.4
XS Rating Curve= 0 ,0
Exp/Cntr=0.3,0.1

Type RM Length L Ch R = 1 ,2384    ,1272,1272,1272
BEGIN DESCRIPTION:
X18607
END DESCRIPTION:
XS GIS Cut Line= 3
      2304462.26      13740763.4       2306383.8      13739491.8
      2307674.21     13739058.52
#Sta/Elev= 30
    2230  493.72  2433.3  489.23  2749.2  478.18  3110.2  475.18  3414.5  474.33
  3474.6  474.09  3621.7   473.4  4244.7  468.24  4453.9  458.13  4588.2  454.88
  4737.8  456.03  4792.4  456.19  4904.7  455.76  4913.4  451.11  4918.7  452.51
  4944.9  443.23  4950.2  444.43    4966  433.83    4967  433.33  5012.2  433.83
  5013.3  445.16  5020.7  449.73  5031.2  451.79    5071  458.76  5076.3  457.94
  5102.6  464.35  5206.8  468.09  5291.8  471.99    5554  476.95  5895.4   479.2
#Mann= 12 ,-1 , 0
    2230     .05       0  3110.2     .07       0  3414.5     .05       0
  3474.6     .07       0  3621.7     .05       0  4453.9      .1       0
  4737.8     .07       0  4792.4      .1       0    4966     .05       0
  5012.2      .1       0  5206.8     .05       0    5554    .035       0
Bank Sta=4966,5012.2
XS Rating Curve= 0 ,0
Exp/Cntr=0.3,0.1

Type RM Length L Ch R = 1 ,1112    ,0,0,0
BEGIN DESCRIPTION:
X18606
END DESCRIPTION:
XS GIS Cut Line= 3
      2304594.16      13741008.3      2306930.12      13740075.8
       2307870.3     13739220.24
#Sta/Elev= 30
    2452  492.74  2638.8  488.59  2824.7  478.59  3094.2  472.15  3740.9  470.52
  4210.8  472.09  4321.6     470  4428.8  465.71  4475.8   462.8  4536.1  460.85
  4643.4  459.64  4799.4   460.1  4864.8  460.57  4931.8  455.26  4950.7  447.33
  4978.2  443.29  4985.6  440.35  4990.9  433.39  4991.9  432.89  5037.2  433.39
  5041.7  449.13  5063.3  457.44  5070.1  456.07  5091.7  462.65  5150.7  462.42
  5417.4  471.71  5747.9  474.51  5749.1   474.5  5909.5  475.99  6238.4  482.03
#Mann= 14 ,-1 , 0
    2452     .05       0  4210.8     .07       0  4321.6     .05       0
  4428.8     .07       0  4475.8     .05       0  4536.1     .07       0
  4643.4     .12       0  4799.4      .1       0  4990.9     .05       0
  5037.2      .1       0  5150.7     .05       0  5747.9    .035       0
  5749.1     .05       0  5909.5    .035       0
Bank Sta=4990.9,5037.2
XS Rating Curve= 0 ,0
Exp/Cntr=0.3,0.1

Chan Stop Cuts=-1
Use User Specified Reach Order=0
Composite Channel Slope=5