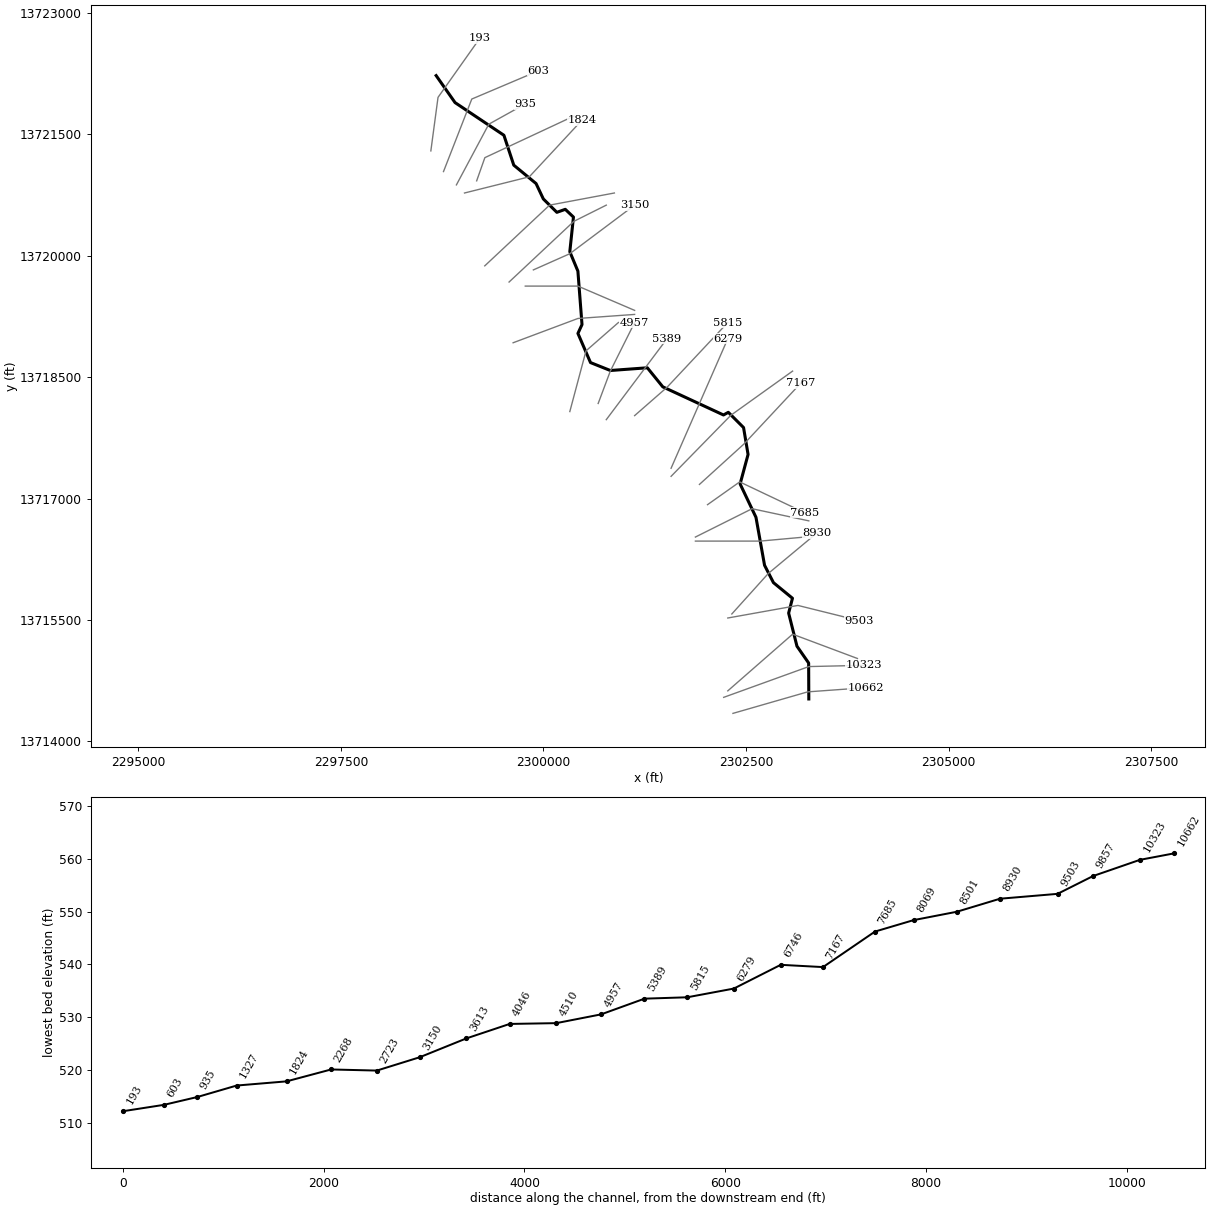
--- COTTONWOOD TRIBUTARY 1 2.prj (project) ---

Proj Title=COTTONWOOD TRIBUTARY 1 2 Base Level Engineering
Current Plan=p01
Default Exp/Contr=0.3,0.1
English Units
Geom File=g01
Flow File=f01
Plan File=p01
Y Axis Title=Elevation
X Axis Title(PF)=Main Channel Distance
X Axis Title(XS)=Station
BEGIN DESCRIPTION:
COTTONWOOD TRIBUTARY 1 2
END DESCRIPTION:
DSS Export Rating Curves= 0
DSS Export Rating Curve Sorted= 0
DSS Export Volume Flow Curves= 0
DXF OffsetX= 0
DXF OffsetY= 0
DXF ScaleX= 1
DXF ScaleY= 10

--- COTTONWOOD TRIBUTARY 1 2.p01 (plan) ---

Plan Title=Multiple Run
Short Identifier=Multiple
Geom File=g01
Flow File=f01
Subcritical Flow
K Sum by GR= 0
Std Step Tol= 0.01
Critical Tol= 0.01
Num of Std Step Trials= 20
Max Error Tol= 0.3
Flow Tol Ratio= 0.001
Split Flow NTrial= 30
Split Flow Tol= 0.02
Split Flow Ratio= 0.02
Log Output Level= 0
Friction Slope Method= 1
Unsteady Friction Slope Method= 2
Unsteady Bridges Friction Slope Method= 1
Parabolic Critical Depth
Global Vel Dist=  1 , 1 , 1
Global Log Level= 0
CheckData=True
Encroach Param= -1, 0, 0, 0
BEGIN DESCRIPTION:
Multiple Run
END DESCRIPTION:

--- COTTONWOOD TRIBUTARY 1 2.f01 (steady flow) ---

Flow Title=Multiple
Number of Profiles=7
Profile Names=10-year,25-year,50-year,1pct_min,100-year,1pct_plu,500-year
River Rch & RM= COTTONWOOD TRIBU,Reach-1,10662
     960    1619    2240    1502    2996    5978    5314
River Rch & RM= COTTONWOOD TRIBU,Reach-1,8930
    1292    2206    3077    2077    4143    8267    7452
River Rch & RM= COTTONWOOD TRIBU,Reach-1,6279
    1549    2640    3679    2476    4941    9858    8840
Boundary for River Rch & Prof#=COTTONWOOD TRIBU,Reach-1,1
Up Type=0
Dn Type=3
Dn Slope=0.005
Boundary for River Rch & Prof#=COTTONWOOD TRIBU,Reach-1,2
Up Type=0
Dn Type=3
Dn Slope=0.005
Boundary for River Rch & Prof#=COTTONWOOD TRIBU,Reach-1,3
Up Type=0
Dn Type=3
Dn Slope=0.005
Boundary for River Rch & Prof#=COTTONWOOD TRIBU,Reach-1,4
Up Type=0
Dn Type=3
Dn Slope=0.005
Boundary for River Rch & Prof#=COTTONWOOD TRIBU,Reach-1,5
Up Type=0
Dn Type=3
Dn Slope=0.005
Boundary for River Rch & Prof#=COTTONWOOD TRIBU,Reach-1,6
Up Type=0
Dn Type=3
Dn Slope=0.005
Boundary for River Rch & Prof#=COTTONWOOD TRIBU,Reach-1,7
Up Type=0
Dn Type=3
Dn Slope=0.005

--- COTTONWOOD TRIBUTARY 1 2.g01 (geometry) ---

Geom Title=Existing Conditions
Program Version=4.10

River Reach=COTTONWOOD TRIBU,Reach-1
Reach XY= 30
        2303275.       13714525.      2303273.03     13714969.11
      2303128.83     13715176.58       2303026.1     13715585.55
      2303073.39     13715768.98      2302838.61     13715961.76
      2302728.75     13716176.55      2302622.74     13716769.06
      2302427.06     13717180.86      2302525.29     13717545.17
      2302469.54     13717877.45      2302281.67      13718065.7
      2302221.67     13718033.02      2301472.57     13718380.52
      2301281.95     13718615.82       2300824.9     13718582.33
      2300580.41     13718680.18      2300425.08     13719040.39
      2300475.39       13719150.      2300424.61     13719809.84
      2300324.86     13720049.89      2300369.89     13720477.31
      2300268.96     13720573.35      2300164.95     13720536.11
      2299998.01     13720701.53      2299908.36     13720891.68
      2299633.13     13721118.93      2299511.38     13721488.22
      2298908.29     13721891.63        2298675.       13722225.

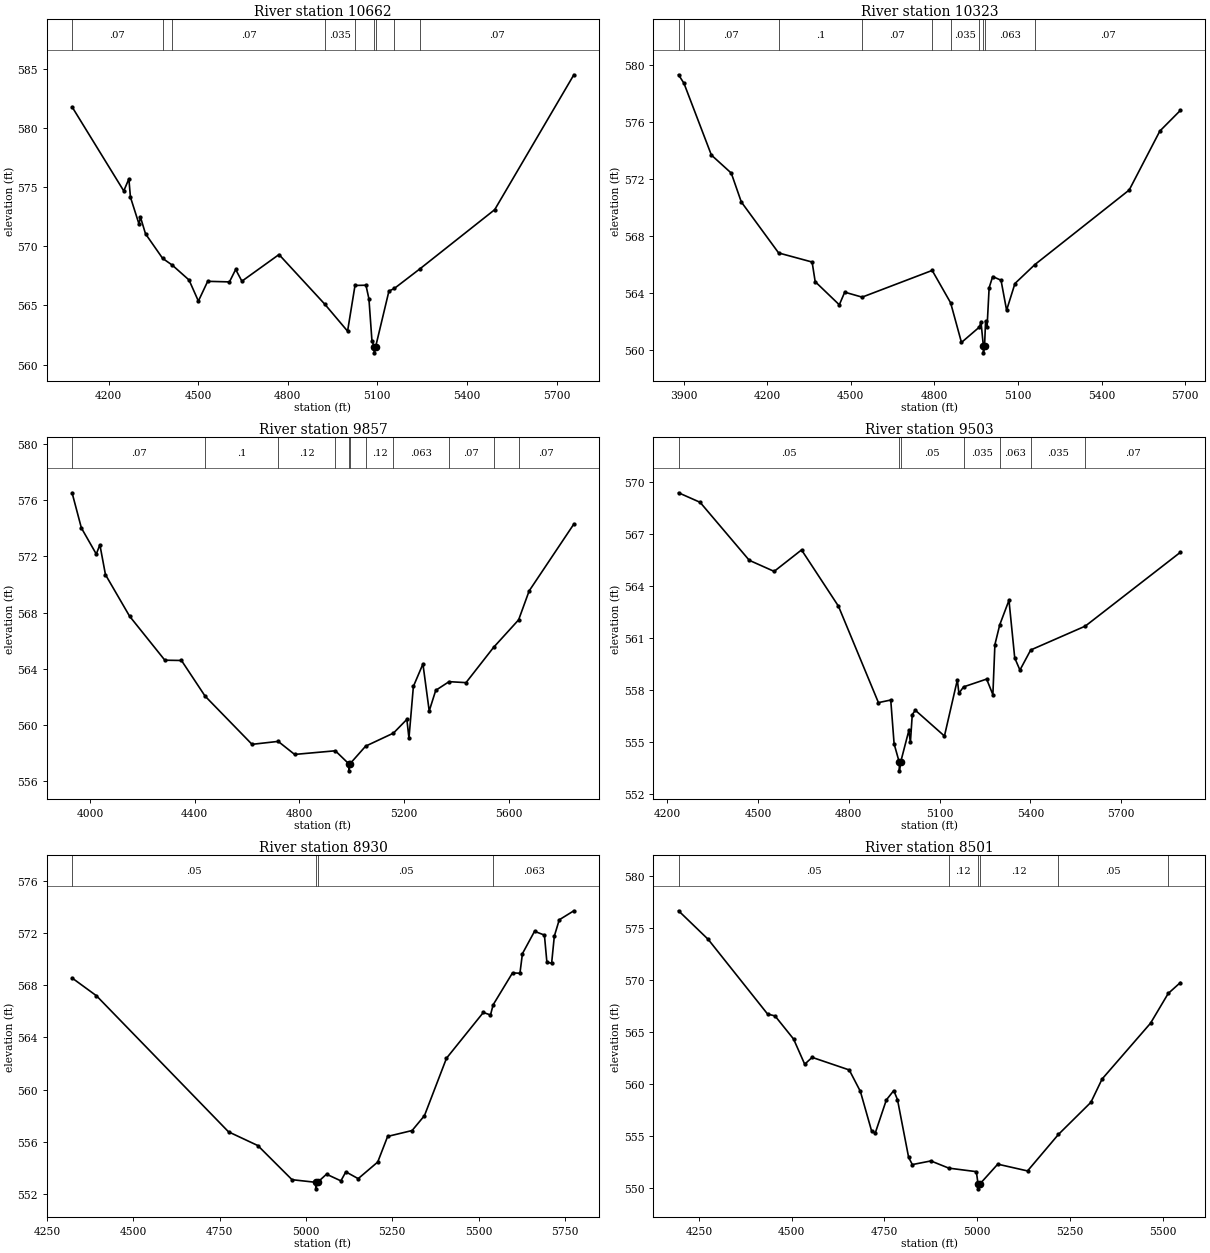
Type RM Length L Ch R = 1 ,10662   ,339,339,339
BEGIN DESCRIPTION:
X18667
END DESCRIPTION:
XS GIS Cut Line= 3
      2302338.67     13714346.92      2303260.57     13714612.55
      2303979.28     13714664.63
#Sta/Elev= 30
  4077.9  581.76    4251  574.66  4268.1  575.68  4273.3  574.14  4301.8  571.88
    4307  572.44  4323.8  571.04    4381  568.97  4413.7  568.39  4469.5  567.14
  4500.8  565.36    4532  567.03  4604.8  566.98  4625.6  568.03  4646.5  567.04
  4770.7  569.29  4923.6  565.11  5000.3  562.82  5025.2  566.68  5061.8   566.7
  5071.8  565.55  5081.9  562.01  5089.7  561.49    5090  560.99  5094.1  561.49
  5138.7   566.2    5157  566.43  5243.4   568.1  5492.9  573.08  5757.9  584.47
#Mann= 9 ,-1 , 0
  4077.9     .07       0    4381      .1       0  4413.7     .07       0
  4923.6    .035       0  5025.2    .063       0  5089.7    .035       0
  5094.1    .063       0    5157    .035       0  5243.4     .07       0
Bank Sta=5089.7,5094.1
XS Rating Curve= 0 ,0
Exp/Cntr=0.3,0.1

Type RM Length L Ch R = 1 ,10323   ,466,466,466
BEGIN DESCRIPTION:
COTTONWOOD TRIBUTARY 1 2 22.0
END DESCRIPTION:
XS GIS Cut Line= 3
      2302224.09     13714544.84        2303275.       13714925.
      2303958.47     13714940.68
#Sta/Elev= 30
  3881.6  579.34  3901.1  578.74  3999.5  573.69  4070.9  572.42  4106.9  570.39
  4240.9   566.8  4361.1  566.16  4372.1  564.78  4458.7  563.15  4478.1  564.04
  4540.6  563.69  4792.1  565.57  4858.3  563.29  4897.2   560.5  4961.9  561.59
  4967.2  561.97  4975.7  560.27    4976  559.77  4980.1  560.27  4983.8  562.02
  4989.1  561.58  4996.5  564.35  5009.2  565.14  5039.2  564.88  5059.2  562.77
  5089.2  564.65  5160.6  565.98  5499.3  571.23  5609.3  575.38  5682.8  576.83
#Mann= 10 ,-1 , 0
  3881.6    .035       0  3901.1     .07       0  4240.9      .1       0
  4540.6     .07       0  4792.1     .12       0  4858.3    .035       0
  4961.9    .063       0  4975.7    .063       0  4980.1    .063       0
  5160.6     .07       0
Bank Sta=4975.7,4980.1
XS Rating Curve= 0 ,0
Exp/Cntr=0.3,0.1

Type RM Length L Ch R = 1 ,9857    ,354,354,354
BEGIN DESCRIPTION:
COTTONWOOD TRIBUTARY 1 2 21.0
END DESCRIPTION:
XS GIS Cut Line= 3
      2302275.02     13714625.02        2303075.       13715325.
      2303875.01       13715025.
#Sta/Elev= 30
    3931  576.54  3966.6  574.03  4023.5  572.17  4037.3  572.83  4058.6   570.7
  4150.7  567.74  4285.5   564.6  4349.1  564.58  4439.2  562.04  4618.6   558.6
  4718.6  558.81  4781.4  557.88  4936.9  558.14  4988.5  557.21  4988.8  556.71
  4992.9  557.21  5052.7  558.47    5159   559.4  5210.3  560.38  5218.3  559.04
  5235.2  562.73  5271.7  564.33  5295.7  560.98  5320.6  562.45  5371.6  563.07
  5436.3     563  5541.4  565.51  5637.4  567.48  5677.5  569.54  5848.4  574.31
#Mann= 11 ,-1 , 0
    3931     .07       0  4439.2      .1       0  4718.6     .12       0
  4936.9      .1       0  4988.5     .05       0  4992.9      .1       0
  5052.7     .12       0    5159    .063       0  5371.6     .07       0
  5541.4     .12       0  5637.4     .07       0
Bank Sta=4988.5,4992.9
XS Rating Curve= 0 ,0
Exp/Cntr=0.3,0.1

Type RM Length L Ch R = 1 ,9503    ,573,573,573
BEGIN DESCRIPTION:
COTTONWOOD TRIBUTARY 1 2 20.0
END DESCRIPTION:
XS GIS Cut Line= 3
      2302274.95     13715524.99      2303140.77     13715680.26
      2303896.01     13715492.75
#Sta/Elev= 30
  4237.6   569.4  4308.8  568.85  4471.3   565.5  4553.5  564.86    4644   566.1
  4765.9  562.85    4898  557.28  4938.7  557.43  4949.8   554.9  4966.8  553.84
  4967.2  553.34  4971.4  553.84  4998.5  555.67  5003.6  554.98  5009.8  556.59
  5019.9  556.84  5116.1  555.35  5158.7  558.59  5163.9  557.82  5179.3  558.19
  5255.5  558.64  5276.1  557.74  5282.8  560.63  5298.9  561.78  5329.3  563.19
  5348.3  559.86  5365.5  559.16  5401.1  560.32  5581.5   561.7  5895.4  565.96
#Mann= 7 ,-1 , 0
  4237.6     .05       0  4966.8     .05       0  4971.4     .05       0
  5179.3    .035       0  5298.9    .063       0  5401.1    .035       0
  5581.5     .07       0
Bank Sta=4966.8,4971.4
XS Rating Curve= 0 ,0
Exp/Cntr=0.3,0.1

Type RM Length L Ch R = 1 ,8930    ,429,429,429
BEGIN DESCRIPTION:
COTTONWOOD TRIBUTARY 1 2 19.0
END DESCRIPTION:
XS GIS Cut Line= 3
        2302325.       13715575.        2302775.       13716075.
      2303374.99     13716574.99
#Sta/Elev= 30
  4322.5  568.55  4393.1  567.19  4775.8  556.78  4860.7  555.73  4959.7  553.12
  5028.1  552.92  5028.6  552.42  5033.8  552.92  5059.6  553.54  5101.3  553.03
  5115.6  553.72  5151.4   553.2    5208  554.47  5236.7  556.43  5307.6  556.88
  5343.4  558.02  5407.2  562.41  5513.9  565.91  5534.7  565.72  5542.4   566.5
  5598.5  568.94    5620  568.91  5627.2  570.41  5662.3  572.12  5690.9  571.83
  5698.1  569.75  5711.8  569.68  5719.6  571.75  5733.9     573  5776.2  573.69
#Mann= 4 ,-1 , 0
  4322.5     .05       0  5028.1     .05       0  5033.8     .05       0
  5542.4    .063       0
Bank Sta=5028.1,5033.8
XS Rating Curve= 0 ,0
Exp/Cntr=0.3,0.1

Type RM Length L Ch R = 1 ,8501    ,432,432,432
BEGIN DESCRIPTION:
COTTONWOOD TRIBUTARY 1 2 18.0
END DESCRIPTION:
XS GIS Cut Line= 3
      2301875.05       13716475.        2302675.       13716475.
      2303224.98       13716525.
#Sta/Elev= 30
  4195.2  576.67  4275.2  573.92  4435.2  566.75  4455.2  566.57  4505.2  564.35
  4535.2  561.93  4555.2  562.59  4655.2  561.38  4685.2  559.32  4715.2  555.55
  4725.2  555.31  4755.2   558.5  4775.2   559.4  4785.2  558.53  4815.2  552.99
  4825.2  552.29  4875.2  552.64  4923.4  551.95  4997.7  551.61  5002.2  550.46
  5002.7  549.96  5008.1  550.46  5055.4  552.33  5135.7  551.68    5219  555.19
  5306.4  558.27  5336.6  560.51  5467.1  565.87  5514.8  568.73  5547.4  569.77
#Mann= 6 ,-1 , 0
  4195.2     .05       0  4923.4     .12       0  5002.2     .05       0
  5008.1     .12       0    5219     .05       0  5514.8    .063       0
Bank Sta=5002.2,5008.1
XS Rating Curve= 0 ,0
Exp/Cntr=0.3,0.1

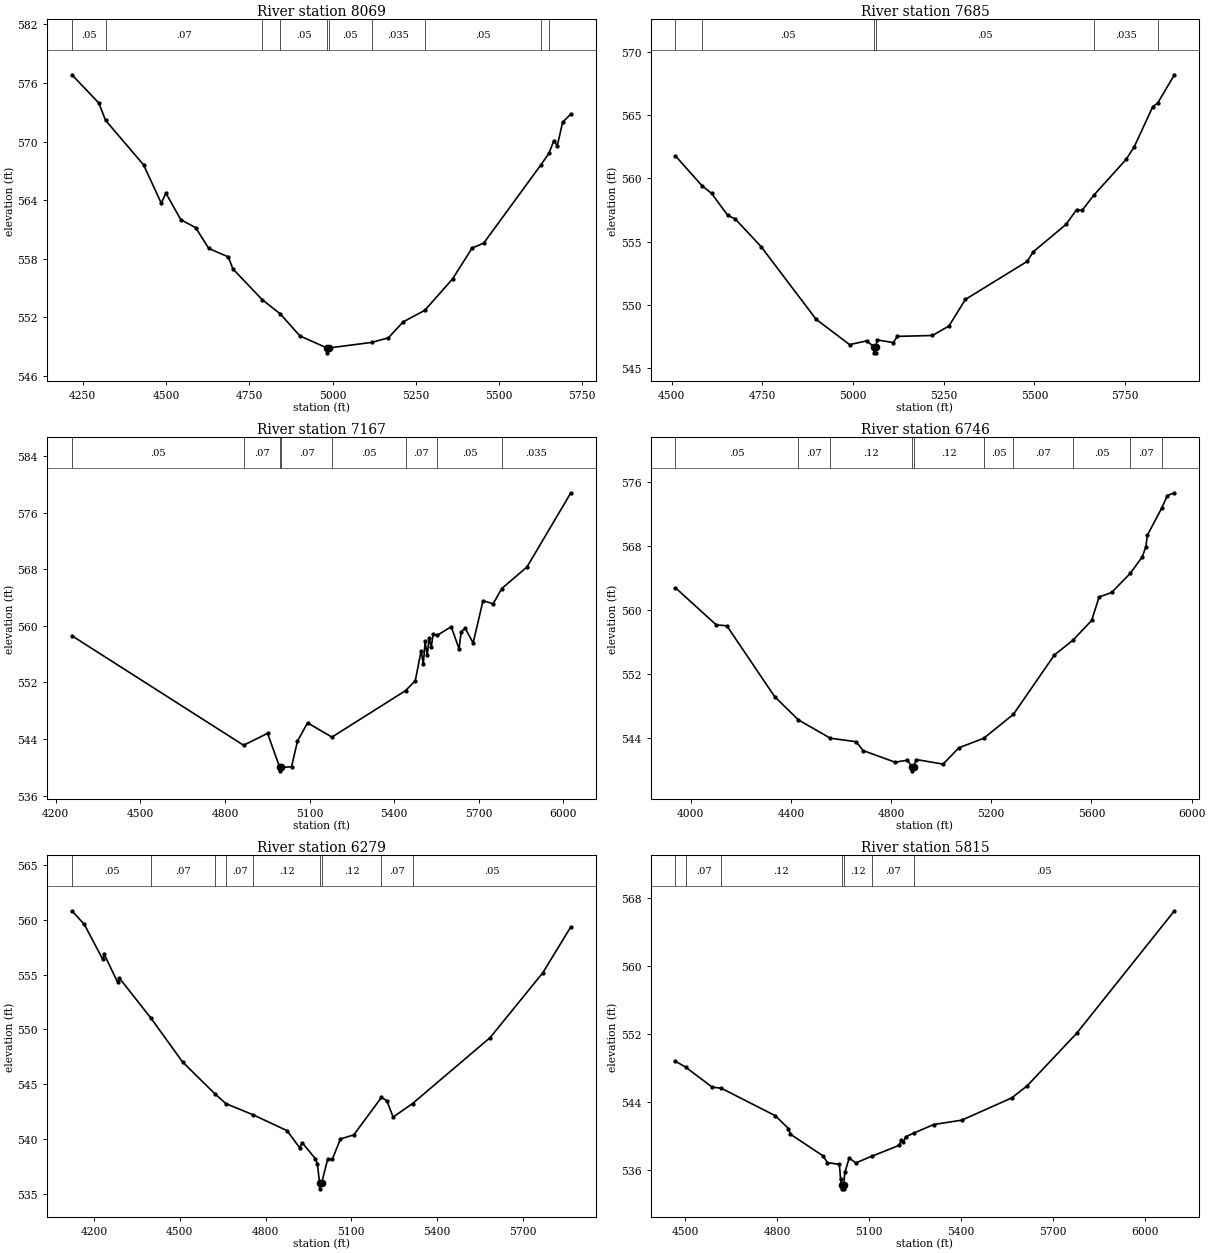
Type RM Length L Ch R = 1 ,8069    ,384,384,384
BEGIN DESCRIPTION:
COTTONWOOD TRIBUTARY 1 2 17.0
END DESCRIPTION:
XS GIS Cut Line= 3
      2301875.02     13716525.01        2302575.       13716875.
      2303275.01       13716725.
#Sta/Elev= 30
  4217.4  576.83  4298.4  573.93  4318.3  572.17  4432.6  567.61  4485.7  563.69
  4499.7  564.71  4544.4     562  4589.1  561.18  4628.3  559.06    4687  558.19
  4700.9  556.96  4788.6  553.82    4843  552.36  4902.2   550.1  4983.1  548.87
  4983.6  548.37    4989  548.87  5118.2  549.44  5167.9  549.91  5212.2  551.54
  5277.2  552.72  5360.5  555.93  5419.3   559.1  5454.2   559.6  5624.8  567.56
  5650.1  568.79  5664.8  570.09    5675  569.55  5691.2  571.98  5715.9  572.81
#Mann= 10 ,-1 , 0
  4217.4     .05       0  4318.3     .07       0  4788.6    .035       0
    4843     .05       0  4983.1     .05       0    4989     .05       0
  5118.2    .035       0  5277.2     .05       0  5624.8    .035       0
  5650.1    .063       0
Bank Sta=4983.1,4989
XS Rating Curve= 0 ,0
Exp/Cntr=0.3,0.1

Type RM Length L Ch R = 1 ,7685    ,518,518,518
BEGIN DESCRIPTION:
COTTONWOOD TRIBUTARY 1 2 16.0
END DESCRIPTION:
XS GIS Cut Line= 3
      2302024.99       13716925.      2302422.02      13717206.3
        2303225.       13716825.
#Sta/Elev= 30
  4510.6  561.76  4583.4  559.42  4610.3   558.8  4654.6  557.07  4675.5  556.78
  4746.9  554.59  4898.2  548.86  4990.5  546.86  5037.2  547.15    5057  546.71
  5057.4  546.21  5062.4  546.21  5062.9  546.71  5066.9  547.23  5111.2  547.02
  5122.3  547.51    5219  547.58  5264.5  548.33  5309.9  550.43  5480.1  553.43
  5497.3   554.2  5587.2  556.35  5616.4  557.52  5631.5  557.46  5663.2  558.64
  5752.8  561.48  5775.4  562.49  5826.5  565.66  5839.6  565.92  5886.1  568.17
#Mann= 6 ,-1 , 0
  4510.6    .035       0  4583.4     .05       0    5057     .05       0
  5062.9     .05       0  5663.2    .035       0  5839.6    .063       0
Bank Sta=5057,5062.9
XS Rating Curve= 0 ,0
Exp/Cntr=0.3,0.1

Type RM Length L Ch R = 1 ,7167    ,421,421,421
BEGIN DESCRIPTION:
COTTONWOOD TRIBUTARY 1 2 15.0
END DESCRIPTION:
XS GIS Cut Line= 3
      2301924.99     13717174.99        2302475.       13717675.
      2303174.98     13718424.98
#Sta/Elev= 30
  4257.2  558.59  4865.8  543.11  4950.8  544.79    4994  539.99  4994.5  539.49
  5000.2  539.99  5035.9  540.06  5056.9  543.68  5092.6  546.28  5179.2  544.26
  5440.1  550.83  5474.6  552.23  5495.6  556.48    5503  554.57  5509.8  557.79
  5517.1  555.85    5524  558.29  5531.3  556.98  5538.1  558.84  5551.9  558.64
  5602.1  559.87    5630  556.74  5637.3  559.15  5651.5  559.66  5679.8  557.58
    5715  563.56  5750.7  563.11  5781.4  565.27  5870.8  568.32  6026.4  578.81
#Mann= 8 ,-1 , 0
  4257.2     .05       0  4865.8     .07       0    4994     .05       0
  5000.2     .07       0  5179.2     .05       0  5440.1     .07       0
  5551.9     .05       0  5781.4    .035       0
Bank Sta=4994,5000.2
XS Rating Curve= 0 ,0
Exp/Cntr=0.3,0.1

Type RM Length L Ch R = 1 ,6746    ,467,467,467
BEGIN DESCRIPTION:
COTTONWOOD TRIBUTARY 1 2 14.0
END DESCRIPTION:
XS GIS Cut Line= 3
      2301574.98     13717274.98      2302312.65     13718029.22
      2303075.02     13718575.01
#Sta/Elev= 30
  3938.7   562.8  4101.4  558.17  4143.8  558.05  4334.7   549.2  4429.5  546.29
    4557     544    4660  543.56  4688.3  542.45  4815.6     541    4865  541.25
  4883.2  540.42  4883.7  539.92  4889.4  540.42  4900.5  541.33  5007.5  540.76
  5070.4   542.8  5169.8  543.99  5288.4  546.99  5451.6  554.39  5525.6  556.24
  5600.8  558.72  5630.3  561.65  5680.7  562.22  5754.4  564.59  5802.3  566.64
    5817   567.9  5823.2  569.38  5881.3  572.81    5903  574.33  5931.3  574.68
#Mann= 10 ,-1 , 0
  3938.7     .05       0  4429.5     .07       0    4557     .12       0
  4883.2     .05       0  4889.4     .12       0  5169.8     .05       0
  5288.4     .07       0  5525.6     .05       0  5754.4     .07       0
  5881.3    .035       0
Bank Sta=4883.2,4889.4
XS Rating Curve= 0 ,0
Exp/Cntr=0.3,0.1

Type RM Length L Ch R = 1 ,6279    ,464,464,464
BEGIN DESCRIPTION:
COTTONWOOD TRIBUTARY 1 2 13.0
END DESCRIPTION:
XS GIS Cut Line= 3
      2301575.01     13717375.02        2301925.       13718175.
        2302275.       13718975.
#Sta/Elev= 30
  4122.3  560.82  4165.9  559.57  4230.3  556.38  4235.7  556.83  4282.5  554.28
    4288  554.69  4399.6  550.99  4509.4  547.02  4622.6  544.11  4661.3  543.21
  4757.4  542.18  4875.4  540.74  4919.1  539.19  4928.8  539.63  4973.7   538.2
  4981.1  537.74  4989.5  535.93    4990  535.43  4996.1  535.93  5017.3  538.13
  5033.3  538.11  5062.2  539.98  5108.9  540.36  5205.7  543.78  5224.7  543.47
  5246.5  541.98  5314.6  543.22  5586.1  549.24  5770.5  555.16  5868.7  559.36
#Mann= 9 ,-1 , 0
  4122.3     .05       0  4399.6     .07       0  4622.6    .035       0
  4661.3     .07       0  4757.4     .12       0  4989.5     .05       0
  4996.1     .12       0  5205.7     .07       0  5314.6     .05       0
Bank Sta=4989.5,4996.1
XS Rating Curve= 0 ,0
Exp/Cntr=0.3,0.1

Type RM Length L Ch R = 1 ,5815    ,426,426,426
BEGIN DESCRIPTION:
COTTONWOOD TRIBUTARY 1 2 12.0
END DESCRIPTION:
XS GIS Cut Line= 3
      2301125.02     13718025.02        2301525.       13718375.
      2302275.03     13719175.03
#Sta/Elev= 30
  4468.6  548.82  4501.8  548.12  4588.6  545.76  4617.9  545.64  4794.6  542.39
  4837.3  540.89  4843.9  540.21  4950.2  537.66  4964.5  536.87  5003.5  536.66
  5007.2  534.94  5010.6  534.28  5011.1  533.78    5017  533.78  5017.5  534.28
  5021.3  535.71  5035.5  537.43  5056.5  536.83  5108.3  537.61  5198.1   538.9
  5205.5  539.52  5212.3  539.27  5219.4   539.9  5247.1  540.37  5311.5  541.36
  5403.3  541.88    5566   544.5  5615.8  545.91  5778.4  552.14  6096.7  566.55
#Mann= 7 ,-1 , 0
  4468.6     .05       0  4501.8     .07       0  4617.9     .12       0
  5010.6     .05       0  5017.5     .12       0  5108.3     .07       0
  5247.1     .05       0
Bank Sta=5010.6,5017.5
XS Rating Curve= 0 ,0
Exp/Cntr=0.3,0.1

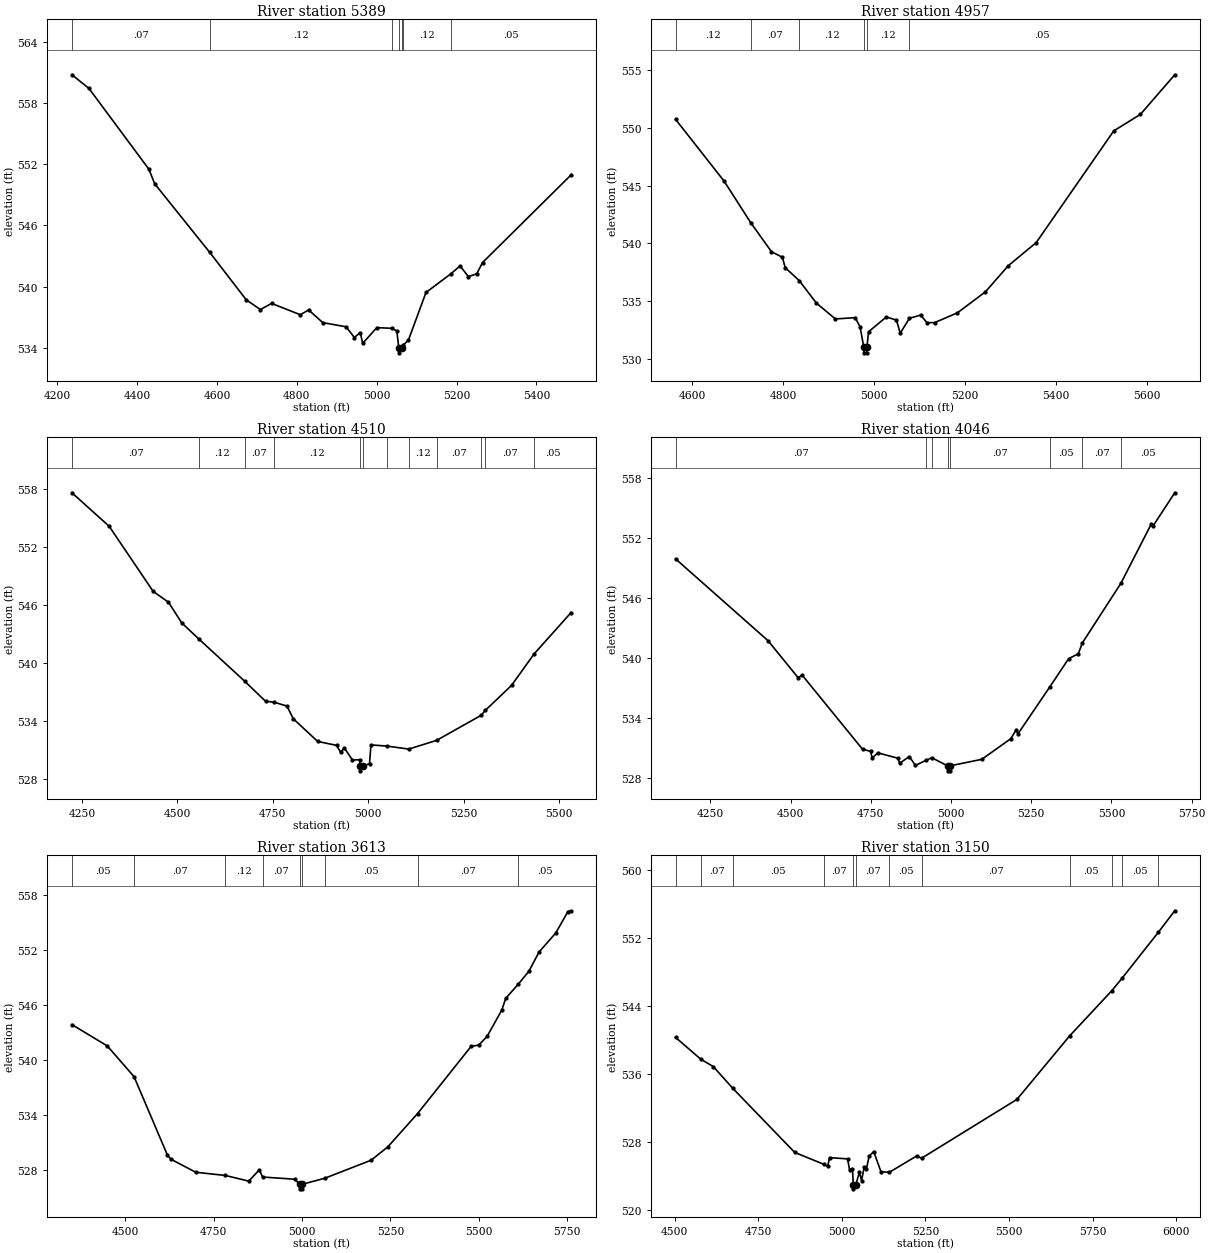
Type RM Length L Ch R = 1 ,5389    ,432,432,432
BEGIN DESCRIPTION:
COTTONWOOD TRIBUTARY 1 2 11.0
END DESCRIPTION:
XS GIS Cut Line= 3
        2300775.     13717975.01        2301225.       13718575.
        2301525.     13718975.01
#Sta/Elev= 30
  4236.9  560.75  4279.6  559.41  4429.6   551.5  4444.2  550.07  4582.1  543.35
  4673.4  538.71  4708.8  537.76  4736.9  538.36  4808.8  537.25  4829.6  537.72
    4865  536.48  4923.4  536.07  4944.2  535.02  4958.8  535.51    4965  534.45
  5000.4  535.99  5038.6  535.92  5050.4  535.66  5055.3  534.02  5055.8  533.52
  5062.3  534.02  5066.2  534.26  5079.6  534.78  5123.4  539.43  5186.1  541.27
  5208.8  542.03  5229.6  540.99  5250.4  541.25    5265  542.36  5486.9  550.95
#Mann= 7 ,-1 , 0
  4236.9     .07       0  4582.1     .12       0  5038.6     .05       0
  5055.3     .05       0  5062.3     .05       0  5066.2     .12       0
  5186.1     .05       0
Bank Sta=5055.3,5062.3
XS Rating Curve= 0 ,0
Exp/Cntr=0.3,0.1

Type RM Length L Ch R = 1 ,4957    ,447,447,447
BEGIN DESCRIPTION:
COTTONWOOD TRIBUTARY 1 2 10.0
END DESCRIPTION:
XS GIS Cut Line= 3
      2300674.98     13718174.95        2300825.       13718575.
      2301125.01     13719175.03
#Sta/Elev= 30
  4563.5  550.73  4670.3  545.39    4729  541.79  4774.5  539.29  4798.5  538.81
  4804.7  537.91  4835.4   536.8  4873.3  534.85  4915.1  533.48  4958.7  533.59
  4969.4   532.8  4977.5  531.05    4978  530.55    4984  530.55  4984.5  531.05
  4988.1  532.37  5027.1  533.65  5049.4  533.38  5057.8  532.25    5078  533.54
  5102.6  533.81  5116.5  533.16  5133.3  533.16  5183.6  534.01  5245.1  535.82
  5295.4  538.08  5356.9  540.08  5527.4  549.73  5586.1  551.16  5661.6  554.58
#Mann= 6 ,-1 , 0
  4563.5     .12       0    4729     .07       0  4835.4     .12       0
  4977.5     .05       0  4984.5     .12       0    5078     .05       0
Bank Sta=4977.5,4984.5
XS Rating Curve= 0 ,0
Exp/Cntr=0.3,0.1

Type RM Length L Ch R = 1 ,4510    ,464,464,464
BEGIN DESCRIPTION:
COTTONWOOD TRIBUTARY 1 2 9.0
END DESCRIPTION:
XS GIS Cut Line= 3
        2300325.       13718075.        2300525.       13718825.
      2300924.99     13719174.99
#Sta/Elev= 30
  4223.8  557.62  4321.5  554.15  4436.6  547.43  4476.7  546.31  4511.6  544.17
  4556.6   542.5  4676.3  538.15  4730.9  536.08  4753.6  535.98  4787.2  535.58
  4803.4  534.28  4867.4  531.93  4917.2  531.52  4927.6  530.81  4937.3  531.26
  4958.6  530.01  4977.4  530.04    4979  529.39  4979.5  528.89  4986.1  529.39
  5003.3  529.63  5007.1  531.57  5048.2  531.45  5106.2  531.14  5179.2  532.04
  5295.5  534.62  5306.8  535.14  5375.4  537.72  5434.3  540.96  5531.5  545.25
#Mann= 12 ,-1 , 0
  4223.8     .07       0  4556.6     .12       0  4676.3     .07       0
  4753.6     .12       0    4979     .05       0  4986.1     .12       0
  5048.2     .07       0  5106.2     .12       0  5179.2     .07       0
  5295.5     .05       0  5306.8     .07       0  5434.3     .05       0
Bank Sta=4979,4986.1
XS Rating Curve= 0 ,0
Exp/Cntr=0.3,0.1

Type RM Length L Ch R = 1 ,4046    ,433,433,433
BEGIN DESCRIPTION:
COTTONWOOD TRIBUTARY 1 2 8.0
END DESCRIPTION:
XS GIS Cut Line= 3
      2299625.05     13718925.02        2300425.       13719225.
      2301124.97       13719275.
#Sta/Elev= 30
  4141.2  549.95  4429.5  541.76    4523  538.07  4536.3   538.3  4724.1   530.9
    4749  530.69  4754.4  530.02  4771.3  530.54  4834.5     530  4839.8   529.5
  4870.1  530.17  4888.8  529.28  4922.4   529.8    4940  530.05  4989.1  529.24
  4989.6  528.74  4996.1  528.74  4996.6  529.24  5095.8  529.89    5186  531.95
  5203.6  532.87  5208.6  532.44  5308.5  537.17  5366.5  539.96  5396.6  540.45
  5409.3  541.54  5529.2  547.49  5624.7  553.47  5629.7  553.24  5697.3  556.56
#Mann= 8 ,-1 , 0
  4141.2     .07       0  4922.4     .12       0    4940     .07       0
  4989.1     .05       0  4996.6     .07       0  5308.5     .05       0
  5409.3     .07       0  5529.2     .05       0
Bank Sta=4989.1,4996.6
XS Rating Curve= 0 ,0
Exp/Cntr=0.3,0.1

Type RM Length L Ch R = 1 ,3613    ,463,463,463
BEGIN DESCRIPTION:
COTTONWOOD TRIBUTARY 1 2 7.0
END DESCRIPTION:
XS GIS Cut Line= 3
      2299775.01       13719625.        2300425.       13719625.
      2301125.03     13719324.99
#Sta/Elev= 30
  4349.6  543.91  4449.6  541.58  4525.2  538.23  4619.6  529.67  4629.6  529.22
  4699.6   527.8  4783.5  527.45  4849.6  526.83  4879.6  528.07  4888.7  527.28
  4979.6  527.04  4993.3  526.49  4993.8  525.99  5000.3  525.99  5000.8  526.49
  5064.2  527.14  5195.4  529.11  5242.6  530.56  5327.1  534.21  5478.3  541.53
  5500.1  541.68  5523.6  542.62  5565.3  545.51  5576.2  546.77  5612.1  548.34
  5641.5  549.72  5670.5  551.83  5717.6   553.9  5752.1  556.24  5761.2  556.33
#Mann= 9 ,-1 , 0
  4349.6     .05       0  4525.2     .07       0  4783.5     .12       0
  4888.7     .07       0  4993.3     .05       0  5000.8     .07       0
  5064.2     .05       0  5327.1     .07       0  5612.1     .05       0
Bank Sta=4993.3,5000.8
XS Rating Curve= 0 ,0
Exp/Cntr=0.3,0.1

Type RM Length L Ch R = 1 ,3150    ,427,427,427
BEGIN DESCRIPTION:
COTTONWOOD TRIBUTARY 1 2 6.0
END DESCRIPTION:
XS GIS Cut Line= 3
        2299875.       13719825.        2300325.       13720025.
      2301124.97     13720624.97
#Sta/Elev= 30
  4503.1  540.29  4578.4  537.72    4616  536.85  4674.1  534.29  4859.4  526.73
  4946.6  525.33  4957.9  525.09  4963.4  526.12  5017.4  525.97  5023.7  524.61
    5032  524.81  5034.5  522.94    5035  522.44  5042.1  522.94  5052.8   524.4
  5059.1  523.42  5067.4  525.05  5073.7  524.79    5082   526.3  5095.5  526.83
  5117.4  524.44  5142.6   524.4  5223.7  526.31  5238.7  526.05  5523.7  532.98
  5681.6  540.48  5807.8  545.81  5838.4  547.28  5946.1  552.66  5995.5  555.21
#Mann= 12 ,-1 , 0
  4503.1     .05       0  4578.4     .07       0  4674.1     .05       0
  4946.6     .07       0  5034.5     .05       0  5042.1     .07       0
  5142.6     .05       0  5238.7     .07       0  5681.6     .05       0
  5807.8     .07       0  5838.4     .05       0  5946.1     .07       0
Bank Sta=5034.5,5042.1
XS Rating Curve= 0 ,0
Exp/Cntr=0.3,0.1

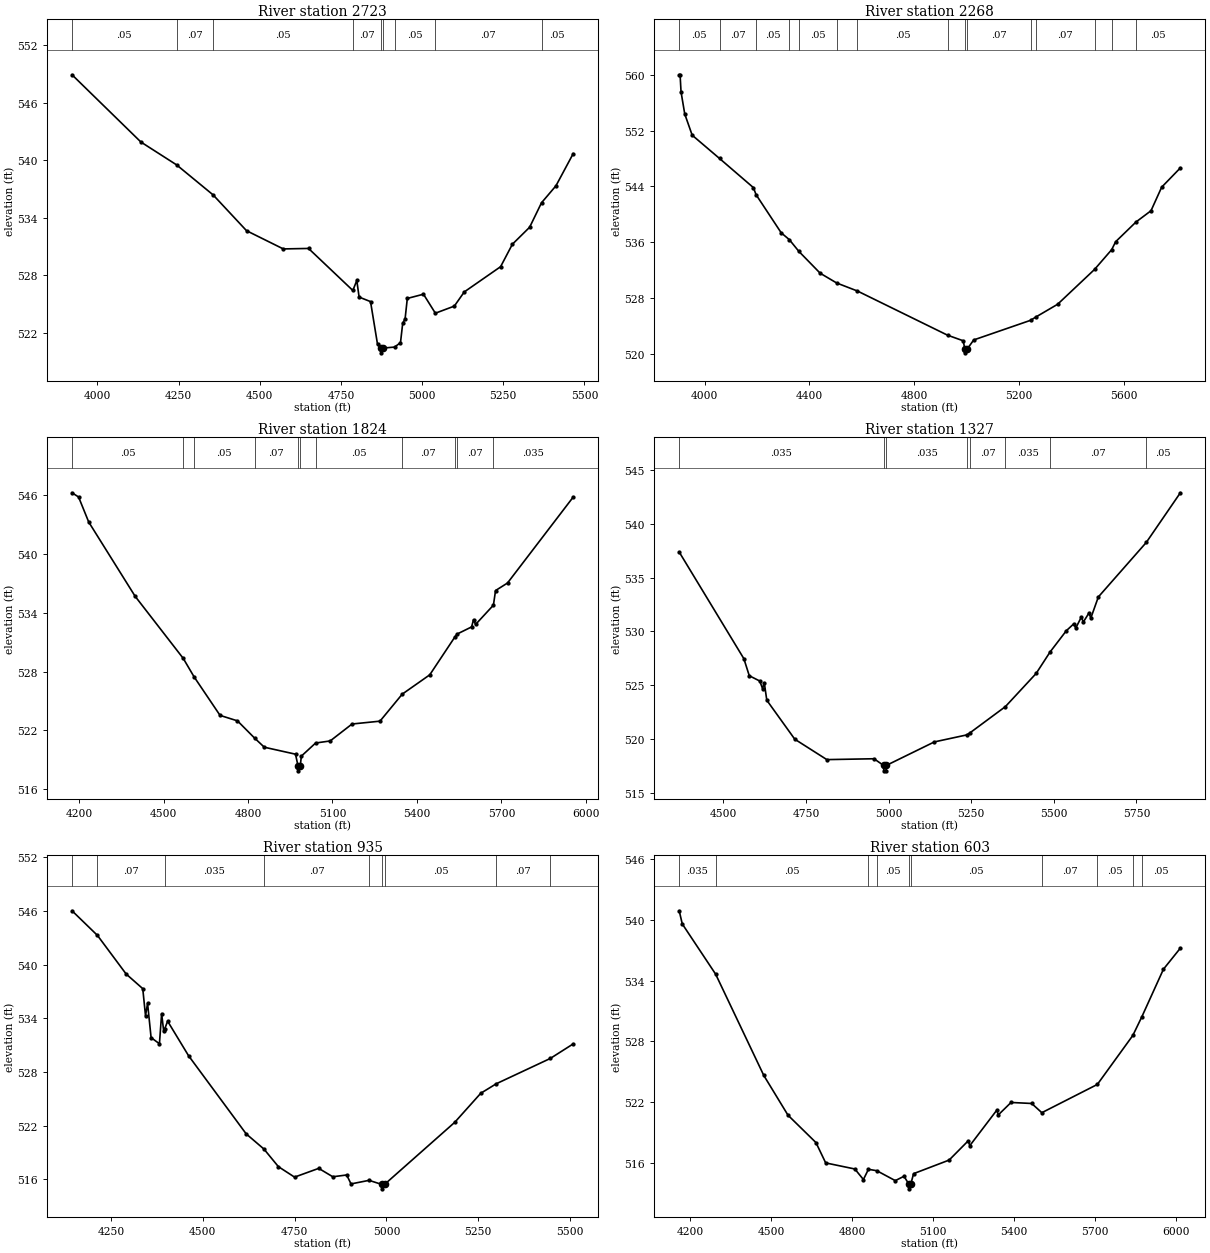
Type RM Length L Ch R = 1 ,2723    ,455,455,455
BEGIN DESCRIPTION:
COTTONWOOD TRIBUTARY 1 2 5.0
END DESCRIPTION:
XS GIS Cut Line= 3
      2299575.03     13719675.03        2300375.       13720425.
      2300775.04     13720625.02
#Sta/Elev= 30
  3921.7   548.9  4133.9  541.89  4243.8  539.51  4356.3  536.38  4459.2  532.65
  4572.5  530.75  4650.2   530.8  4786.7  526.42  4798.9  527.46    4806  525.73
  4841.2  525.26  4862.7  520.82  4872.9  520.42  4873.4  519.92  4880.7  520.42
  4915.2  520.52  4933.5  520.98  4940.3     523  4947.7  523.47  4954.5  525.59
  5004.3  526.03  5040.9  524.05  5099.3  524.79    5130  526.27  5241.9   528.9
  5278.2  531.24  5331.3  533.01  5367.9  535.56  5412.4  537.33  5465.5  540.68
#Mann= 9 ,-1 , 0
  3921.7     .05       0  4243.8     .07       0  4356.3     .05       0
  4786.7     .07       0  4872.9     .05       0  4880.7     .07       0
  4915.2     .05       0  5040.9     .07       0  5367.9     .05       0
Bank Sta=4872.9,4880.7
XS Rating Curve= 0 ,0
Exp/Cntr=0.3,0.1

Type RM Length L Ch R = 1 ,2268    ,444,444,444
BEGIN DESCRIPTION:
COTTONWOOD TRIBUTARY 1 2 4.0
END DESCRIPTION:
XS GIS Cut Line= 3
      2299275.03     13719875.03        2300075.       13720625.
      2300875.01       13720775.
#Sta/Elev= 30
  3903.5  559.99  3906.9  559.99  3910.5  557.54  3924.7  554.36    3953  551.33
  4057.3  547.99  4186.5  543.81  4196.4  542.81  4292.5  537.33  4323.2  536.36
  4359.8  534.67    4441  531.54    4504  530.14  4583.1  528.99  4926.5  522.66
  4986.1  521.86  4992.7  520.63  4993.2  520.13  5000.5  520.63  5026.3  521.98
  5242.8  524.79  5262.9  525.26    5346  527.09  5486.7  532.08  5552.2  534.92
  5567.3  536.06    5645  538.89  5702.1   540.5  5742.8  543.88    5814  546.64
#Mann= 15 ,-1 , 0
  3903.5     .05       0  4057.3     .07       0  4196.4     .05       0
  4323.2     .07       0  4359.8     .05       0    4504     .07       0
  4583.1     .05       0  4926.5     .07       0  4992.7     .05       0
  5000.5     .07       0  5242.8     .05       0  5262.9     .07       0
  5486.7     .05       0  5552.2     .07       0    5645     .05       0
Bank Sta=4992.7,5000.5
XS Rating Curve= 0 ,0
Exp/Cntr=0.3,0.1

Type RM Length L Ch R = 1 ,1824    ,497,497,497
BEGIN DESCRIPTION:
COTTONWOOD TRIBUTARY 1 2 3.0
END DESCRIPTION:
XS GIS Cut Line= 3
      2299024.95     13720774.99        2299825.       13720975.
      2300474.99     13721674.99
#Sta/Elev= 30
  4175.1  546.26  4198.3  545.83  4234.4  543.27  4399.3  535.69  4570.2  529.35
  4608.2  527.49  4700.8  523.54  4762.7  522.98  4823.2  521.23    4858  520.29
  4968.8  519.58  4977.7  518.38  4978.2  517.88  4985.7  518.38  4989.5  519.38
  5040.2  520.72  5091.9  520.93  5169.6  522.66  5268.8  522.95  5347.9  525.71
  5445.6  527.68  5533.6  531.49  5542.6  531.84  5594.2  532.57    5601  533.31
  5608.3  532.82  5671.7  534.79  5679.2  536.28  5721.7  537.05    5955  545.82
#Mann= 11 ,-1 , 0
  4175.1     .05       0  4570.2    .035       0  4608.2     .05       0
  4823.2     .07       0  4977.7     .05       0  4985.7     .07       0
  5040.2     .05       0  5347.9     .07       0  5533.6     .05       0
  5542.6     .07       0  5671.7    .035       0
Bank Sta=4977.7,4985.7
XS Rating Curve= 0 ,0
Exp/Cntr=0.3,0.1

Type RM Length L Ch R = 1 ,1327    ,392,392,392
BEGIN DESCRIPTION:
COTTONWOOD TRIBUTARY 1 2 2.0
END DESCRIPTION:
XS GIS Cut Line= 3
      2299175.01     13720925.02      2299276.19     13721211.51
        2300375.       13721725.
#Sta/Elev= 30
  4366.2  537.36  4561.9  527.48  4578.3   525.9  4610.1  525.41  4618.4  524.71
  4623.7  525.25  4631.3  523.63    4716  520.02    4813  518.13  4955.7  518.21
  4984.8  517.59  4985.3  517.09  4992.4  517.09  4992.9  517.59  5138.4  519.77
  5236.7  520.42  5246.2  520.61  5353.4  523.04  5446.4  526.11  5488.6   528.1
  5537.8  530.07  5560.7  530.72  5566.2  530.31  5583.5  531.35    5589  530.86
  5606.4  531.72  5611.9  531.24  5634.7   533.2  5779.8  538.25  5882.9  542.85
#Mann= 8 ,-1 , 0
  4366.2    .035       0  4984.8    .035       0  4992.9    .035       0
  5236.7     .05       0  5246.2     .07       0  5353.4    .035       0
  5488.6     .07       0  5779.8     .05       0
Bank Sta=4984.8,4992.9
XS Rating Curve= 0 ,0
Exp/Cntr=0.3,0.1

Type RM Length L Ch R = 1 ,935     ,332,332,332
BEGIN DESCRIPTION:
COTTONWOOD TRIBUTARY 1 2 1.0
END DESCRIPTION:
XS GIS Cut Line= 3
      2298925.01     13720875.02        2299325.       13721625.
      2299775.04     13721875.02
#Sta/Elev= 30
  4143.9  546.02    4213  543.27  4291.2  538.95  4336.5  537.31    4344  534.28
  4349.6  535.66  4359.2  531.83  4381.9  531.15  4387.9  534.52  4393.6  532.52
  4396.4  532.82  4404.2  533.67  4461.2  529.81  4618.1  521.07  4666.5  519.37
  4705.9   517.4  4749.9  516.23  4815.7  517.21    4854  516.27  4891.9  516.47
  4903.6  515.47  4952.8  515.87    4987  515.42  4987.5  514.92  4995.1  515.42
  5186.1  522.36    5257  525.61  5299.1  526.67  5446.2   529.5  5508.7  531.13
#Mann= 9 ,-1 , 0
  4143.9     .05       0    4213     .07       0  4396.4    .035       0
  4666.5     .07       0  4952.8     .05       0    4987     .05       0
  4995.1     .05       0  5299.1     .07       0  5446.2     .05       0
Bank Sta=4987,4995.1
XS Rating Curve= 0 ,0
Exp/Cntr=0.3,0.1

Type RM Length L Ch R = 1 ,603     ,410,410,410
BEGIN DESCRIPTION:
X18666
END DESCRIPTION:
XS GIS Cut Line= 3
      2298765.78     13721039.65      2299114.73     13721935.47
      2299937.61     13722284.41
#Sta/Elev= 30
  4160.4   540.9  4171.8   539.6  4295.3  534.64  4473.5  524.64  4563.2  520.71
  4666.6  518.01  4702.7     516  4810.6   515.4  4842.3  514.36  4860.9  515.37
  4891.9  515.23  4960.3  514.25  4992.5  514.68  5009.9  513.94  5010.4  513.44
    5018  513.94  5028.1  514.94  5159.6  516.28  5230.6  518.19    5236   517.7
  5336.1  521.21  5341.5  520.74  5388.9  521.97  5465.3  521.87  5502.8  520.96
  5708.3  523.75  5839.7  528.59  5873.2  530.44    5953  535.13  6015.6  537.21
#Mann= 10 ,-1 , 0
  4160.4    .035       0  4295.3     .05       0  4860.9     .07       0
  4891.9     .05       0  5009.9     .05       0    5018     .05       0
  5502.8     .07       0  5708.3     .05       0  5839.7     .07       0
  5873.2     .05       0
Bank Sta=5009.9,5018
XS Rating Curve= 0 ,0
Exp/Cntr=0.3,0.1

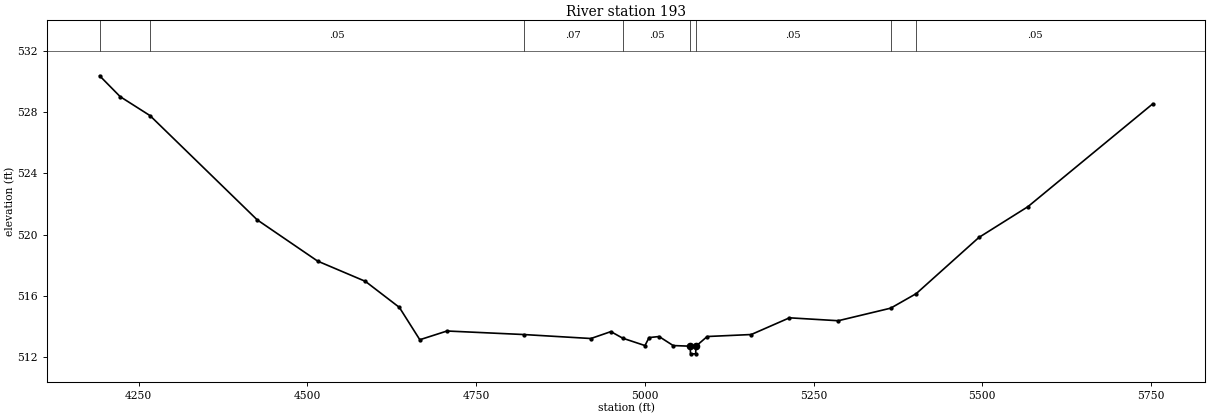
Type RM Length L Ch R = 1 ,193     ,0,0,0
BEGIN DESCRIPTION:
X18665
END DESCRIPTION:
XS GIS Cut Line= 3
      2298609.52     13721294.83      2298698.07      13721956.3
      2299213.67     13722685.44
#Sta/Elev= 30
  4192.2  530.37  4222.6  529.01  4266.9  527.77  4425.7  520.97  4515.2  518.28
  4585.9  516.96  4636.3  515.26  4666.6  513.15  4706.9  513.72  4820.3  513.49
  4920.1  513.23  4949.7  513.68  4967.3  513.25  5000.2  512.77  5006.3  513.29
  5021.1  513.36    5042  512.77  5067.2  512.73  5067.7  512.23  5075.3  512.23
  5075.8  512.73  5092.4  513.36  5157.7  513.49  5214.3  514.58  5286.6  514.39
  5364.3  515.21  5402.2  516.16  5494.9  519.82  5567.6  521.83  5752.6  528.54
#Mann= 8 ,-1 , 0
  4192.2     .07       0  4266.9     .05       0  4820.3     .07       0
  4967.3     .05       0  5067.2     .05       0  5075.8     .05       0
  5364.3    .035       0  5402.2     .05       0
Bank Sta=5067.2,5075.8
XS Rating Curve= 0 ,0
Exp/Cntr=0.3,0.1

Chan Stop Cuts=-1
Use User Specified Reach Order=0
Composite Channel Slope=5