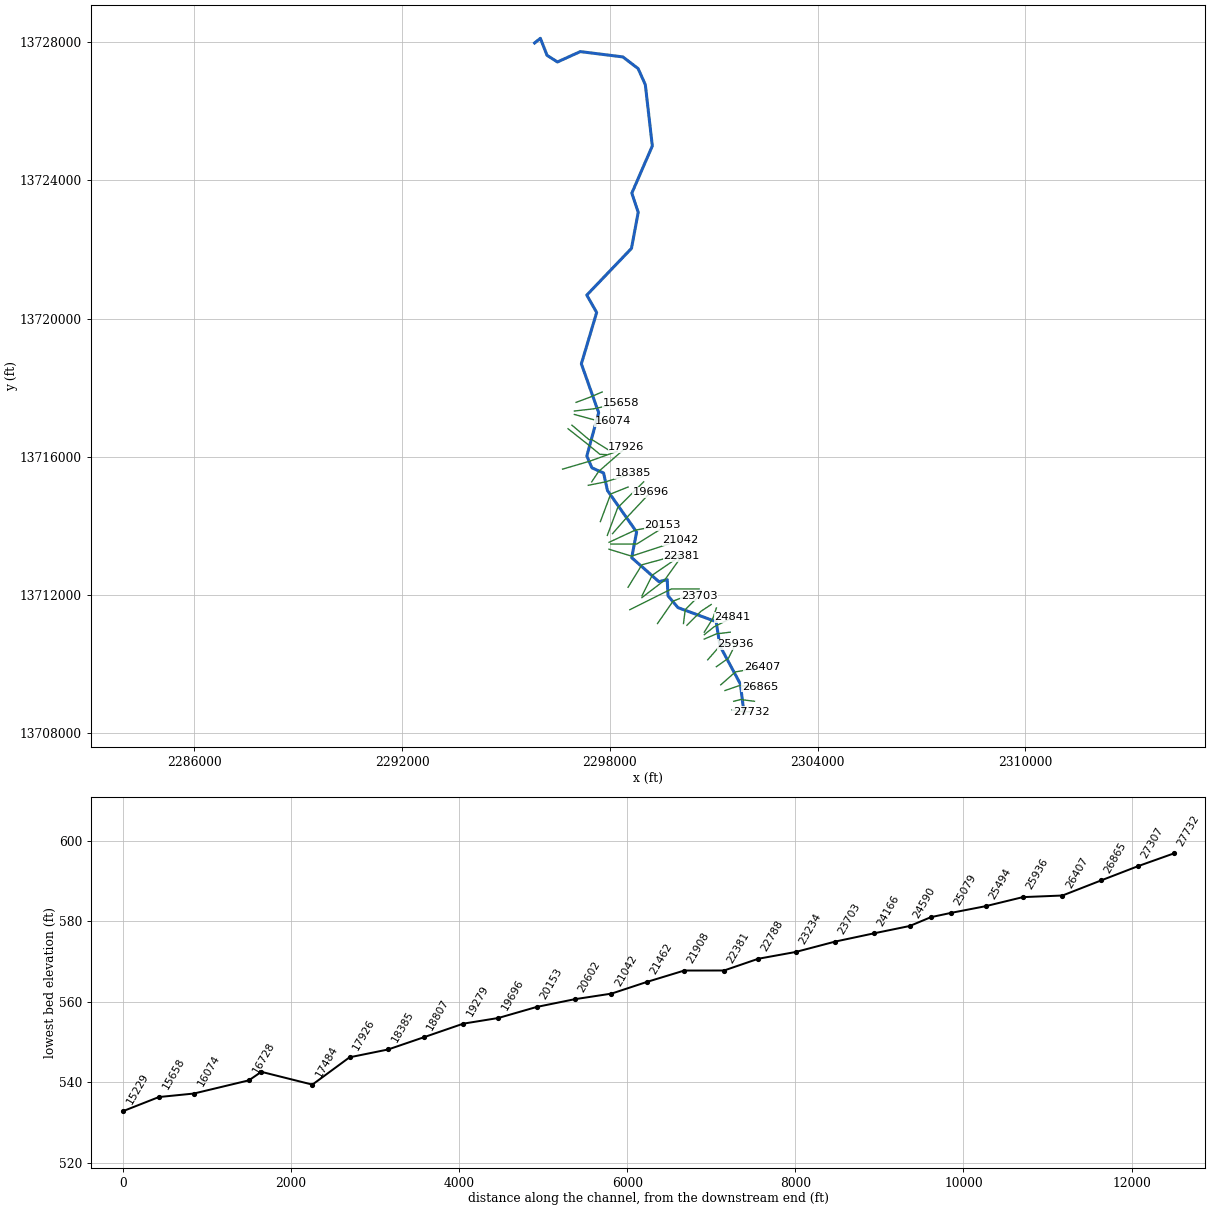
--- COTTONWOOD TRIBUTARY 1.prj (project) ---

Proj Title=COTTONWOOD TRIBUTARY 1 Base Level Engineering
Current Plan=p01
Default Exp/Contr=0.3,0.1
English Units
Geom File=g01
Flow File=f01
Plan File=p01
Y Axis Title=Elevation
X Axis Title(PF)=Main Channel Distance
X Axis Title(XS)=Station
BEGIN DESCRIPTION:
COTTONWOOD TRIBUTARY 1
END DESCRIPTION:
DSS Export Rating Curves= 0
DSS Export Rating Curve Sorted= 0
DSS Export Volume Flow Curves= 0
DXF OffsetX= 0
DXF OffsetY= 0
DXF ScaleX= 1
DXF ScaleY= 10

--- COTTONWOOD TRIBUTARY 1.p01 (plan) ---

Plan Title=Multiple Run
Short Identifier=Multiple
Geom File=g01
Flow File=f01
Subcritical Flow
K Sum by GR= 0
Std Step Tol= 0.01
Critical Tol= 0.01
Num of Std Step Trials= 20
Max Error Tol= 0.3
Flow Tol Ratio= 0.001
Split Flow NTrial= 30
Split Flow Tol= 0.02
Split Flow Ratio= 0.02
Log Output Level= 0
Friction Slope Method= 1
Unsteady Friction Slope Method= 2
Unsteady Bridges Friction Slope Method= 1
Parabolic Critical Depth
Global Vel Dist=  1 , 1 , 1
Global Log Level= 0
CheckData=True
Encroach Param= -1, 0, 0, 0
BEGIN DESCRIPTION:
Multiple Run
END DESCRIPTION:

--- COTTONWOOD TRIBUTARY 1.f01 (steady flow) ---

Flow Title=Multiple
Number of Profiles=7
Profile Names=10-year,25-year,50-year,1pct_min,100-year,1pct_plu,500-year
River Rch & RM= COTTONWOOD TRIBU,Reach-1,27732
     903    1515    2090    1396    2786    5559    4910
River Rch & RM= COTTONWOOD TRIBU,Reach-1,25936
    1096    1838    2535    1689    3371    6726    5915
River Rch & RM= COTTONWOOD TRIBU,Reach-1,18807
    1377    2329    3227    2160    4310    8600    7629
River Rch & RM= COTTONWOOD TRIBU,Reach-1,10209
    1480    2502    3466    2319    4626    9230    8175
River Rch & RM= COTTONWOOD TRIBU,Reach-1,9347
    2526    4363    6133    4156    8292   16545   15040
River Rch & RM= COTTONWOOD TRIBU,Reach-1,1919
    2551    4401    6182    4185    8351   16663   15120
Boundary for River Rch & Prof#=COTTONWOOD TRIBU,Reach-1,1
Up Type=0
Dn Type=3
Dn Slope=0.005
Boundary for River Rch & Prof#=COTTONWOOD TRIBU,Reach-1,2
Up Type=0
Dn Type=3
Dn Slope=0.005
Boundary for River Rch & Prof#=COTTONWOOD TRIBU,Reach-1,3
Up Type=0
Dn Type=3
Dn Slope=0.005
Boundary for River Rch & Prof#=COTTONWOOD TRIBU,Reach-1,4
Up Type=0
Dn Type=3
Dn Slope=0.005
Boundary for River Rch & Prof#=COTTONWOOD TRIBU,Reach-1,5
Up Type=0
Dn Type=3
Dn Slope=0.005
Boundary for River Rch & Prof#=COTTONWOOD TRIBU,Reach-1,6
Up Type=0
Dn Type=3
Dn Slope=0.005
Boundary for River Rch & Prof#=COTTONWOOD TRIBU,Reach-1,7
Up Type=0
Dn Type=3
Dn Slope=0.005

--- COTTONWOOD TRIBUTARY 1.g01 (geometry) ---

Geom Title=Existing Conditions
Program Version=4.10

River Reach=COTTONWOOD TRIBU,Reach-1
Reach XY= 30
        2301875.       13708575.      2301766.72     13709428.22
      2301178.37     13710526.74      2301069.54     13711227.45
      2299965.32     13711635.76      2299678.46      13711976.5
      2299655.23     13712446.03      2299414.92     13712386.09
      2298629.74     13713080.62      2298771.52     13713823.73
      2297930.46     13715022.34      2297817.18     13715531.82
      2297480.26     13715680.47      2297332.78      13716021.6
      2297675.88       13717275.      2297175.38     13718690.27
      2297617.72     13720174.91      2297332.58     13720678.35
      2298622.94     13722030.46      2298817.44       13723075.
      2298633.02     13723628.35      2299225.04     13724994.98
      2299022.76     13726769.07      2298814.48     13727234.79
      2298373.45     13727571.25      2297145.05     13727725.21
      2296485.48     13727425.93      2296185.61     13727614.94
      2295992.13       13728109.        2295825.       13727975.

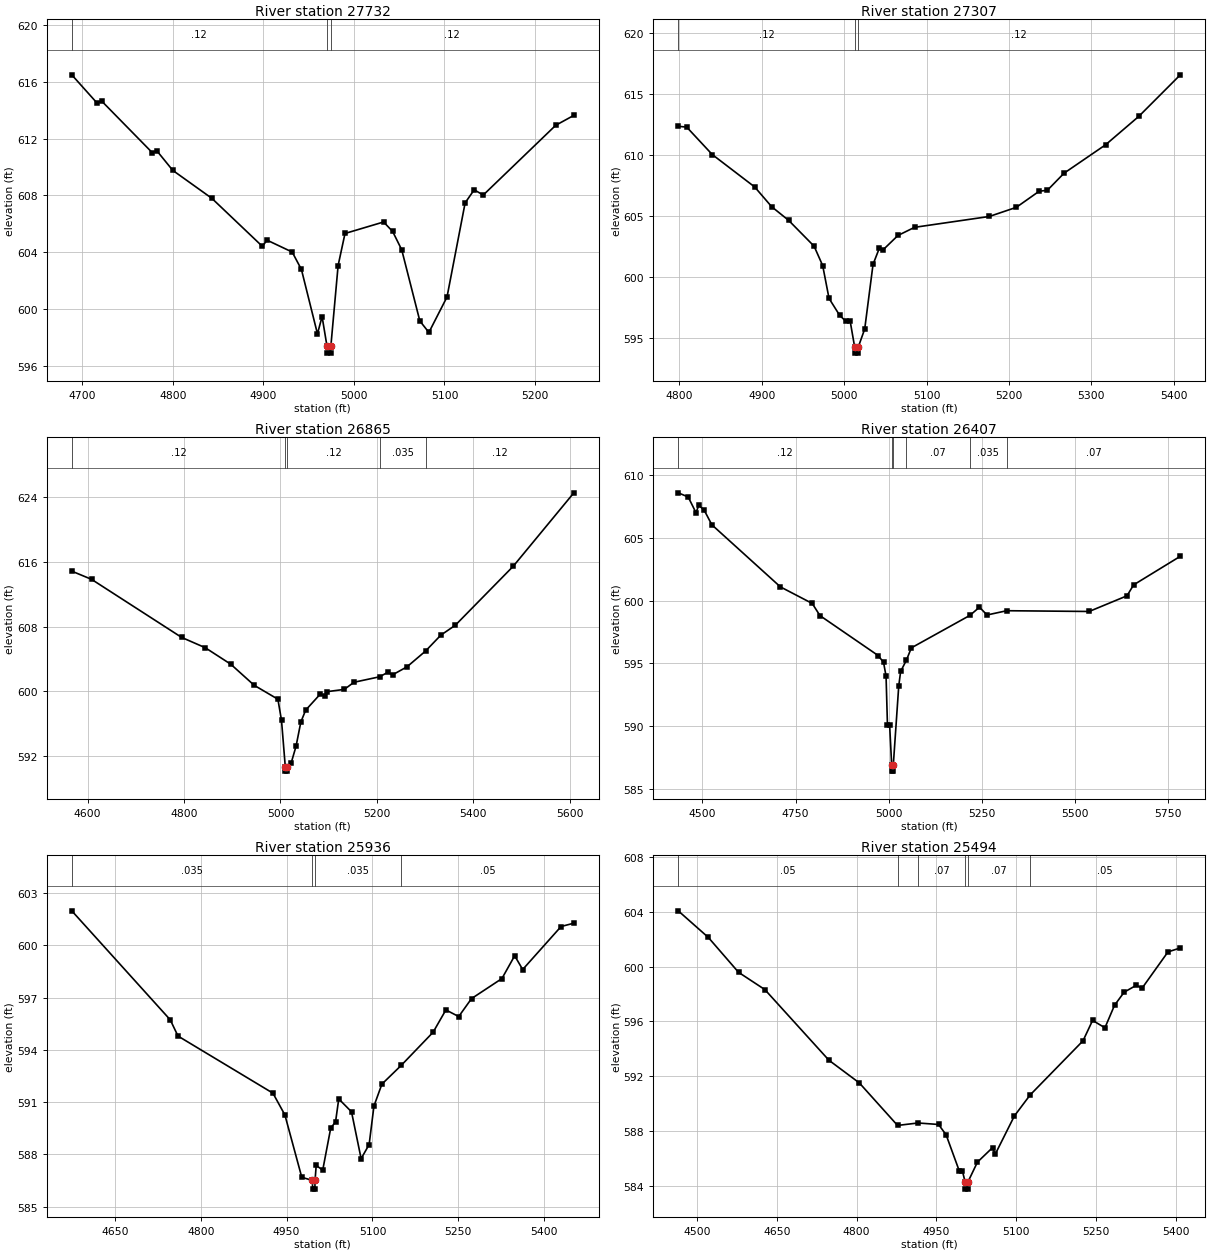
Type RM Length L Ch R = 1 ,27732   ,425,425,425
BEGIN DESCRIPTION:
COTTONWOOD TRIBUTARY 1 59.0
END DESCRIPTION:
XS GIS Cut Line= 3
      2301524.98       13708675.        2301825.       13708625.
      2302075.04       13708625.
#Sta/Elev= 30
  4688.6  616.51  4716.5  614.52  4721.6  614.66  4777.3  611.03  4782.4  611.16
  4800.1  609.77  4843.2   607.8    4899  604.41  4904.1  604.85  4931.9  604.01
  4942.1  602.78  4959.8  598.24  4964.9  599.46  4970.3  597.38  4970.6  596.88
  4974.4  596.88  4974.6  597.38  4982.6  603.06  4990.2  605.32  5032.8  606.13
  5042.8  605.46  5052.8  604.17  5072.8  599.15  5082.8  598.34  5102.8  600.84
  5122.8  607.48  5132.8   608.4  5142.8  608.03  5222.8  612.95  5242.8  613.65
#Mann= 3 ,-1 , 0
  4688.6     .12       0  4970.3     .05       0  4974.6     .12       0
Bank Sta=4970.3,4974.6
XS Rating Curve= 0 ,0
Exp/Cntr=0.3,0.1

Type RM Length L Ch R = 1 ,27307   ,442,442,442
BEGIN DESCRIPTION:
COTTONWOOD TRIBUTARY 1 58.0
END DESCRIPTION:
XS GIS Cut Line= 3
      2301574.98     13708924.99        2301775.       13708975.
      2302175.01       13708925.
#Sta/Elev= 30
  4798.6  612.33  4808.9  612.26  4839.9  610.01  4891.4  607.35    4912  605.73
  4932.6  604.61  4963.5  602.49  4973.9   600.9  4981.6  598.21  4994.5  596.82
  5002.2  596.32  5007.3  596.32  5012.7  594.22    5013  593.72  5016.8  593.72
  5017.1  594.22  5024.9   595.7    5035     601  5042.6  602.32  5047.6  602.22
  5065.2  603.37  5085.4  604.04  5176.1  604.93  5208.9  605.68  5236.6     607
  5246.6  607.08  5266.8  608.48  5317.2  610.81  5357.5  613.14  5407.9  616.55
#Mann= 3 ,-1 , 0
  4798.6     .12       0  5012.7     .05       0  5017.1     .12       0
Bank Sta=5012.7,5017.1
XS Rating Curve= 0 ,0
Exp/Cntr=0.3,0.1

Type RM Length L Ch R = 1 ,26865   ,458,458,458
BEGIN DESCRIPTION:
COTTONWOOD TRIBUTARY 1 57.0
END DESCRIPTION:
XS GIS Cut Line= 3
      2301323.53     13709235.78        2301725.       13709375.
      2302340.48     13709345.78
#Sta/Elev= 30
  4567.2  614.84  4608.2  613.83    4795  606.66  4843.9  605.39  4896.9  603.35
  4945.4  600.75  4994.6  599.03  5002.1  596.42    5010  590.65  5010.3  590.15
  5014.1  590.15  5014.4  590.65  5022.2  591.17  5032.2  593.21  5042.2  596.21
  5052.2  597.68  5082.2  599.64  5092.2  599.45  5097.4  599.97  5132.3  600.24
  5152.3  601.12  5205.7   601.8  5222.4  602.35  5232.4  602.04  5262.4  603.03
  5300.7  604.97  5332.5  606.94  5362.5  608.16  5482.7  615.45  5608.3  624.51
#Mann= 5 ,-1 , 0
  4567.2     .12       0    5010     .05       0  5014.4     .12       0
  5205.7    .035       0  5300.7     .12       0
Bank Sta=5010,5014.4
XS Rating Curve= 0 ,0
Exp/Cntr=0.3,0.1

Type RM Length L Ch R = 1 ,26407   ,471,471,471
BEGIN DESCRIPTION:
COTTONWOOD TRIBUTARY 1 56.0
END DESCRIPTION:
XS GIS Cut Line= 3
      2301201.73     13709400.74        2301625.       13709775.
      2302395.92     13709911.41
#Sta/Elev= 30
    4435   608.6  4461.7  608.27  4482.6  607.02  4490.2   607.6  4504.4  607.23
  4525.3  606.05  4709.3   601.1  4794.7  599.78  4815.5  598.81    4972  595.62
  4986.2  595.08  4992.9  593.99  4996.7  590.09  5002.5  590.09    5008  586.91
  5008.3  586.41  5012.1  586.41  5012.4  586.91    5027  593.21  5032.1  594.36
  5047.6  595.26  5060.9  596.24  5218.1  598.83  5243.7  599.48    5264  598.86
    5317   599.2  5538.2  599.14  5639.8  600.39  5657.5  601.26  5782.9  603.54
#Mann= 6 ,-1 , 0
    4435     .12       0    5008     .05       0  5012.4     .12       0
  5047.6     .07       0  5218.1    .035       0    5317     .07       0
Bank Sta=5008,5012.4
XS Rating Curve= 0 ,0
Exp/Cntr=0.3,0.1

Type RM Length L Ch R = 1 ,25936   ,442,442,442
BEGIN DESCRIPTION:
COTTONWOOD TRIBUTARY 1 55.0
END DESCRIPTION:
XS GIS Cut Line= 3
      2301074.99     13709924.99        2301425.       13710175.
      2301624.98     13710574.96
#Sta/Elev= 30
  4574.6  601.99  4746.7  595.73  4760.2   594.8  4926.1  591.52    4947  590.27
  4976.5  586.69  4995.1  586.51  4995.4  586.01  4999.4  586.01  4999.7  586.51
  5001.7  587.37  5013.1   587.1  5027.1  589.52  5035.5  589.87  5041.1  591.19
  5063.4  590.45  5080.2  587.76  5094.2  588.57  5102.6  590.78  5116.5  592.04
  5150.1  593.11    5206  595.02  5228.3   596.3  5250.7  595.92  5273.1  596.95
  5326.2   598.1  5348.5  599.41  5362.5  598.62  5429.6  601.09  5451.9  601.28
#Mann= 4 ,-1 , 0
  4574.6    .035       0  4995.1    .035       0  4999.7    .035       0
  5150.1     .05       0
Bank Sta=4995.1,4999.7
XS Rating Curve= 0 ,0
Exp/Cntr=0.3,0.1

Type RM Length L Ch R = 1 ,25494   ,415,415,415
BEGIN DESCRIPTION:
COTTONWOOD TRIBUTARY 1 54.0
END DESCRIPTION:
XS GIS Cut Line= 3
        2300825.       13710125.        2301175.       13710525.
      2301574.98       13710625.
#Sta/Elev= 30
  4464.6  604.08  4521.1  602.14    4578  599.59  4627.4  598.33  4747.9  593.17
  4804.9  591.52  4876.9  588.41  4915.4  588.59  4953.9  588.48  4968.1  587.73
  4992.8   585.1  4998.7   585.1    5004  584.26  5004.4  583.76  5008.5  583.76
  5008.9  584.26    5027  585.73  5055.4  586.79  5060.5  586.31  5096.6  589.11
  5126.2  590.64  5225.5  594.59  5243.5  596.08  5266.7  595.54  5284.7  597.18
  5302.8  598.14    5326  598.65  5336.3  598.42  5385.2  601.08  5408.4  601.37
#Mann= 6 ,-1 , 0
  4464.6     .05       0  4876.9    .035       0  4915.4     .07       0
    5004     .05       0  5008.9     .07       0  5126.2     .05       0
Bank Sta=5004,5008.9
XS Rating Curve= 0 ,0
Exp/Cntr=0.3,0.1

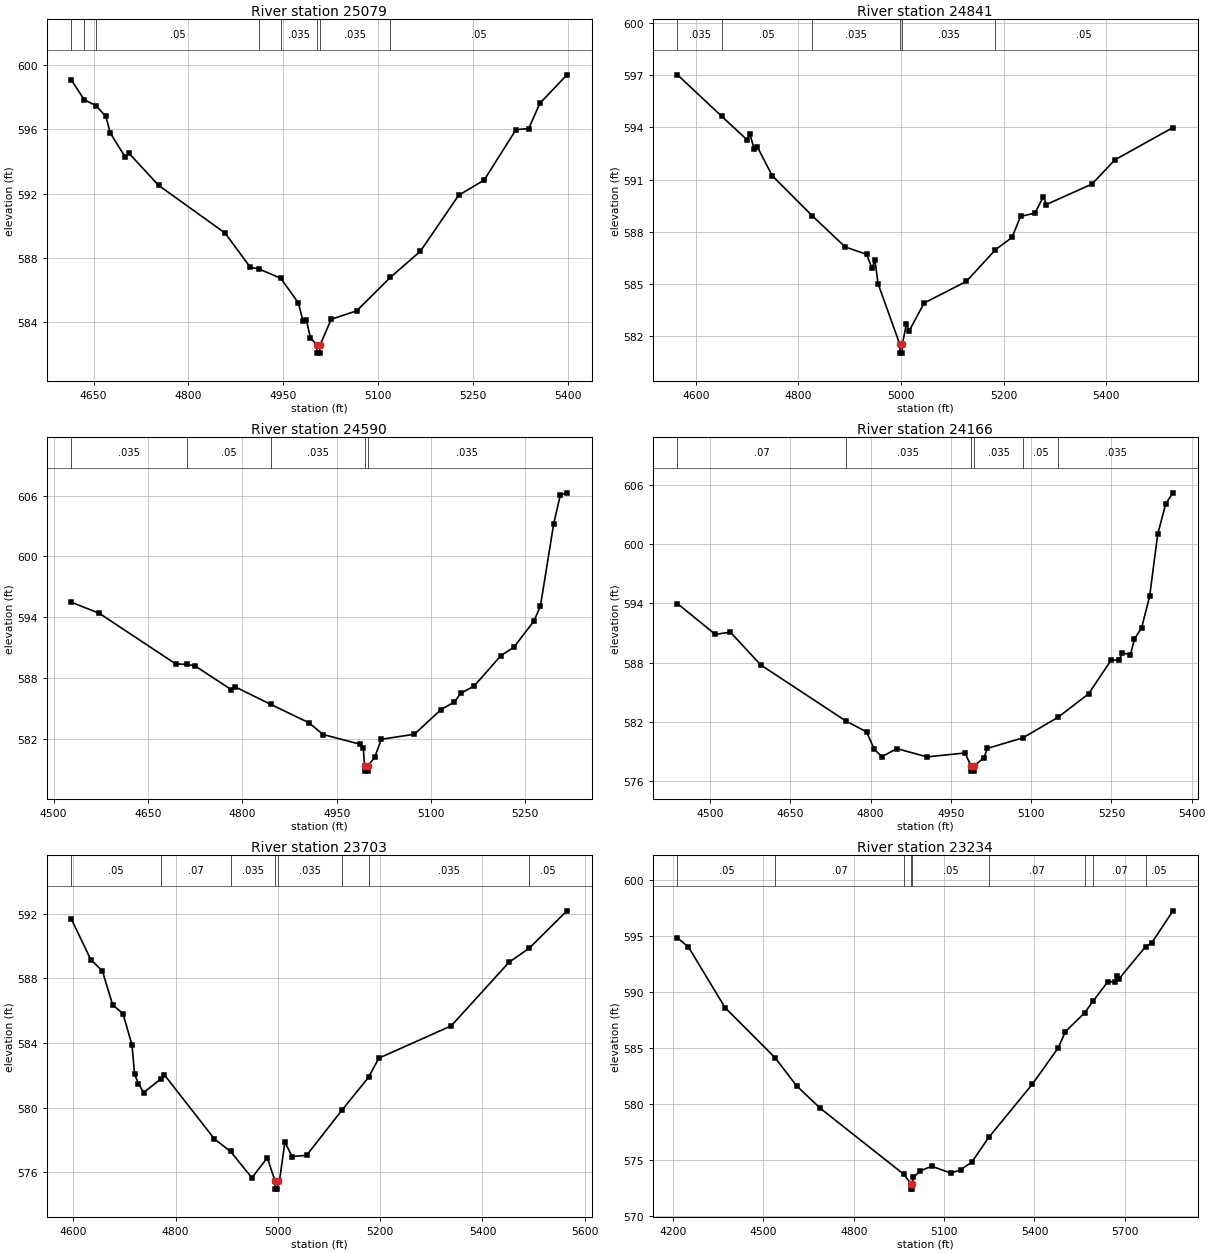
Type RM Length L Ch R = 1 ,25079   ,238,238,238
BEGIN DESCRIPTION:
COTTONWOOD TRIBUTARY 1 53.0
END DESCRIPTION:
XS GIS Cut Line= 3
      2300725.02     13710725.01        2301075.       13710875.
      2301475.02       13710925.
#Sta/Elev= 30
  4614.9  599.06    4635  597.85  4654.1  597.46  4669.3   596.8  4676.5  595.76
  4700.1  594.27  4705.5  594.53  4752.7  592.52  4857.9  589.55  4897.8  587.42
  4911.3  587.32  4945.9  586.74  4973.9  585.21  4981.2  584.08  4986.6  584.13
    4993  583.03  5003.3  582.58  5003.6  582.08  5007.8  582.08  5008.2  582.58
  5025.9  584.19  5066.2  584.71  5119.4  586.79    5167  588.42  5227.5   591.9
  5267.8  592.84  5318.2  595.98  5338.3  596.05    5356  597.62  5398.8  599.39
#Mann= 8 ,-1 , 0
  4614.9     .05       0    4635    .035       0  4654.1     .05       0
  4911.3     .12       0  4945.9    .035       0  5003.3    .035       0
  5008.2    .035       0  5119.4     .05       0
Bank Sta=5003.3,5008.2
XS Rating Curve= 0 ,0
Exp/Cntr=0.3,0.1

Type RM Length L Ch R = 1 ,24841   ,251,251,251
BEGIN DESCRIPTION:
X18664
END DESCRIPTION:
XS GIS Cut Line= 3
      2300726.46     13710854.16      2301005.35     13711078.06
      2301547.45     13711353.04
#Sta/Elev= 30
  4564.2  597.02  4650.3  594.64  4699.1   593.3  4705.6  593.59  4713.5  592.76
    4720  592.87  4748.8  591.22    4827  588.91  4891.2  587.12  4932.7   586.7
  4943.3   585.9  4948.9  586.36  4955.1  585.01  4997.5  581.52  4997.8  581.02
    5002  581.02  5002.4  581.52  5010.1  582.68  5015.7   582.3  5044.8   583.9
    5127  585.14  5183.7  586.96    5216  587.67  5232.7  588.88  5260.6  589.07
  5277.2  590.01  5282.8  589.56  5371.9  590.74  5416.4  592.13  5529.7  593.99
#Mann= 6 ,-1 , 0
  4564.2    .035       0  4650.3     .05       0    4827    .035       0
  4997.5    .035       0  5002.4    .035       0  5183.7     .05       0
Bank Sta=4997.5,5002.4
XS Rating Curve= 0 ,0
Exp/Cntr=0.3,0.1

Type RM Length L Ch R = 1 ,24590   ,424,424,424
BEGIN DESCRIPTION:
COTTONWOOD TRIBUTARY 1 52.0
END DESCRIPTION:
XS GIS Cut Line= 3
      2300725.02     13710925.03        2300975.       13711325.
        2301075.     13711625.01
#Sta/Elev= 30
  4528.3  595.48  4572.5   594.4  4693.9  589.41  4711.5  589.36  4724.6  589.22
  4782.4  586.87  4788.3  587.15  4845.3  585.41  4905.6  583.61  4928.6  582.44
  4986.4   581.5  4992.3  581.13  4994.5  579.33  4994.9  578.83  4999.2  578.83
  4999.5  579.33  5010.5  580.19    5021  581.97  5073.7  582.47  5115.9   584.9
    5137  585.64  5147.5  586.51  5168.6  587.22  5210.8   590.2  5231.9  591.06
  5263.5  593.61    5274   595.1  5295.1  603.21  5305.6  606.05  5316.2  606.28
#Mann= 5 ,-1 , 0
  4528.3    .035       0  4711.5     .05       0  4845.3    .035       0
  4994.5    .035       0  4999.5    .035       0
Bank Sta=4994.5,4999.5
XS Rating Curve= 0 ,0
Exp/Cntr=0.3,0.1

Type RM Length L Ch R = 1 ,24166   ,463,463,463
BEGIN DESCRIPTION:
COTTONWOOD TRIBUTARY 1 51.0
END DESCRIPTION:
XS GIS Cut Line= 3
      2300225.03     13711125.03        2300625.       13711525.
      2300925.01       13711725.
#Sta/Elev= 30
  4438.9  593.98  4509.6  590.86  4537.8  591.09  4594.4  587.77  4753.1  582.11
  4792.4  580.98  4806.5  579.26  4820.7  578.47    4849  579.29  4905.5  578.45
  4976.3  578.85  4987.8  577.51  4988.2  577.01  4992.5  577.01  4992.9  577.51
    5012  578.38  5018.1  579.31  5084.9  580.39  5150.7  582.48  5207.3  584.84
  5249.4  588.25  5264.4  588.25  5270.4  588.99  5285.5   588.8    5293  590.38
  5306.5  591.53  5321.5  594.72  5336.5     601  5351.6   604.1  5365.1   605.2
#Mann= 6 ,-1 , 0
  4438.9     .07       0  4753.1    .035       0  4987.8    .035       0
  4992.9    .035       0  5084.9     .05       0  5150.7    .035       0
Bank Sta=4987.8,4992.9
XS Rating Curve= 0 ,0
Exp/Cntr=0.3,0.1

Type RM Length L Ch R = 1 ,23703   ,469,469,469
BEGIN DESCRIPTION:
COTTONWOOD TRIBUTARY 1 50.0
END DESCRIPTION:
XS GIS Cut Line= 3
      2300124.99     13711174.96        2300175.       13711575.
      2300574.97     13711974.97
#Sta/Elev= 30
  4596.4  591.66  4634.2  589.16  4656.9  588.45  4677.1  586.35  4697.2  585.82
  4714.9  583.85  4719.9  582.06  4727.5  581.48  4737.5  580.93  4770.9  581.76
  4777.8  582.04  4876.1  578.05  4907.5  577.28  4949.2  575.65  4979.4  576.89
  4994.5  575.45  4994.9  574.95  4999.2  574.95  4999.6  575.45  5003.1  575.45
  5013.7  577.86  5027.8  576.97  5056.1  577.04  5125.3  579.84  5177.2  581.87
  5197.5  583.06    5339  585.06  5452.1     589  5491.3  589.86  5565.2  592.18
#Mann= 8 ,-1 , 0
  4596.4     .05       0  4770.9     .07       0  4907.5    .035       0
  4994.5    .035       0  4999.6    .035       0  5125.3     .07       0
  5177.2    .035       0  5491.3     .05       0
Bank Sta=4994.5,4999.6
XS Rating Curve= 0 ,0
Exp/Cntr=0.3,0.1

Type RM Length L Ch R = 1 ,23234   ,446,446,446
BEGIN DESCRIPTION:
COTTONWOOD TRIBUTARY 1 49.0
END DESCRIPTION:
XS GIS Cut Line= 3
      2299374.99     13711174.99        2299825.       13711825.
      2300625.01       13712125.
#Sta/Elev= 30
  4214.8  594.85  4251.3  594.04  4372.9  588.61  4539.2  584.12  4610.1  581.62
  4689.2   579.6    4967  573.68  4989.3  572.87  4989.7  572.37  4994.1  572.37
  4994.5  572.87    4998  573.42  5020.5     574  5058.8  574.42  5122.9   573.8
  5154.9  574.11  5191.4  574.77  5248.5  577.01  5392.5  581.75    5478  584.98
  5502.9  586.47  5566.9  588.16  5595.2  589.22  5643.5  590.94  5667.5  590.91
  5673.8  591.47  5679.1  591.14  5768.6  594.07  5789.5  594.42  5859.8  597.28
#Mann= 9 ,-1 , 0
  4214.8     .05       0  4539.2     .07       0    4967     .05       0
  4989.3     .05       0  4994.5     .05       0  5248.5     .07       0
  5566.9     .05       0  5595.2     .07       0  5768.6     .05       0
Bank Sta=4989.3,4994.5
XS Rating Curve= 0 ,0
Exp/Cntr=0.3,0.1

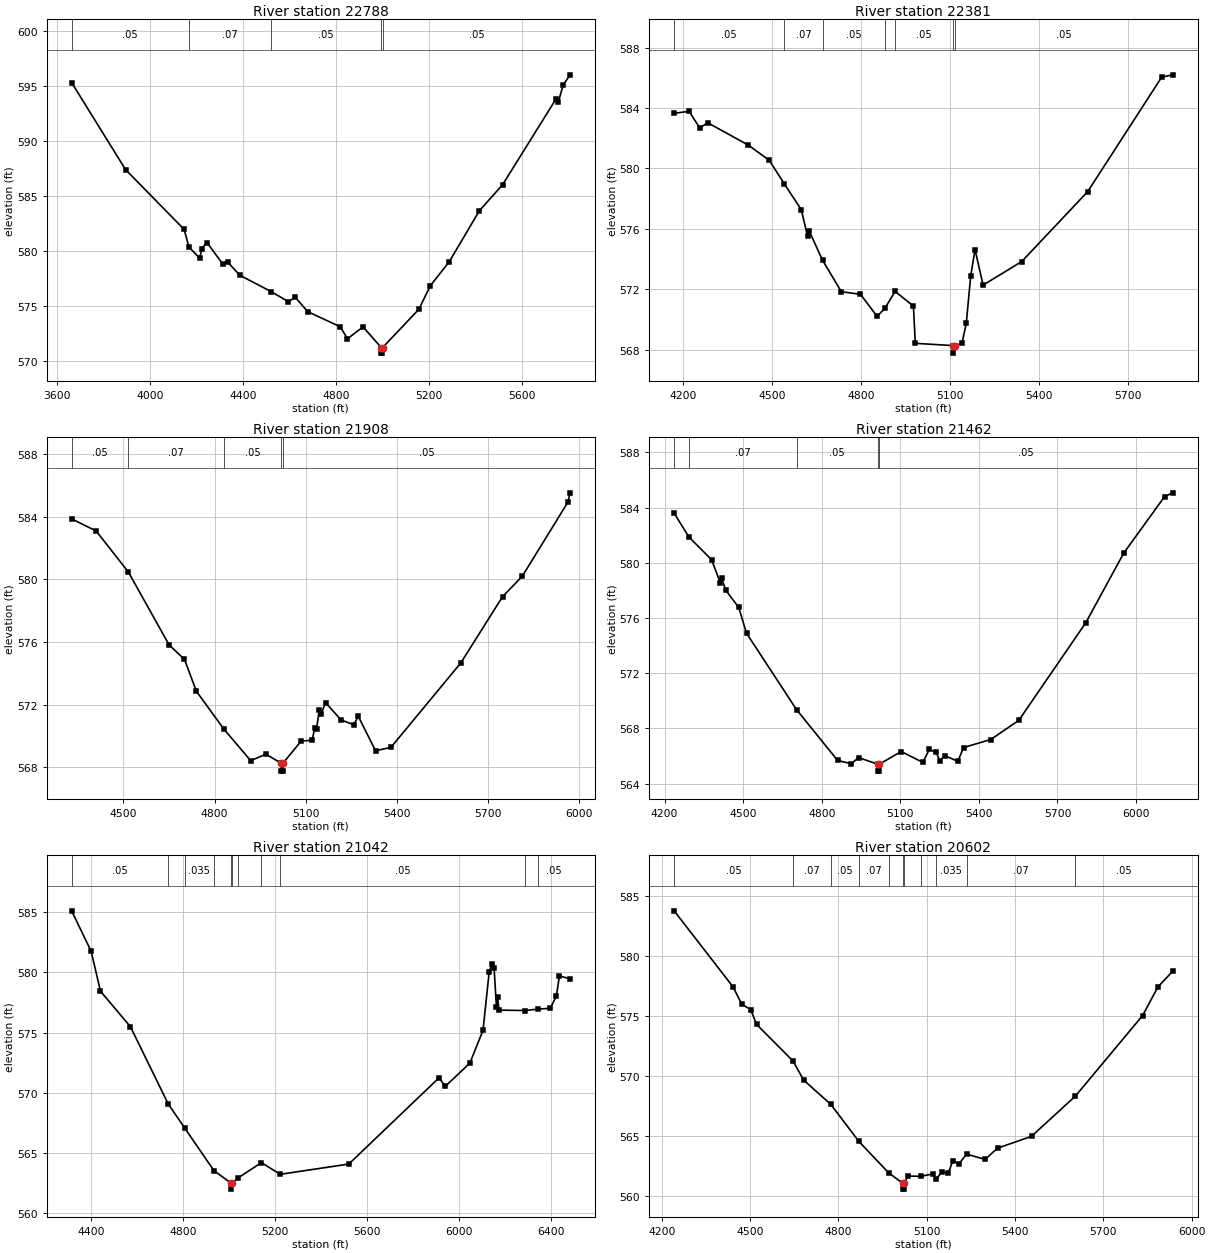
Type RM Length L Ch R = 1 ,22788   ,407,407,407
BEGIN DESCRIPTION:
COTTONWOOD TRIBUTARY 1 48.0
END DESCRIPTION:
XS GIS Cut Line= 3
      2298574.97     13711574.98        2299775.       13712175.
      2300575.02       13712175.
#Sta/Elev= 30
  3664.3  595.34  3896.3   587.4  4147.9  581.95  4168.1  580.35    4215  579.33
  4223.4  580.21  4245.7  580.76  4312.8  578.83  4335.2  578.96  4388.3  577.76
  4521.2  576.29  4595.1  575.38  4625.8  575.75    4679  574.46  4818.7  573.08
  4849.5  571.99  4916.5  573.07    4995  571.18  4995.4  570.68  4999.8  570.68
  5000.2  571.18    5156  574.67    5206  576.84    5286  578.98    5416  583.65
    5516  586.03    5746  593.86    5756   593.6    5776  595.11    5806  596.04
#Mann= 5 ,-1 , 0
  3664.3     .05       0  4168.1     .07       0  4521.2     .05       0
    4995     .05       0  5000.2     .05       0
Bank Sta=4995,5000.2
XS Rating Curve= 0 ,0
Exp/Cntr=0.3,0.1

Type RM Length L Ch R = 1 ,22381   ,473,473,473
BEGIN DESCRIPTION:
COTTONWOOD TRIBUTARY 1 47.0
END DESCRIPTION:
XS GIS Cut Line= 3
        2298925.       13711925.        2299575.       13712425.
        2300075.     13713125.01
#Sta/Elev= 30
  4169.6  583.66  4220.1  583.79  4255.7  582.69  4283.1  583.03  4419.7  581.55
  4490.4  580.54  4541.3  578.97  4598.2  577.27  4619.1  575.52  4625.4  575.83
  4670.1  573.91  4733.2  571.83  4797.6  571.66  4853.7   570.2  4879.6  570.72
  4914.4  571.85  4976.1  570.88  4982.4  568.41  5109.8  568.26  5110.3  567.76
  5115.3  568.26  5139.6   568.4  5154.3  569.74  5169.1  572.86  5183.8  574.63
  5210.9  572.27  5341.1  573.83  5563.6  578.47    5813  586.06  5849.9  586.21
#Mann= 7 ,-1 , 0
  4169.6     .05       0  4541.3     .07       0  4670.1     .05       0
  4879.6     .07       0  4914.4     .05       0  5109.8     .05       0
  5115.3     .05       0
Bank Sta=5109.8,5115.3
XS Rating Curve= 0 ,0
Exp/Cntr=0.3,0.1

Type RM Length L Ch R = 1 ,21908   ,446,446,446
BEGIN DESCRIPTION:
COTTONWOOD TRIBUTARY 1 46.0
END DESCRIPTION:
XS GIS Cut Line= 3
      2298925.01     13711975.02        2299225.       13712575.
      2300024.98     13713124.98
#Sta/Elev= 30
  4329.2  583.86  4410.2  583.08  4516.3  580.46  4650.6   575.8  4700.9  574.89
  4740.1  572.85  4830.5  570.44  4918.9  568.42  4969.3  568.83  5019.6  568.25
    5020  567.75  5024.7  567.75  5025.1  568.25  5085.2  569.67  5121.4  569.72
  5129.9  570.51    5136  570.47  5144.8  571.65  5150.9  571.41  5165.8  572.12
  5216.5  571.02  5258.4  570.71  5273.3  571.25  5330.1  569.05  5380.9  569.27
  5610.9  574.66  5748.3  578.89  5813.1  580.19  5963.4  584.92  5970.8  585.52
#Mann= 5 ,-1 , 0
  4329.2     .05       0  4516.3     .07       0  4830.5     .05       0
  5019.6     .05       0  5025.1     .05       0
Bank Sta=5019.6,5025.1
XS Rating Curve= 0 ,0
Exp/Cntr=0.3,0.1

Type RM Length L Ch R = 1 ,21462   ,420,420,420
BEGIN DESCRIPTION:
COTTONWOOD TRIBUTARY 1 45.0
END DESCRIPTION:
XS GIS Cut Line= 3
      2298524.99     13712224.98        2298925.       13712875.
      2300024.99       13713175.
#Sta/Elev= 30
  4236.5   583.6  4292.4  581.88  4379.6  580.22  4412.3  578.57  4418.2  578.88
  4433.6  578.01  4483.1  576.77  4512.8   574.9  4703.7  569.37  4860.7  565.68
  4912.8  565.45    4941  565.89  5014.3  565.41  5014.7  564.91  5019.4  564.91
  5019.8  565.41  5103.4  566.33  5186.3  565.54  5210.5  566.48  5238.1  566.26
  5250.2  565.64  5269.2  566.04  5319.3  565.62  5341.8  566.62  5445.4   567.2
  5552.5  568.59  5808.2  575.66  5953.3  580.71  6108.8  584.79  6139.9  585.07
#Mann= 5 ,-1 , 0
  4236.5     .05       0  4292.4     .07       0  4703.7     .05       0
  5014.3     .05       0  5019.8     .05       0
Bank Sta=5014.3,5019.8
XS Rating Curve= 0 ,0
Exp/Cntr=0.3,0.1

Type RM Length L Ch R = 1 ,21042   ,440,440,440
BEGIN DESCRIPTION:
COTTONWOOD TRIBUTARY 1 44.0
END DESCRIPTION:
XS GIS Cut Line= 3
      2297974.96     13713325.01        2298625.       13713125.
      2300039.07     13713588.15
#Sta/Elev= 30
  4314.9   585.1  4399.9  581.75  4440.5  578.43  4570.6  575.49  4734.5   569.1
  4806.7  567.08  4934.2  563.54    5008  562.51  5008.5  562.01  5013.8  562.51
  5037.6  562.92  5140.2  564.21  5222.6  563.24  5520.5  564.09  5913.2  571.25
  5939.8  570.53  6047.3  572.47  6104.3   575.2  6130.9  580.01    6142   580.7
  6152.5  580.32  6162.7  577.09    6168  577.91  6173.6  576.86  6288.4  576.83
  6345.2  576.95  6396.2  577.01  6422.8     578  6436.6   579.7    6483  579.46
#Mann= 11 ,-1 , 0
  4314.9     .05       0  4734.5     .07       0  4806.7    .035       0
  4934.2     .07       0    5008     .05       0  5013.8     .07       0
  5037.6     .05       0  5140.2     .07       0  5222.6     .05       0
  6288.4     .07       0  6345.2     .05       0
Bank Sta=5008,5013.8
XS Rating Curve= 0 ,0
Exp/Cntr=0.3,0.1

Type RM Length L Ch R = 1 ,20602   ,449,449,449
BEGIN DESCRIPTION:
COTTONWOOD TRIBUTARY 1 43.0
END DESCRIPTION:
XS GIS Cut Line= 3
      2298025.03       13713475.        2298775.       13713475.
      2299575.03     13713975.02
#Sta/Elev= 30
  4242.1  583.74  4442.1  577.42  4472.1  575.97  4502.1  575.53  4522.1   574.3
  4645.5  571.27  4682.1  569.67  4774.1  567.66  4869.7  564.57    4971  561.96
    5018  561.11  5018.5  560.61  5023.4  560.61  5023.9  561.11  5036.3  561.69
  5081.7  561.68  5121.8  561.88  5132.4  561.43  5151.9  562.06  5173.1  561.91
  5188.4  562.96  5209.6  562.71  5235.4  563.52  5298.1  563.08  5340.5  564.01
  5456.1     565  5605.4  568.35  5833.5  575.04  5885.3  577.41  5935.5  578.72
#Mann= 11 ,-1 , 0
  4242.1     .05       0  4645.5     .07       0  4774.1     .05       0
  4869.7     .07       0    4971    .035       0    5018    .035       0
  5023.9    .035       0  5081.7     .07       0  5132.4    .035       0
  5235.4     .07       0  5605.4     .05       0
Bank Sta=5018,5023.9
XS Rating Curve= 0 ,0
Exp/Cntr=0.3,0.1

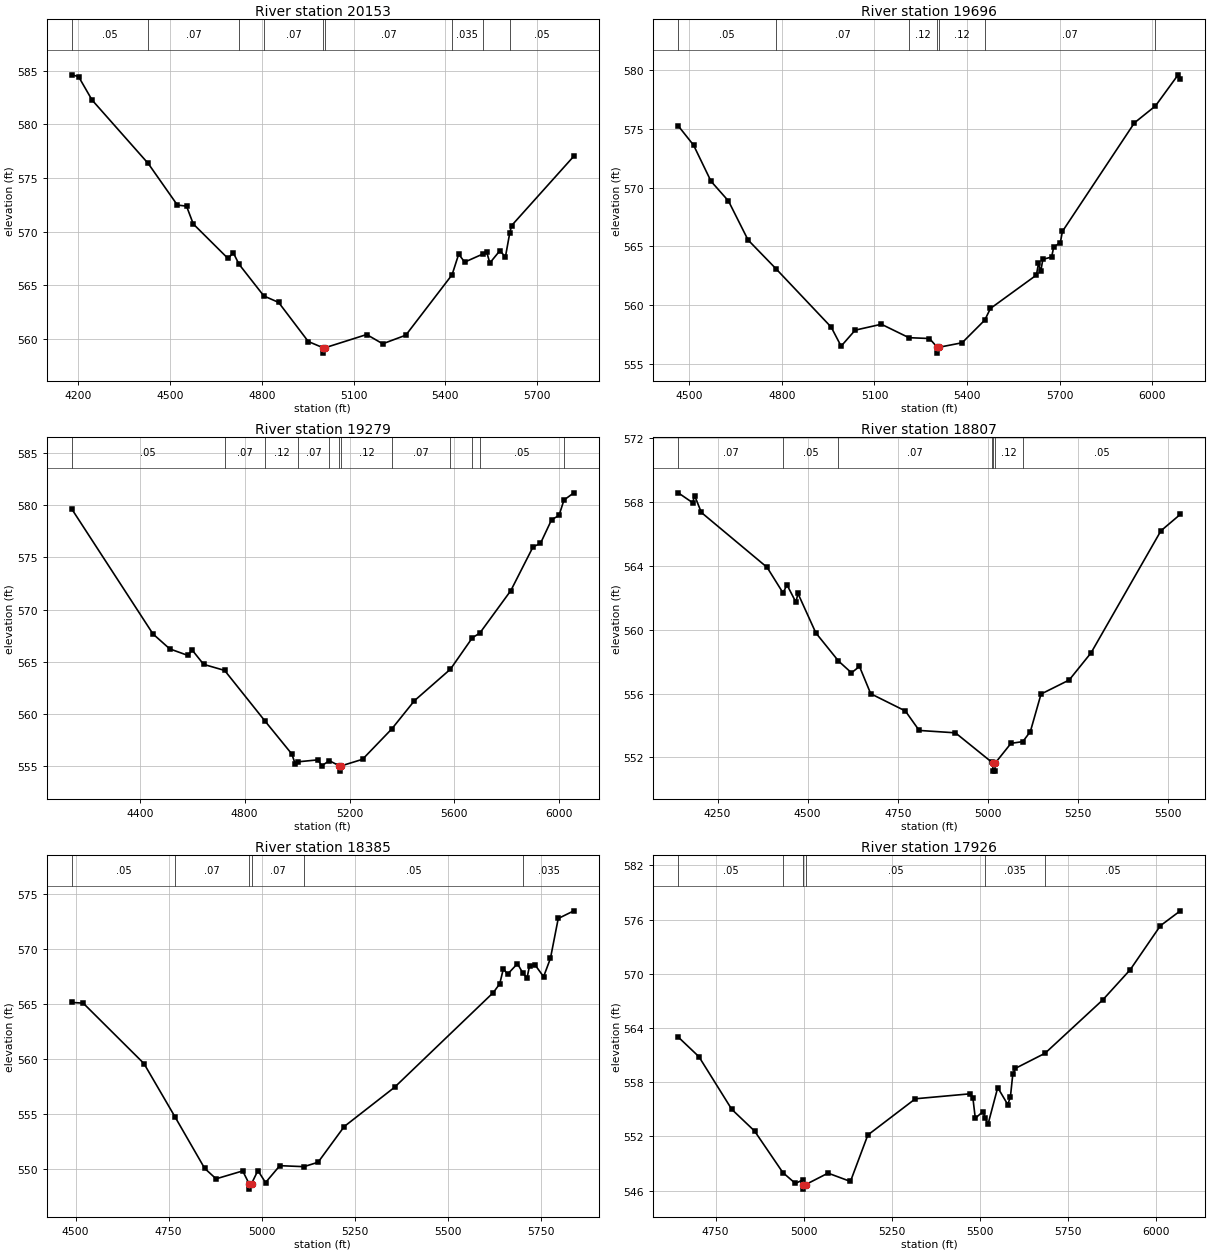
Type RM Length L Ch R = 1 ,20153   ,457,457,457
BEGIN DESCRIPTION:
COTTONWOOD TRIBUTARY 1 42.0
END DESCRIPTION:
XS GIS Cut Line= 3
      2297974.99       13713525.        2298725.       13713875.
        2299525.       13714025.
#Sta/Elev= 30
  4178.8   584.6  4200.9  584.44    4245  582.26  4428.7  576.35  4524.1  572.48
    4554  572.38  4576.1  570.72  4689.6  567.51  4706.9  568.04  4725.7  566.97
  4806.9  564.02  4855.1  563.42  4952.1  559.78  5000.6   559.2  5001.1   558.7
  5006.7   559.2    5143  560.43  5195.5  559.57    5271  560.37  5422.2  565.99
  5443.9  567.91  5463.4  567.17  5521.8  567.91  5535.5   568.1  5545.7  567.09
  5578.8  568.24  5596.6  567.64  5610.6  569.85  5616.9  570.57  5820.4  577.03
#Mann= 9 ,-1 , 0
  4178.8     .05       0  4428.7     .07       0  4725.7     .05       0
  4806.9     .07       0  5000.6     .05       0  5006.7     .07       0
  5422.2    .035       0  5521.8     .07       0  5610.6     .05       0
Bank Sta=5000.6,5006.7
XS Rating Curve= 0 ,0
Exp/Cntr=0.3,0.1

Type RM Length L Ch R = 1 ,19696   ,417,417,417
BEGIN DESCRIPTION:
COTTONWOOD TRIBUTARY 1 41.0
END DESCRIPTION:
XS GIS Cut Line= 3
      2298074.99     13713774.99        2298425.       13714175.
        2299175.       13714975.
#Sta/Elev= 30
  4463.6  575.23  4513.4  573.59  4569.9  570.53  4626.4  568.86    4690  565.55
  4780.1  563.12  4959.5  558.16  4991.8  556.54  5037.4   557.9  5122.4   558.4
  5211.6  557.26  5278.2  557.19  5303.4  556.45  5303.9  555.95  5309.6  556.45
  5384.2  556.83  5457.5  558.75    5476  559.74    5625  562.57  5631.8  563.56
  5639.1  562.89    5646  563.91  5674.3   564.1  5681.2  564.95  5702.6  565.33
  5709.5  566.28    5943  575.49  6011.1  576.92  6084.6  579.56  6091.7  579.23
#Mann= 7 ,-1 , 0
  4463.6     .05       0  4780.1     .07       0  5211.6     .12       0
  5303.4     .05       0  5309.6     .12       0  5457.5     .07       0
  6011.1     .05       0
Bank Sta=5303.4,5309.6
XS Rating Curve= 0 ,0
Exp/Cntr=0.3,0.1

Type RM Length L Ch R = 1 ,19279   ,472,472,472
BEGIN DESCRIPTION:
COTTONWOOD TRIBUTARY 1 40.0
END DESCRIPTION:
XS GIS Cut Line= 3
      2297924.98     13713724.96        2298225.       13714525.
      2298974.99     13715274.99
#Sta/Elev= 30
  4140.5  579.63  4450.3  567.67  4514.3  566.24  4582.9  565.62  4599.8  566.13
  4643.4  564.76  4723.5  564.18  4877.7  559.33  4979.8  556.18  4992.3  555.26
  5002.8  555.43  5079.8  555.62  5093.9  555.05  5122.8  555.54  5161.6  555.04
  5162.1  554.54  5167.8  555.04  5249.5  555.67  5360.8  558.57  5447.5  561.28
  5584.9   564.3  5668.6  567.31  5696.8  567.75  5815.2  571.82    5900  576.01
  5928.3  576.34  5970.8  578.61    5999  579.01  6017.9  580.49  6055.6  581.18
#Mann= 12 ,-1 , 0
  4140.5     .05       0  4723.5     .07       0  4877.7     .12       0
  5002.8     .07       0  5122.8     .12       0  5161.6     .05       0
  5167.8     .12       0  5360.8     .07       0  5584.9     .05       0
  5668.6     .07       0  5696.8     .05       0  6017.9    .035       0
Bank Sta=5161.6,5167.8
XS Rating Curve= 0 ,0
Exp/Cntr=0.3,0.1

Type RM Length L Ch R = 1 ,18807   ,422,422,422
BEGIN DESCRIPTION:
COTTONWOOD TRIBUTARY 1 39.0
END DESCRIPTION:
XS GIS Cut Line= 3
        2297725.     13714125.01        2298025.       13714925.
      2298524.99       13715125.
#Sta/Elev= 30
    4141  568.58    4181  567.96  4186.4  568.41  4205.1  567.35  4387.5  563.91
  4431.7  562.31  4442.7  562.81  4467.6  561.72    4473  562.28  4522.8   559.8
  4585.6  558.04  4621.6   557.3  4643.8   557.7    4675  555.99  4771.1  554.91
  4809.4  553.69    4910  553.54  5011.4  551.69  5013.6  551.64  5014.1  551.14
  5019.7  551.14  5020.2  551.64  5064.1  552.88    5097  552.99  5117.9  553.62
  5147.5  555.97  5225.6  556.85  5286.2  558.55  5480.1   566.2  5533.9  567.23
#Mann= 7 ,-1 , 0
    4141     .07       0  4431.7     .05       0  4585.6     .07       0
  5011.4     .12       0  5013.6     .05       0  5020.2     .12       0
    5097     .05       0
Bank Sta=5013.6,5020.2
XS Rating Curve= 0 ,0
Exp/Cntr=0.3,0.1

Type RM Length L Ch R = 1 ,18385   ,459,459,459
BEGIN DESCRIPTION:
COTTONWOOD TRIBUTARY 1 38.0
END DESCRIPTION:
XS GIS Cut Line= 3
      2297375.03     13715175.01        2297875.       13715275.
      2298674.98     13715524.99
#Sta/Elev= 30
  4489.8  565.15  4520.4  565.09  4683.5  559.58  4767.5  554.68  4846.7  550.01
  4877.3  549.06  4948.7  549.78  4965.8  548.62  4966.3  548.12  4972.4  548.62
  4989.5  549.81  5010.1  548.72  5048.4  550.26    5113  550.17  5151.1  550.57
  5221.3  553.83  5356.4  557.41  5621.5  566.05  5638.8  566.85  5648.7  568.24
  5659.7  567.72  5686.4  568.69  5701.4   567.8  5712.1  567.38  5718.9  568.51
  5733.1   568.6  5756.6   567.5    5775  569.18  5795.9  572.81  5837.8  573.51
#Mann= 6 ,-1 , 0
  4489.8     .05       0  4767.5     .07       0  4965.8     .05       0
  4972.4     .07       0    5113     .05       0  5701.4    .035       0
Bank Sta=4965.8,4972.4
XS Rating Curve= 0 ,0
Exp/Cntr=0.3,0.1

Type RM Length L Ch R = 1 ,17926   ,442,442,442
BEGIN DESCRIPTION:
COTTONWOOD TRIBUTARY 1 37.0
END DESCRIPTION:
XS GIS Cut Line= 3
      2297474.98     13715274.97        2297675.       13715575.
      2298474.99     13716274.99
#Sta/Elev= 30
  4644.3     563  4702.9  560.83  4796.1     555  4860.7   552.6    4941     548
  4976.4   546.8  4997.2  547.18  4998.4  546.67  4998.9  546.17  5005.4  546.67
    5069  547.94  5132.6  547.02  5181.9  552.16  5316.7  556.17  5472.3  556.72
  5479.9  556.22  5486.6  554.01  5508.4  554.76  5514.5  554.07  5522.6  553.34
  5550.2  557.41  5578.6  555.53  5586.2  556.38  5592.9  558.89  5600.5  559.54
  5684.5  561.21  5848.2  567.12    5926  570.46  6011.4  575.32  6067.9  576.97
#Mann= 7 ,-1 , 0
  4644.3     .05       0    4941     .07       0  4997.2     .05       0
  4998.4     .05       0  5005.4     .05       0  5514.5    .035       0
  5684.5     .05       0
Bank Sta=4998.4,5005.4
XS Rating Curve= 0 ,0
Exp/Cntr=0.3,0.1

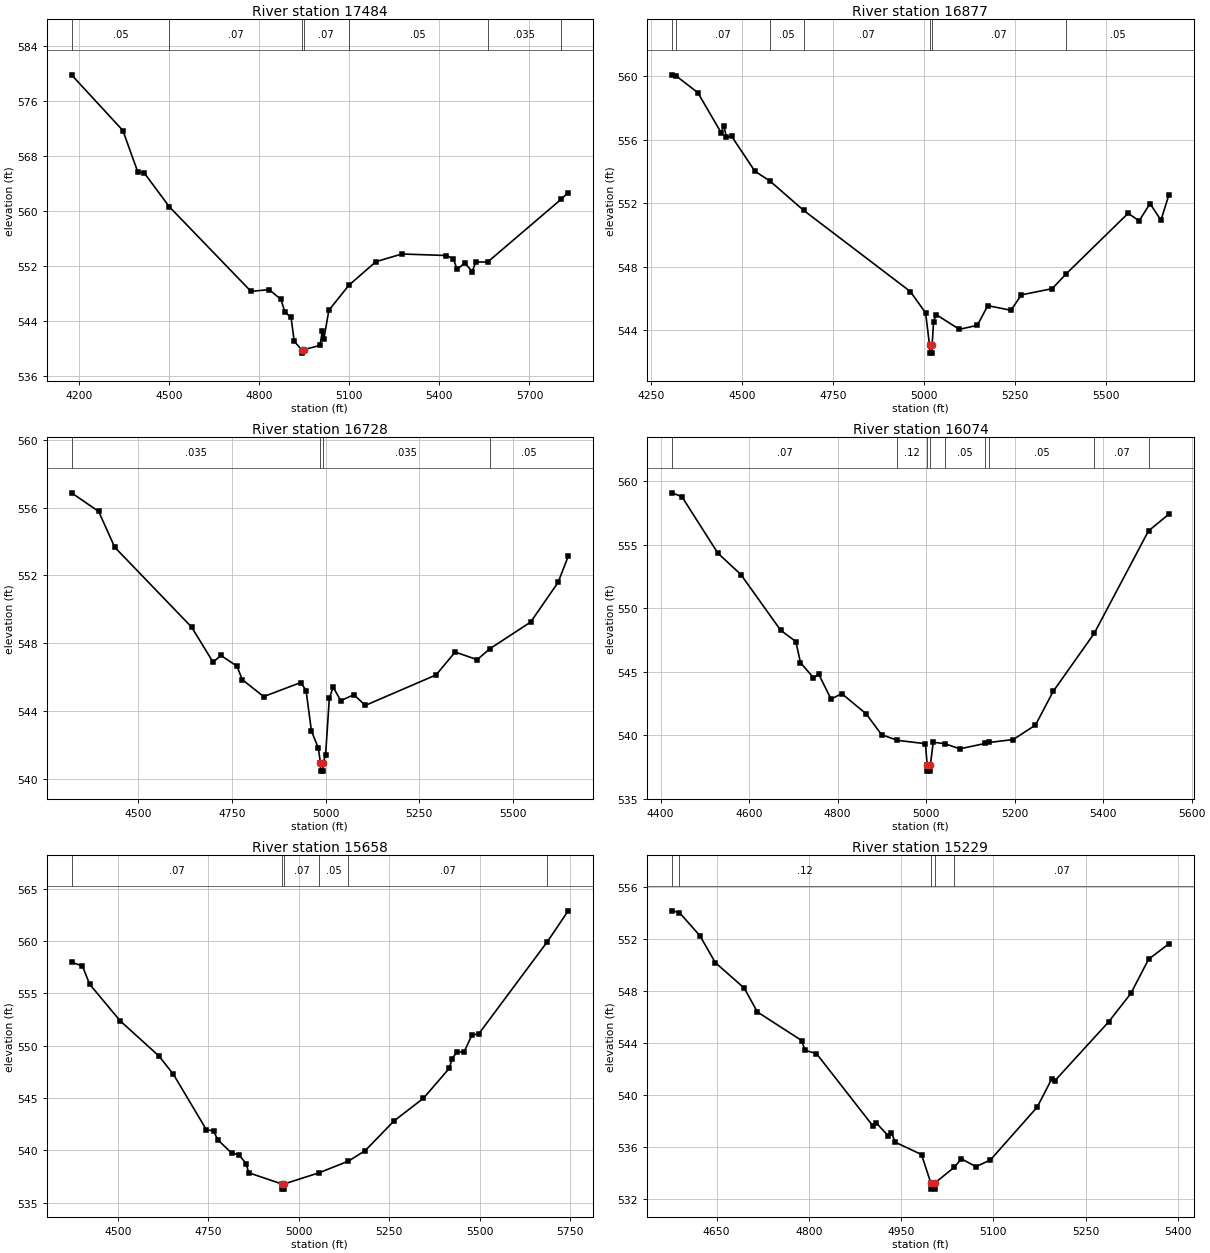
Type RM Length L Ch R = 1 ,17484   ,607,607,607
BEGIN DESCRIPTION:
COTTONWOOD TRIBUTARY 1 36.0
END DESCRIPTION:
XS GIS Cut Line= 3
      2296633.36     13715642.54        2297425.       13715875.
      2298204.56     13716157.11
#Sta/Elev= 30
  4174.9  579.75    4346  571.67  4395.5  565.68  4417.9  565.47  4500.9   560.6
  4772.6  548.34  4833.2  548.59  4872.7  547.16  4885.3  545.35  4906.1  544.55
  4916.6   541.1  4941.1  539.88  4941.6  539.38  4948.2  539.88  5002.6   540.5
    5010  542.56  5015.3  541.42  5031.9  545.59  5098.5  549.22  5188.5  552.64
  5275.1  553.76  5423.1  553.54  5446.6  553.06    5459  551.54  5484.3  552.44
  5509.7  551.22  5521.1  552.62  5560.4  552.58  5805.8  561.71    5829  562.68
#Mann= 7 ,-1 , 0
  4174.9     .05       0  4500.9     .07       0  4941.1     .05       0
  4948.2     .07       0  5098.5     .05       0  5560.4    .035       0
  5805.8     .05       0
Bank Sta=4941.1,4948.2
XS Rating Curve= 0 ,0
Exp/Cntr=0.3,0.1

Type RM Length L Ch R = 1 ,16877   ,149,149,149
BEGIN DESCRIPTION:
COTTONWOOD TRIBUTARY 1 35.0
END DESCRIPTION:
XS GIS Cut Line= 4
      2296791.75     13716811.82      2297366.77     13716355.34
      2297710.78     13716071.65      2297896.39     13716062.81
#Sta/Elev= 30
  4307.8  560.09  4319.1  560.02  4378.6  558.97  4442.7  556.45  4450.7  556.88
  4457.1  556.15  4471.6  556.22  4535.6  554.02  4577.1   553.4  4669.3  551.56
  4963.1  546.44  5005.1  545.09  5015.9  543.06  5016.4  542.56  5022.5  542.56
    5023  543.06    5027  544.55  5033.9  544.99  5097.8  544.06  5147.3  544.31
    5176  545.55  5239.8  545.26  5268.5  546.23  5353.1  546.62  5391.4  547.55
  5562.2  551.37  5592.2  550.89  5622.3  551.98  5652.3  550.93  5673.7   552.5
#Mann= 7 ,-1 , 0
  4307.8    .035       0  4319.1     .07       0  4577.1     .05       0
  4669.3     .07       0  5015.9     .05       0    5023     .07       0
  5391.4     .05       0
Bank Sta=5015.9,5023
XS Rating Curve= 0 ,0
Exp/Cntr=0.3,0.1

Type RM Length L Ch R = 1 ,16728   ,654,654,654
BEGIN DESCRIPTION:
COTTONWOOD TRIBUTARY 1 34.0
END DESCRIPTION:
XS GIS Cut Line= 4
      2296902.75     13716915.19      2297402.07     13716491.52
      2297471.22     13716502.49      2297981.03     13716184.52
#Sta/Elev= 30
  4321.9  556.87  4394.4  555.77  4437.2  553.66  4642.6  548.94  4699.8  546.87
  4720.6  547.27  4763.5  546.64  4777.7  545.84  4834.9  544.84  4933.7  545.67
    4948   545.2  4962.3  542.81  4980.8  541.79  4986.2  540.94  4986.7  540.44
  4992.9  540.44  4993.4  540.94    5000  541.38  5010.1  544.75  5020.2   545.4
  5040.5   544.6  5075.5  544.95  5106.2  544.32    5295  546.12  5345.9  547.47
  5404.7  547.02  5438.2  547.66  5547.4  549.24  5620.6  551.58  5647.6  553.12
#Mann= 4 ,-1 , 0
  4321.9    .035       0  4986.2    .035       0  4993.4    .035       0
  5438.2     .05       0
Bank Sta=4986.2,4993.4
XS Rating Curve= 0 ,0
Exp/Cntr=0.3,0.1

Type RM Length L Ch R = 1 ,16074   ,416,416,416
BEGIN DESCRIPTION:
COTTONWOOD TRIBUTARY 1 33.0
END DESCRIPTION:
XS GIS Cut Line= 3
      2296975.02     13717224.99        2297525.       13717075.
      2298074.97       13717025.
#Sta/Elev= 30
  4425.9   559.1  4448.3  558.79  4529.5  554.34  4581.4  552.66  4671.2  548.27
  4705.7  547.37  4716.1  545.71  4745.5  544.52  4757.6  544.78  4785.2  542.84
  4809.4  543.27  4864.7  541.67  4899.2  540.04  4934.6  539.59  4998.5  539.32
  5002.3  537.66  5002.8  537.16  5009.2  537.16  5009.7  537.66    5016  539.44
  5042.2  539.32  5076.3  538.92  5133.2  539.34  5142.5  539.42  5196.8  539.65
    5247  540.79  5287.2  543.45  5379.8  548.02  5502.5   556.1  5548.2  557.41
#Mann= 9 ,-1 , 0
  4425.9     .07       0  4934.6     .12       0  5002.3     .05       0
  5009.7     .12       0  5042.2     .05       0  5133.2     .12       0
  5142.5     .05       0  5379.8     .07       0  5502.5     .05       0
Bank Sta=5002.3,5009.7
XS Rating Curve= 0 ,0
Exp/Cntr=0.3,0.1

Type RM Length L Ch R = 1 ,15658   ,429,429,429
BEGIN DESCRIPTION:
COTTONWOOD TRIBUTARY 1 32.0
END DESCRIPTION:
XS GIS Cut Line= 3
      2296975.03       13717325.      2297521.11     13717386.62
      2298326.34     13717555.53
#Sta/Elev= 30
  4372.3  557.99  4402.5  557.62  4422.6  555.87  4507.1  552.37  4613.8  549.02
    4654  547.26  4744.6  541.99  4764.7  541.84  4776.7     541  4815.1  539.72
  4835.2  539.58  4855.3  538.69  4861.6  537.86  4952.7  536.79  4953.2  536.29
  4959.7  536.29  4960.2  536.79  5056.8  537.86  5137.5  538.97  5184.1  539.98
    5263   542.8  5344.7  544.98  5416.3  547.85  5423.4  548.75  5436.7  549.37
  5457.1  549.42  5478.4     551    5498  551.16  5687.3  559.96  5744.6   562.9
#Mann= 6 ,-1 , 0
  4372.3     .07       0  4952.7     .05       0  4960.2     .07       0
  5056.8     .05       0  5137.5     .07       0  5687.3     .05       0
Bank Sta=4952.7,4960.2
XS Rating Curve= 0 ,0
Exp/Cntr=0.3,0.1

Type RM Length L Ch R = 1 ,15229   ,483,483,483
BEGIN DESCRIPTION:
COTTONWOOD TRIBUTARY 1 31.0
END DESCRIPTION:
XS GIS Cut Line= 3
      2297025.02     13717575.01        2297425.       13717725.
      2297775.03     13717875.01
#Sta/Elev= 30
  4577.4  554.17  4589.5  554.03  4622.8  552.25  4647.7  550.19  4694.9  548.22
  4716.2  546.39  4788.3  544.19  4793.6  543.44  4812.3  543.19    4904  537.63
  4909.3  537.87  4928.9  536.87  4934.3  537.11  4940.5  536.37  4983.2  535.42
  4998.2  533.26  4998.7  532.76  5005.2  532.76  5005.7  533.26  5036.2  534.43
  5048.1  535.09  5071.7  534.49  5095.2     535  5171.4  539.07    5195  541.23
  5200.4  541.11  5287.5  545.62  5323.7  547.81  5352.7  550.45  5385.4  551.62
#Mann= 5 ,-1 , 0
  4577.4     .07       0  4589.5     .12       0  4998.2     .05       0
  5005.7     .12       0  5036.2     .07       0
Bank Sta=4998.2,5005.7
XS Rating Curve= 0 ,0
Exp/Cntr=0.3,0.1