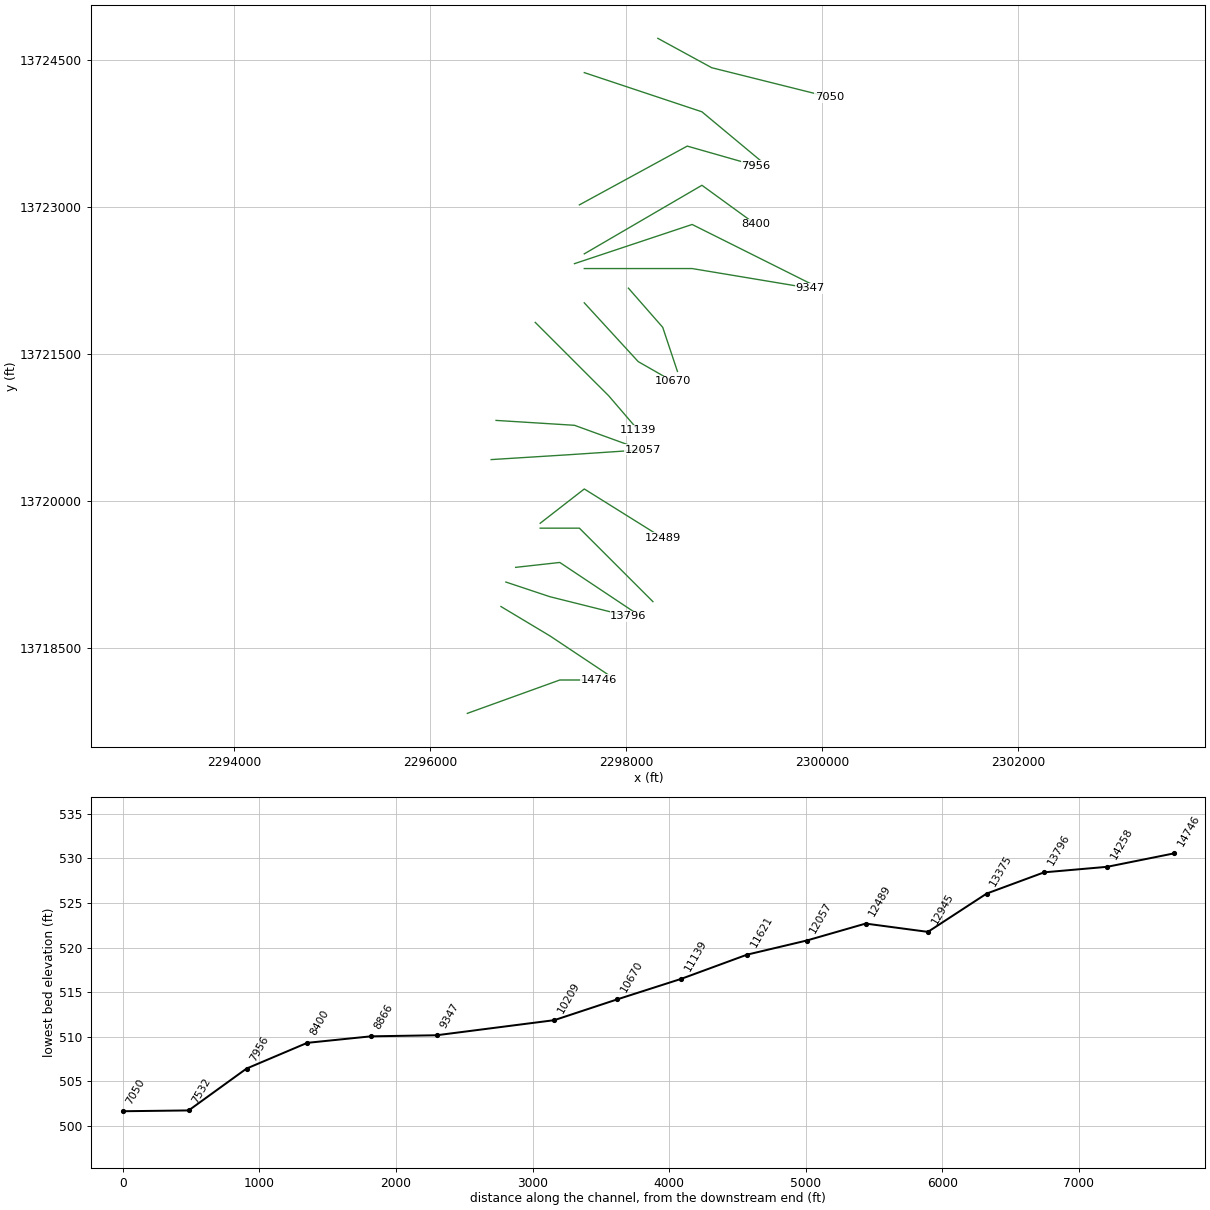
HEC-RAS study COTTONWOOD TRIBUTARY 1.prj: COTTONWOOD TRIBUTARY 1 Base Level Engineering

--- COTTONWOOD TRIBUTARY 1.g01 (geometry) --- (continued)

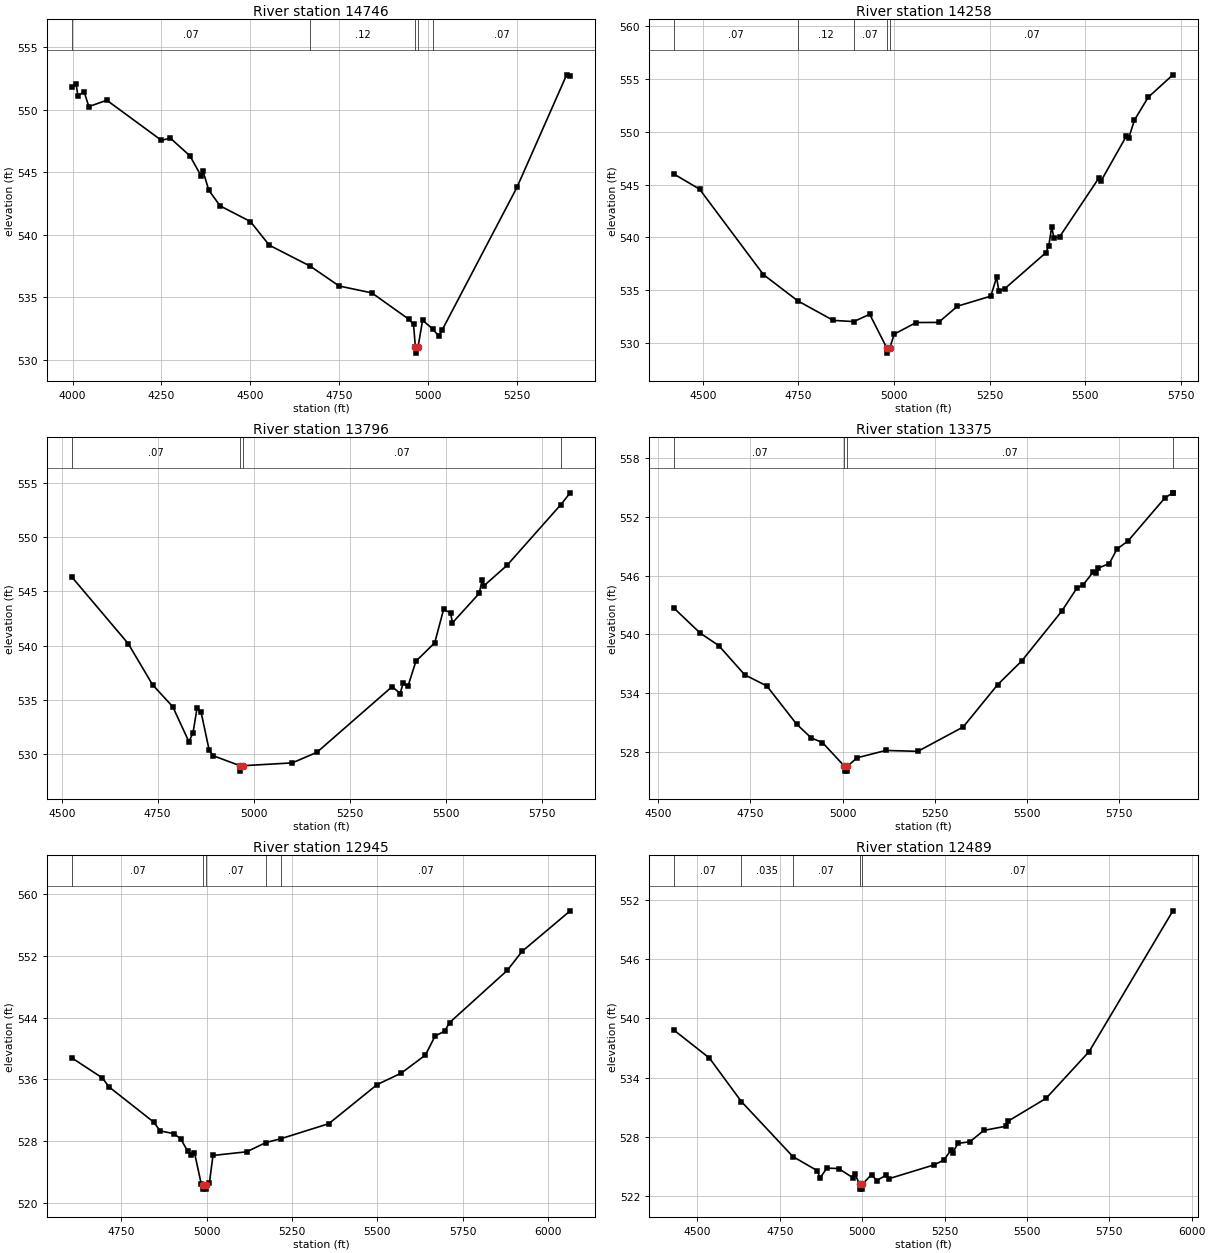
Type RM Length L Ch R = 1 ,14746   ,488,488,488
BEGIN DESCRIPTION:
COTTONWOOD TRIBUTARY 1 30.0
END DESCRIPTION:
XS GIS Cut Line= 3
      2296381.91     13717834.41        2297325.       13718175.
      2297724.99       13718175.
#Sta/Elev= 30
  3997.3  551.82  4009.8  552.04  4015.1   551.1  4032.5  551.42  4045.8  550.23
  4096.3  550.74  4249.9  547.54  4275.2  547.71  4330.2   546.3  4361.9  544.68
  4367.2  545.06  4383.3  543.55  4415.2   542.3  4500.3  541.05  4553.5  539.16
  4668.4  537.49    4750   535.9    4842  535.35  4946.8  533.23  4959.3  532.83
  4964.3  531.04  4964.8  530.54  4971.9  531.04  4984.7  533.16  5012.7  532.49
    5030  531.91    5040   532.4    5250  543.77    5390  552.77    5400  552.68
#Mann= 5 ,-1 , 0
  3997.3     .07       0  4668.4     .12       0  4964.3     .05       0
  4971.9     .12       0  5012.7     .07       0
Bank Sta=4964.3,4971.9
XS Rating Curve= 0 ,0
Exp/Cntr=0.3,0.1

Type RM Length L Ch R = 1 ,14258   ,462,462,462
BEGIN DESCRIPTION:
COTTONWOOD TRIBUTARY 1 29.0
END DESCRIPTION:
XS GIS Cut Line= 3
      2296724.99     13718925.01        2297225.       13718625.
      2297824.99     13718225.01
#Sta/Elev= 30
  4425.1  545.99  4491.2  544.58  4658.3  536.48  4748.3  533.99  4841.1  532.14
  4894.7  532.03  4936.3  532.72  4980.9  529.54  4981.4  529.04  4988.9  529.54
  5000.4  530.84  5057.8  531.94  5116.4  531.95  5165.9  533.49  5253.1  534.44
  5268.1  536.21  5274.1  534.97  5289.1  535.13  5397.3  538.56  5404.8  539.23
  5412.3     541  5418.3  539.93  5433.4  540.08  5535.5  545.62  5541.5  545.36
  5607.6   549.6  5613.6  549.39  5628.7  551.12  5664.7  553.28  5729.3  555.41
#Mann= 5 ,-1 , 0
  4425.1     .07       0  4748.3     .12       0  4894.7     .07       0
  4980.9     .05       0  4988.9     .07       0
Bank Sta=4980.9,4988.9
XS Rating Curve= 0 ,0
Exp/Cntr=0.3,0.1

Type RM Length L Ch R = 1 ,13796   ,421,421,421
BEGIN DESCRIPTION:
COTTONWOOD TRIBUTARY 1 28.0
END DESCRIPTION:
XS GIS Cut Line= 3
      2296774.96     13719175.01        2297225.       13719025.
        2298025.       13718825.
#Sta/Elev= 30
  4525.8  546.36  4673.4  540.18  4736.7  536.39  4789.4  534.36  4831.5  531.13
  4842.1  531.96  4852.6  534.22  4863.2  533.85  4884.2  530.36  4894.8  529.84
  4964.5  528.92    4965  528.42  4972.6  528.92  5100.7  529.18  5165.1  530.16
    5361  536.22  5381.6  535.58  5389.3  536.51  5402.2  536.26  5422.8  538.56
  5471.8  540.26    5495  543.35    5513  543.01  5518.1  542.11  5587.7  544.82
  5595.5  546.08  5600.6  545.54  5659.9   547.4  5800.3  553.01  5824.8   554.1
#Mann= 4 ,-1 , 0
  4525.8     .07       0  4964.5     .05       0  4972.6     .07       0
  5800.3     .05       0
Bank Sta=4964.5,4972.6
XS Rating Curve= 0 ,0
Exp/Cntr=0.3,0.1

Type RM Length L Ch R = 1 ,13375   ,430,430,430
BEGIN DESCRIPTION:
COTTONWOOD TRIBUTARY 1 27.0
END DESCRIPTION:
XS GIS Cut Line= 3
      2296874.99       13719325.        2297325.       13719375.
      2298075.03     13718874.98
#Sta/Elev= 30
    4543  542.65  4613.4  540.13  4663.7  538.86  4734.2  535.88  4794.5  534.73
    4875  530.85  4915.3  529.42  4945.5  528.96  5005.2  526.54  5005.7  526.04
  5012.9  526.04  5013.4  526.54  5039.3   527.4  5117.5  528.15  5204.6  528.06
  5327.8  530.55  5420.9  534.85    5487   537.3  5595.2  542.36  5637.3  544.77
  5652.3     545  5680.8  546.37  5688.3  546.24  5694.4  546.77  5724.4  547.22
  5745.4  548.71  5775.5  549.54  5874.6  553.89  5896.2  554.45  5897.2  554.45
#Mann= 4 ,-1 , 0
    4543     .07       0  5005.2     .05       0  5013.4     .07       0
  5896.2     .05       0
Bank Sta=5005.2,5013.4
XS Rating Curve= 0 ,0
Exp/Cntr=0.3,0.1

Type RM Length L Ch R = 1 ,12945   ,456,456,456
BEGIN DESCRIPTION:
COTTONWOOD TRIBUTARY 1 26.0
END DESCRIPTION:
XS GIS Cut Line= 3
      2297124.97       13719725.        2297525.       13719725.
      2298275.01     13718974.99
#Sta/Elev= 30
  4604.5  538.81  4694.5  536.19  4714.5  535.01  4844.5  530.47  4864.5   529.3
  4904.5  528.95  4924.5  528.27  4944.5  526.66  4954.5  526.24  4964.5  526.47
  4984.5  522.39  4990.4  522.25  4990.9  521.75  4998.1  521.75  4998.6  522.25
  5008.1  522.53  5018.7  526.12  5117.7   526.6  5173.7   527.8  5217.4  528.29
  5358.1  530.25  5499.5  535.32  5570.2  536.81  5640.9  539.15  5669.2  541.61
  5697.5  542.27  5711.6  543.36  5881.3  550.17  5923.8   552.6  6065.2  557.88
#Mann= 5 ,-1 , 0
  4604.5     .07       0  4990.4     .05       0  4998.6     .07       0
  5173.7     .12       0  5217.4     .07       0
Bank Sta=4990.4,4998.6
XS Rating Curve= 0 ,0
Exp/Cntr=0.3,0.1

Type RM Length L Ch R = 1 ,12489   ,432,432,432
BEGIN DESCRIPTION:
COTTONWOOD TRIBUTARY 1 25.0
END DESCRIPTION:
XS GIS Cut Line= 3
      2297125.03     13719775.02        2297575.       13720125.
      2298374.96     13719625.02
#Sta/Elev= 30
  4429.6  538.79  4536.3  535.98  4633.4  531.56  4789.8  525.98  4863.9  524.55
  4872.1  523.82  4892.9  524.81  4928.2  524.77  4971.6  523.84  4977.9  524.21
  4992.3  523.18  4992.8  522.68  5000.1  522.68  5000.6  523.18  5028.5  524.16
  5043.9  523.55    5071  524.07  5080.4  523.73  5217.2  525.13  5247.3  525.61
  5269.1  526.61    5275  526.38  5290.3  527.32  5326.9  527.49  5369.3  528.64
    5436  529.06  5442.5  529.57    5558  531.89  5688.9  536.64    5943  550.92
#Mann= 5 ,-1 , 0
  4429.6     .07       0  4633.4    .035       0  4789.8     .07       0
  4992.3     .05       0  5000.6     .07       0
Bank Sta=4992.3,5000.6
XS Rating Curve= 0 ,0
Exp/Cntr=0.3,0.1

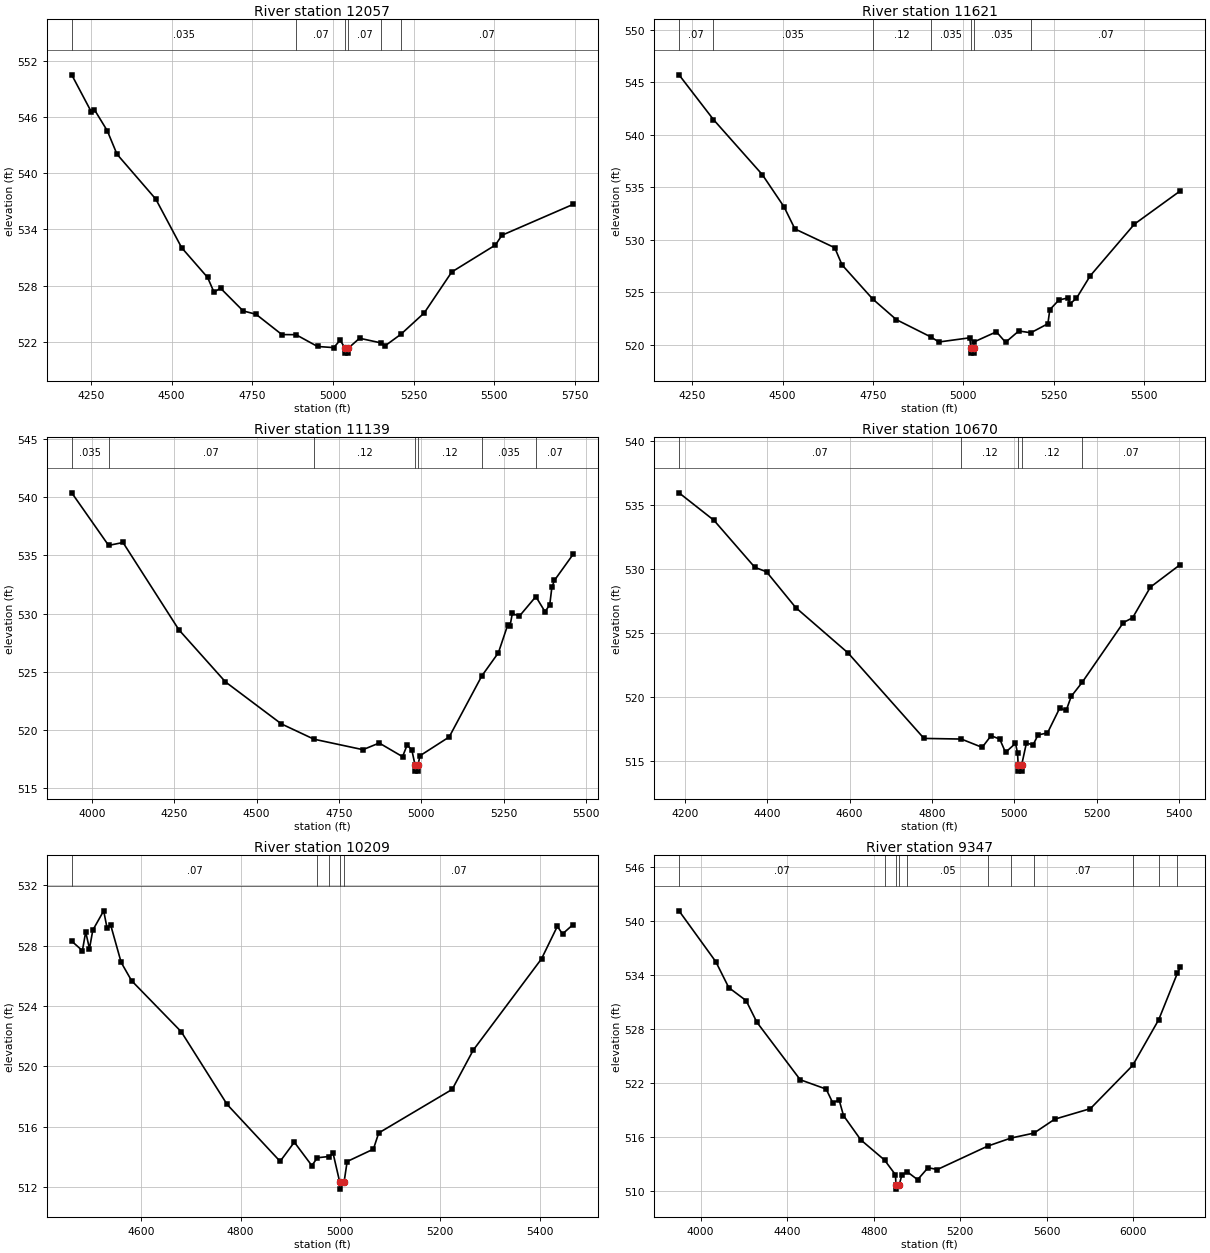
Type RM Length L Ch R = 1 ,12057   ,436,436,436
BEGIN DESCRIPTION:
COTTONWOOD TRIBUTARY 1 24.0
END DESCRIPTION:
XS GIS Cut Line= 3
      2296625.03       13720425.        2297425.       13720475.
        2298175.       13720525.
#Sta/Elev= 30
  4190.6  550.51  4250.7  546.59  4260.7   546.8  4300.8  544.53  4330.8  542.03
  4451.1  537.23  4531.2  532.04  4611.4  528.87  4631.4  527.29  4651.5  527.72
  4721.6  525.29  4761.7  524.93  4841.8  522.76  4885.4  522.75  4952.1  521.49
  5002.2  521.37  5022.2  522.16    5038  521.28  5038.5  520.78    5046  520.78
  5046.5  521.28  5082.3  522.37  5147.6  521.88  5162.5  521.59  5210.2  522.79
  5282.8  525.08    5368  529.45  5503.3  532.33  5523.3  533.37  5743.8  536.67
#Mann= 6 ,-1 , 0
  4190.6    .035       0  4885.4     .07       0    5038     .05       0
  5046.5     .07       0  5147.6    .035       0  5210.2     .07       0
Bank Sta=5038,5046.5
XS Rating Curve= 0 ,0
Exp/Cntr=0.3,0.1

Type RM Length L Ch R = 1 ,11621   ,482,482,482
BEGIN DESCRIPTION:
COTTONWOOD TRIBUTARY 1 23.0
END DESCRIPTION:
XS GIS Cut Line= 3
      2296674.99       13720825.        2297475.       13720775.
        2298025.       13720575.
#Sta/Elev= 30
  4213.4  545.71  4308.6  541.45  4443.9   536.2    4504  533.13    4534  531.03
  4644.2  529.24  4664.3  527.61    4749  524.36  4814.6  522.39  4910.1  520.74
  4932.3  520.26  5017.6  520.66  5020.7   519.7  5021.2   519.2  5028.7   519.2
  5029.2   519.7  5030.3  520.28  5091.4  521.23  5116.7  520.23  5153.3  521.31
  5186.6  521.14  5233.8     522  5239.1  523.34  5264.4  524.26  5289.6  524.46
  5294.9  523.89  5312.9  524.43  5350.8  526.56  5473.2  531.49  5600.2  534.66
#Mann= 7 ,-1 , 0
  4213.4     .07       0  4308.6    .035       0    4749     .12       0
  4910.1    .035       0  5020.7    .035       0  5029.2    .035       0
  5186.6     .07       0
Bank Sta=5020.7,5029.2
XS Rating Curve= 0 ,0
Exp/Cntr=0.3,0.1

Type RM Length L Ch R = 1 ,11139   ,469,469,469
BEGIN DESCRIPTION:
COTTONWOOD TRIBUTARY 1 22.0
END DESCRIPTION:
XS GIS Cut Line= 3
      2297074.99     13721825.01        2297825.       13721075.
      2298125.03     13720724.96
#Sta/Elev= 30
  3939.1  540.36    4051  535.85  4094.7   536.1  4264.4  528.61  4405.8  524.14
  4575.5  520.54  4674.2  519.23    4823  518.33  4872.5   518.9  4943.2  517.73
  4957.3  518.74  4971.5  518.29  4981.3  516.99  4981.8  516.49  4989.4  516.49
  4989.9  516.99  4996.2  517.81  5084.8  519.42  5183.9  524.66  5234.1  526.64
  5262.6  529.04  5269.2   528.9  5276.4  530.01  5297.8  529.78  5347.8  531.46
  5375.7  530.16    5390  530.76  5396.5  532.26  5404.2  532.85  5460.8  535.08
#Mann= 7 ,-1 , 0
  3939.1    .035       0    4051     .07       0  4674.2     .12       0
  4981.3     .05       0  4989.9     .12       0  5183.9    .035       0
  5347.8     .07       0
Bank Sta=4981.3,4989.9
XS Rating Curve= 0 ,0
Exp/Cntr=0.3,0.1

Type RM Length L Ch R = 1 ,10670   ,461,461,461
BEGIN DESCRIPTION:
COTTONWOOD TRIBUTARY 1 21.0
END DESCRIPTION:
XS GIS Cut Line= 3
      2297575.01     13722024.98        2298125.       13721425.
      2298474.97     13721225.02
#Sta/Elev= 30
  4185.8  535.97  4270.6  533.82  4369.8  530.14  4398.2  529.79  4469.1  526.99
  4596.1  523.44  4780.5  516.75  4871.1   516.7  4921.7  516.05  4943.3  516.96
  4964.3   516.7  4978.4  515.66  5002.6  516.36  5007.6  515.61  5009.1  514.69
  5009.6  514.19  5017.2  514.19  5017.7  514.69  5029.2   516.4  5045.1  516.23
  5057.3  517.02  5080.3  517.18  5109.9  519.12  5125.7  518.94  5137.9  520.04
  5164.3  521.13  5264.6  525.82  5286.9  526.19  5330.1  528.59  5402.8  530.36
#Mann= 5 ,-1 , 0
  4185.8     .07       0  4871.1     .12       0  5009.1     .05       0
  5017.7     .12       0  5164.3     .07       0
Bank Sta=5009.1,5017.7
XS Rating Curve= 0 ,0
Exp/Cntr=0.3,0.1

Type RM Length L Ch R = 1 ,10209   ,862,862,862
BEGIN DESCRIPTION:
COTTONWOOD TRIBUTARY 1 20.0
END DESCRIPTION:
XS GIS Cut Line= 3
      2298024.98     13722175.02        2298375.       13721775.
      2298525.01     13721324.98
#Sta/Elev= 30
  4461.3  528.29  4482.7  527.66  4489.3   528.9  4496.9  527.79  4503.6  529.02
  4525.4   530.3    4532  529.19  4539.6  529.34  4560.5  526.88  4581.4  525.67
    4681  522.29  4773.1  517.47  4879.4   513.7  4907.9  514.97    4943  513.42
  4954.3  513.94  4977.2  514.02  4985.7  514.23  4998.8  512.36  4999.3  511.86
  5007.9  512.36  5013.9  513.69  5066.6  514.51  5077.2  515.58  5224.7  518.47
  5266.9  521.07  5403.9  527.12  5435.6  529.27  5446.1  528.77  5467.2  529.39
#Mann= 5 ,-1 , 0
  4461.3     .07       0  4954.3     .05       0  4977.2     .07       0
  4998.8     .05       0  5007.9     .07       0
Bank Sta=4998.8,5007.9
XS Rating Curve= 0 ,0
Exp/Cntr=0.3,0.1

Type RM Length L Ch R = 1 ,9347    ,481,481,481
BEGIN DESCRIPTION:
COTTONWOOD TRIBUTARY 1 19.0
END DESCRIPTION:
XS GIS Cut Line= 3
      2297575.01       13722375.        2298675.       13722375.
      2299874.96     13722175.01
#Sta/Elev= 30
  3900.1  541.08  4070.1  535.43  4130.1  532.55  4210.1  531.11  4260.1   528.7
  4460.1  522.32  4580.1  521.28  4610.1  519.77  4640.1  520.06  4660.1  518.34
  4740.1  515.64  4849.8   513.4  4900.1  511.77  4902.6  510.67  4903.1  510.17
  4917.6  510.67  4930.1  511.75  4955.8  512.07  5002.6  511.22  5050.8  512.55
  5093.9  512.35  5326.6  514.95  5433.4  515.84  5539.9  516.39  5636.2  517.94
    5801  519.11  5996.3  523.91  6116.7  528.99  6202.9  534.15  6216.6  534.83
#Mann= 11 ,-1 , 0
  3900.1     .07       0  4849.8     .12       0  4902.6     .05       0
  4917.6     .12       0  4955.8     .05       0  5326.6    .035       0
  5433.4     .05       0  5539.9     .07       0  5996.3     .05       0
  6116.7     .07       0  6202.9     .05       0
Bank Sta=4902.6,4917.6
XS Rating Curve= 0 ,0
Exp/Cntr=0.3,0.1

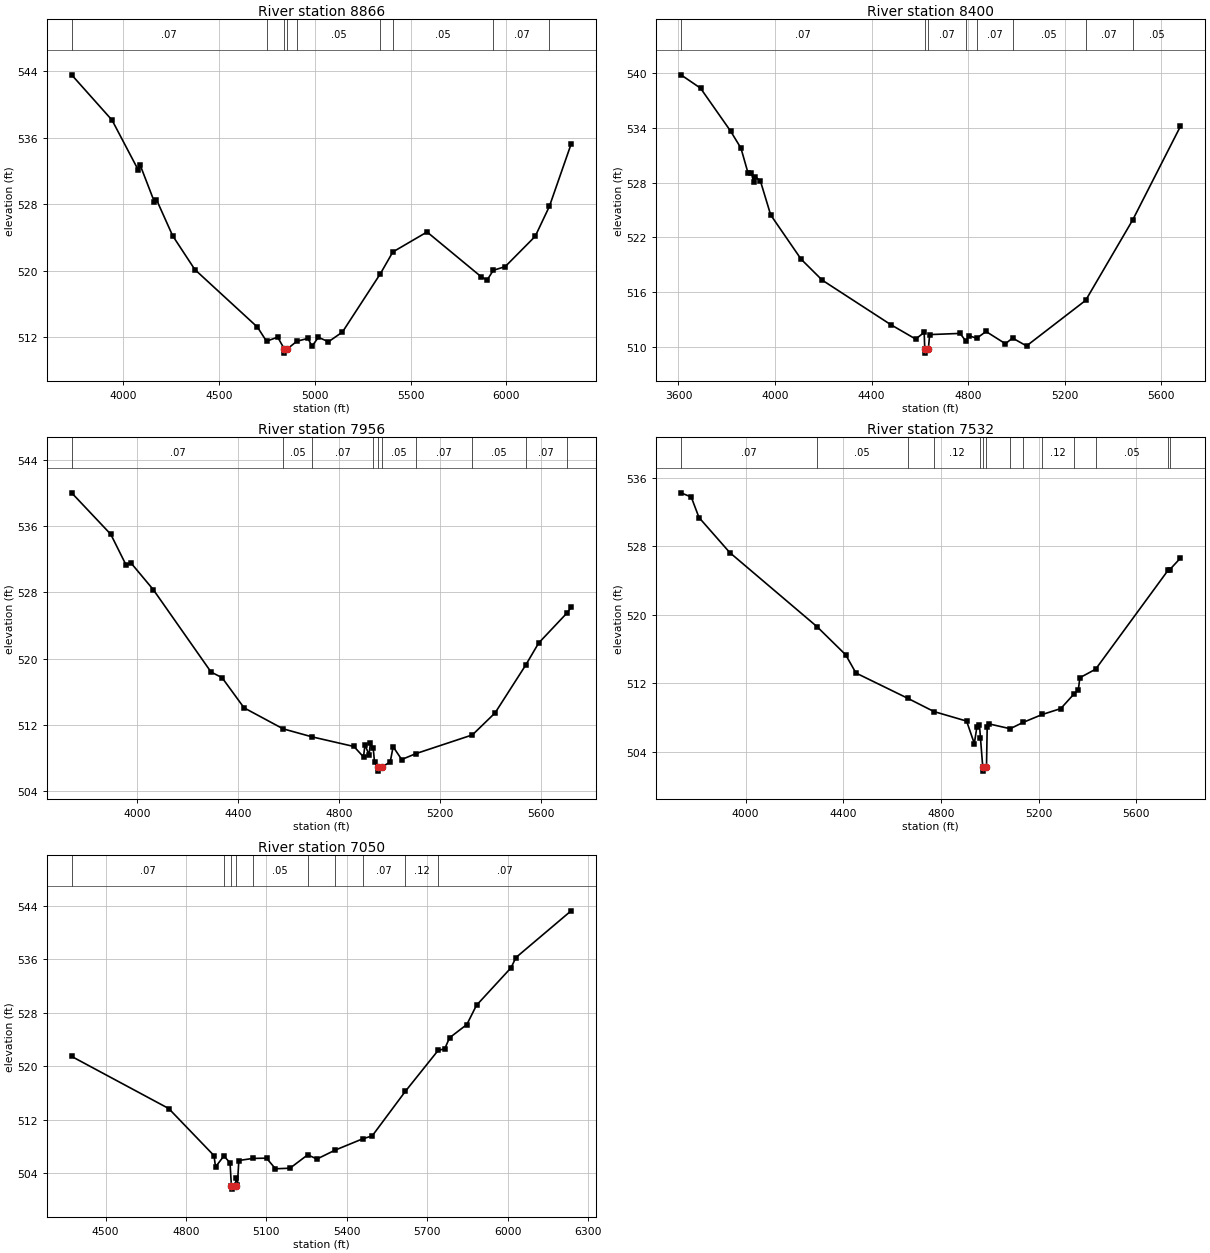
Type RM Length L Ch R = 1 ,8866    ,466,466,466
BEGIN DESCRIPTION:
COTTONWOOD TRIBUTARY 1 18.0
END DESCRIPTION:
XS GIS Cut Line= 3
      2297474.97     13722424.99        2298675.       13722825.
      2299875.02     13722224.99
#Sta/Elev= 30
  3731.2  543.59    3942  538.13  4079.1  532.11  4089.6  532.67  4163.4  528.25
  4173.9  528.55  4258.3   524.2  4374.2  520.12    4701  513.18  4748.2  511.48
  4806.4  511.98  4841.1  510.55  4841.6  510.05  4856.1  510.55  4906.7  511.48
  4964.5  511.83  4985.6  510.86  5018.5  511.96  5071.6  511.42  5144.3  512.59
  5342.9  519.64  5407.3  522.24  5585.9  524.65  5868.2  519.26    5899  518.85
  5931.8  520.03    5994  520.48  6150.5  524.13  6224.8  527.76  6337.8  535.25
#Mann= 9 ,-1 , 0
  3731.2     .07       0  4748.2     .12       0  4841.1     .05       0
  4856.1     .12       0  4906.7     .05       0  5342.9    .035       0
  5407.3     .05       0  5931.8     .07       0  6224.8     .05       0
Bank Sta=4841.1,4856.1
XS Rating Curve= 0 ,0
Exp/Cntr=0.3,0.1

Type RM Length L Ch R = 1 ,8400    ,444,444,444
BEGIN DESCRIPTION:
COTTONWOOD TRIBUTARY 1 17.0
END DESCRIPTION:
XS GIS Cut Line= 3
      2297575.03     13722525.02        2298775.       13723225.
      2299325.01     13722824.99
#Sta/Elev= 30
  3610.4  539.81  3691.4  538.35  3815.9  533.65  3858.9  531.78  3888.2  529.06
  3901.9  529.09  3911.4  528.06  3917.6  528.62  3939.1  528.22  3982.1  524.46
  4108.2  519.61  4195.4  517.32  4479.1  512.45  4582.8  510.86    4618  511.59
  4620.4  509.82  4620.9  509.32  4635.5  509.82  4640.7  511.35  4766.8  511.48
  4791.1  510.62  4802.8  511.23  4835.8  510.95  4874.3  511.69  4954.5  510.35
  4984.2  510.97  5042.1  510.11    5287   515.1  5482.1  523.92  5679.7  534.17
#Mann= 8 ,-1 , 0
  3610.4     .07       0  4620.4     .05       0  4635.5     .07       0
  4791.1     .12       0  4835.8     .07       0  4984.2     .05       0
    5287     .07       0  5482.1     .05       0
Bank Sta=4620.4,4635.5
XS Rating Curve= 0 ,0
Exp/Cntr=0.3,0.1

Type RM Length L Ch R = 1 ,7956    ,424,424,424
BEGIN DESCRIPTION:
COTTONWOOD TRIBUTARY 1 16.0
END DESCRIPTION:
XS GIS Cut Line= 3
      2297524.99       13723025.        2298625.       13723625.
      2299324.99       13723425.
#Sta/Elev= 30
  3738.8     540    3894     535  3953.8  531.35  3975.6  531.49    4063  528.31
  4291.7  518.39  4335.4  517.71  4422.7  514.07  4577.5  511.54  4692.6  510.57
  4858.4  509.41  4896.4  508.15  4902.1  509.62  4918.2  508.41  4923.9  509.79
  4934.9  509.19  4940.1  507.52  4954.3  506.94  4954.8  506.44  4969.5  506.94
  5002.2  507.54  5013.9  509.38  5047.7  507.84    5105  508.56  5328.3  510.81
  5418.2  513.46  5539.1   519.2  5591.1  521.89  5701.9  525.46  5719.8  526.19
#Mann= 10 ,-1 , 0
  3738.8     .07       0  4577.5     .05       0  4692.6     .07       0
  4934.9     .05       0  4954.3     .05       0  4969.5     .05       0
    5105     .07       0  5328.3     .05       0  5539.1     .07       0
  5701.9     .05       0
Bank Sta=4954.3,4969.5
XS Rating Curve= 0 ,0
Exp/Cntr=0.3,0.1

Type RM Length L Ch R = 1 ,7532    ,482,482,482
BEGIN DESCRIPTION:
COTTONWOOD TRIBUTARY 1 15.0
END DESCRIPTION:
XS GIS Cut Line= 3
      2297575.03     13724374.99        2298775.       13723975.
        2299375.       13723475.
#Sta/Elev= 30
  3735.2  534.23  3777.3  533.74    3809  531.35  3935.4  527.25  4292.5  518.61
  4409.8  515.33    4452   513.2  4663.4  510.26  4771.7   508.7  4905.2  507.59
  4936.8  504.97  4947.4  506.91  4957.9  507.12    4962  505.63  4971.3  502.25
  4971.8  501.75  4986.7  502.25  4989.5  506.88  4997.4  507.26  5083.8   506.7
  5136.8  507.44  5215.1  508.36    5291  509.05  5346.5   510.8  5362.6  511.19
  5369.1  512.65  5433.8  513.65  5730.9  525.21  5737.7  525.28  5781.1  526.61
#Mann= 14 ,-1 , 0
  3735.2     .07       0  4292.5     .05       0  4663.4     .07       0
  4771.7     .12       0    4962     .05       0  4971.3     .05       0
  4986.7     .05       0  5083.8     .12       0  5136.8     .05       0
  5215.1     .12       0  5346.5     .07       0  5433.8     .05       0
  5730.9     .07       0  5737.7     .05       0
Bank Sta=4971.3,4986.7
XS Rating Curve= 0 ,0
Exp/Cntr=0.3,0.1

Type RM Length L Ch R = 1 ,7050    ,452,452,452
BEGIN DESCRIPTION:
COTTONWOOD TRIBUTARY 1 14.0
END DESCRIPTION:
XS GIS Cut Line= 3
      2298324.98     13724725.01        2298875.       13724425.
      2300074.95     13724125.01
#Sta/Elev= 30
  4373.5   521.5  4735.7  513.71  4904.6  506.67  4910.3  504.98  4941.5  506.62
  4964.4  505.59  4969.5  502.16    4970  501.66    4985  502.16  4986.3  503.25
  4991.9  502.28  4997.2  505.94  5049.7  506.25  5100.5  506.29    5134   504.7
  5188.1  504.79  5254.2  506.79  5288.6  506.16  5356.4  507.49  5458.7  509.17
  5494.8  509.62  5618.3  516.27  5740.5  522.39  5765.4  522.65  5783.4  524.29
  5847.8  526.27  5883.9  529.15  6012.8  534.76  6030.8  536.28  6236.9  543.27
#Mann= 10 ,-1 , 0
  4373.5     .07       0  4941.5     .12       0  4969.5     .05       0
    4985     .12       0  5049.7     .05       0  5254.2     .07       0
  5356.4     .05       0  5458.7     .07       0  5618.3     .12       0
  5740.5     .07       0
Bank Sta=4969.5,4985
XS Rating Curve= 0 ,0
Exp/Cntr=0.3,0.1