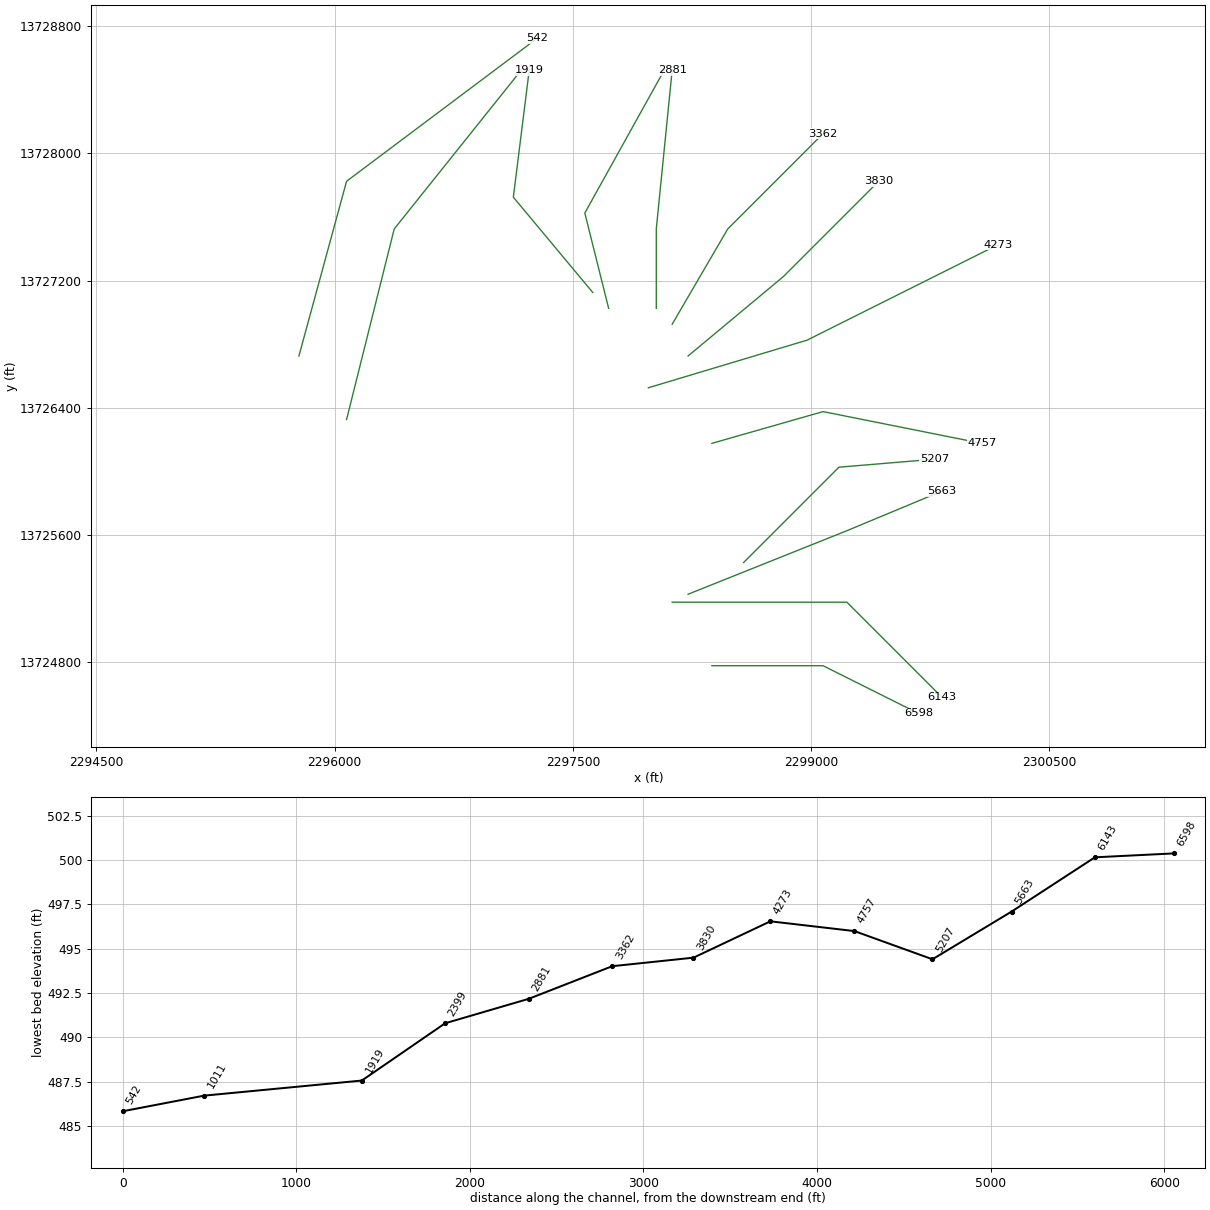
HEC-RAS study COTTONWOOD TRIBUTARY 1.prj: COTTONWOOD TRIBUTARY 1 Base Level Engineering

--- COTTONWOOD TRIBUTARY 1.g01 (geometry) --- (continued)

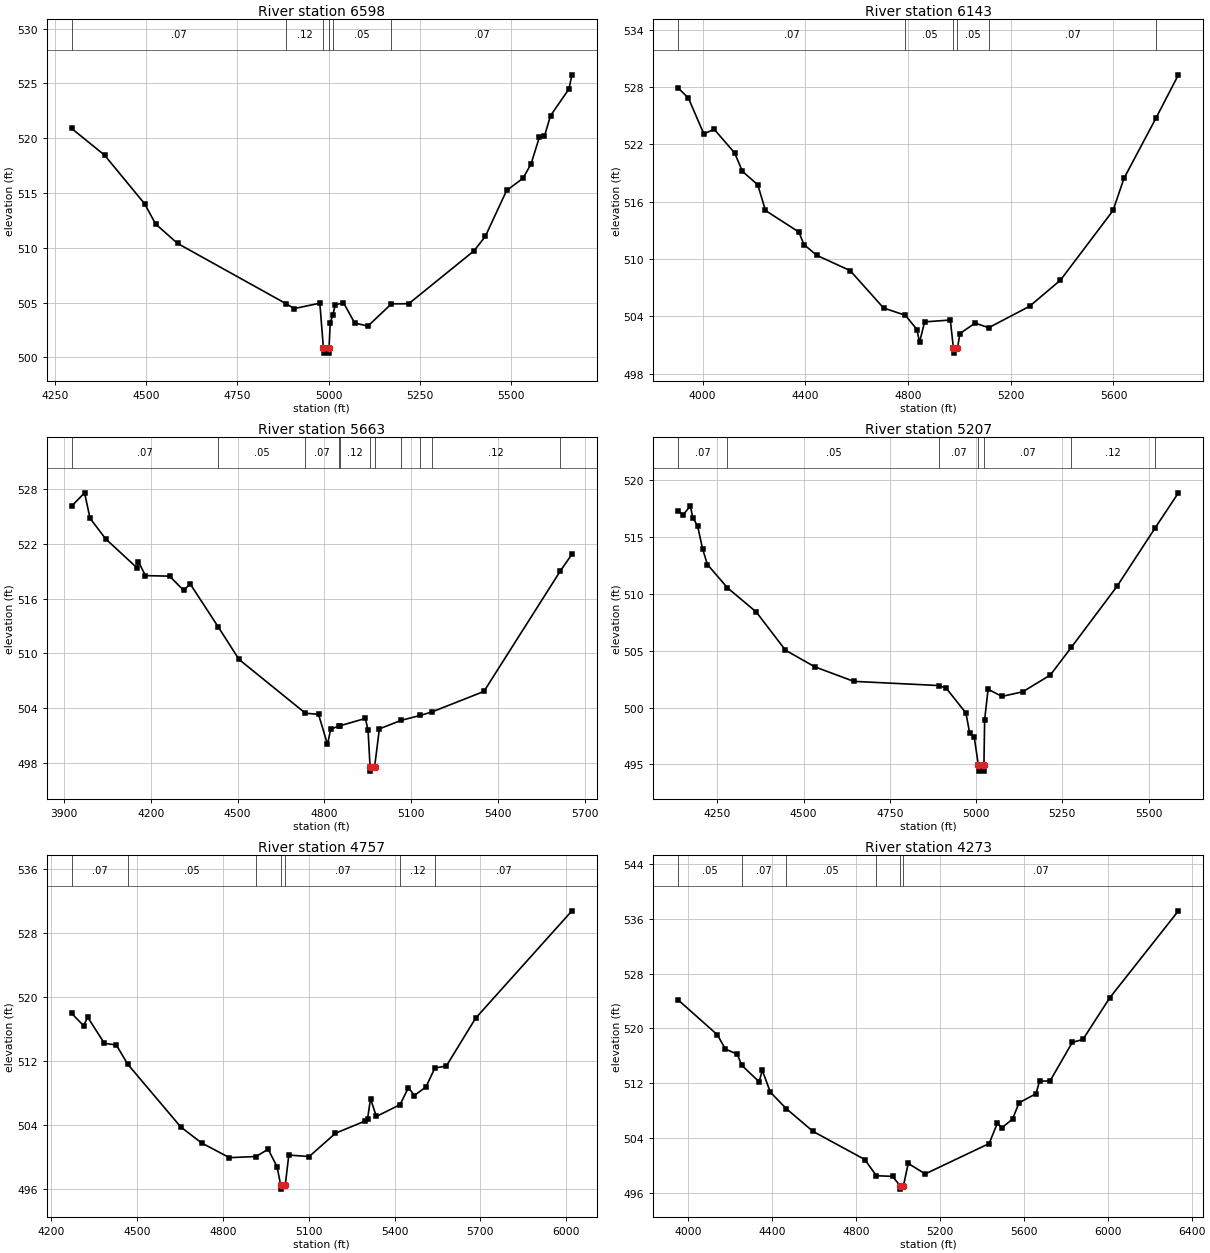
Type RM Length L Ch R = 1 ,6598    ,455,455,455
BEGIN DESCRIPTION:
COTTONWOOD TRIBUTARY 1 13.0
END DESCRIPTION:
XS GIS Cut Line= 3
      2298374.97       13724775.        2299075.       13724775.
      2299674.96     13724475.02
#Sta/Elev= 30
  4295.8  520.89  4385.8  518.46  4495.8  514.01  4525.8  512.17  4585.8   510.4
  4882.9   504.9  4905.8  504.45  4975.8  504.94  4985.5  500.88    4986  500.38
  5000.6  500.38  5001.1  500.88  5004.2  503.13    5011  503.84  5018.2  504.78
  5040.5  504.99  5071.3  503.13  5107.6  502.85    5172  504.88  5219.4  504.89
  5398.3  509.72  5429.1  511.03  5487.8  515.24  5532.5  516.34  5554.8  517.67
  5577.2  520.08  5591.2  520.18  5607.9  522.06  5658.3  524.49  5666.6  525.79
#Mann= 6 ,-1 , 0
  4295.8     .07       0  4882.9     .12       0  4985.5     .05       0
  5001.1     .12       0    5011     .05       0    5172     .07       0
Bank Sta=4985.5,5001.1
XS Rating Curve= 0 ,0
Exp/Cntr=0.3,0.1

Type RM Length L Ch R = 1 ,6143    ,480,480,480
BEGIN DESCRIPTION:
COTTONWOOD TRIBUTARY 1 12.0
END DESCRIPTION:
XS GIS Cut Line= 3
      2298125.03       13725175.        2299225.       13725175.
        2299825.       13724575.
#Sta/Elev= 30
  3904.6   527.9  3944.6  526.83  4004.6  523.09  4044.6  523.58  4124.6   521.1
  4154.6  519.18  4214.6  517.77  4244.6  515.08  4374.6  512.83  4394.6  511.51
  4444.6  510.39  4574.6  508.79  4704.6  504.88  4789.6  504.12  4834.6  502.63
  4844.6  501.29  4864.6  503.43  4964.6  503.62  4976.8  500.66  4977.3  500.16
  4992.4  500.66  5002.1  502.21  5061.1   503.3  5114.1  502.82  5273.3  505.06
  5393.5  507.79  5598.5  515.08    5641  518.44    5766  524.76  5853.1  529.27
#Mann= 6 ,-1 , 0
  3904.6     .07       0  4789.6     .05       0  4976.8     .05       0
  4992.4     .05       0  5114.1     .07       0    5766     .12       0
Bank Sta=4976.8,4992.4
XS Rating Curve= 0 ,0
Exp/Cntr=0.3,0.1

Type RM Length L Ch R = 1 ,5663    ,456,456,456
BEGIN DESCRIPTION:
COTTONWOOD TRIBUTARY 1 11.0
END DESCRIPTION:
XS GIS Cut Line= 3
      2298224.96     13725224.98        2299225.       13725625.
      2299825.02     13725875.01
#Sta/Elev= 30
  3927.2  526.14  3971.7  527.59  3990.5  524.81  4044.4  522.55  4152.1  519.39
  4157.5  520.06  4181.7  518.52  4265.2  518.46  4313.6  516.91  4336.5   517.6
  4432.8  512.92  4504.8  509.34  4734.4  503.44  4779.4  503.33  4810.4  500.02
  4821.2  501.67  4848.7  502.05  4854.5  502.08    4941  502.87  4950.4  501.62
  4957.3   497.6  4957.8   497.1  4973.2   497.6  4989.5  501.73  5064.5  502.66
    5130   503.2  5169.8  503.57  5350.4  505.83  5613.9  519.01  5654.3  520.86
#Mann= 11 ,-1 , 0
  3927.2     .07       0  4432.8     .05       0  4734.4     .07       0
  4848.7     .05       0  4854.5     .12       0  4957.3     .05       0
  4973.2     .12       0  5064.5     .12       0    5130     .07       0
  5169.8     .12       0  5613.9     .07       0
Bank Sta=4957.3,4973.2
XS Rating Curve= 0 ,0
Exp/Cntr=0.3,0.1

Type RM Length L Ch R = 1 ,5207    ,450,450,450
BEGIN DESCRIPTION:
COTTONWOOD TRIBUTARY 1 10.0
END DESCRIPTION:
XS GIS Cut Line= 3
      2298575.01     13725425.01        2299175.       13726025.
      2299775.01       13726075.
#Sta/Elev= 30
  4136.1   517.3  4150.2  516.93  4171.4  517.71  4178.5  516.69  4192.7  515.93
  4206.8  513.96  4220.9  512.57  4279.1  510.52  4362.4   508.4  4447.2  505.04
  4532.1  503.58  4645.2   502.3  4893.4  501.93  4913.9  501.68  4970.5  499.52
  4981.1   497.8  4994.6   497.4  5006.7  494.91  5007.2  494.41  5022.2  494.41
  5022.7  494.91  5024.8  498.93  5034.8   501.6  5074.9  500.98  5135.1  501.38
  5215.4  502.86  5276.2  505.29  5408.6  510.65  5519.3  515.79  5586.7  518.87
#Mann= 7 ,-1 , 0
  4136.1     .07       0  4279.1     .05       0  4893.4     .07       0
  5006.7     .05       0  5022.7     .07       0  5276.2     .12       0
  5519.3     .07       0
Bank Sta=5006.7,5022.7
XS Rating Curve= 0 ,0
Exp/Cntr=0.3,0.1

Type RM Length L Ch R = 1 ,4757    ,484,484,484
BEGIN DESCRIPTION:
COTTONWOOD TRIBUTARY 1 9.0
END DESCRIPTION:
XS GIS Cut Line= 3
      2298375.05     13726175.01        2299075.       13726375.
      2300075.03     13726174.99
#Sta/Elev= 30
    4272  517.94  4313.6  516.41  4327.9  517.46  4386.4   514.2    4428     514
  4467.5  511.61  4652.9  503.77  4725.7  501.77  4823.2  499.93  4916.1  500.07
  4958.4  500.98  4989.6   498.8  5002.2   496.5  5002.7     496  5018.2   496.5
  5030.6  500.25  5101.9  500.07  5193.7  502.98  5295.7  504.48  5305.9  504.81
  5316.1  507.29  5336.5  505.07  5419.4  506.55  5448.7  508.68  5469.1  507.69
  5509.9  508.76  5540.8  511.12  5581.2  511.38  5683.2  517.34  6019.8  530.75
#Mann= 7 ,-1 , 0
    4272     .07       0  4467.5     .05       0  4916.1     .07       0
  5002.2     .05       0  5018.2     .07       0  5419.4     .12       0
  5540.8     .07       0
Bank Sta=5002.2,5018.2
XS Rating Curve= 0 ,0
Exp/Cntr=0.3,0.1

Type RM Length L Ch R = 1 ,4273    ,443,443,443
BEGIN DESCRIPTION:
COTTONWOOD TRIBUTARY 1 8.0
END DESCRIPTION:
XS GIS Cut Line= 3
        2297975.       13726525.        2298975.       13726825.
      2300175.03     13727425.01
#Sta/Elev= 30
  3951.4  524.16  4138.5  519.07  4176.7  516.99  4233.3  516.25  4254.2  514.64
  4337.7  512.21  4352.5  513.91  4390.8  510.71  4466.5  508.31  4594.3  504.98
  4841.4  500.87  4896.5  498.51  4973.7  498.41  5009.6  497.05  5010.1  496.55
  5025.9  497.05  5048.5   500.3  5129.6  498.77  5434.3   503.2  5473.4  506.15
  5495.8  505.52  5546.1  506.78  5576.8  509.14  5657.9  510.48  5674.6   512.3
  5724.9  512.34  5831.2  517.98  5881.5  518.39    6010  524.49  6337.1  537.17
#Mann= 6 ,-1 , 0
  3951.4     .05       0  4254.2     .07       0  4466.5     .05       0
  4896.5     .07       0  5009.6     .05       0  5025.9     .07       0
Bank Sta=5009.6,5025.9
XS Rating Curve= 0 ,0
Exp/Cntr=0.3,0.1

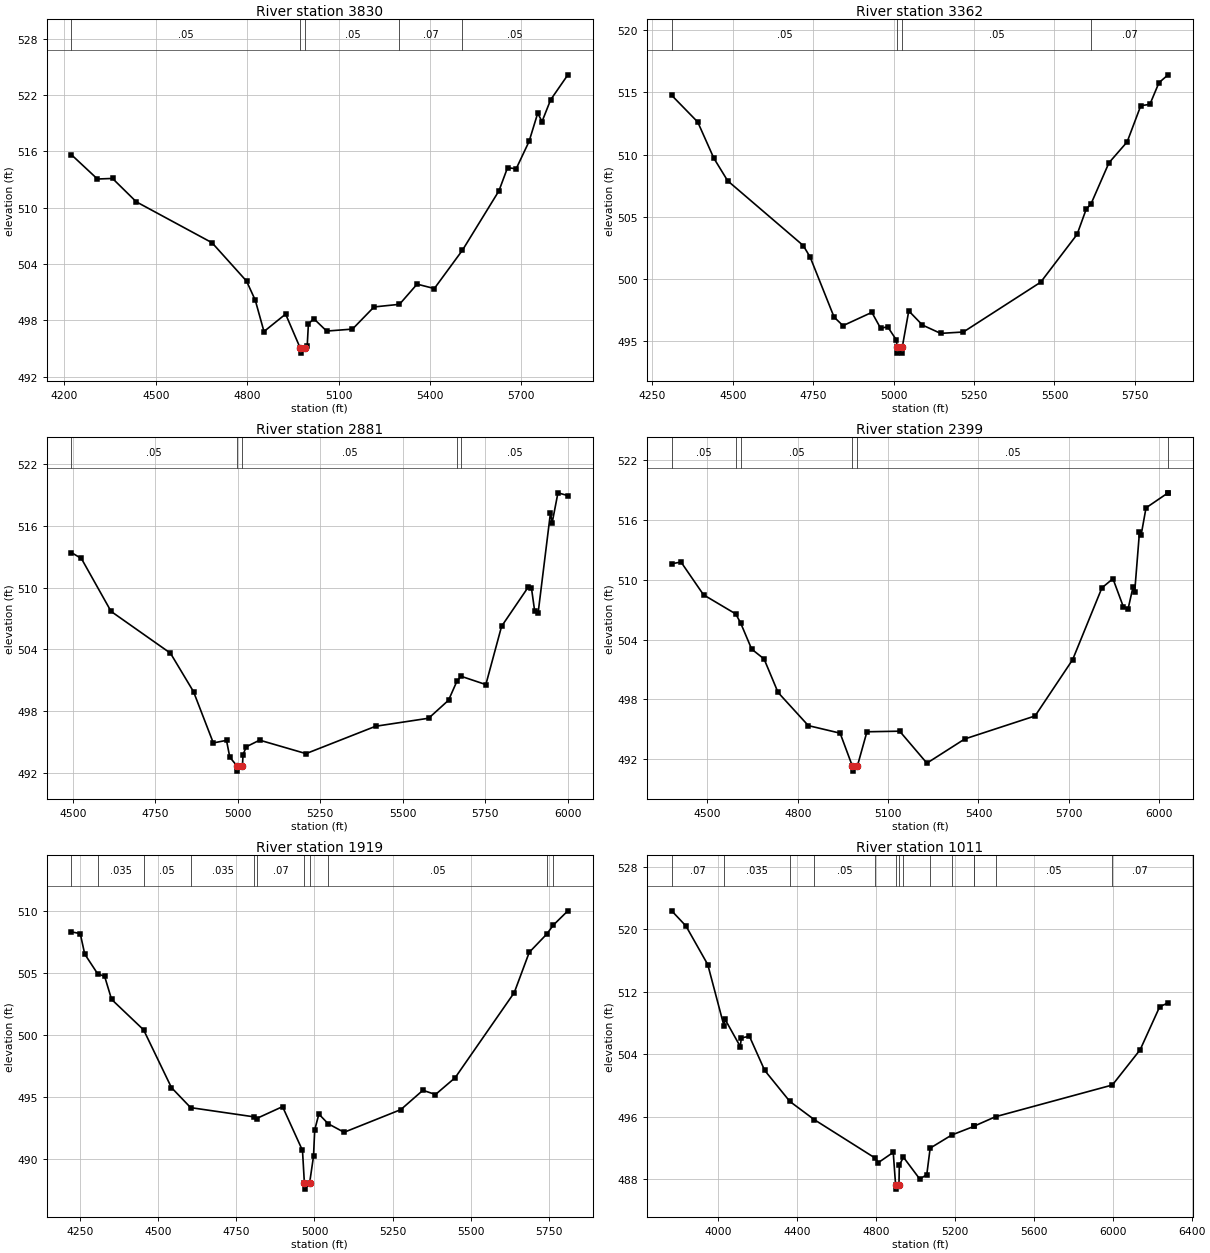
Type RM Length L Ch R = 1 ,3830    ,468,468,468
BEGIN DESCRIPTION:
COTTONWOOD TRIBUTARY 1 7.0
END DESCRIPTION:
XS GIS Cut Line= 3
      2298225.03     13726725.02        2298825.       13727225.
      2299424.99     13727824.99
#Sta/Elev= 30
  4223.2  515.63  4308.4  513.05  4357.9  513.11    4436  510.62  4684.6  506.26
  4797.9  502.17  4826.5  500.14  4855.1   496.8  4926.1  498.66  4974.6     495
  4975.1   494.5  4990.9     495    4997  495.26  5000.9  497.59  5018.3  498.18
  5060.8  496.85  5145.6  497.06  5216.3  499.42  5299.9   499.7  5357.7  501.85
  5414.3  501.38  5506.7  505.47  5626.4  511.79  5654.7  514.26    5683  514.14
  5725.4  517.06  5753.7  520.06  5767.9  519.17  5796.1  521.49  5852.7  524.15
#Mann= 5 ,-1 , 0
  4223.2     .05       0  4974.6     .05       0  4990.9     .05       0
  5299.9     .07       0  5506.7     .05       0
Bank Sta=4974.6,4990.9
XS Rating Curve= 0 ,0
Exp/Cntr=0.3,0.1

Type RM Length L Ch R = 1 ,3362    ,481,481,481
BEGIN DESCRIPTION:
COTTONWOOD TRIBUTARY 1 6.0
END DESCRIPTION:
XS GIS Cut Line= 3
      2298125.02     13726925.03        2298475.       13727525.
      2299074.99     13728124.99
#Sta/Elev= 30
    4310  514.77    4391  512.62    4441  509.71    4484  507.89  4718.9  502.68
  4740.4  501.75  4814.8  496.92  4842.5  496.23  4932.2   497.3  4959.5  496.02
  4981.4  496.14  5008.1  495.09  5010.5  494.52    5011  494.02  5026.4  494.02
  5026.9  494.52    5047  497.42  5089.4  496.28    5146  495.61  5216.7  495.72
  5457.1  499.73  5570.3  503.58  5598.6  505.61    5613     506  5669.3  509.34
  5725.8  511.02  5768.3  513.94  5796.5  514.04  5824.8  515.79  5853.1  516.42
#Mann= 4 ,-1 , 0
    4310     .05       0  5010.5     .05       0  5026.9     .05       0
    5613     .07       0
Bank Sta=5010.5,5026.9
XS Rating Curve= 0 ,0
Exp/Cntr=0.3,0.1

Type RM Length L Ch R = 1 ,2881    ,482,482,482
BEGIN DESCRIPTION:
COTTONWOOD TRIBUTARY 1 5.0
END DESCRIPTION:
XS GIS Cut Line= 3
        2298025.     13727024.97        2298025.       13727525.
        2298125.     13728524.99
#Sta/Elev= 30
  4495.9  513.41  4525.9  512.84  4615.9   507.7  4795.9  503.64  4865.9   499.9
  4925.9  494.92  4965.9  495.17  4975.9  493.53  4997.8  492.68  4998.3  492.18
  5014.2  492.68    5016  493.79  5026.1  494.55  5066.3  495.19    5207  493.88
    5418  496.54  5578.8  497.32  5639.1  499.07  5664.3   500.9  5676.8   501.4
  5752.2  500.59  5799.9  506.25  5880.3  510.04  5890.4  509.99  5900.4  507.69
  5910.5   507.5  5948.2   517.3  5953.2   516.3  5970.8  519.22  6000.9  518.95
#Mann= 5 ,-1 , 0
  4495.9     .05       0  4997.8     .05       0  5014.2     .05       0
  5664.3     .07       0  5676.8     .05       0
Bank Sta=4997.8,5014.2
XS Rating Curve= 0 ,0
Exp/Cntr=0.3,0.1

Type RM Length L Ch R = 1 ,2399    ,480,480,480
BEGIN DESCRIPTION:
COTTONWOOD TRIBUTARY 1 4.0
END DESCRIPTION:
XS GIS Cut Line= 3
      2297725.01     13727024.97        2297575.       13727625.
      2298075.02     13728525.04
#Sta/Elev= 30
  4381.5  511.62  4412.5  511.79  4487.2   508.5  4594.2  506.58  4610.3  505.68
    4647  503.05  4688.2  502.06  4734.6   498.7  4835.1  495.37  4940.7  494.61
  4981.4   491.3  4981.9   490.8  4997.9   491.3  5029.7  494.75  5138.4  494.81
  5228.8   491.6  5354.6  494.03    5588  496.34  5712.7  501.99  5809.9   509.2
  5846.5  510.12  5880.8  507.32  5896.9   507.1  5912.9  509.24  5918.6  508.75
  5934.6   514.8  5940.3  514.53  5956.3  517.23  6029.5  518.74  6029.6  518.74
#Mann= 6 ,-1 , 0
  4381.5     .05       0  4594.2    .035       0  4610.3     .05       0
  4981.4     .05       0  4997.9     .05       0  6029.5     .07       0
Bank Sta=4981.4,4997.9
XS Rating Curve= 0 ,0
Exp/Cntr=0.3,0.1

Type RM Length L Ch R = 1 ,1919    ,908,908,908
BEGIN DESCRIPTION:
COTTONWOOD TRIBUTARY 1 3.0
END DESCRIPTION:
XS GIS Cut Line= 3
      2297625.01     13727124.99        2297125.       13727725.
        2297225.     13728525.04
#Sta/Elev= 30
    4223  508.34    4251   508.2  4265.3  506.55  4306.3  504.97  4329.1  504.74
  4351.2  502.89  4453.6  500.43  4542.6  495.77    4604  494.15  4808.2   493.4
  4814.8  493.27  4897.9  494.23  4961.7  490.69  4967.7  488.07  4968.2  487.57
  4984.5  488.07  4996.9  490.22  5000.8  492.36  5014.1  493.63  5043.7  492.85
  5094.7  492.16  5276.1  493.99  5346.7  495.55    5387  495.21    5450  496.57
  5638.9  503.44  5686.8  506.69  5742.7  508.16  5763.5  508.88  5810.3  510.04
#Mann= 11 ,-1 , 0
    4223     .05       0  4306.3    .035       0  4453.6     .05       0
    4604    .035       0  4808.2     .05       0  4814.8     .07       0
  4967.7     .05       0  4984.5     .07       0  5043.7     .05       0
  5742.7     .07       0  5763.5     .05       0
Bank Sta=4967.7,4984.5
XS Rating Curve= 0 ,0
Exp/Cntr=0.3,0.1

Type RM Length L Ch R = 1 ,1011    ,469,469,469
BEGIN DESCRIPTION:
COTTONWOOD TRIBUTARY 1 2.0
END DESCRIPTION:
XS GIS Cut Line= 3
        2296075.     13726324.99        2296375.       13727525.
      2297175.02     13728525.03
#Sta/Elev= 30
  3762.8  522.37    3835  520.43  3945.8  515.48  4027.6  507.66  4033.4  508.47
  4110.7  504.98  4115.8  506.09  4157.1   506.3  4234.4  501.93  4362.1  497.95
  4486.6  495.61  4793.3  490.72  4811.6  490.13  4886.4  491.43  4898.5  487.22
    4899  486.72  4915.4  487.22  4917.3  489.81  4938.4   490.8  5021.3     488
  5056.6  488.59  5073.7  491.97  5182.8  493.65  5294.7  494.75  5297.6   494.8
  5405.7     496  5997.9  500.06  6138.7  504.57  6237.9  510.09  6280.4  510.57
#Mann= 14 ,-1 , 0
  3762.8     .07       0  4027.6    .035       0  4362.1     .07       0
  4486.6     .05       0  4793.3     .12       0  4898.5     .05       0
  4915.4     .12       0  4938.4     .07       0  5073.7     .05       0
  5182.8     .07       0  5294.7     .05       0  5297.6     .07       0
  5405.7     .05       0  5997.9     .07       0
Bank Sta=4898.5,4915.4
XS Rating Curve= 0 ,0
Exp/Cntr=0.3,0.1

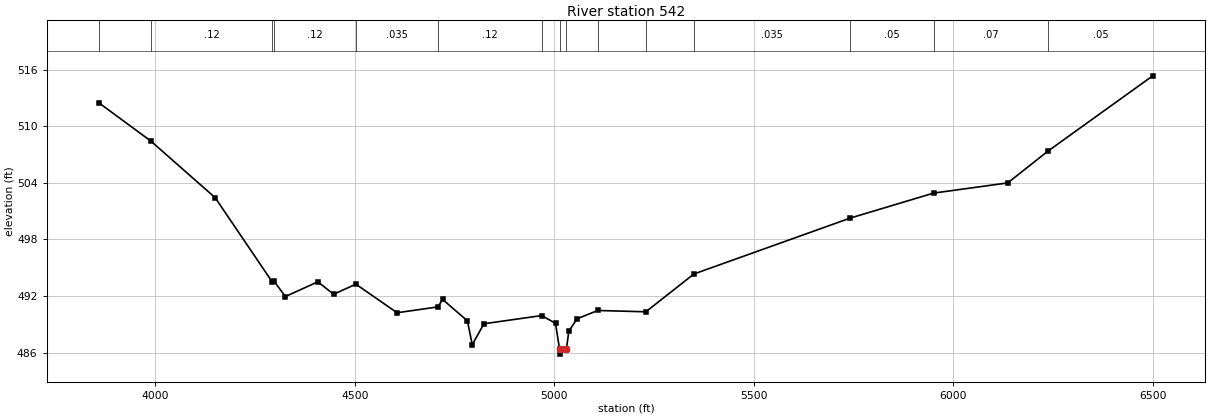
Type RM Length L Ch R = 1 ,542     ,0,0,0
BEGIN DESCRIPTION:
COTTONWOOD TRIBUTARY 1 1.0
END DESCRIPTION:
XS GIS Cut Line= 3
      2295775.01     13726725.04        2296075.       13727825.
      2297274.97     13728724.98
#Sta/Elev= 30
  3859.9  512.46  3988.4  508.46  4150.1  502.44  4293.2   493.5    4297  493.61
  4326.3  491.95  4407.5  493.51  4447.2  492.19  4502.8  493.26  4606.2  490.23
  4708.5  490.85  4720.2  491.64  4782.4  489.37  4794.5  486.84  4823.8  489.06
  4968.4  489.93  5003.2  489.11  5013.4  486.34  5013.9  485.84  5030.4  486.34
  5036.5  488.27  5057.3  489.59  5109.2  490.47  5229.6  490.33    5350  494.34
  5741.8  500.27  5950.6  502.92  6136.5     504  6237.5  507.38    6500  515.36
#Mann= 15 ,-1 , 0
  3859.9     .07       0  3988.4     .12       0  4293.2     .07       0
    4297     .12       0  4502.8    .035       0  4708.5     .12       0
  4968.4     .05       0  5013.4     .05       0  5030.4     .05       0
  5109.2     .05       0  5229.6     .07       0    5350    .035       0
  5741.8     .05       0  5950.6     .07       0  6237.5     .05       0
Bank Sta=5013.4,5030.4
XS Rating Curve= 0 ,0
Exp/Cntr=0.3,0.1

Chan Stop Cuts=-1
Use User Specified Reach Order=0
Composite Channel Slope=5