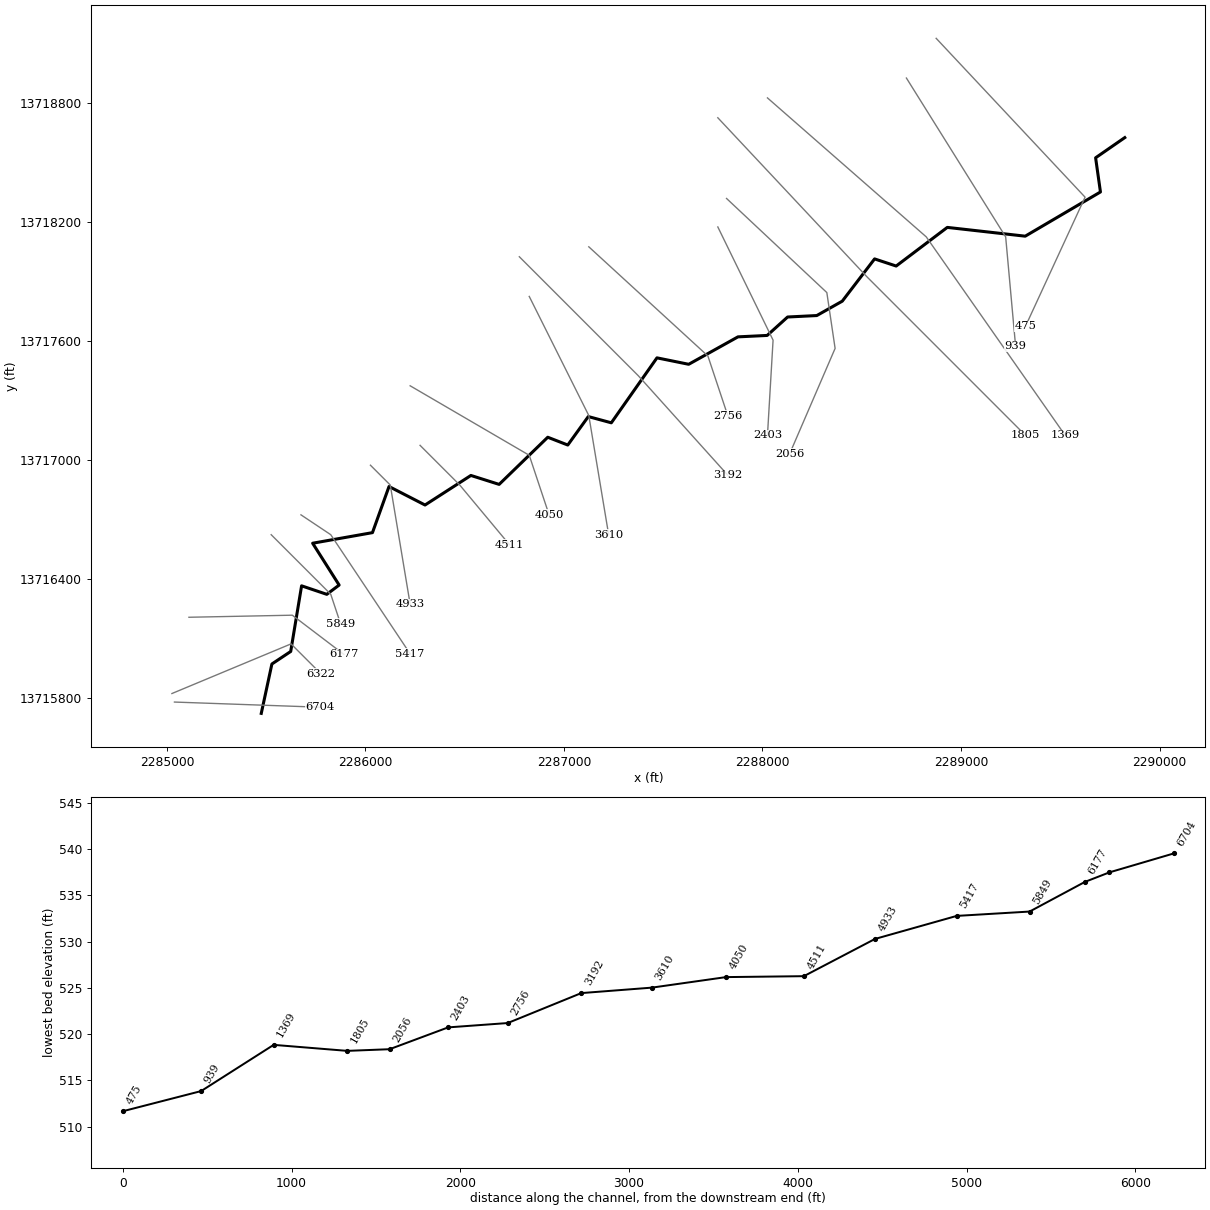
--- COTTONWOOD TRIBUTARY 2.prj (project) ---

Proj Title=COTTONWOOD TRIBUTARY 2 Base Level Engineering
Current Plan=p01
Default Exp/Contr=0.3,0.1
English Units
Geom File=g01
Flow File=f01
Plan File=p01
BEGIN DESCRIPTION:
COTTONWOOD TRIBUTARY 2
END DESCRIPTION:

--- COTTONWOOD TRIBUTARY 2.p01 (plan) ---

Plan Title=Multiple Run
Short Identifier=Multiple
Geom File=g01
Flow File=f01
Subcritical Flow
K Sum by GR= 0
Std Step Tol= 0.01
Critical Tol= 0.01
Num of Std Step Trials= 20
Max Error Tol= 0.3
Flow Tol Ratio= 0.001
Split Flow NTrial= 30
Split Flow Tol= 0.02
Split Flow Ratio= 0.02
Log Output Level= 0
Friction Slope Method= 1
Unsteady Friction Slope Method= 2
Unsteady Bridges Friction Slope Method= 1
Parabolic Critical Depth
Global Vel Dist=  1 , 1 , 1
Global Log Level= 0
CheckData=True
Encroach Param= -1, 0, 0, 0
BEGIN DESCRIPTION:
Multiple Run
END DESCRIPTION:

--- COTTONWOOD TRIBUTARY 2.f01 (steady flow) ---

Flow Title=Multiple
Number of Profiles=7
Profile Names=10-year,25-year,50-year,1pct_min,100-year,1pct_plu,500-year
River Rch & RM= COTTONWOOD TRIBU,Reach-1,6704
     571     916    1226     794    1584    3160    2618
River Rch & RM= COTTONWOOD TRIBU,Reach-1,1805
     807    1323    1795    1177    2349    4688    3993
Boundary for River Rch & Prof#=COTTONWOOD TRIBU,Reach-1,1
Up Type=0
Dn Type=3
Dn Slope=0.005
Boundary for River Rch & Prof#=COTTONWOOD TRIBU,Reach-1,2
Up Type=0
Dn Type=3
Dn Slope=0.005
Boundary for River Rch & Prof#=COTTONWOOD TRIBU,Reach-1,3
Up Type=0
Dn Type=3
Dn Slope=0.005
Boundary for River Rch & Prof#=COTTONWOOD TRIBU,Reach-1,4
Up Type=0
Dn Type=3
Dn Slope=0.005
Boundary for River Rch & Prof#=COTTONWOOD TRIBU,Reach-1,5
Up Type=0
Dn Type=3
Dn Slope=0.005
Boundary for River Rch & Prof#=COTTONWOOD TRIBU,Reach-1,6
Up Type=0
Dn Type=3
Dn Slope=0.005
Boundary for River Rch & Prof#=COTTONWOOD TRIBU,Reach-1,7
Up Type=0
Dn Type=3
Dn Slope=0.005

--- COTTONWOOD TRIBUTARY 2.g01 (geometry) ---

Geom Title=Existing Conditions

River Reach=COTTONWOOD TRIBU,Reach-1
Reach XY= 30
      2285475.00     13715725.00      2285528.55     13715973.70
      2285623.35     13716036.83      2285678.15     13716367.42
      2285805.09     13716324.61      2285867.33     13716371.27
      2285733.82     13716582.00      2286035.18     13716635.32
      2286118.62     13716867.68      2286299.97     13716774.50
      2286531.04     13716923.37      2286673.28     13716878.34
      2286918.25     13717115.86      2287019.13     13717076.58
      2287122.46     13717219.99      2287238.41     13717188.53
      2287468.33     13717515.71      2287628.22     13717483.27
      2287876.47     13717621.44      2288023.53     13717628.56
      2288126.47     13717721.44      2288273.44     13717728.76
      2288401.86     13717801.20      2288564.63     13718014.05
      2288673.35     13717978.16      2288930.93     13718172.77
      2289323.53     13718128.55      2289702.45     13718351.16
      2289678.11     13718523.38      2289825.00     13718625.00

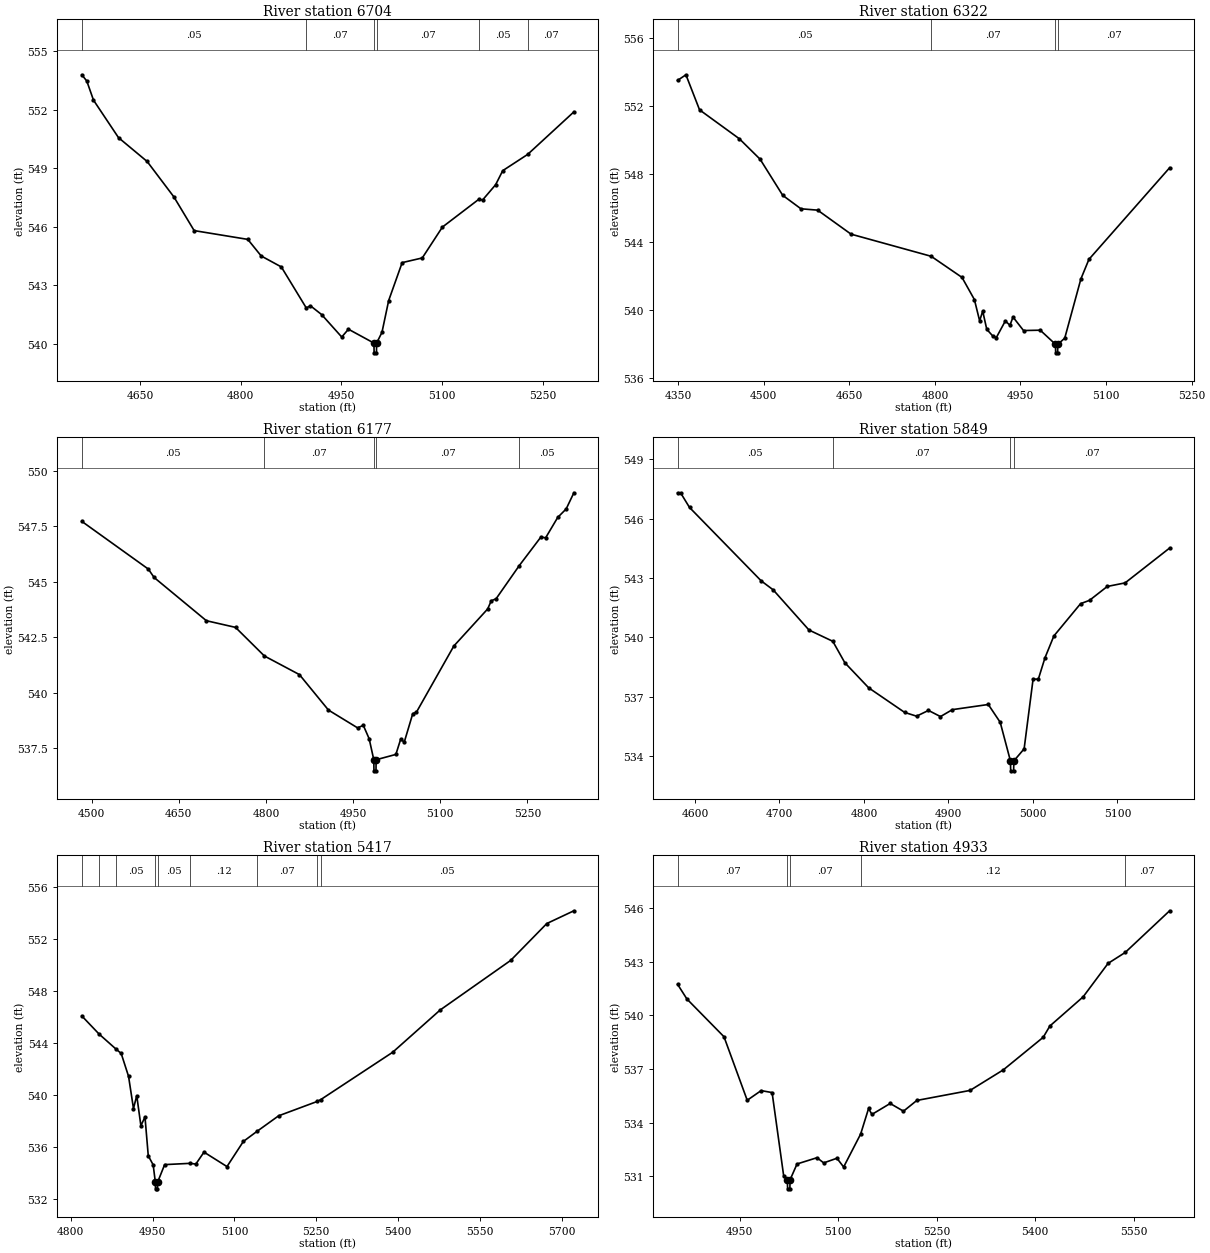
Type RM Length L Ch R = 1,6704,382,382,382
BEGIN DESCRIPTION:
X18668
END DESCRIPTION:
XS GIS Cut Line= 2
      2285037.65     13715782.02      2285770.99     13715756.02
#Sta/Elev= 30
  4562.9  553.79  4570.3  553.47  4580.3  552.49  4617.6  550.57  4660.3  549.35
  4700.3  547.53  4730.4  545.81  4810.4  545.36  4830.4  544.51  4860.4  543.95
  4897.6  541.85  4903.8  541.96  4920.5  541.51  4950.5  540.36  4960.5  540.76
  4998.5  540.05  4998.8  539.55  5002.3  539.55  5002.5  540.05  5010.5  540.60
  5020.5  542.23  5040.6  544.17  5070.6  544.41  5100.6  545.99  5154.8  547.41
  5160.6  547.38  5180.0  548.16  5190.6  548.88  5227.7  549.71  5296.7  551.89
#Mann=6,-1,0
  4562.9    0.05       0  4897.6    0.07       0  4998.5    0.05       0
  5002.5    0.07       0  5154.8    0.05       0  5227.7    0.07       0
Bank Sta=4998.5,5002.5
Exp/Cntr=0.3,0.1

Type RM Length L Ch R = 1,6322,145,145,145
BEGIN DESCRIPTION:
COTTONWOOD TRIBUTARY 2 14.0
END DESCRIPTION:
XS GIS Cut Line= 3
      2285025.00     13715825.00      2285625.00     13716075.00
      2285774.98     13715925.02
#Sta/Elev= 30
  4349.2  553.50  4363.8  553.83  4387.7  551.77  4457.5  550.07  4493.8  548.87
  4533.4  546.75  4565.3  545.96  4594.6  545.88  4653.1  544.47  4793.5  543.17
  4847.5  541.93  4869.2  540.63  4878.4  539.38  4883.8  539.95  4890.9  538.88
  4901.7  538.48  4907.7  538.40  4923.4  539.37  4931.5  539.12  4936.9  539.60
  4955.3  538.81  4984.6  538.83  5011.3  538.00  5011.6  537.50  5015.1  537.50
  5015.3  538.00  5027.5  538.36  5055.8  541.84  5069.9  542.99  5211.3  548.37
#Mann=4,-1,0
  4349.2    0.05       0  4793.5    0.07       0  5011.3    0.05       0
  5015.3    0.07       0
Bank Sta=5011.3,5015.3
Exp/Cntr=0.3,0.1

Type RM Length L Ch R = 1,6177,328,328,328
BEGIN DESCRIPTION:
X18669
END DESCRIPTION:
XS GIS Cut Line= 3
      2285110.59     13716209.10      2285631.42     13716219.52
      2285890.94     13716022.28
#Sta/Elev= 30
  4483.1  547.72  4597.5  545.57  4607.5  545.19  4697.5  543.24  4747.6  542.94
  4797.3  541.65  4857.6  540.81  4907.6  539.21  4957.6  538.41  4967.6  538.52
  4977.6  537.92  4985.6  536.97  4985.9  536.47  4989.4  536.47  4989.6  536.97
  5023.6  537.21  5031.8  537.89  5038.1  537.77  5052.7  539.05  5058.9  539.11
  5123.4  542.10  5181.6  543.77  5187.8  544.14  5196.1  544.23  5236.1  545.73
  5273.1  547.01  5281.4  546.98  5302.2  547.90  5316.7  548.28  5330.0  549.01
#Mann=5,-1,0
  4483.1    0.05       0  4797.3    0.07       0  4985.6    0.05       0
  4989.6    0.07       0  5236.1    0.05       0
Bank Sta=4985.6,4989.6
Exp/Cntr=0.3,0.1

Type RM Length L Ch R = 1,5849,432,432,432
BEGIN DESCRIPTION:
COTTONWOOD TRIBUTARY 2 13.0
END DESCRIPTION:
XS GIS Cut Line= 3
      2285525.03     13716624.97      2285825.00     13716325.00
      2285874.99     13716175.03
#Sta/Elev= 30
  4579.5  547.30  4583.0  547.30  4593.6  546.56  4678.5  542.85  4692.6  542.40
  4735.0  540.37  4763.2  539.80  4777.4  538.72  4805.7  537.45  4848.2  536.21
  4862.3  536.02  4876.4  536.31  4890.6  536.00  4904.7  536.35  4947.2  536.61
  4961.3  535.71  4973.4  533.76  4973.7  533.26  4977.2  533.26  4977.4  533.76
  4989.6  534.37  5000.2  537.89  5006.4  537.89  5014.3  538.97  5024.8  540.07
  5056.4  541.70  5067.0  541.87  5088.0  542.57  5109.1  542.75  5161.8  544.51
#Mann=4,-1,0
  4579.5    0.05       0  4763.2    0.07       0  4973.4    0.05       0
  4977.4    0.07       0
Bank Sta=4973.4,4977.4
Exp/Cntr=0.3,0.1

Type RM Length L Ch R = 1,5417,484,484,484
BEGIN DESCRIPTION:
COTTONWOOD TRIBUTARY 2 12.0
END DESCRIPTION:
XS GIS Cut Line= 3
      2285675.01     13716724.99      2285825.00     13716625.00
      2286225.01     13716024.98
#Sta/Elev= 30
  4820.5  546.07  4852.1  544.68  4882.2  543.56  4892.6  543.19  4906.1  541.43
  4915.1  538.96  4921.1  539.95  4928.7  537.64  4936.2  538.31  4942.2  535.33
  4951.2  534.63  4955.2  533.29  4955.5  532.79  4959.0  532.79  4959.2  533.29
  4972.2  534.65  5019.4  534.75  5029.3  534.69  5044.3  535.61  5086.4  534.50
  5116.4  536.43  5141.2  537.20  5181.0  538.40  5251.5  539.50  5258.0  539.64
  5389.9  543.28  5477.0  546.53  5606.2  550.34  5672.3  553.17  5721.9  554.15
#Mann=9,-1,0
  4820.5    0.05       0  4852.1    0.07       0  4882.2    0.05       0
  4955.2    0.05       0  4959.2    0.05       0  5019.4    0.12       0
  5141.2    0.07       0  5251.5    0.12       0  5258.0    0.05       0
Bank Sta=4955.2,4959.2
Exp/Cntr=0.3,0.1

Type RM Length L Ch R = 1,4933,422,422,422
BEGIN DESCRIPTION:
COTTONWOOD TRIBUTARY 2 11.0
END DESCRIPTION:
XS GIS Cut Line= 3
      2286024.98     13716975.02      2286125.00     13716875.00
      2286225.00     13716275.02
#Sta/Elev= 30
  4855.1  541.73  4869.3  540.91  4925.8  538.80  4961.2  535.25  4982.4  535.79
  4999.1  535.68  5016.8  531.01  5022.4  530.80  5022.7  530.30  5026.2  530.30
  5026.4  530.80  5037.1  531.69  5067.5  532.04  5077.7  531.75  5097.9  532.01
  5108.1  531.52  5134.0  533.36  5146.1  534.79  5151.2  534.46  5179.0  535.07
  5199.3  534.64  5219.6  535.24  5300.7  535.80  5351.4  536.95  5412.2  538.77
  5422.3  539.40  5473.0  541.03  5511.0  542.90  5537.1  543.51  5604.8  545.84
#Mann=5,-1,0
  4855.1    0.07       0  5022.4    0.05       0  5026.4    0.07       0
  5134.0    0.12       0  5537.1    0.07       0
Bank Sta=5022.4,5026.4
Exp/Cntr=0.3,0.1

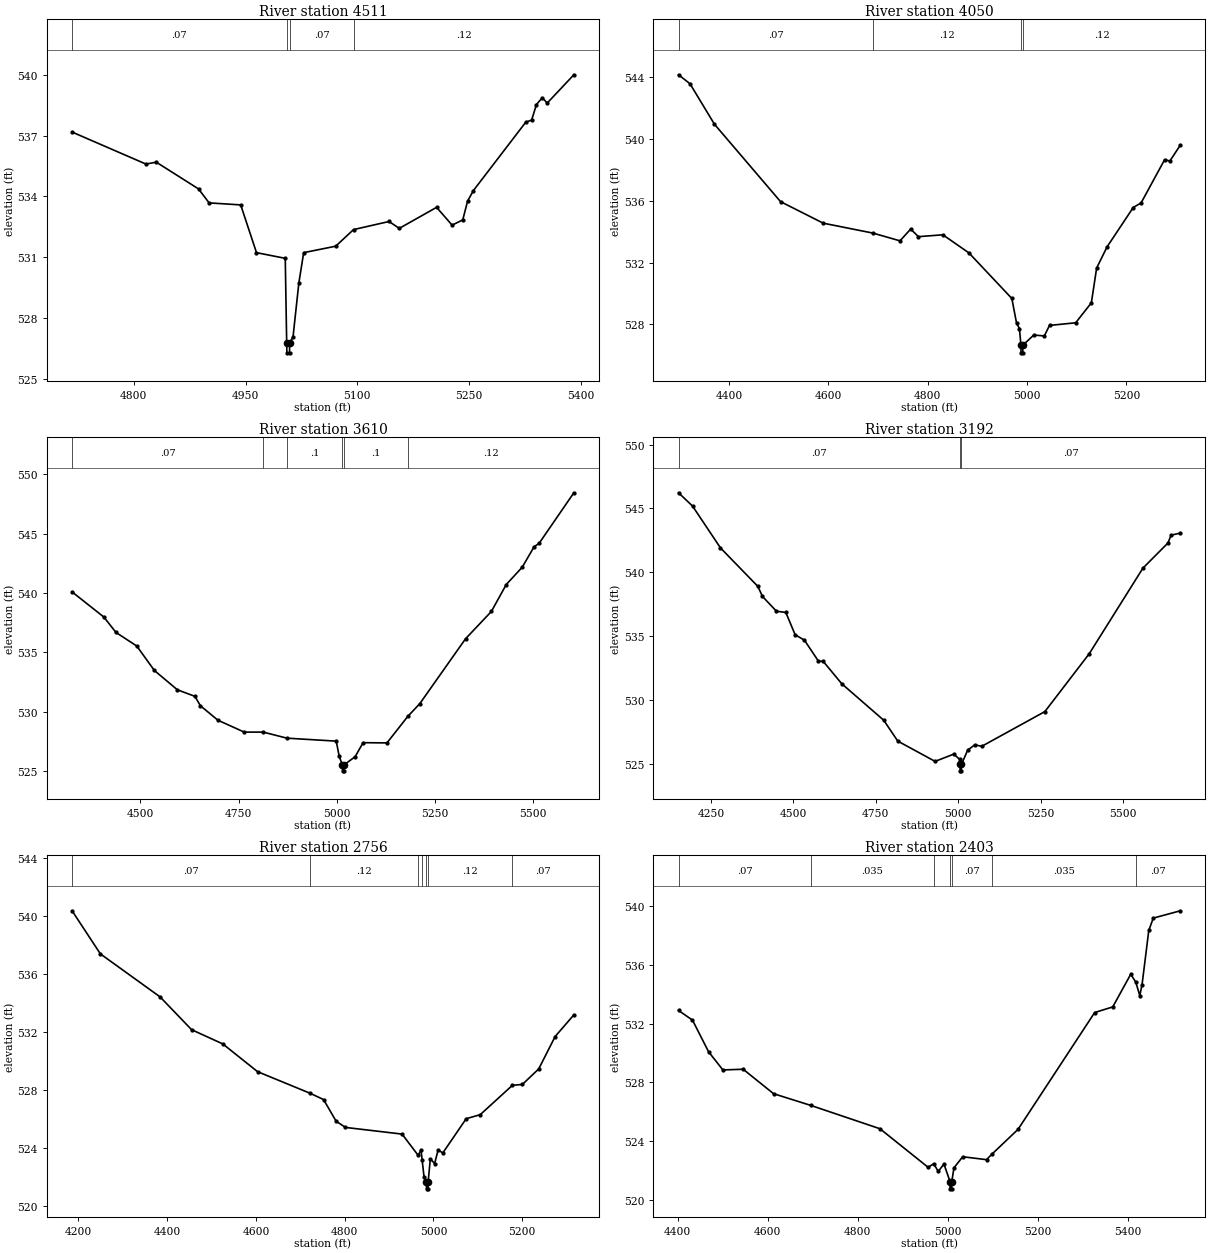
Type RM Length L Ch R = 1,4511,461,461,461
BEGIN DESCRIPTION:
COTTONWOOD TRIBUTARY 2 10.0
END DESCRIPTION:
XS GIS Cut Line= 3
      2286275.00     13717075.00      2286475.00     13716875.00
      2286725.03     13716574.97
#Sta/Elev= 30
  4717.2  537.18  4816.2  535.60  4830.3  535.69  4886.9  534.37  4901.1  533.68
  4943.5  533.58  4964.7  531.22  5003.3  530.94  5005.2  526.77  5005.5  526.27
  5009.0  526.27  5009.2  526.77  5013.7  527.05  5021.5  529.71  5028.0  531.22
  5071.0  531.54  5094.9  532.36  5142.6  532.76  5156.3  532.42  5206.4  533.46
  5227.2  532.58  5241.5  532.84  5248.0  533.77  5255.8  534.29  5326.1  537.67
  5333.9  537.77  5340.4  538.54  5348.3  538.88  5354.8  538.61  5390.6  540.01
#Mann=4,-1,0
  4717.2    0.07       0  5005.2    0.05       0  5009.2    0.07       0
  5094.9    0.12       0
Bank Sta=5005.2,5009.2
Exp/Cntr=0.3,0.1

Type RM Length L Ch R = 1,4050,440,440,440
BEGIN DESCRIPTION:
COTTONWOOD TRIBUTARY 2 9.0
END DESCRIPTION:
XS GIS Cut Line= 3
      2286225.03     13717374.98      2286825.00     13717025.00
      2286924.99     13716725.02
#Sta/Elev= 30
  4298.0  544.12  4321.1  543.54  4370.3  540.93  4503.5  535.93  4589.5  534.54
  4689.6  533.90  4744.1  533.40  4765.6  534.16  4781.3  533.67  4830.5  533.79
  4883.0  532.62  4969.4  529.68  4978.9  528.09  4984.7  527.74  4987.7  526.67
  4987.9  526.17  4991.4  526.17  4991.7  526.67  5013.7  527.32  5034.8  527.26
  5045.3  527.94  5098.0  528.11  5129.6  529.40  5140.2  531.64  5161.2  533.01
  5213.9  535.55  5229.8  535.85  5277.2  538.64  5287.7  538.55  5308.8  539.58
#Mann=4,-1,0
  4298.0    0.07       0  4689.6    0.12       0  4987.7    0.05       0
  4991.7    0.12       0
Bank Sta=4987.7,4991.7
Exp/Cntr=0.3,0.1

Type RM Length L Ch R = 1,3610,418,418,418
BEGIN DESCRIPTION:
COTTONWOOD TRIBUTARY 2 8.0
END DESCRIPTION:
XS GIS Cut Line= 3
      2286824.98     13717825.04      2287125.00     13717225.00
      2287224.99     13716625.04
#Sta/Elev= 30
  4325.6  540.09  4406.7  537.97  4437.4  536.68  4490.6  535.53  4535.3  533.48
  4594.0  531.85  4638.7  531.30  4652.7  530.51  4697.4  529.29  4764.5  528.29
  4813.0  528.29  4873.2  527.78  4999.0  527.53  5006.6  526.24  5014.7  525.53
  5015.0  525.03  5018.5  525.03  5018.7  525.53  5047.2  526.22  5067.4  527.40
  5128.3  527.38  5181.6  529.62  5211.9  530.68  5328.5  536.14  5394.4  538.44
  5432.4  540.71  5472.9  542.16  5503.4  543.89  5516.0  544.17  5604.7  548.43
#Mann=6,-1,0
  4325.6    0.07       0  4813.0    0.12       0  4873.2     0.1       0
  5014.7    0.05       0  5018.7     0.1       0  5181.6    0.12       0
Bank Sta=5014.7,5018.7
Exp/Cntr=0.3,0.1

Type RM Length L Ch R = 1,3192,436,436,436
BEGIN DESCRIPTION:
COTTONWOOD TRIBUTARY 2 7.0
END DESCRIPTION:
XS GIS Cut Line= 3
      2286775.03     13718024.97      2287375.00     13717425.00
      2287825.02     13716924.97
#Sta/Elev= 30
  4151.8  546.22  4194.2  545.18  4279.0  541.90  4392.2  538.89  4406.3  538.10
  4448.7  536.94  4477.0  536.85  4505.3  535.10  4533.6  534.67  4576.0  533.03
  4590.2  533.02  4646.7  531.26  4774.0  528.40  4816.4  526.77  4929.6  525.18
  4986.1  525.75  5003.6  525.35  5005.4  524.94  5005.6  524.44  5009.1  524.44
  5009.4  524.94  5028.3  526.06  5050.0  526.48  5070.9  526.36  5262.3  529.08
  5396.8  533.61  5559.7  540.32  5635.6  542.29  5644.9  542.90  5673.0  543.06
#Mann=3,-1,0
  4151.8    0.07       0  5005.4    0.05       0  5009.4    0.07       0
Bank Sta=5005.4,5009.4
Exp/Cntr=0.3,0.1

Type RM Length L Ch R = 1,2756,353,353,353
BEGIN DESCRIPTION:
COTTONWOOD TRIBUTARY 2 6.0
END DESCRIPTION:
XS GIS Cut Line= 3
      2287125.00     13718075.00      2287725.00     13717525.00
      2287825.01     13717224.97
#Sta/Elev= 30
  4186.0  540.35  4249.8  537.38  4384.2  534.42  4455.2  532.16  4525.5  531.18
  4603.8  529.27  4722.3  527.78  4752.4  527.35  4780.7  525.86  4801.7  525.43
  4929.3  524.97  4965.7  523.50  4971.9  523.89  4974.5  523.18  4978.7  522.04
  4984.1  521.70  4984.3  521.20  4987.8  521.20  4988.1  521.70  4992.9  523.27
  5002.6  522.94  5010.5  523.88  5021.0  523.67  5073.7  526.03  5105.4  526.31
  5177.8  528.33  5200.2  528.39  5237.1  529.46  5274.0  531.69  5316.2  533.18
#Mann=7,-1,0
  4186.0    0.07       0  4722.3    0.12       0  4965.7    0.07       0
  4974.5    0.12       0  4984.1    0.05       0  4988.1    0.12       0
  5177.8    0.07       0
Bank Sta=4984.1,4988.1
Exp/Cntr=0.3,0.1

Type RM Length L Ch R = 1,2403,347,347,347
BEGIN DESCRIPTION:
COTTONWOOD TRIBUTARY 2 5.0
END DESCRIPTION:
XS GIS Cut Line= 3
      2287775.00     13718174.99      2288053.29     13717604.94
      2288025.00     13717125.03
#Sta/Elev= 30
  4402.0  532.90  4433.0  532.24  4468.8  530.08  4500.6  528.84  4545.6  528.89
  4613.2  527.22  4696.1  526.42  4849.6  524.83  4956.6  522.20  4969.0  522.44
  4979.2  521.92  4991.8  522.42  5005.3  521.23  5005.5  520.73  5009.0  520.73
  5009.3  521.23  5014.0  522.16  5033.5  522.92  5086.4  522.72  5099.6  523.13
  5156.5  524.79  5326.8  532.76  5366.9  533.14  5406.9  535.37  5418.2  534.83
  5427.0  533.91  5432.1  534.67  5447.0  538.36  5457.0  539.20  5517.1  539.70
#Mann=7,-1,0
  4402.0    0.07       0  4696.1   0.035       0  4969.0    0.07       0
  5005.3    0.05       0  5009.3    0.07       0  5099.6   0.035       0
  5418.2    0.07       0
Bank Sta=5005.3,5009.3
Exp/Cntr=0.3,0.1

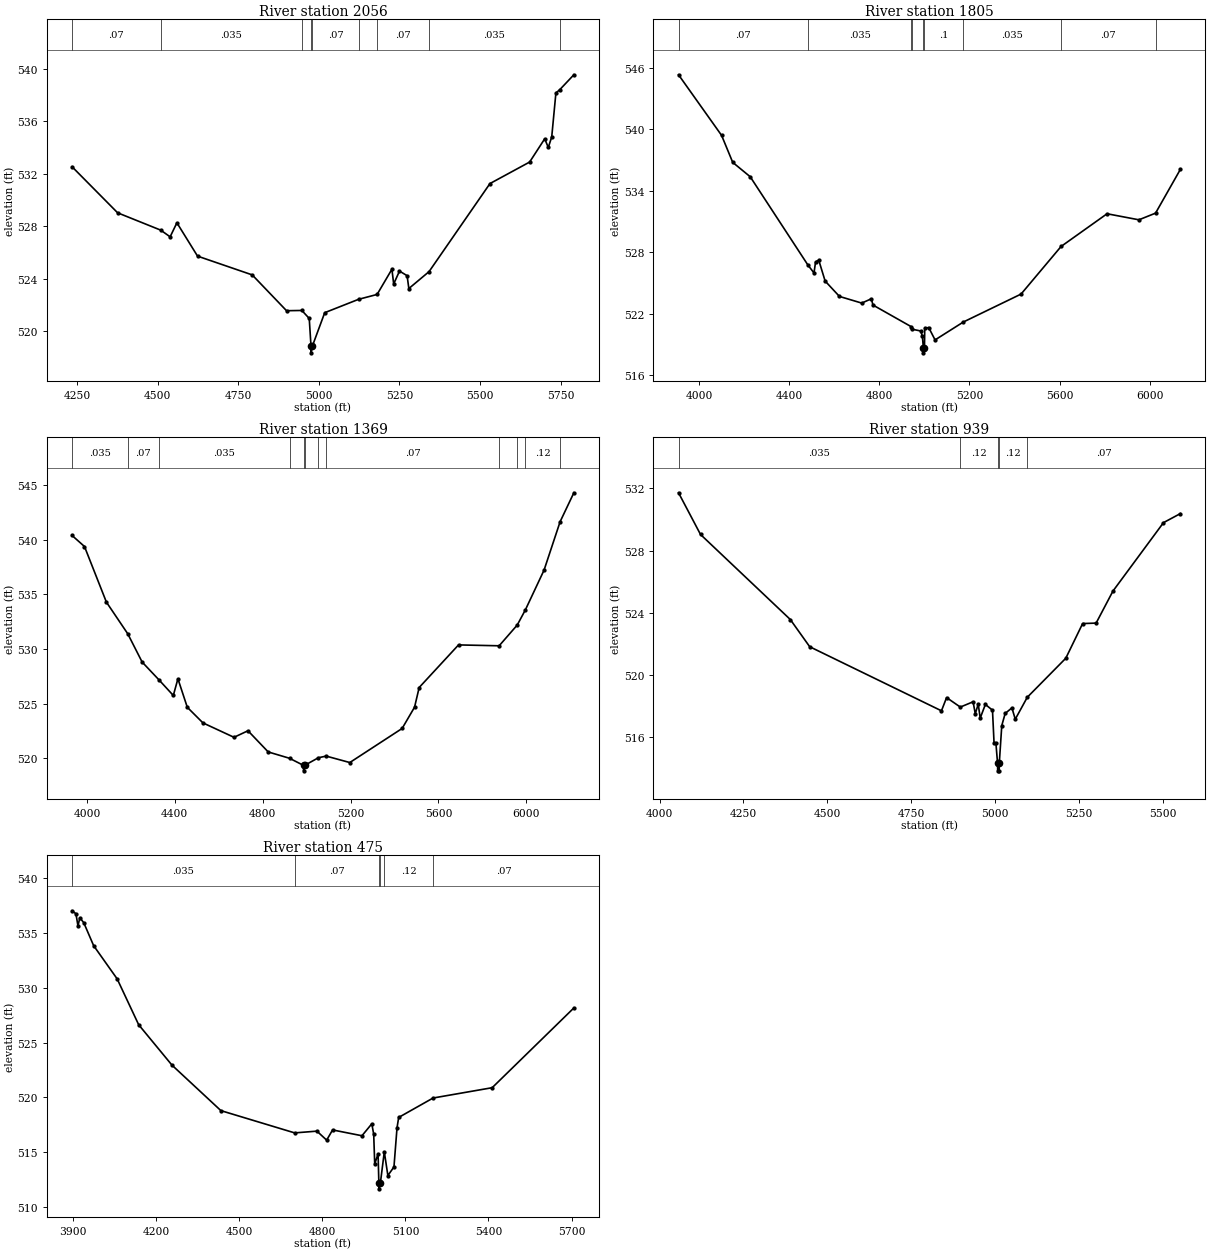
Type RM Length L Ch R = 1,2056,251,251,251
BEGIN DESCRIPTION:
X18670
END DESCRIPTION:
XS GIS Cut Line= 4
      2287818.88     13718318.51      2288324.12     13717844.52
      2288365.79     13717563.27      2288136.61     13717031.99
#Sta/Elev= 30
  4235.0  532.55  4376.3  529.04  4509.9  527.72  4539.0  527.21  4560.0  528.28
  4624.0  525.74  4793.5  524.31  4899.9  521.58  4947.4  521.60  4970.3  520.99
  4975.8  518.87  4976.1  518.37  4979.8  518.87  5018.3  521.43  5123.4  522.45
  5180.7  522.82  5226.6  524.74  5232.1  523.62  5250.1  524.60  5273.7  524.25
  5279.1  523.27  5341.8  524.56  5530.6  531.27  5653.6  532.91  5700.3  534.68
  5711.5  534.02  5722.1  534.83  5735.0  538.17  5747.2  538.43  5790.7  539.56
#Mann=9,-1,0
  4235.0    0.07       0  4509.9   0.035       0  4947.4    0.07       0
  4975.8    0.05       0  4979.8    0.07       0  5123.4   0.035       0
  5180.7    0.07       0  5341.8   0.035       0  5747.2    0.07       0
Bank Sta=4975.8,4979.8
Exp/Cntr=0.3,0.1

Type RM Length L Ch R = 1,1805,436,436,436
BEGIN DESCRIPTION:
COTTONWOOD TRIBUTARY 2 4.0
END DESCRIPTION:
XS GIS Cut Line= 3
      2287775.00     13718725.00      2288525.00     13717925.00
      2289325.03     13717124.97
#Sta/Elev= 30
  3908.3  545.30  4099.5  539.39  4148.9  536.76  4226.5  535.36  4483.7  526.72
  4509.8  525.98  4516.7  527.05  4530.8  527.23  4559.2  525.19  4622.7  523.69
  4721.8  523.04  4764.3  523.46  4771.6  522.85  4940.7  520.75  4946.1  520.49
  4983.6  520.32  4991.0  519.82  4995.3  518.69  4995.7  518.19  5000.3  518.69
  5001.5  520.58  5019.0  520.66  5047.3  519.45  5173.3  521.20  5429.2  523.92
  5606.8  528.56  5811.0  531.75  5952.4  531.16  6026.3  531.81  6136.3  536.07
#Mann=9,-1,0
  3908.3    0.07       0  4483.7   0.035       0  4940.7    0.07       0
  4946.1     0.1       0  4995.3    0.05       0  5000.3     0.1       0
  5173.3   0.035       0  5606.8    0.07       0  6026.3    0.12       0
Bank Sta=4995.3,5000.3
Exp/Cntr=0.3,0.1

Type RM Length L Ch R = 1,1369,430,430,430
BEGIN DESCRIPTION:
COTTONWOOD TRIBUTARY 2 3.0
END DESCRIPTION:
XS GIS Cut Line= 3
      2288024.97     13718825.03      2288825.00     13718125.00
      2289524.99     13717125.01
#Sta/Elev= 30
  3932.5  540.39  3989.0  539.38  4088.7  534.29  4185.9  531.39  4251.4  528.80
  4326.6  527.20  4393.3  525.74  4414.2  527.27  4456.9  524.66  4528.1  523.23
  4669.5  521.91  4733.1  522.51  4825.2  520.57  4922.2  519.99  4985.8  519.34
  4986.2  518.84  4991.0  519.34  5053.6  520.04  5089.0  520.19  5196.5  519.60
  5434.6  522.72  5491.2  524.67  5512.2  526.47  5691.3  530.37  5876.2  530.29
  5958.5  532.19  5995.6  533.58  6080.6  537.22  6153.6  541.65  6216.2  544.30
#Mann=12,-1,0
  3932.5   0.035       0  4185.9    0.07       0  4326.6   0.035       0
  4922.2    0.07       0  4985.8    0.05       0  4991.0    0.07       0
  5053.6   0.035       0  5089.0    0.07       0  5876.2    0.12       0
  5958.5    0.07       0  5995.6    0.12       0  6153.6    0.07       0
Bank Sta=4985.8,4991
Exp/Cntr=0.3,0.1

Type RM Length L Ch R = 1,939,464,464,464
BEGIN DESCRIPTION:
COTTONWOOD TRIBUTARY 2 2.0
END DESCRIPTION:
XS GIS Cut Line= 3
      2288724.98     13718925.04      2289225.00     13718125.00
      2289275.00     13717575.01
#Sta/Elev= 30
  4056.4  531.72  4121.9  529.04  4389.6  523.57  4447.4  521.82  4840.1  517.70
  4855.4  518.55  4896.3  517.94  4934.4  518.28  4940.9  517.51  4949.7  518.13
  4955.6  517.23  4971.0  518.11  4992.2  517.74  4996.9  515.62  5002.4  515.62
  5007.3  514.34  5007.7  513.84  5012.1  513.84  5012.5  514.34  5019.9  516.75
  5030.0  517.53  5050.1  517.89  5060.1  517.16  5095.9  518.57  5210.7  521.08
  5260.9  523.31  5301.1  523.34  5351.3  525.40  5501.9  529.80  5552.1  530.38
#Mann=5,-1,0
  4056.4   0.035       0  4896.3    0.12       0  5007.3    0.05       0
  5012.5    0.12       0  5095.9    0.07       0
Bank Sta=5007.3,5012.5
Exp/Cntr=0.3,0.1

Type RM Length L Ch R = 1,475,0,0,0
BEGIN DESCRIPTION:
COTTONWOOD TRIBUTARY 2 1.0
END DESCRIPTION:
XS GIS Cut Line= 3
      2288874.97     13719125.03      2289625.00     13718325.00
      2289325.01     13717675.02
#Sta/Elev= 30
  3896.0  537.01  3910.0  536.74  3917.3  535.63  3924.1  536.37  3938.3  535.92
  3973.9  533.83  4058.9  530.80  4136.6  526.62  4256.8  522.94  4433.6  518.79
  4700.1  516.76  4780.4  516.92  4815.6  516.10  4837.0  517.03  4943.1  516.50
  4978.7  517.59  4985.5  516.64  4989.2  513.92  5001.3  514.86  5004.2  512.16
  5004.7  511.66  5009.5  512.16  5023.8  515.04  5036.7  512.87  5058.7  513.66
  5069.7  517.21  5075.7  518.17  5200.0  519.94  5413.4  520.88  5708.5  528.15
#Mann=6,-1,0
  3896.0   0.035       0  4700.1    0.07       0  5004.2    0.05       0
  5009.5    0.07       0  5023.8    0.12       0  5200.0    0.07       0
Bank Sta=5004.2,5009.5
Exp/Cntr=0.3,0.1

Chan Stop Cuts=-1