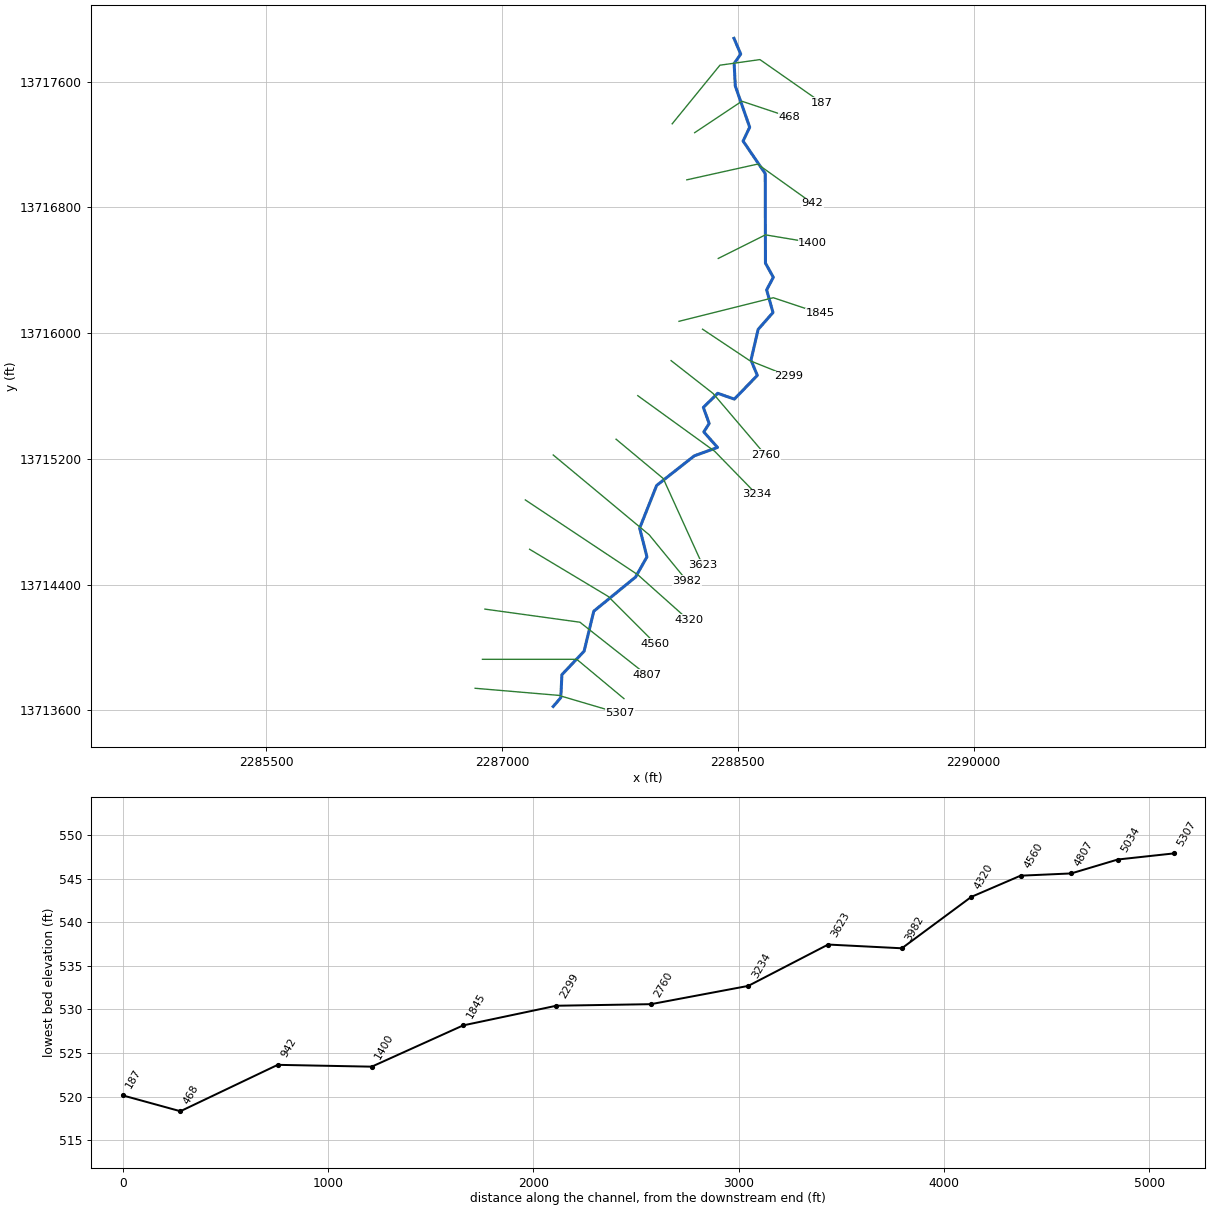
--- COTTONWOOD TRIBUTARY 3.prj (project) ---

Proj Title=COTTONWOOD TRIBUTARY 3 Base Level Engineering
Current Plan=p01
Default Exp/Contr=0.3,0.1
English Units
Geom File=g01
Flow File=f01
Plan File=p01
BEGIN DESCRIPTION:
COTTONWOOD TRIBUTARY 3
END DESCRIPTION:

--- COTTONWOOD TRIBUTARY 3.p01 (plan) ---

Plan Title=Multiple Run
Short Identifier=Multiple
Geom File=g01
Flow File=f01
Subcritical Flow
K Sum by GR= 0
Std Step Tol= 0.01
Critical Tol= 0.01
Num of Std Step Trials= 20
Max Error Tol= 0.3
Flow Tol Ratio= 0.001
Split Flow NTrial= 30
Split Flow Tol= 0.02
Split Flow Ratio= 0.02
Log Output Level= 0
Friction Slope Method= 1
Unsteady Friction Slope Method= 2
Unsteady Bridges Friction Slope Method= 1
Parabolic Critical Depth
Global Vel Dist=  1 , 1 , 1
Global Log Level= 0
CheckData=True
Encroach Param= -1, 0, 0, 0
BEGIN DESCRIPTION:
Multiple Run
END DESCRIPTION:

--- COTTONWOOD TRIBUTARY 3.f01 (steady flow) ---

Flow Title=Multiple
Number of Profiles=7
Profile Names=10-year,25-year,50-year,1pct_min,100-year,1pct_plu,500-year
River Rch & RM= COTTONWOOD TRIBU,Reach-1,5307
     386     607     800     512    1021    2038    1648
Boundary for River Rch & Prof#=COTTONWOOD TRIBU,Reach-1,1
Up Type=0
Dn Type=3
Dn Slope=0.005
Boundary for River Rch & Prof#=COTTONWOOD TRIBU,Reach-1,2
Up Type=0
Dn Type=3
Dn Slope=0.005
Boundary for River Rch & Prof#=COTTONWOOD TRIBU,Reach-1,3
Up Type=0
Dn Type=3
Dn Slope=0.005
Boundary for River Rch & Prof#=COTTONWOOD TRIBU,Reach-1,4
Up Type=0
Dn Type=3
Dn Slope=0.005
Boundary for River Rch & Prof#=COTTONWOOD TRIBU,Reach-1,5
Up Type=0
Dn Type=3
Dn Slope=0.005
Boundary for River Rch & Prof#=COTTONWOOD TRIBU,Reach-1,6
Up Type=0
Dn Type=3
Dn Slope=0.005
Boundary for River Rch & Prof#=COTTONWOOD TRIBU,Reach-1,7
Up Type=0
Dn Type=3
Dn Slope=0.005

--- COTTONWOOD TRIBUTARY 3.g01 (geometry) ---

Geom Title=Existing Conditions

River Reach=COTTONWOOD TRIBU,Reach-1
Reach XY= 30
      2287325.00     13713625.00      2287373.09     13713680.79
      2287380.46     13713827.45      2287521.46     13713976.47
      2287583.14     13714231.06      2287848.73     13714448.12
      2287921.33     13714576.58      2287875.09     13714759.61
      2287983.13     13715031.07      2288222.58     13715219.46
      2288370.19     13715272.76      2288282.93     13715371.43
      2288317.16     13715424.90      2288280.11     13715527.32
      2288371.57     13715617.19      2288477.29     13715580.12
      2288623.34     13715731.05      2288583.11     13715828.29
      2288628.56     13716023.53      2288723.02     13716130.90
      2288682.60     13716275.01      2288725.21     13716354.79
      2288675.09     13716445.03      2288673.80     13717014.50
      2288532.83     13717221.60      2288574.85     13717309.58
      2288483.28     13717571.78      2288475.97     13717714.36
      2288517.65     13717775.03      2288475.00     13717875.00

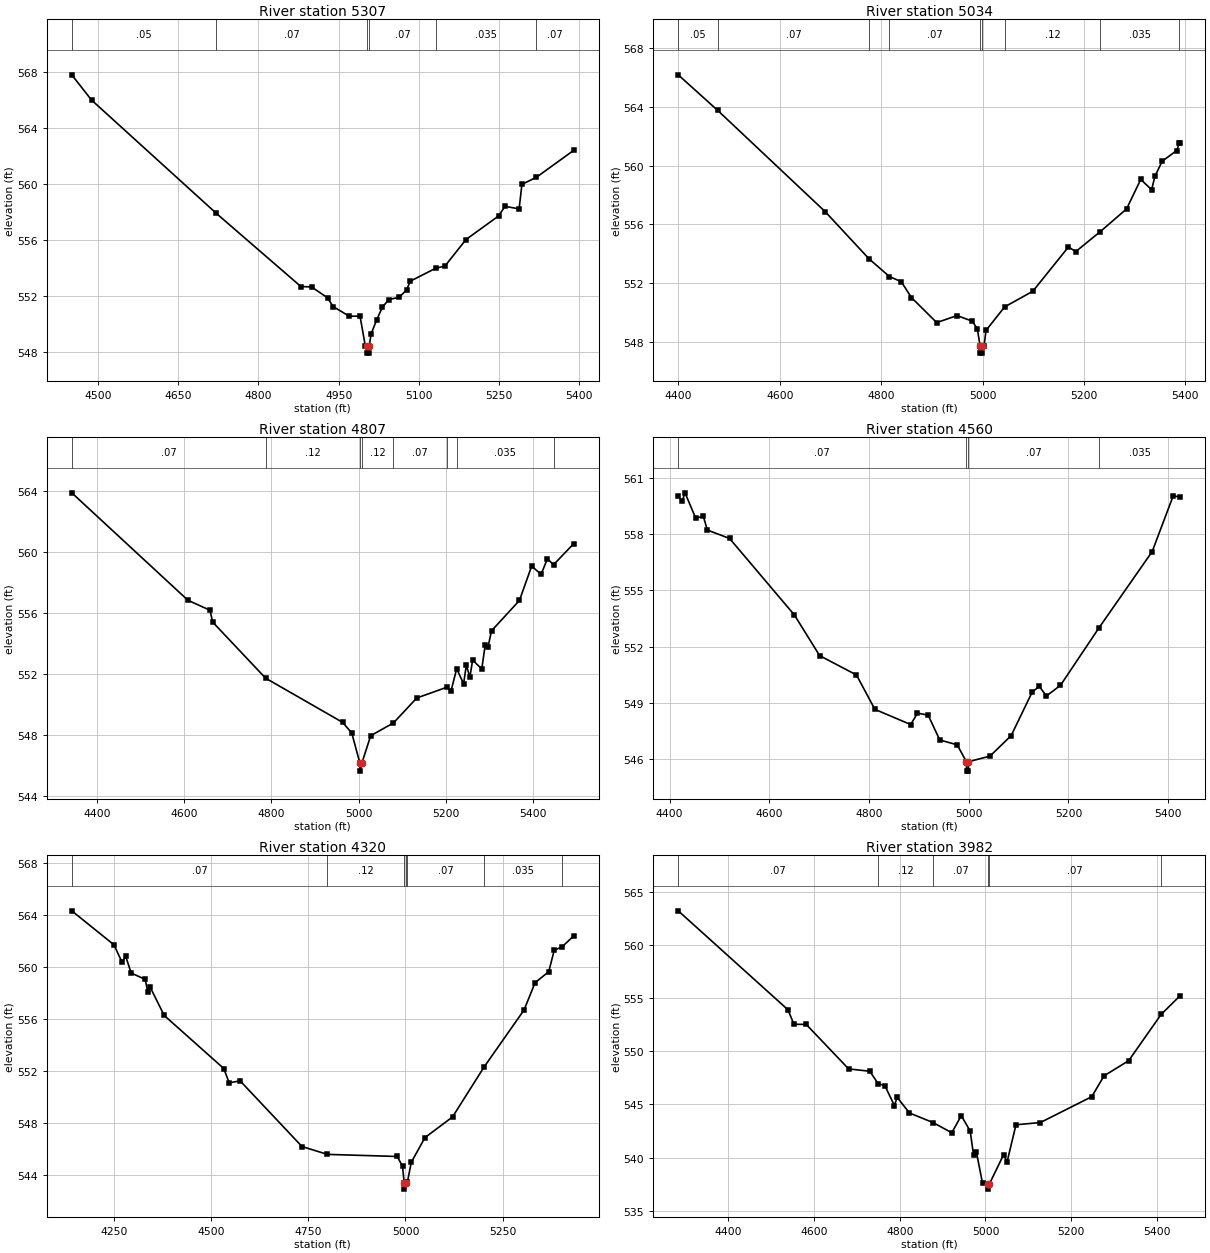
Type RM Length L Ch R = 1,5307,273,273,273
BEGIN DESCRIPTION:
X18673
END DESCRIPTION:
XS GIS Cut Line= 3
      2286828.27     13713740.90      2287359.56     13713695.76
      2287748.42     13713581.18
#Sta/Elev= 30
  4451.0  567.82  4487.9  566.02  4721.5  557.91  4879.3  552.69  4899.3  552.66
  4929.3  551.88  4939.5  551.26  4969.6  550.57  4989.9  550.57  4999.8  548.43
  5003.0  548.43  5003.3  547.93  5006.8  547.93  5007.0  548.43  5010.7  549.32
  5021.2  550.32  5031.6  551.21  5043.6  551.76  5062.9  551.92  5076.9  552.44
  5083.7  553.07  5131.0  553.99  5148.8  554.16  5188.0  556.05  5248.8  557.73
  5260.9  558.42  5287.3  558.24  5292.5  559.99  5319.7  560.50  5389.6  562.43
#Mann=6,-1,0
  4451.0    0.05       0  4721.5    0.07       0  5003.0    0.05       0
  5007.0    0.07       0  5131.0   0.035       0  5319.7    0.07       0
Bank Sta=5003,5007
Exp/Cntr=0.3,0.1

Type RM Length L Ch R = 1,5034,227,227,227
BEGIN DESCRIPTION:
COTTONWOOD TRIBUTARY 3 10.0
END DESCRIPTION:
XS GIS Cut Line= 3
      2286874.97     13713925.00      2287475.00     13713925.00
      2287774.97     13713675.03
#Sta/Elev= 30
  4399.7  566.20  4477.7  563.77  4689.7  556.87  4776.3  553.65  4816.3  552.45
  4839.7  552.10  4859.7  551.02  4909.7  549.31  4949.7  549.79  4979.7  549.41
  4989.7  548.89  4995.2  547.73  4995.5  547.23  4999.0  547.23  4999.2  547.73
  5003.0  547.73  5006.9  548.78  5043.6  550.38  5099.3  551.45  5169.6  554.47
  5183.9  554.15  5232.6  555.52  5284.2  557.06  5312.1  559.07  5333.6  558.37
  5340.1  559.28  5354.4  560.31  5383.1  561.04  5388.1  561.52  5390.2  561.52
#Mann=9,-1,0
  4399.7    0.05       0  4477.7    0.07       0  4776.3    0.12       0
  4816.3    0.07       0  4995.2    0.05       0  4999.2    0.07       0
  5043.6    0.12       0  5232.6   0.035       0  5388.1    0.07       0
Bank Sta=4995.2,4999.2
Exp/Cntr=0.3,0.1

Type RM Length L Ch R = 1,4807,247,247,247
BEGIN DESCRIPTION:
X18675
END DESCRIPTION:
XS GIS Cut Line= 3
      2286890.79     13714244.37      2287494.98     13714161.03
      2287921.03     13713825.04
#Sta/Elev= 30
  4341.6  563.86  4608.3  556.82  4658.8  556.17  4665.1  555.39  4786.5  551.72
  4963.6  548.82  4984.4  548.12  5003.2  546.13  5003.5  545.63  5007.2  546.13
  5027.8  547.95  5080.1  548.79  5133.5  550.42  5202.1  551.12  5212.1  550.87
  5225.2  552.34  5241.0  551.35  5247.3  552.57  5255.4  551.78  5261.8  552.91
  5282.7  552.32  5290.7  553.90  5297.0  553.75  5305.1  554.82  5369.2  556.81
  5397.3  559.06  5418.9  558.52  5433.4  559.54  5447.5  559.15  5494.1  560.54
#Mann=8,-1,0
  4341.6    0.07       0  4786.5    0.12       0  5003.2    0.05       0
  5007.2    0.12       0  5080.1    0.07       0  5202.1    0.12       0
  5225.2   0.035       0  5447.5    0.12       0
Bank Sta=5003.2,5007.2
Exp/Cntr=0.3,0.1

Type RM Length L Ch R = 1,4560,240,240,240
BEGIN DESCRIPTION:
COTTONWOOD TRIBUTARY 3 9.0
END DESCRIPTION:
XS GIS Cut Line= 3
      2287175.03     13714624.98      2287675.00     13714325.00
      2287974.98     13714025.02
#Sta/Elev= 30
  4417.2  560.03  4424.9  559.73  4430.8  560.19  4452.1  558.85  4467.7  558.93
  4475.5  558.21  4520.2  557.76  4650.4  553.68  4700.9  551.52  4774.8  550.49
  4811.7  548.66  4883.6  547.85  4897.2  548.46  4918.6  548.35  4941.9  547.03
  4976.9  546.77  4995.3  545.87  4995.6  545.37  4999.1  545.37  4999.3  545.87
  5042.7  546.17  5085.1  547.26  5127.5  549.59  5141.7  549.88  5155.8  549.37
  5184.1  549.94  5260.8  552.98  5368.0  557.06  5410.4  560.04  5424.5  559.95
#Mann=4,-1,0
  4417.2    0.07       0  4995.3    0.05       0  4999.3    0.07       0
  5260.8   0.035       0
Bank Sta=4995.3,4999.3
Exp/Cntr=0.3,0.1

Type RM Length L Ch R = 1,4320,338,338,338
BEGIN DESCRIPTION:
X18674
END DESCRIPTION:
XS GIS Cut Line= 3
      2287147.75     13714938.82      2287863.03     13714463.12
      2288185.92     13714174.95
#Sta/Elev= 30
  4141.4  564.32  4249.9  561.71  4270.9  560.36  4280.0  560.84  4294.2  559.54
  4330.3  559.05  4337.1  558.06  4343.1  558.45  4379.2  556.28  4532.5  552.20
  4546.4  551.10  4574.6  551.25  4733.9  546.20  4799.3  545.60  4978.8  545.44
  4992.4  544.69  4996.6  543.43  4996.9  542.93  5000.6  543.43  5005.2  543.51
  5014.9  544.99  5050.1  546.89  5121.1  548.48  5202.3  552.32  5305.1  556.70
  5333.5  558.80  5368.6  559.64  5382.8  561.30  5402.0  561.53  5433.2  562.40
#Mann=7,-1,0
  4141.4    0.07       0  4799.3    0.12       0  4996.6    0.05       0
  5000.6    0.12       0  5005.2    0.07       0  5202.3   0.035       0
  5402.0    0.05       0
Bank Sta=4996.6,5000.6
Exp/Cntr=0.3,0.1

Type RM Length L Ch R = 1,3982,359,359,359
BEGIN DESCRIPTION:
COTTONWOOD TRIBUTARY 3 8.0
END DESCRIPTION:
XS GIS Cut Line= 3
      2287325.02     13715224.99      2287935.95     13714716.59
      2288175.03     13714424.97
#Sta/Elev= 30
  4282.9  563.19  4538.7  553.90  4553.0  552.53  4581.7  552.51  4680.6  548.33
  4730.1  548.11  4749.3  546.95  4765.2  546.76  4787.4  544.89  4793.9  545.66
  4822.5  544.19  4877.4  543.29  4921.4  542.33  4943.6  543.94  4964.4  542.48
  4972.2  540.22  4978.7  540.54  4993.1  537.59  5005.4  537.53  5005.6  537.03
  5009.4  537.53  5042.5  540.28  5050.3  539.56  5071.2  543.08  5128.2  543.29
  5248.1  545.72  5276.8  547.68  5334.2  549.10  5410.0  553.45  5454.8  555.23
#Mann=6,-1,0
  4282.9    0.07       0  4749.3    0.12       0  4877.4    0.07       0
  5005.4    0.05       0  5009.4    0.07       0  5410.0   0.035       0
Bank Sta=5005.4,5009.4
Exp/Cntr=0.3,0.1

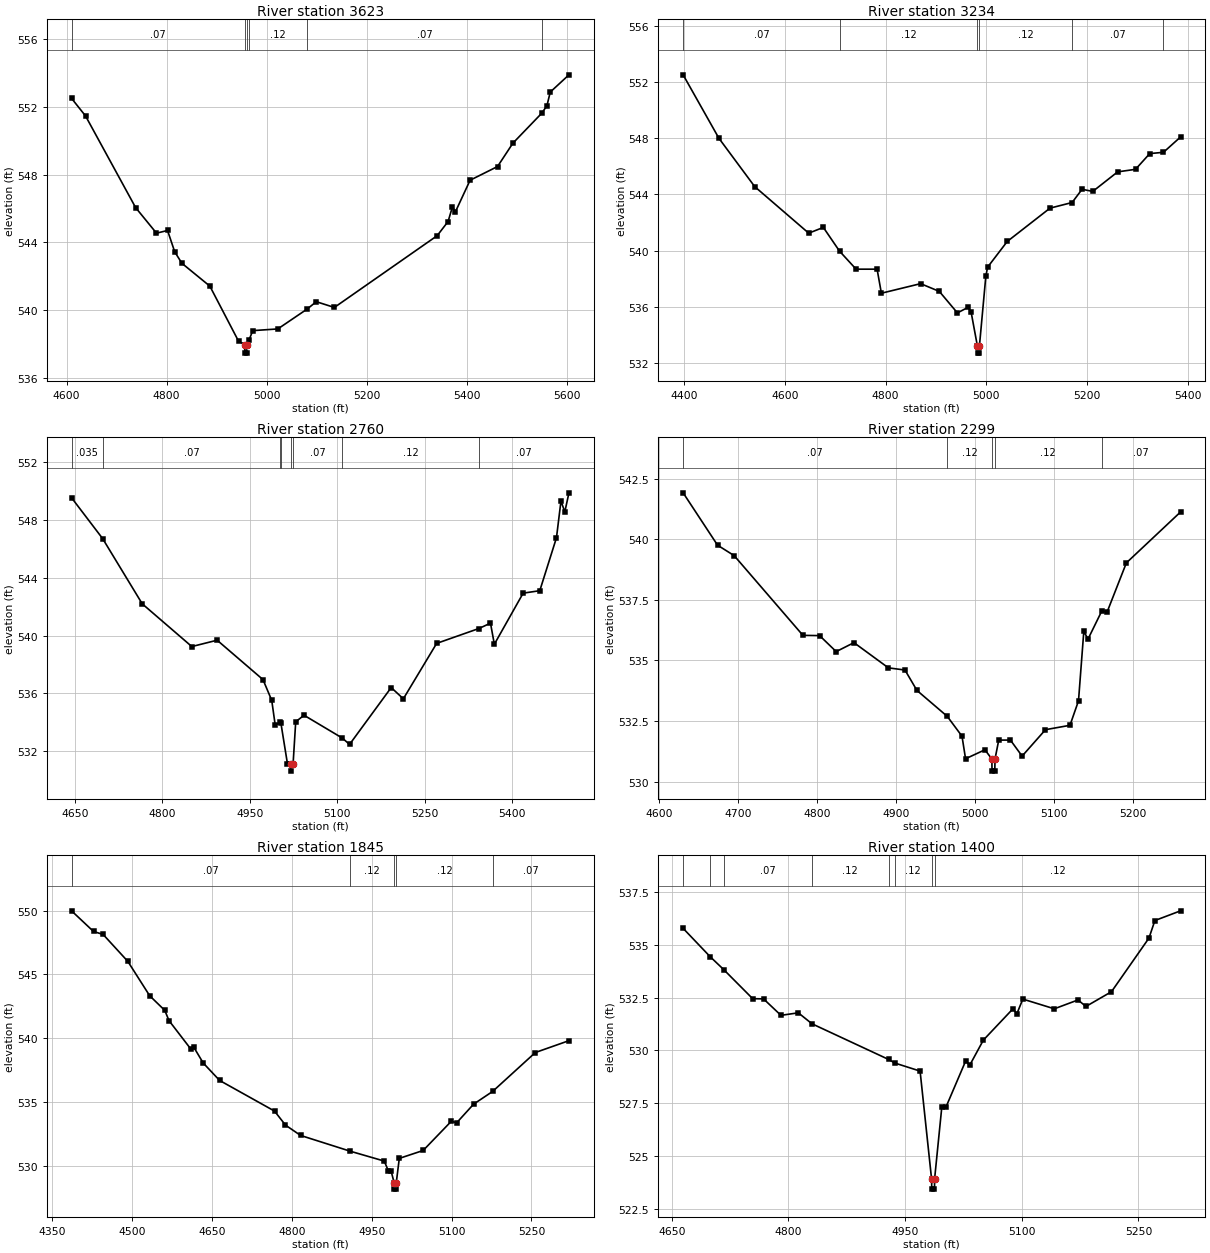
Type RM Length L Ch R = 1,3623,389,389,389
BEGIN DESCRIPTION:
COTTONWOOD TRIBUTARY 3 7.0
END DESCRIPTION:
XS GIS Cut Line= 3
      2287724.98     13715325.01      2288025.00     13715075.00
      2288275.00     13714524.99
#Sta/Elev= 30
  4609.9  552.52  4637.9  551.48  4738.1  546.06  4779.8  544.55  4801.9  544.71
  4816.2  543.45  4830.6  542.77  4886.5  541.42  4943.8  538.17  4956.1  537.96
  4956.4  537.46  4959.9  537.46  4960.1  537.96  4964.4  538.21  4972.4  538.79
  5022.4  538.89  5081.3  540.07  5099.3  540.50  5135.5  540.16  5341.0  544.40
  5362.9  545.24  5371.7  546.12  5377.2  545.79  5406.9  547.68  5461.8  548.49
  5492.5  549.87  5550.5  551.65  5560.6  552.09  5567.2  552.89  5604.6  553.91
#Mann=6,-1,0
  4609.9    0.07       0  4956.1    0.05       0  4960.1    0.07       0
  4964.4    0.12       0  5081.3    0.07       0  5550.5   0.035       0
Bank Sta=4956.1,4960.1
Exp/Cntr=0.3,0.1

Type RM Length L Ch R = 1,3234,474,474,474
BEGIN DESCRIPTION:
X18672
END DESCRIPTION:
XS GIS Cut Line= 3
      2287863.03     13715602.01      2288352.62     13715247.84
      2288619.97     13714973.54
#Sta/Elev= 30
  4398.2  552.50  4469.2  547.99  4540.3  544.55  4647.5  541.24  4676.5  541.65
  4708.7  539.96  4741.5  538.68  4783.2  538.68  4791.7  536.97  4869.6  537.65
  4906.7  537.10  4942.6  535.57  4963.4  535.96  4969.6  535.67  4982.3  533.21
  4982.6  532.71  4986.1  532.71  4986.3  533.21  4999.0  538.17  5002.5  538.82
  5041.5  540.65  5126.4  543.02  5170.3  543.42  5190.0  544.36  5211.3  544.21
  5260.7  545.60  5296.1  545.78  5324.4  546.90  5351.6  546.99  5385.5  548.08
#Mann=6,-1,0
  4398.2    0.07       0  4708.7    0.12       0  4982.3    0.05       0
  4986.3    0.12       0  5170.3    0.07       0  5351.6   0.035       0
Bank Sta=4982.3,4986.3
Exp/Cntr=0.3,0.1

Type RM Length L Ch R = 1,2760,461,461,461
BEGIN DESCRIPTION:
COTTONWOOD TRIBUTARY 3 6.0
END DESCRIPTION:
XS GIS Cut Line= 3
      2288074.98     13715825.02      2288342.20     13715615.90
      2288675.00     13715225.00
#Sta/Elev= 30
  4644.5  549.55  4697.8  546.72  4765.7  542.20  4850.7  539.24  4894.1  539.68
  4972.7  536.95  4987.7  535.51  4993.7  533.78  5002.6  534.02  5003.4  533.94
  5014.6  531.13  5020.3  531.11  5020.5  530.61  5024.3  531.11  5028.8  534.03
  5043.1  534.48  5108.7  532.90  5121.1  532.46  5192.5  536.40  5213.3  535.62
  5270.4  539.46  5342.8  540.49  5362.7  540.86  5369.3  539.40  5418.7  542.94
  5447.2  543.11  5475.8  546.78  5483.5  549.32  5490.1  548.57  5497.2  549.89
#Mann=8,-1,0
  4644.5   0.035       0  4697.8    0.07       0  5002.6    0.12       0
  5003.4    0.07       0  5020.3    0.05       0  5024.3    0.07       0
  5108.7    0.12       0  5342.8    0.07       0
Bank Sta=5020.3,5024.3
Exp/Cntr=0.3,0.1

Type RM Length L Ch R = 1,2299,454,454,454
BEGIN DESCRIPTION:
COTTONWOOD TRIBUTARY 3 5.0
END DESCRIPTION:
XS GIS Cut Line= 3
      2288274.99     13716025.01      2288575.00     13715825.00
      2288824.98     13715725.01
#Sta/Elev= 30
  4630.7  541.91  4674.3  539.75  4695.3  539.32  4782.4  536.03  4803.5  536.02
  4824.5  535.36  4847.0  535.73  4890.6  534.69  4911.6  534.60  4926.7  533.76
  4965.1  532.69  4983.8  531.87  4988.3  530.94  5012.8  531.31  5021.6  530.93
  5021.8  530.43  5025.3  530.43  5025.6  530.93  5030.3  531.71  5045.1  531.71
  5059.9  531.05  5089.5  532.14  5120.5  532.32  5131.3  533.33  5138.0  536.19
  5143.4  535.88  5160.7  537.03  5167.6  537.00  5191.9  539.02  5260.5  541.12
#Mann=5,-1,0
  4630.7    0.07       0  4965.1    0.12       0  5021.6    0.05       0
  5025.6    0.12       0  5160.7    0.07       0
Bank Sta=5021.6,5025.6
Exp/Cntr=0.3,0.1

Type RM Length L Ch R = 1,1845,445,445,445
BEGIN DESCRIPTION:
COTTONWOOD TRIBUTARY 3 4.0
END DESCRIPTION:
XS GIS Cut Line= 3
      2288124.97     13716074.99      2288725.00     13716225.00
      2289024.97     13716125.01
#Sta/Elev= 30
  4385.8  549.99  4427.1  548.37  4445.1  548.14  4491.5  546.03  4532.7  543.33
  4561.1  542.18  4568.8  541.39  4610.0  539.15  4615.2  539.32  4633.2  538.06
  4664.1  536.69  4767.2  534.29  4787.8  533.19  4816.2  532.38  4909.7  531.14
  4973.4  530.37  4981.1  529.61  4986.3  529.59  4992.0  528.67  4992.2  528.17
  4995.7  528.17  4996.0  528.67  5001.7  530.58  5046.5  531.20  5099.2  533.48
  5109.7  533.38  5141.3  534.83  5177.1  535.83  5257.3  538.88  5320.5  539.81
#Mann=5,-1,0
  4385.8    0.07       0  4909.7    0.12       0  4992.0    0.05       0
  4996.0    0.12       0  5177.1    0.07       0
Bank Sta=4992,4996
Exp/Cntr=0.3,0.1

Type RM Length L Ch R = 1,1400,458,458,458
BEGIN DESCRIPTION:
COTTONWOOD TRIBUTARY 3 3.0
END DESCRIPTION:
XS GIS Cut Line= 3
      2288375.00     13716475.00      2288675.00     13716625.00
      2288975.05     13716574.99
#Sta/Elev= 30
  4664.6  535.78  4699.3  534.44  4716.7  533.83  4754.0  532.45  4768.0  532.44
  4790.4  531.66  4812.7  531.78  4830.3  531.26  4928.9  529.57  4936.9  529.40
  4969.3  529.02  4984.0  523.93  4984.3  523.43  4987.8  523.43  4988.0  523.93
  4997.2  527.31  5002.5  527.31  5027.9  529.50  5033.0  529.29  5050.7  530.49
  5088.7  531.97  5093.8  531.74  5101.4  532.43  5141.9  531.97  5172.4  532.39
  5182.5  532.08  5215.4  532.78  5263.6  535.32  5271.2  536.15  5304.2  536.61
#Mann=8,-1,0
  4664.6    0.07       0  4699.3    0.12       0  4716.7    0.07       0
  4830.3    0.12       0  4928.9    0.07       0  4936.9    0.12       0
  4984.0    0.05       0  4988.0    0.12       0
Bank Sta=4984,4988
Exp/Cntr=0.3,0.1

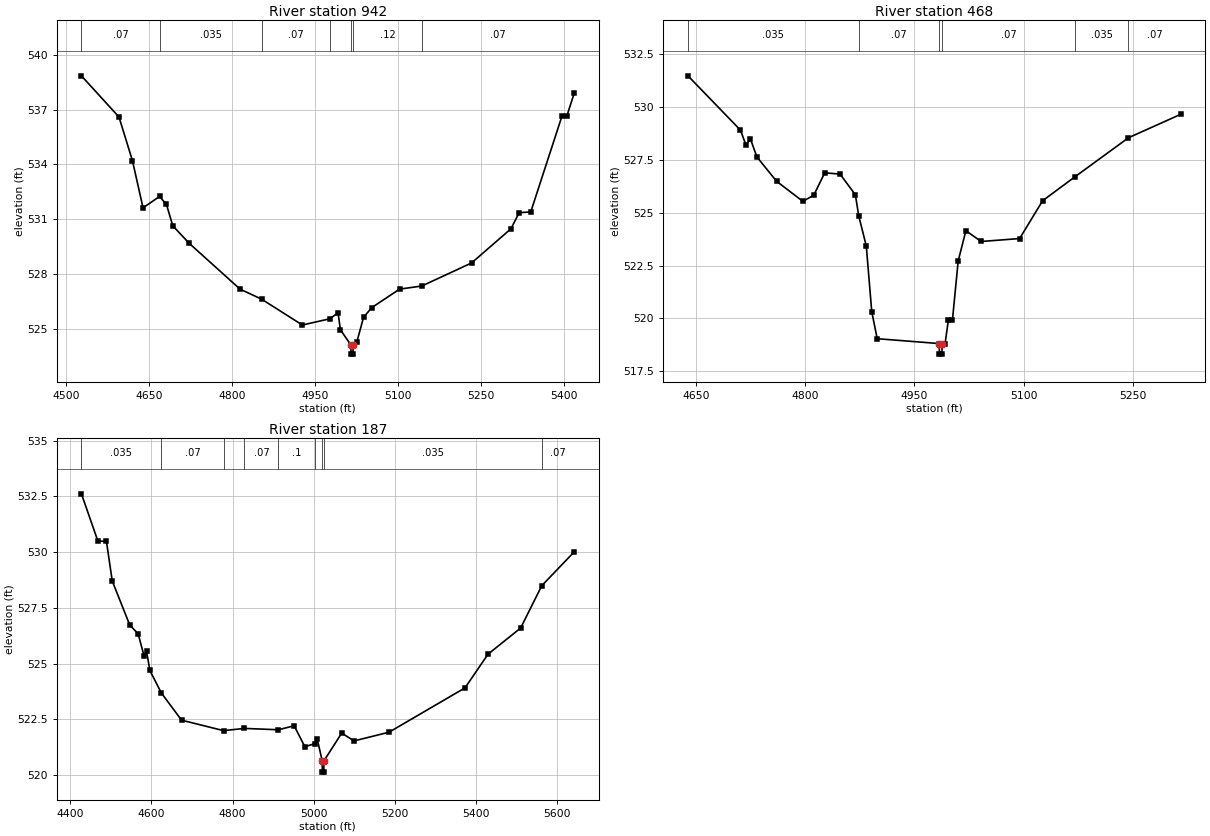
Type RM Length L Ch R = 1,942,474,474,474
BEGIN DESCRIPTION:
COTTONWOOD TRIBUTARY 3 2.0
END DESCRIPTION:
XS GIS Cut Line= 3
      2288175.01     13716975.00      2288625.00     13717075.00
      2288975.01     13716824.99
#Sta/Elev= 30
  4528.3  538.84  4596.2  536.59  4620.5  534.21  4639.7  531.63  4669.5  532.25
  4682.0  531.82  4693.5  530.65  4722.9  529.70  4815.1  527.19  4854.2  526.64
  4927.8  525.23  4977.5  525.57  4992.3  525.90  4996.6  524.97  5015.5  524.14
  5015.8  523.64  5019.3  523.64  5019.5  524.14  5026.1  524.28  5038.4  525.65
  5053.2  526.18  5103.6  527.19  5143.7  527.36  5233.8  528.62  5305.1  530.49
  5319.8  531.37  5340.7  531.40  5397.3  536.65  5405.9  536.63  5419.4  537.90
#Mann=7,-1,0
  4528.3    0.07       0  4669.5   0.035       0  4854.2    0.07       0
  4977.5    0.12       0  5015.5    0.05       0  5019.5    0.12       0
  5143.7    0.07       0
Bank Sta=5015.5,5019.5
Exp/Cntr=0.3,0.1

Type RM Length L Ch R = 1,468,281,281,281
BEGIN DESCRIPTION:
COTTONWOOD TRIBUTARY 3 1.0
END DESCRIPTION:
XS GIS Cut Line= 3
      2288224.98     13717274.98      2288525.00     13717475.00
      2288824.99     13717375.00
#Sta/Elev= 30
  4639.1  531.48  4711.2  528.91  4718.8  528.20  4724.8  528.50  4733.8  527.64
  4760.8  526.49  4796.9  525.54  4811.9  525.83  4826.9  526.89  4848.0  526.83
  4869.0  525.85  4873.7  524.84  4884.0  523.43  4891.5  520.32  4899.0  519.04
  4984.2  518.81  4984.4  518.31  4987.9  518.31  4988.2  518.81  4992.2  518.81
  4996.7  519.91  5002.3  519.91  5010.2  522.72  5020.8  524.15  5041.8  523.64
  5094.6  523.78  5126.2  525.57  5170.9  526.71  5244.1  528.55  5315.9  529.66
#Mann=6,-1,0
  4639.1   0.035       0  4873.7    0.07       0  4984.2    0.05       0
  4988.2    0.07       0  5170.9   0.035       0  5244.1    0.07       0
Bank Sta=4984.2,4988.2
Exp/Cntr=0.3,0.1

Type RM Length L Ch R = 1,187,0,0,0
BEGIN DESCRIPTION:
X18671
END DESCRIPTION:
XS GIS Cut Line= 4
      2288081.86     13717331.23      2288385.50     13717704.09
      2288640.01     13717739.81      2289031.44     13717466.25
#Sta/Elev= 30
  4427.2  532.61  4468.0  530.48  4488.8  530.49  4503.2  528.70  4546.3  526.73
  4567.1  526.33  4581.5  525.35  4587.9  525.54  4595.9  524.69  4624.3  523.68
  4674.1  522.46  4777.9  521.99  4828.9  522.09  4913.2  522.03  4951.8  522.21
  4978.2  521.27  5003.3  521.41  5008.5  521.63  5021.1  520.63  5021.4  520.13
  5024.9  520.13  5025.1  520.63  5069.1  521.88  5099.5  521.53  5185.8  521.92
  5373.3  523.91  5430.0  525.42  5510.3  526.59  5562.5  528.49  5642.6  530.01
#Mann=9,-1,0
  4427.2   0.035       0  4624.3    0.07       0  4777.9   0.035       0
  4828.9    0.07       0  4913.2     0.1       0  5003.3   0.035       0
  5021.1    0.05       0  5025.1   0.035       0  5562.5    0.07       0
Bank Sta=5021.1,5025.1
Exp/Cntr=0.3,0.1

Chan Stop Cuts=-1