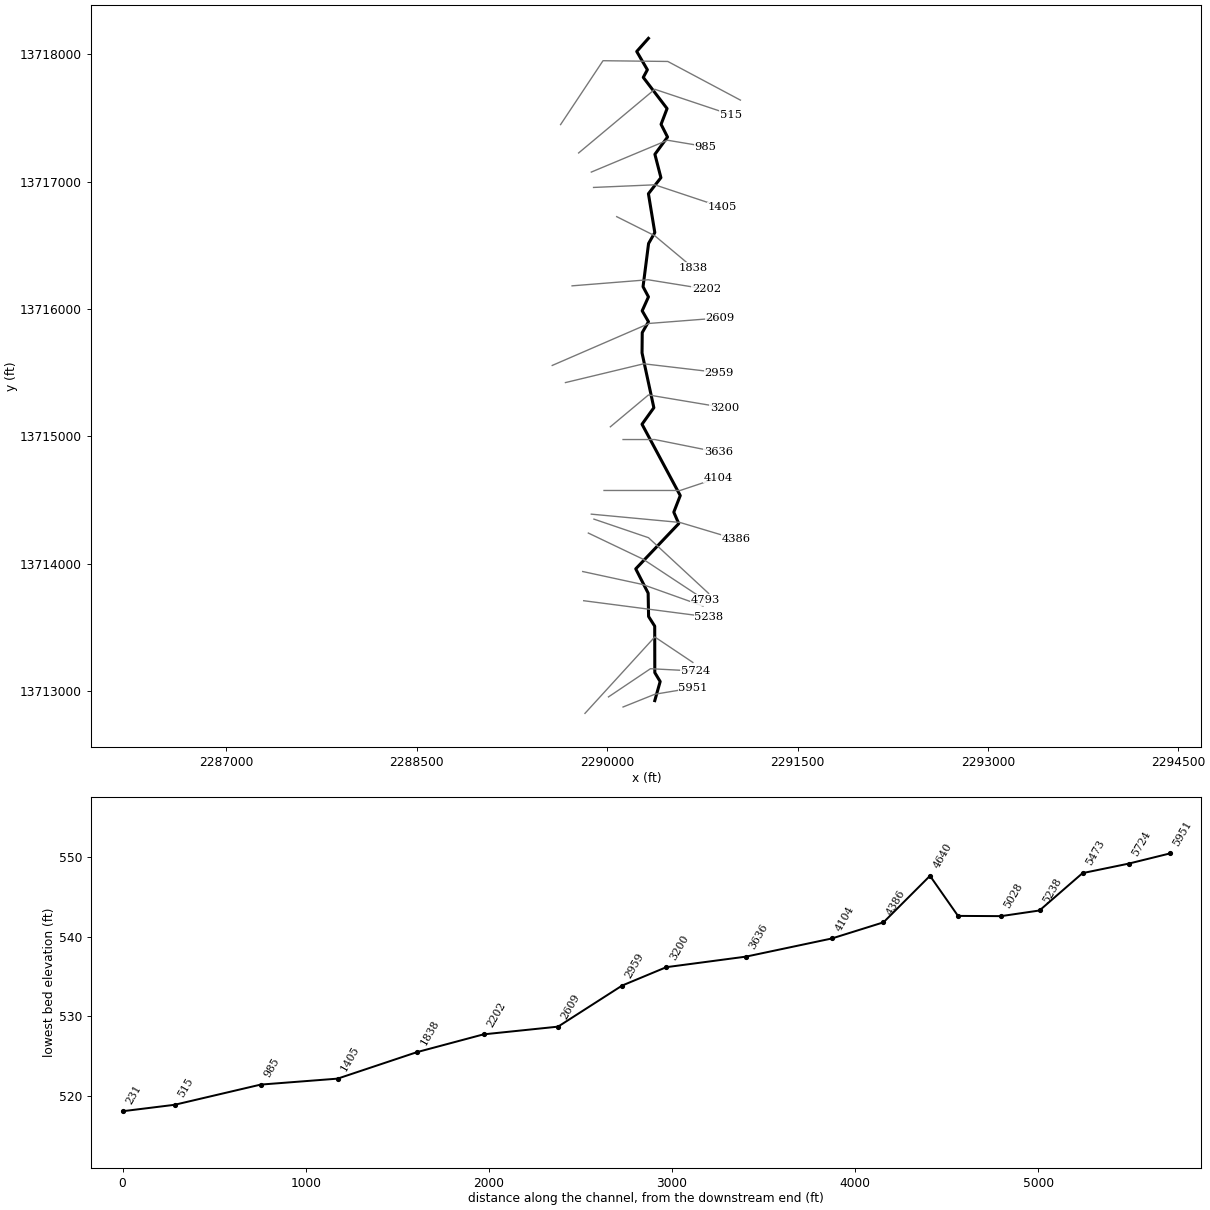
--- COTTONWOOD TRIBUTARY 6.prj (project) ---

Proj Title=COTTONWOOD TRIBUTARY 6 Base Level Engineering
Current Plan=p01
Default Exp/Contr=0.3,0.1
English Units
Geom File=g01
Flow File=f01
Plan File=p01
BEGIN DESCRIPTION:
COTTONWOOD TRIBUTARY 6
END DESCRIPTION:

--- COTTONWOOD TRIBUTARY 6.p01 (plan) ---

Plan Title=Multiple Run
Short Identifier=Multiple
Geom File=g01
Flow File=f01
Subcritical Flow
K Sum by GR= 0
Std Step Tol= 0.01
Critical Tol= 0.01
Num of Std Step Trials= 20
Max Error Tol= 0.3
Flow Tol Ratio= 0.001
Split Flow NTrial= 30
Split Flow Tol= 0.02
Split Flow Ratio= 0.02
Log Output Level= 0
Friction Slope Method= 1
Unsteady Friction Slope Method= 2
Unsteady Bridges Friction Slope Method= 1
Parabolic Critical Depth
Global Vel Dist=  1 , 1 , 1
Global Log Level= 0
CheckData=True
Encroach Param= -1, 0, 0, 0
BEGIN DESCRIPTION:
Multiple Run
END DESCRIPTION:

--- COTTONWOOD TRIBUTARY 6.f01 (steady flow) ---

Flow Title=Multiple
Number of Profiles=7
Profile Names=10-year,25-year,50-year,1pct_min,100-year,1pct_plu,500-year
River Rch & RM= COTTONWOOD TRIBU,Reach-1,5951
     428     678     899     578    1154    2302    1882
Boundary for River Rch & Prof#=COTTONWOOD TRIBU,Reach-1,1
Up Type=0
Dn Type=3
Dn Slope=0.005
Boundary for River Rch & Prof#=COTTONWOOD TRIBU,Reach-1,2
Up Type=0
Dn Type=3
Dn Slope=0.005
Boundary for River Rch & Prof#=COTTONWOOD TRIBU,Reach-1,3
Up Type=0
Dn Type=3
Dn Slope=0.005
Boundary for River Rch & Prof#=COTTONWOOD TRIBU,Reach-1,4
Up Type=0
Dn Type=3
Dn Slope=0.005
Boundary for River Rch & Prof#=COTTONWOOD TRIBU,Reach-1,5
Up Type=0
Dn Type=3
Dn Slope=0.005
Boundary for River Rch & Prof#=COTTONWOOD TRIBU,Reach-1,6
Up Type=0
Dn Type=3
Dn Slope=0.005
Boundary for River Rch & Prof#=COTTONWOOD TRIBU,Reach-1,7
Up Type=0
Dn Type=3
Dn Slope=0.005

--- COTTONWOOD TRIBUTARY 6.g01 (geometry) ---

Geom Title=Existing Conditions

River Reach=COTTONWOOD TRIBU,Reach-1
Reach XY= 30
      2290375.00     13712925.00      2290417.49     13713074.99
      2290375.18     13713144.98      2290374.48     13713509.78
      2290326.22     13713585.51      2290322.76     13713769.07
      2290224.95     13713959.66      2290563.89     13714314.95
      2290524.79     13714404.79      2290575.78     13714535.05
      2290274.53     13715095.16      2290367.67     13715224.90
      2290274.64     13715654.85      2290276.24     13715814.50
      2290325.39     13715900.00      2290275.79     13715985.69
      2290325.20     13716095.20      2290282.59     13716174.99
      2290326.22     13716514.50      2290375.23     13716599.93
      2290324.94     13716905.01      2290423.37     13717031.04
      2290375.94     13717214.52      2290475.48     13717349.97
      2290424.62     13717450.00      2290471.86     13717573.36
      2290284.31     13717818.34      2290316.75     13717878.23
      2290232.77     13718021.77      2290325.00     13718125.00

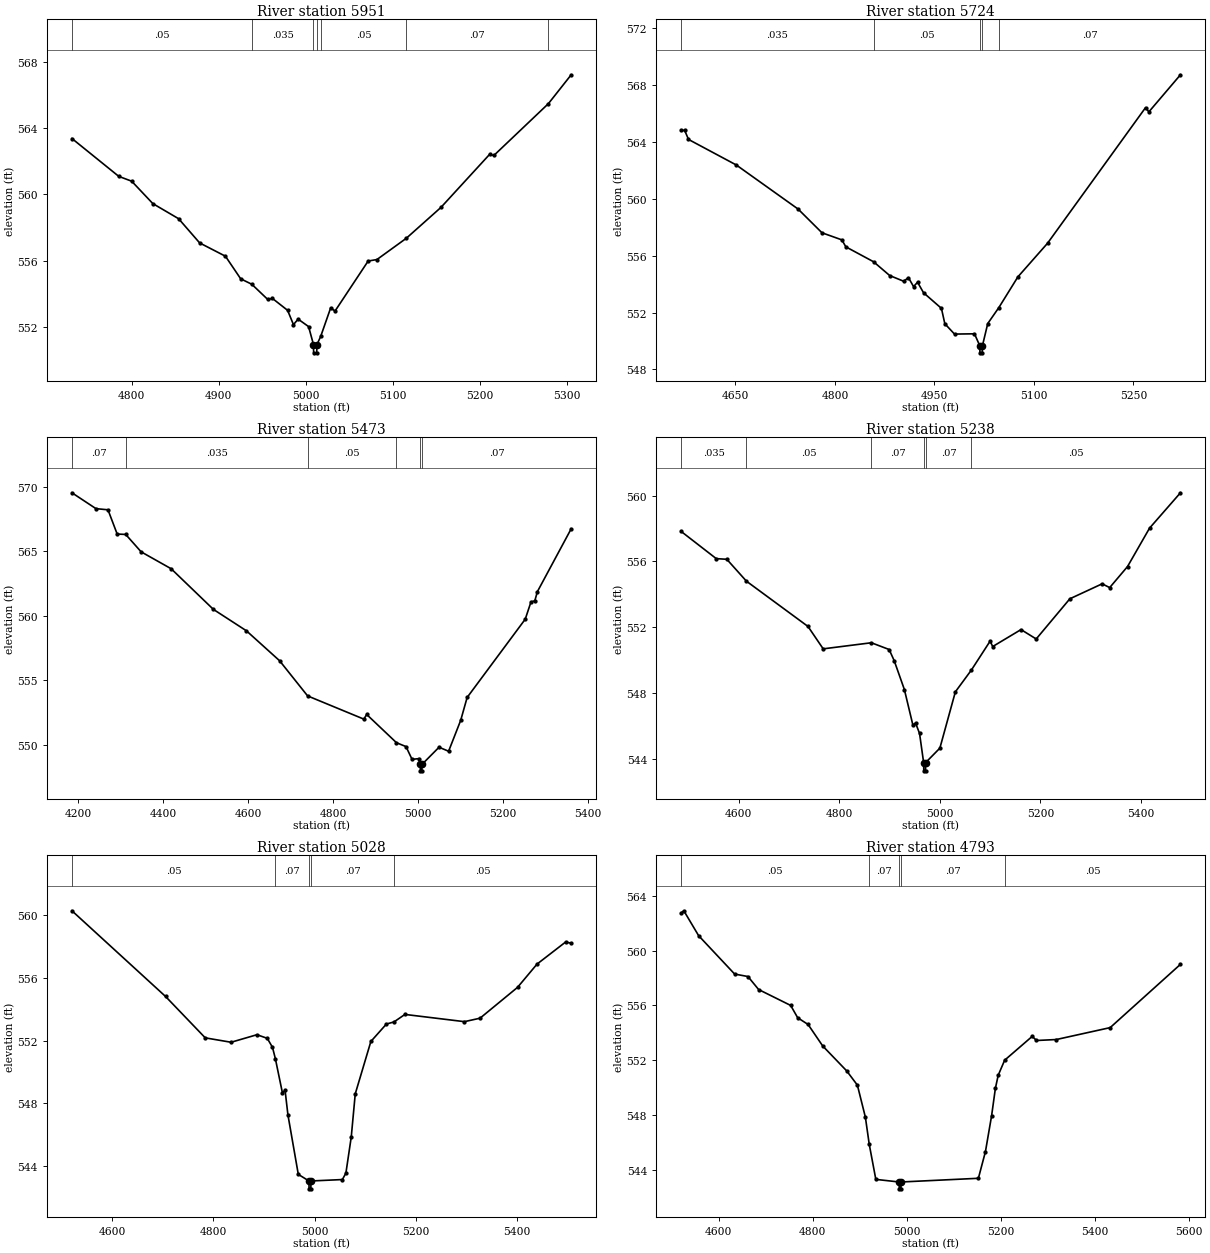
Type RM Length L Ch R = 1,5951,227,227,227
BEGIN DESCRIPTION:
COTTONWOOD TRIBUTARY 6 13.0
END DESCRIPTION:
XS GIS Cut Line= 3
      2290125.04     13712875.02      2290375.00     13712975.00
      2290675.04     13713025.01
#Sta/Elev= 30
  4731.4  563.37  4785.2  561.09  4800.0  560.80  4824.3  559.45  4853.9  558.54
  4878.1  557.08  4907.7  556.28  4925.2  554.92  4938.0  554.59  4956.2  553.68
  4961.6  553.74  4979.1  553.02  4985.8  552.16  4991.2  552.49  5003.2  552.04
  5008.8  550.96  5009.0  550.46  5012.5  550.46  5012.8  550.96  5017.1  551.45
  5028.5  553.16  5033.6  552.98  5071.6  555.99  5081.7  556.08  5115.4  557.36
  5155.2  559.22  5211.0  562.41  5216.0  562.35  5278.6  565.47  5304.8  567.21
#Mann=7,-1,0
  4731.4    0.05       0  4938.0   0.035       0  5008.8   0.035       0
  5012.8   0.035       0  5017.1    0.05       0  5115.4    0.07       0
  5278.6    0.05       0
Bank Sta=5008.8,5012.8
Exp/Cntr=0.3,0.1

Type RM Length L Ch R = 1,5724,251,251,251
BEGIN DESCRIPTION:
X18680
END DESCRIPTION:
XS GIS Cut Line= 3
      2290010.24     13712954.27      2290341.01     13713175.65
      2290695.13     13713157.43
#Sta/Elev= 30
  4568.3  564.83  4573.5  564.83  4579.3  564.19  4651.4  562.39  4744.5  559.29
  4780.5  557.62  4810.5  557.12  4816.5  556.63  4858.3  555.58  4882.6  554.61
  4903.6  554.21  4910.9  554.46  4918.6  553.83  4924.6  554.14  4933.6  553.40
  4960.6  552.30  4965.7  551.22  4980.3  550.49  5010.4  550.51  5018.4  549.67
  5018.6  549.17  5022.1  549.17  5022.4  549.67  5030.4  551.23  5047.2  552.36
  5075.9  554.52  5120.5  556.88  5268.3  566.43  5273.3  566.13  5320.9  568.74
#Mann=5,-1,0
  4568.3   0.035       0  4858.3    0.05       0  5018.4    0.05       0
  5022.4    0.05       0  5047.2    0.07       0
Bank Sta=5018.4,5022.4
Exp/Cntr=0.3,0.1

Type RM Length L Ch R = 1,5473,235,235,235
BEGIN DESCRIPTION:
COTTONWOOD TRIBUTARY 6 12.0
END DESCRIPTION:
XS GIS Cut Line= 3
      2289824.97     13712824.96      2290375.00     13713425.00
      2290674.96     13713225.03
#Sta/Elev= 30
  4185.9  569.54  4242.4  568.31  4270.7  568.22  4292.3  566.34  4312.4  566.31
  4348.7  564.96  4419.3  563.65  4518.6  560.50  4596.3  558.84  4674.3  556.52
  4740.3  553.79  4872.6  551.99  4879.3  552.35  4949.4  550.16  4971.8  549.86
  4986.0  548.87  5002.9  548.93  5005.4  548.48  5005.7  547.98  5009.2  547.98
  5009.4  548.48  5049.5  549.81  5072.0  549.50  5100.5  551.90  5115.6  553.67
  5252.3  559.74  5265.8  561.08  5274.8  561.16  5280.8  561.87  5360.4  566.75
#Mann=6,-1,0
  4185.9    0.07       0  4312.4   0.035       0  4740.3    0.05       0
  4949.4    0.07       0  5005.4    0.05       0  5009.4    0.07       0
Bank Sta=5005.4,5009.4
Exp/Cntr=0.3,0.1

Type RM Length L Ch R = 1,5238,210,210,210
BEGIN DESCRIPTION:
X18679
END DESCRIPTION:
XS GIS Cut Line= 2
      2289815.01     13713709.50      2290799.38     13713581.90
#Sta/Elev= 30
  4486.0  557.82  4555.7  556.17  4576.7  556.13  4615.7  554.80  4738.1  552.05
  4768.3  550.69  4864.1  551.06  4899.4  550.65  4909.5  549.97  4929.7  548.22
  4946.8  546.04  4951.9  546.19  4959.9  545.55  4968.0  543.78  4968.3  543.28
  4971.8  543.28  4972.0  543.78  5000.3  544.66  5031.1  548.08  5062.9  549.40
  5100.2  551.16  5105.3  550.83  5161.6  551.86  5191.8  551.29  5258.7  553.73
  5322.9  554.64  5337.9  554.41  5373.4  555.69  5417.1  558.02  5478.6  560.17
#Mann=6,-1,0
  4486.0   0.035       0  4615.7    0.05       0  4864.1    0.07       0
  4968.0    0.05       0  4972.0    0.07       0  5062.9    0.05       0
Bank Sta=4968,4972
Exp/Cntr=0.3,0.1

Type RM Length L Ch R = 1,5028,235,235,235
BEGIN DESCRIPTION:
COTTONWOOD TRIBUTARY 6 11.0
END DESCRIPTION:
XS GIS Cut Line= 3
      2289807.15     13713938.67      2290278.51     13713837.11
      2290755.06     13713667.84
#Sta/Elev= 30
  4520.0  560.25  4705.3  554.80  4783.8  552.17  4834.9  551.89  4886.1  552.37
  4906.5  552.14  4916.8  551.57  4922.5  550.85  4936.5  548.67  4941.7  548.84
  4947.4  547.27  4967.9  543.49  4989.0  543.07  4989.2  542.57  4992.7  542.57
  4993.0  543.07  5055.1  543.16  5062.1  543.57  5072.7  545.87  5080.6  548.61
  5111.5  551.94  5142.3  553.05  5157.1  553.18  5178.9  553.66  5296.6  553.20
  5327.5  553.42  5401.7  555.38  5440.3  556.86  5496.7  558.26  5507.9  558.19
#Mann=5,-1,0
  4520.0    0.05       0  4922.5    0.07       0  4989.0    0.05       0
  4993.0    0.07       0  5157.1    0.05       0
Bank Sta=4989,4993
Exp/Cntr=0.3,0.1

Type RM Length L Ch R = 1,4793,153,153,153
BEGIN DESCRIPTION:
X18681
END DESCRIPTION:
XS GIS Cut Line= 3
      2289851.45     13714240.74      2290283.72     13714035.03
      2290770.37     13713714.93
#Sta/Elev= 30
  4520.5  562.75  4526.1  562.90  4557.6  561.08  4634.1  558.28  4662.4  558.10
  4685.1  557.15  4753.2  555.99  4768.1  555.09  4790.2  554.60  4821.3  553.03
  4872.3  551.21  4895.0  550.17  4912.0  547.83  4920.2  545.85  4934.2  543.29
  4983.8  543.10  4984.1  542.60  4987.6  542.60  4987.8  543.10  5152.2  543.37
  5167.2  545.32  5180.3  547.94  5188.3  549.93  5194.3  550.89  5208.0  551.99
  5266.6  553.73  5275.7  553.43  5317.8  553.50  5432.3  554.37  5581.7  558.99
#Mann=5,-1,0
  4520.5    0.05       0  4920.2    0.07       0  4983.8    0.05       0
  4987.8    0.07       0  5208.0    0.05       0
Bank Sta=4983.8,4987.8
Exp/Cntr=0.3,0.1

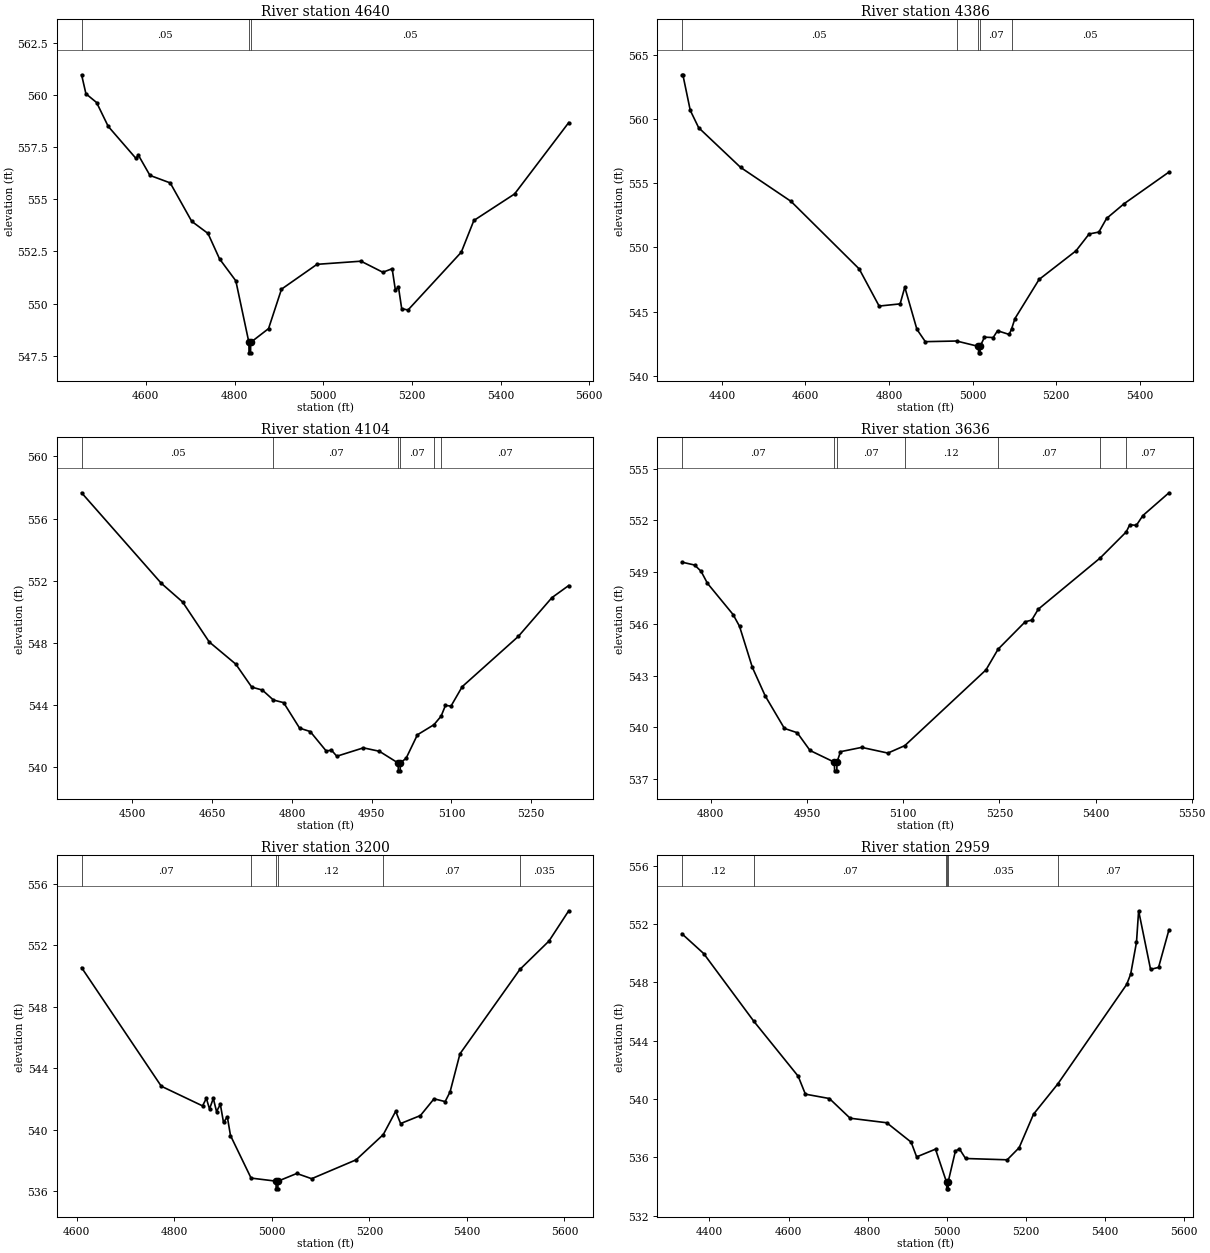
Type RM Length L Ch R = 1,4640,254,254,254
BEGIN DESCRIPTION:
X18678
END DESCRIPTION:
XS GIS Cut Line= 3
      2289895.70     13714350.13      2290325.38     13714204.30
      2290799.36     13713766.78
#Sta/Elev= 30
  4455.0  560.96  4464.8  560.05  4488.9  559.63  4515.0  558.49  4577.8  556.95
  4583.1  557.11  4609.2  556.14  4654.9  555.78  4703.4  553.94  4740.1  553.36
  4766.2  552.14  4802.9  551.09  4832.4  548.14  4832.7  547.64  4836.2  547.64
  4836.4  548.14  4876.7  548.80  4905.9  550.69  4986.0  551.88  5085.2  552.03
  5134.5  551.50  5155.5  551.67  5162.9  550.63  5169.7  550.80  5177.0  549.76
  5191.2  549.69  5311.4  552.46  5339.8  553.98  5431.6  555.25  5553.8  558.67
#Mann=3,-1,0
  4455.0    0.05       0  4832.4    0.05       0  4836.4    0.05       0
Bank Sta=4832.4,4836.4
Exp/Cntr=0.3,0.1

Type RM Length L Ch R = 1,4386,282,282,282
BEGIN DESCRIPTION:
COTTONWOOD TRIBUTARY 6 10.0
END DESCRIPTION:
XS GIS Cut Line= 3
      2289874.91     13714389.19      2290572.78     13714324.09
      2291018.10     13714191.27
#Sta/Elev= 30
  4304.3  563.43  4306.8  563.43  4324.5  560.66  4344.6  559.31  4445.0  556.22
  4565.5  553.58  4728.7  548.32  4776.4  545.43  4826.6  545.60  4837.8  546.90
  4866.8  543.62  4886.9  542.66  4961.7  542.71  5014.1  542.29  5014.4  541.79
  5017.9  541.79  5018.1  542.29  5028.4  543.01  5049.3  542.98  5059.7  543.51
  5087.6  543.22  5093.2  543.64  5101.4  544.46  5159.1  547.50  5247.5  549.73
  5278.8  551.04  5302.2  551.19  5320.6  552.25  5362.3  553.39  5469.9  555.86
#Mann=5,-1,0
  4304.3    0.05       0  4961.7    0.07       0  5014.1    0.05       0
  5018.1    0.07       0  5093.2    0.05       0
Bank Sta=5014.1,5018.1
Exp/Cntr=0.3,0.1

Type RM Length L Ch R = 1,4104,468,468,468
BEGIN DESCRIPTION:
COTTONWOOD TRIBUTARY 6 9.0
END DESCRIPTION:
XS GIS Cut Line= 3
      2289975.03     13714575.00      2290575.00     13714575.00
      2290875.00     13714675.00
#Sta/Elev= 30
  4404.5  557.66  4554.5  551.83  4594.5  550.63  4644.5  548.06  4694.5  546.63
  4724.5  545.15  4744.5  544.96  4765.2  544.32  4784.5  544.15  4814.5  542.51
  4834.5  542.29  4864.5  541.04  4874.5  541.09  4884.5  540.70  4934.5  541.24
  4964.5  541.02  5000.0  540.26  5000.2  539.76  5003.7  539.76  5004.0  540.26
  5015.0  540.58  5036.1  542.08  5067.2  542.73  5080.7  543.28  5088.8  543.97
  5099.3  543.93  5120.4  545.18  5225.8  548.41  5289.1  550.91  5320.7  551.69
#Mann=6,-1,0
  4404.5    0.05       0  4765.2    0.07       0  5000.0    0.05       0
  5004.0    0.07       0  5067.2    0.12       0  5080.7    0.07       0
Bank Sta=5000,5004
Exp/Cntr=0.3,0.1

Type RM Length L Ch R = 1,3636,436,436,436
BEGIN DESCRIPTION:
COTTONWOOD TRIBUTARY 6 8.0
END DESCRIPTION:
XS GIS Cut Line= 3
      2290124.96     13714975.00      2290375.00     13714975.00
      2290874.95     13714875.01
#Sta/Elev= 30
  4754.7  549.58  4774.7  549.41  4784.7  549.05  4794.7  548.35  4834.7  546.54
  4844.7  545.86  4864.7  543.48  4884.7  541.83  4914.7  539.94  4934.7  539.69
  4954.7  538.66  4992.7  537.98  4993.0  537.48  4996.5  537.48  4996.7  537.98
  5002.2  538.59  5035.3  538.84  5076.1  538.51  5102.5  538.94  5229.1  543.33
  5248.0  544.53  5290.3  546.12  5300.5  546.22  5310.7  546.85  5407.3  549.82
  5447.9  551.33  5453.5  551.75  5463.7  551.71  5473.9  552.28  5514.6  553.60
#Mann=7,-1,0
  4754.7    0.07       0  4992.7    0.05       0  4996.7    0.07       0
  5102.5    0.12       0  5248.0    0.07       0  5407.3    0.05       0
  5447.9    0.07       0
Bank Sta=4992.7,4996.7
Exp/Cntr=0.3,0.1

Type RM Length L Ch R = 1,3200,241,241,241
BEGIN DESCRIPTION:
COTTONWOOD TRIBUTARY 6 7.0
END DESCRIPTION:
XS GIS Cut Line= 3
      2290024.97     13715074.98      2290325.00     13715325.00
      2290924.97     13715225.00
#Sta/Elev= 30
  4609.9  550.55  4773.3  542.83  4857.9  541.55  4865.7  542.04  4872.2  541.35
  4880.0  542.04  4886.6  541.18  4894.4  541.65  4900.9  540.47  4908.7  540.84
  4915.2  539.62  4957.4  536.85  5008.6  536.65  5008.8  536.15  5012.3  536.15
  5012.6  536.65  5051.1  537.15  5081.6  536.81  5172.8  538.04  5228.4  539.68
  5253.9  541.20  5264.0  540.40  5304.6  540.92  5332.5  542.01  5355.3  541.83
  5365.4  542.46  5385.7  544.94  5508.5  550.43  5568.2  552.28  5608.7  554.25
#Mann=6,-1,0
  4609.9    0.07       0  4957.4    0.12       0  5008.6    0.05       0
  5012.6    0.12       0  5228.4    0.07       0  5508.5   0.035       0
Bank Sta=5008.6,5012.6
Exp/Cntr=0.3,0.1

Type RM Length L Ch R = 1,2959,350,350,350
BEGIN DESCRIPTION:
X18677
END DESCRIPTION:
XS GIS Cut Line= 3
      2289671.30     13715422.18      2290287.62     13715569.75
      2290881.15     13715500.43
#Sta/Elev= 30
  4330.1  551.33  4385.3  549.97  4511.7  545.34  4624.2  541.56  4642.4  540.33
  4703.1  540.03  4755.5  538.68  4848.0  538.37  4909.7  537.04  4923.6  536.03
  4971.3  536.56  4998.2  534.38  4999.5  534.34  4999.7  533.84  5003.2  533.84
  5003.5  534.34  5021.6  536.43  5031.7  536.58  5047.3  535.92  5152.5  535.83
  5182.7  536.66  5219.1  538.96  5280.4  541.03  5454.5  547.85  5464.6  548.56
  5479.3  550.74  5484.7  552.90  5514.9  548.88  5535.1  549.02  5561.4  551.60
#Mann=6,-1,0
  4330.1    0.12       0  4511.7    0.07       0  4998.2   0.035       0
  4999.5   0.035       0  5003.5   0.035       0  5280.4    0.07       0
Bank Sta=4999.5,5003.5
Exp/Cntr=0.3,0.1

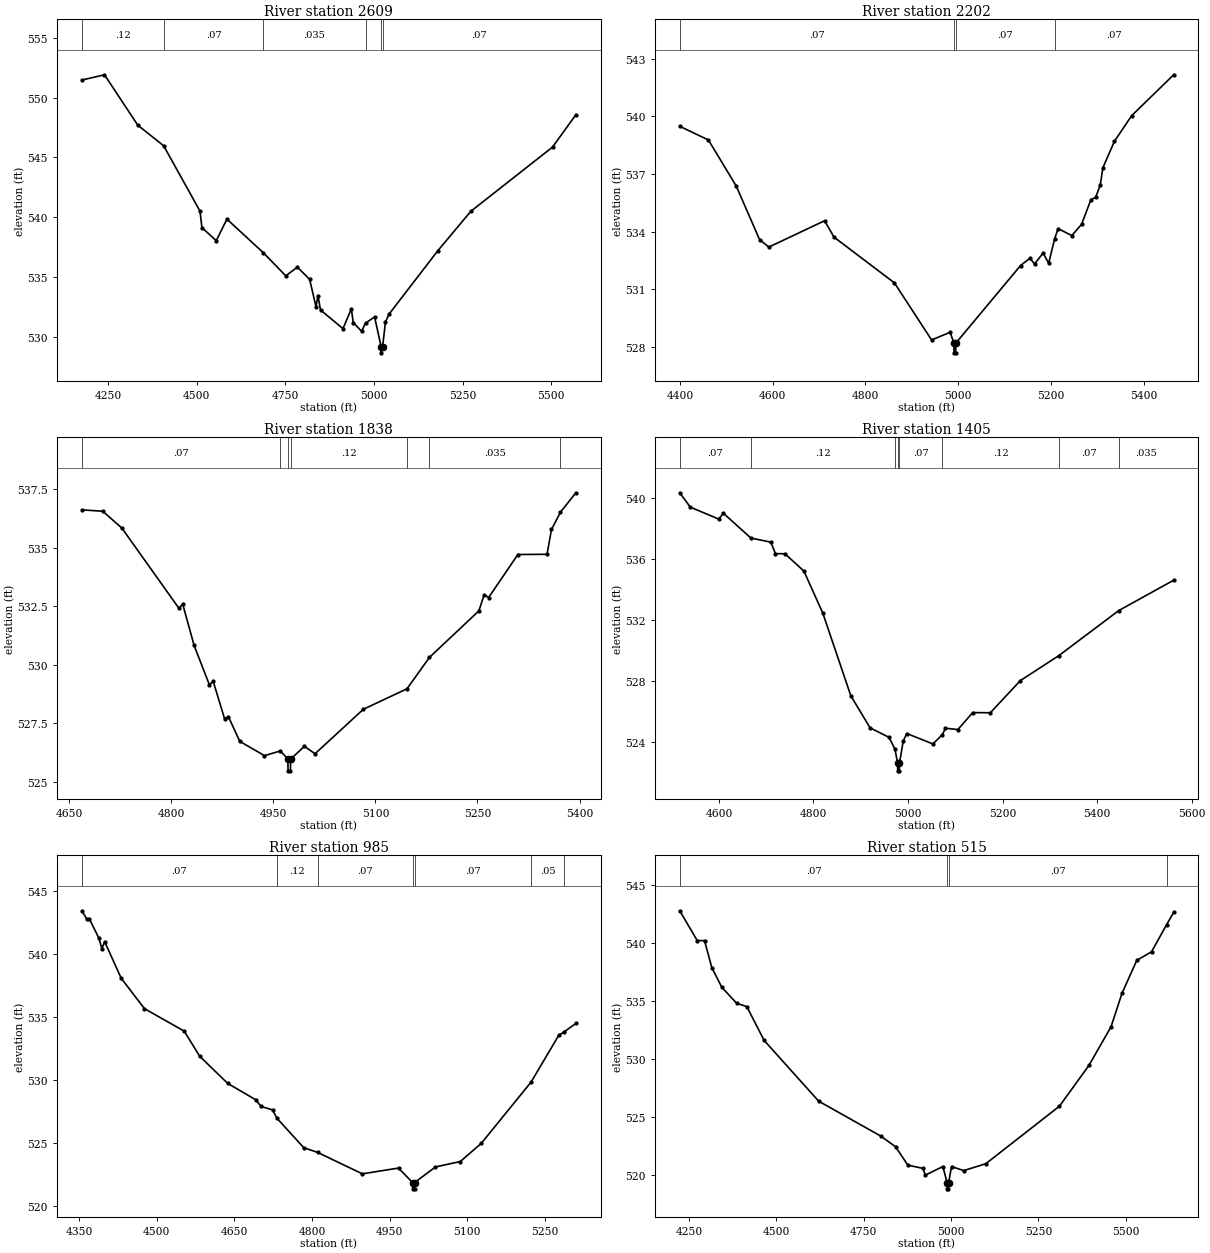
Type RM Length L Ch R = 1,2609,407,407,407
BEGIN DESCRIPTION:
COTTONWOOD TRIBUTARY 6 6.0
END DESCRIPTION:
XS GIS Cut Line= 3
      2289567.13     13715556.72      2290331.03     13715886.59
      2290890.47     13715929.96
#Sta/Elev= 30
  4175.9  551.46  4239.5  551.90  4333.5  547.69  4406.4  545.97  4508.9  540.51
  4514.4  539.13  4554.8  538.04  4584.9  539.84  4687.4  537.04  4750.9  535.10
  4783.6  535.83  4818.2  534.81  4836.3  532.51  4841.7  533.46  4848.9  532.25
  4912.3  530.69  4935.8  532.35  4941.2  531.20  4964.7  530.47  4975.9  531.15
  5001.4  531.67  5020.0  529.17  5020.2  528.67  5024.0  529.17  5032.0  531.23
  5042.1  531.90  5179.5  537.19  5272.7  540.49  5503.4  545.86  5569.1  548.56
#Mann=6,-1,0
  4175.9    0.12       0  4406.4    0.07       0  4687.4   0.035       0
  4975.9    0.07       0  5020.0    0.05       0  5024.0    0.07       0
Bank Sta=5020,5024
Exp/Cntr=0.3,0.1

Type RM Length L Ch R = 1,2202,364,364,364
BEGIN DESCRIPTION:
COTTONWOOD TRIBUTARY 6 5.0
END DESCRIPTION:
XS GIS Cut Line= 3
      2289723.34     13716181.72      2290322.35     13716229.47
      2290781.18     13716155.88
#Sta/Elev= 30
  4399.4  539.48  4461.3  538.77  4521.4  536.37  4571.6  533.59  4591.7  533.20
  4712.0  534.57  4732.1  533.72  4862.5  531.34  4942.8  528.37  4982.9  528.77
  4990.9  528.20  4991.2  527.70  4994.7  527.70  4994.9  528.20  5134.7  532.24
  5154.9  532.62  5165.0  532.32  5183.3  532.89  5195.4  532.36  5208.3  533.64
  5215.7  534.16  5245.3  533.80  5266.3  534.38  5286.6  535.67  5296.7  535.78
  5306.8  536.44  5312.3  537.32  5337.2  538.70  5374.3  540.03  5465.0  542.16
#Mann=4,-1,0
  4399.4    0.07       0  4990.9   0.035       0  4994.9    0.07       0
  5208.3    0.07       0
Bank Sta=4990.9,4994.9
Exp/Cntr=0.3,0.1

Type RM Length L Ch R = 1,1838,433,433,433
BEGIN DESCRIPTION:
COTTONWOOD TRIBUTARY 6 4.0
END DESCRIPTION:
XS GIS Cut Line= 3
      2290075.00     13716725.00      2290375.00     13716575.00
      2290674.98     13716325.02
#Sta/Elev= 30
  4668.7  536.62  4699.4  536.56  4727.4  535.84  4811.3  532.41  4816.8  532.59
  4833.6  530.82  4856.0  529.14  4861.6  529.29  4878.3  527.69  4883.9  527.78
  4900.7  526.72  4937.0  526.11  4960.4  526.31  4971.4  525.96  4971.6  525.46
  4975.1  525.46  4975.4  525.96  4995.7  526.51  5011.3  526.19  5082.2  528.09
  5146.5  528.97  5179.4  530.31  5252.1  532.30  5259.9  532.99  5266.4  532.87
  5309.4  534.71  5352.3  534.72  5358.8  535.78  5372.0  536.52  5394.6  537.35
#Mann=7,-1,0
  4668.7    0.07       0  4960.4    0.12       0  4971.4    0.05       0
  4975.4    0.12       0  5146.5    0.07       0  5179.4   0.035       0
  5372.0    0.07       0
Bank Sta=4971.4,4975.4
Exp/Cntr=0.3,0.1

Type RM Length L Ch R = 1,1405,420,420,420
BEGIN DESCRIPTION:
COTTONWOOD TRIBUTARY 6 3.0
END DESCRIPTION:
XS GIS Cut Line= 3
      2289892.65     13716954.30      2290375.00     13716975.00
      2290908.31     13716798.04
#Sta/Elev= 30
  4517.2  540.32  4539.6  539.38  4599.6  538.60  4609.6  538.98  4667.7  537.36
  4709.7  537.09  4719.7  536.34  4739.8  536.33  4779.8  535.20  4819.8  532.45
  4879.1  527.04  4919.9  524.94  4960.0  524.32  4972.6  523.53  4978.0  522.63
  4978.2  522.13  4981.7  522.13  4982.0  522.63  4990.0  524.09  4997.5  524.57
  5052.8  523.89  5072.8  524.50  5079.2  524.92  5105.4  524.83  5137.0  525.94
  5174.2  525.93  5237.6  528.03  5319.2  529.67  5445.6  532.61  5561.9  534.60
#Mann=8,-1,0
  4517.2    0.07       0  4667.7    0.12       0  4972.6    0.07       0
  4978.0    0.05       0  4982.0    0.07       0  5072.8    0.12       0
  5319.2    0.07       0  5445.6   0.035       0
Bank Sta=4978,4982
Exp/Cntr=0.3,0.1

Type RM Length L Ch R = 1,985,470,470,470
BEGIN DESCRIPTION:
COTTONWOOD TRIBUTARY 6 2.0
END DESCRIPTION:
XS GIS Cut Line= 3
      2289874.98     13717074.99      2290475.00     13717325.00
      2290775.04     13717274.99
#Sta/Elev= 30
  4355.4  543.46  4364.6  542.81  4370.0  542.80  4387.9  541.31  4393.9  540.45
  4399.3  541.01  4431.3  538.10  4476.2  535.69  4553.1  533.90  4582.9  531.91
  4637.1  529.75  4691.3  528.45  4701.5  527.92  4723.8  527.65  4732.0  526.99
  4783.9  524.65  4810.9  524.27  4897.1  522.57  4967.0  523.03  4994.2  521.88
  4994.5  521.38  4998.0  521.38  4998.2  521.88  5038.4  523.12  5086.5  523.55
  5127.1  525.00  5223.0  529.85  5276.6  533.57  5286.7  533.84  5309.6  534.51
#Mann=7,-1,0
  4355.4    0.07       0  4732.0    0.12       0  4810.9    0.07       0
  4994.2    0.05       0  4998.2    0.07       0  5223.0    0.05       0
  5286.7    0.07       0
Bank Sta=4994.2,4998.2
Exp/Cntr=0.3,0.1

Type RM Length L Ch R = 1,515,284,284,284
BEGIN DESCRIPTION:
COTTONWOOD TRIBUTARY 6 1.0
END DESCRIPTION:
XS GIS Cut Line= 3
      2289774.99     13717224.99      2290375.00     13717725.00
      2290975.01     13717525.00
#Sta/Elev= 30
  4223.6  542.76  4273.7  540.20  4294.6  540.19  4315.4  537.87  4344.0  536.18
  4387.0  534.79  4415.6  534.52  4465.1  531.61  4621.3  526.38  4798.3  523.39
  4841.3  522.46  4876.4  520.88  4919.4  520.60  4926.5  520.02  4976.7  520.76
  4989.0  519.34  4989.2  518.84  4992.7  518.84  4993.0  519.34  5001.4  520.76
  5036.3  520.41  5099.5  521.00  5310.3  525.95  5394.7  529.46  5457.9  532.78
  5489.5  535.68  5531.7  538.50  5573.8  539.23  5616.8  541.56  5637.1  542.62
#Mann=4,-1,0
  4223.6    0.07       0  4989.0    0.05       0  4993.0    0.07       0
  5616.8    0.05       0
Bank Sta=4989,4993
Exp/Cntr=0.3,0.1

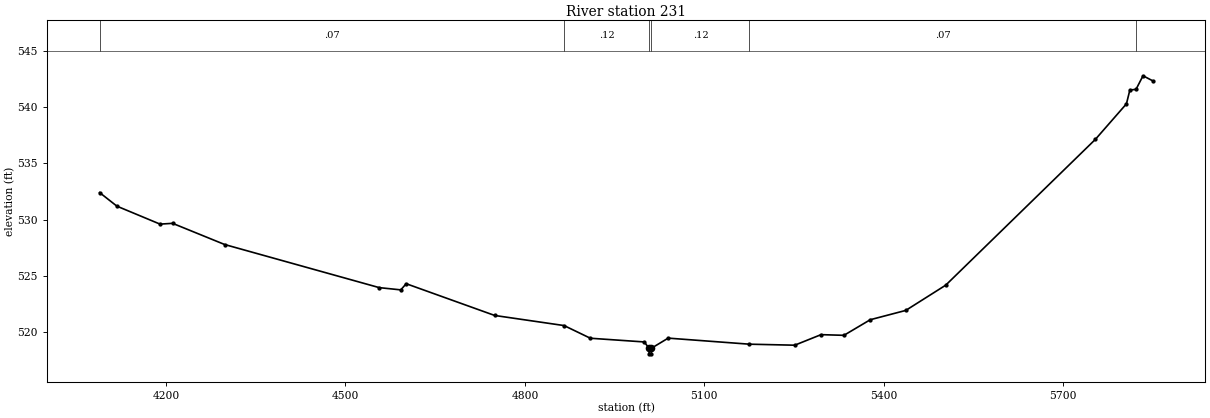
Type RM Length L Ch R = 1,231,0,0,0
BEGIN DESCRIPTION:
X18676
END DESCRIPTION:
XS GIS Cut Line= 4
      2289632.81     13717447.70      2289967.22     13717949.30
      2290477.66     13717943.44      2291049.78     13717639.86
#Sta/Elev= 30
  4088.9  532.40  4117.8  531.19  4189.9  529.59  4210.9  529.66  4298.1  527.77
  4556.5  523.93  4592.5  523.73  4601.5  524.28  4749.5  521.45  4865.5  520.55
  4909.5  519.42  4999.6  519.09  5007.6  518.53  5007.8  518.03  5011.3  518.03
  5011.6  518.53  5039.6  519.43  5175.5  518.89  5251.2  518.80  5295.2  519.74
  5333.5  519.68  5377.5  521.07  5436.9  521.90  5503.7  524.15  5753.9  537.14
  5805.9  540.31  5811.6  541.54  5821.9  541.60  5833.6  542.81  5849.9  542.36
#Mann=6,-1,0
  4088.9    0.07       0  4865.5    0.12       0  5007.6    0.05       0
  5011.6    0.12       0  5175.5    0.07       0  5821.9    0.05       0
Bank Sta=5007.6,5011.6
Exp/Cntr=0.3,0.1

Chan Stop Cuts=-1