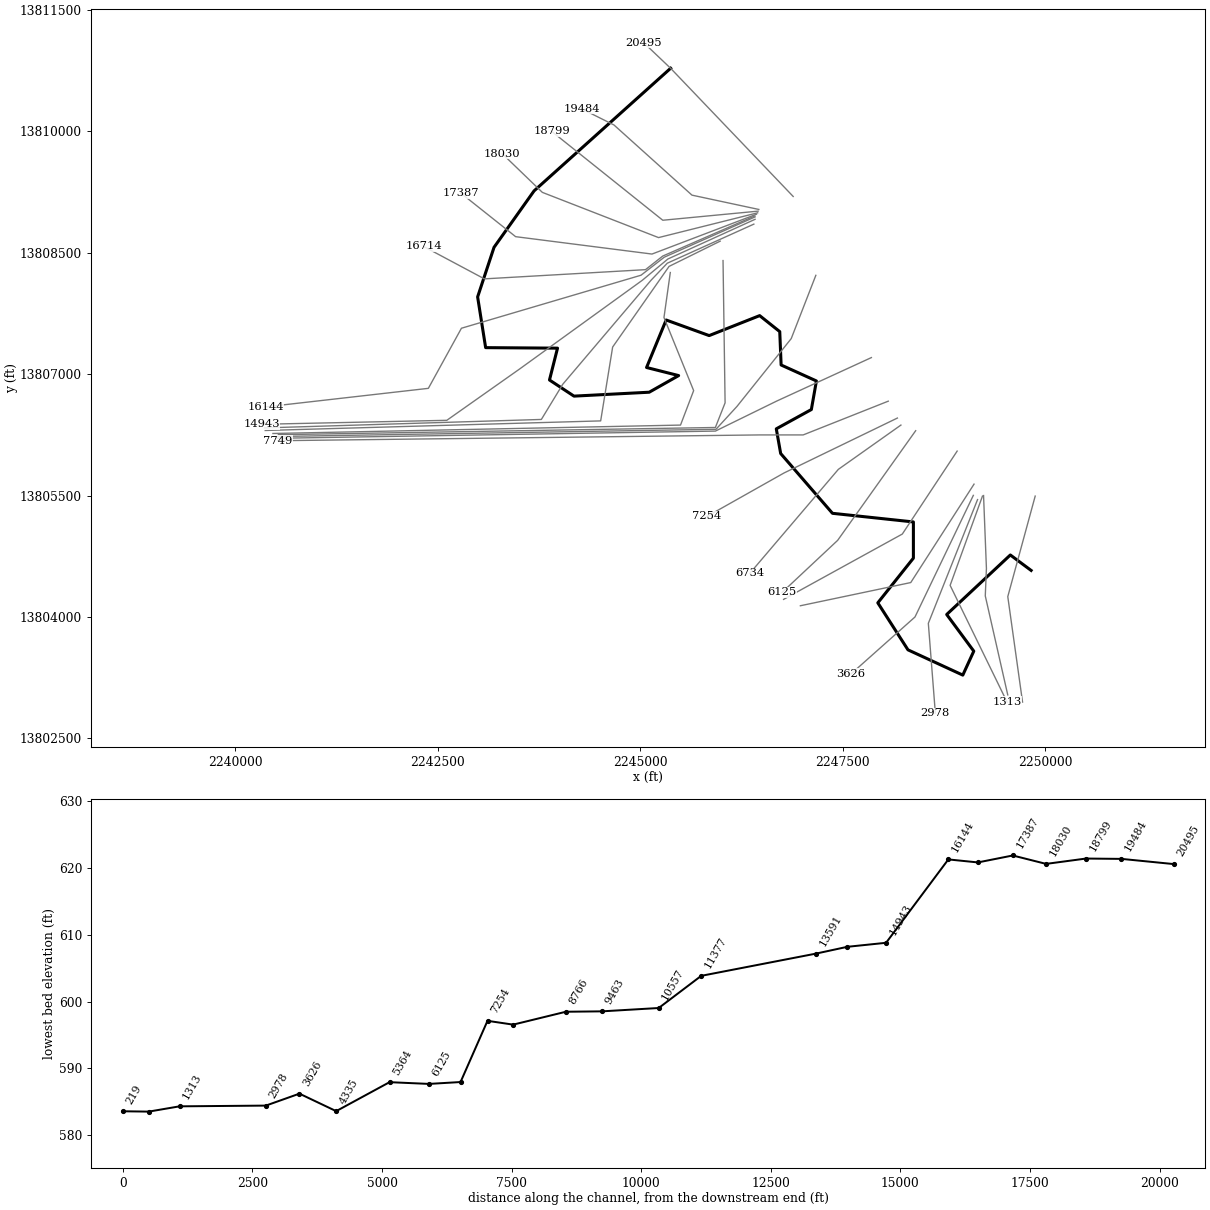
--- Comal River.prj (project) ---

Proj Title=Comal River Base Level Engineering
Current Plan=p01
Default Exp/Contr=0.3,0.1
English Units
Geom File=g01
Flow File=f01
Plan File=p01
Y Axis Title=Elevation
X Axis Title(PF)=Main Channel Distance
X Axis Title(XS)=Station
BEGIN DESCRIPTION:
Comal River
END DESCRIPTION:
DSS Export Rating Curves= 0
DSS Export Rating Curve Sorted= 0
DSS Export Volume Flow Curves= 0
DXF OffsetX= 0
DXF OffsetY= 0
DXF ScaleX= 1
DXF ScaleY= 10

--- Comal River.p01 (plan) ---

Plan Title=Multiple Run
Program Version=4.10
Short Identifier=Multiple
Geom File=g01
Flow File=f01
Subcritical Flow
K Sum by GR= 0
Std Step Tol= 0.01
Critical Tol= 0.01
Num of Std Step Trials= 20
Max Error Tol= 0.3
Flow Tol Ratio= 0.001
Split Flow NTrial= 30
Split Flow Tol= 0.02
Split Flow Ratio= 0.02
Log Output Level= 0
Friction Slope Method= 1
Unsteady Friction Slope Method= 2
Unsteady Bridges Friction Slope Method= 1
Parabolic Critical Depth
Global Vel Dist= 1 , 1 , 1
Global Log Level= 0
CheckData=True
Encroach Param=-1 ,0,0, 0
BEGIN DESCRIPTION:
Multiple Run
END DESCRIPTION:
Computation Interval=1HOUR
Output Interval=1HOUR
Run HTab= 0
Run UNet= 0
Run PostProcess= 0
Run WQNet= 0
UNET Theta= 1
UNET Theta Warmup= 1
UNET ZTol= 0.02
UNET ZSATol= 0.05
UNET MxIter= 20
UNET MaxInSteps= 0
UNET DtIC= 0
UNET DtMin= 0
UNET MaxCRTS= 20
UNET WFStab= 2
UNET SFStab= 1
UNET WFX= 1
UNET SFX= 1
UNET DSS MLevel= 4
UNET DZMax Abort= 100
UNET Convert EG Bridges= 0
UNET Use Existing IB Tables=-1
UNET Froude Reduction=False
UNET Froude Limit= 1
UNET Froude Power= 10
UNET Time Slicing=0,0, 5
UNET Junction Losses=0
Instantaneous Interval=1HOUR
Write IC File= 0
Write IC File at Sim End=0
Echo Input=False
Echo Parameters=False
Echo Output=False
Write Detailed= 0
WQ AD Non Conservative
WQ ULTIMATE=-1
WQ Max Comp Step=1HOUR
WQ Output Interval=15MIN
WQ Output Selected Increments= 0
WQ Output face flow=0
WQ Output face velocity=0
WQ Output face area=0
WQ Output face dispersion=0
WQ Output cell volume=0
WQ Output cell surface area=0
WQ Output cell continuity=0
WQ Output cumulative cell continuity=0
WQ Output face conc=0
WQ Output face dconc_dx=0
WQ Output face courant=0
WQ Output face peclet=0
WQ Output face adv mass=0
WQ Output face disp mass=0
WQ Output cell mass=0
WQ Output cell source sink temp=0
WQ Output cell source sink nsm=0
WQ Output MaxMinRange=-1
WQ Daily Max Min Mean=-1
WQ Daily Range=0
WQ Daily Time=0
WQ Create Restart=0
WQ Fixed Restart=0
WQ System Summary=0
WQ Use Fixed Temperature=0
Sorting and Armoring Iterations= 10
XS Update Threshold= 0.02
Hydraulics Update Threshold= 0.02
Energy Slope Method= 1
Volume Change Method= 0
XS Weighting Method= 0
Number of US Weighted Cross Sections= 1
Number of DS Weighted Cross Sections= 1
Upstream XS Weight=0.25
Main XS Weight=0.5
Downstream XS Weight=0.25
Number of DS XS's Weighted with US Boundary= 1
Upstream Boundary Weight= 1
Weight of XSs Associated with US Boundary= 0
Number of US XS's Weighted with DS Boundary= 1
Downstream Boundary Weight= 0.5
Weight of XSs Associated with DS Boundary= 0.5
Sediment Output Level= 4
Mass or Volume Output= 0
Output Increment Type= 1
Profile and TS Output Increment= 10
XS Output Flag= 0
XS Output Increment= 10
Disregard all LS=0
Disregard all Conn=0
Disregard all Breaches=0
Disregard all Pumps=0

--- Comal River.f01 (steady flow) ---

Flow Title=Multiple
Program Version=4.10
Number of Profiles= 7
Profile Names=10-year,25-year,50-year,1pct_min,100-year,1pct_plu,500-year
River Rch & RM=Comal River,Reach-1         ,20495
    2968    5166    7300    4971    9918   19790   18140
River Rch & RM=Comal River,Reach-1         ,19484
    3022    5261    7436    5063   10103   20157   18477
River Rch & RM=Comal River,Reach-1         ,16714
    3000    5217    7367    5013   10001   19956   18262
River Rch & RM=Comal River,Reach-1         ,16144
    3460    6041    8555    5834   11640   23225   21349
River Rch & RM=Comal River,Reach-1         ,7254
   12761   22810   32833   22678   45248   90282   85041
Boundary for River Rch & Prof#=Comal River,Reach-1         , 1
Up Type= 0
Dn Type= 3
Dn Slope=0.002
Boundary for River Rch & Prof#=Comal River,Reach-1         , 2
Up Type= 0
Dn Type= 3
Dn Slope=0.002
Boundary for River Rch & Prof#=Comal River,Reach-1         , 3
Up Type= 0
Dn Type= 3
Dn Slope=0.002
Boundary for River Rch & Prof#=Comal River,Reach-1         , 4
Up Type= 0
Dn Type= 3
Dn Slope=0.002
Boundary for River Rch & Prof#=Comal River,Reach-1         , 5
Up Type= 0
Dn Type= 3
Dn Slope=0.002
Boundary for River Rch & Prof#=Comal River,Reach-1         , 6
Up Type= 0
Dn Type= 3
Dn Slope=0.002
Boundary for River Rch & Prof#=Comal River,Reach-1         , 7
Up Type= 0
Dn Type= 3
Dn Slope=0.002
DSS Import GetInterval= 0
DSS Import GetPeak= 0
DSS Import FillOption= 0

--- Comal River.g01 (geometry) ---

Geom Title=Existing Conditions
Program Version=4.10

River Reach=Comal River     ,Reach-1
Reach XY= 30
      2245374.26     13810775.49      2243688.36     13809261.64
      2243193.83     13808564.58      2242991.31      13807952.3
      2243090.21     13807325.89      2243977.75     13807319.58
      2243878.53     13806926.47      2244180.94     13806727.26
      2245109.78     13806775.52      2245473.05     13806980.89
      2245076.98     13807080.62      2245318.81     13807667.19
      2245850.07     13807474.77      2246473.42     13807721.33
      2246721.46     13807523.54      2246738.36     13807111.65
      2247173.97     13806914.57      2247111.64     13806561.65
      2246678.74     13806323.44      2246732.76     13806018.79
       2247372.3     13805280.36      2248371.49     13805173.75
      2248371.39      13804726.5      2247932.08       13804175.
      2248304.42     13803594.58      2248981.45     13803282.64
      2249117.02     13803578.35       2248782.5     13804031.05
      2249568.27     13804765.89        2249825.       13804575.

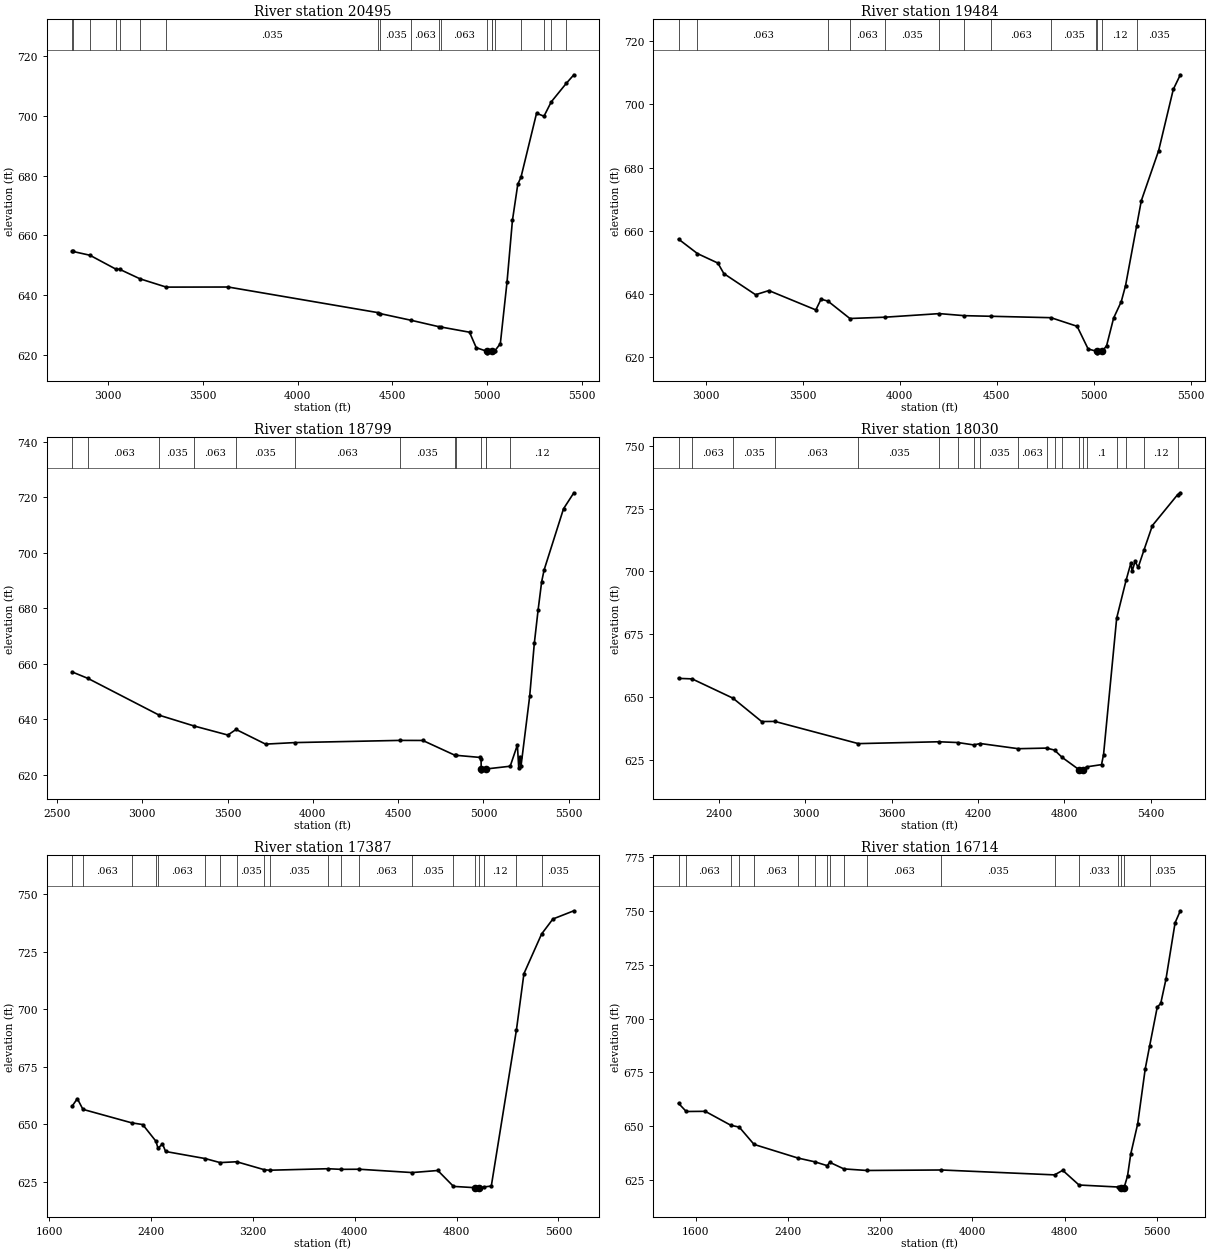
Type RM Length L Ch R = 1 ,20495   ,1011,1011,1011
BEGIN DESCRIPTION:
Blieders Creek 11.0
END DESCRIPTION:
XS GIS Cut Line= 3
       2246887.3     13809192.39      2245373.57     13810775.55
      2245042.32      13811090.7
#Sta/Elev= 30
  2809.7  654.59  2813.2  654.59  2903.7  653.31  3039.7  648.69    3060  648.62
  3168.5   645.4  3306.8  642.63  3633.6  642.66  4422.1   634.1  4434.4  633.77
  4599.1  631.51  4746.3  629.35  4753.7  629.29  4906.7  627.52  4942.2  622.34
  4999.1  621.11  4999.6  620.61  5026.2  621.11    5028  621.13  5038.6  621.16
  5069.3  623.66  5104.9  644.48  5133.2  664.99  5161.5   677.1  5178.5   679.5
  5260.4  700.87  5299.6  699.89  5338.2  704.71  5417.2  710.89  5457.3  713.77
#Mann= 20 ,-1 , 0
  2809.7    .063       0  2813.2    .094       0  2903.7    .035       0
  3039.7    .094       0    3060    .035       0  3168.5    .063       0
  3306.8    .035       0  4422.1    .063       0  4434.4    .035       0
  4599.1    .063       0  4746.3    .094       0  4753.7    .063       0
  4999.1     .05       0  5026.2    .063       0    5028    .035       0
  5038.6    .063       0  5178.5    .094       0  5299.6    .035       0
  5338.2    .063       0  5417.2    .035       0
Bank Sta=4999.1,5026.2
XS Rating Curve= 0 ,0
Exp/Cntr=0.3,0.1

Type RM Length L Ch R = 1 ,19484   ,685,685,685
BEGIN DESCRIPTION:
Blieders Creek 10.0
END DESCRIPTION:
XS GIS Cut Line= 4
      2246463.33     13809032.15      2245637.66     13809208.86
        2244675.       13810075.      2244275.03     13810274.98
#Sta/Elev= 30
  2860.9  657.37  2958.5  652.79  3063.7  649.79  3094.5  646.46    3258  639.78
  3326.5  641.09  3568.6  634.97  3595.5  638.36  3630.9  637.76  3744.1  632.25
  3925.6  632.67  4205.3   633.8  4334.2  633.15  4469.8  632.96  4780.8  632.51
  4915.4  629.79  4972.2  622.61  5014.9   621.9  5017.4  621.89  5017.9  621.39
  5044.6  621.89  5067.3  623.62  5103.6   632.4  5142.8  637.57  5165.1  642.67
  5222.6  661.67  5246.2   669.5  5335.6  685.36  5411.1  704.74  5447.4  709.36
#Mann= 13 ,-1 , 0
  2860.9    .094       0  2958.5    .063       0  3630.9    .035       0
  3744.1    .063       0  3925.6    .035       0  4205.3    .063       0
  4334.2    .035       0  4469.8    .063       0  4780.8    .035       0
  5014.9     .12       0  5017.4    .035       0  5044.6     .12       0
  5222.6    .035       0
Bank Sta=5017.4,5044.6
XS Rating Curve= 0 ,0
Exp/Cntr=0.3,0.1

Type RM Length L Ch R = 1 ,18799   ,769,769,769
BEGIN DESCRIPTION:
X18261
END DESCRIPTION:
XS GIS Cut Line= 3
      2246454.41     13809011.39      2245277.38     13808898.84
      2243903.13     13809998.24
#Sta/Elev= 30
  2588.2  657.06  2681.5  654.72  3100.2  641.45  3304.7  637.57  3501.8  634.33
  3549.7  636.34  3722.8  631.06  3892.9  631.61  4509.4   632.4  4644.5  632.38
  4831.1  627.11  4840.1  627.03  4978.4  626.28  4986.4   625.7  4987.2  621.94
  4987.7  621.44  5014.5  621.94  5016.7  622.12  5157.2   623.1  5199.3  630.75
  5207.4  622.47  5213.8  626.56  5220.8  623.23  5271.4  648.26  5298.6  667.33
    5321  679.43  5341.8  689.57  5356.2   693.8  5469.9  715.81  5530.5  721.56
#Mann= 13 ,-1 , 0
  2588.2    .094       0  2681.5    .063       0  3100.2    .035       0
  3304.7    .063       0  3549.7    .035       0  3892.9    .063       0
  4509.4    .035       0  4831.1      .1       0  4840.1    .035       0
  4987.2    .035       0  5014.5    .035       0  5016.7    .033       0
  5157.2     .12       0
Bank Sta=4987.2,5014.5
XS Rating Curve= 0 ,0
Exp/Cntr=0.3,0.1

Type RM Length L Ch R = 1 ,18030   ,643,643,643
BEGIN DESCRIPTION:
X18262
END DESCRIPTION:
XS GIS Cut Line= 4
      2246448.47     13808990.63      2245224.85     13808684.68
      2243790.25     13809243.06      2243295.74     13809720.21
#Sta/Elev= 30
  2117.6  657.43  2211.8  657.23  2496.3  649.54  2695.3  640.26  2787.4   640.3
  3367.5  631.47  3925.9  632.21  4059.5   631.9  4169.6  630.95  4215.3  631.51
  4478.9  629.45  4676.3  629.69  4730.9   628.9  4783.2  626.03  4900.5  621.14
    4901  620.64  4927.8  621.14  4953.5  622.22  5057.8  623.11  5071.9  627.12
  5163.1  681.41  5228.5  696.47  5262.8  703.49    5270  699.99  5291.1  703.96
  5312.5  701.59  5353.8  708.66  5411.5  718.26  5585.9  730.48  5605.5  731.28
#Mann= 20 ,-1 , 0
  2117.6    .094       0  2211.8    .063       0  2496.3    .035       0
  2787.4    .063       0  3367.5    .035       0  3925.9    .063       0
  4059.5    .035       0  4169.6    .063       0  4215.3    .035       0
  4478.9    .063       0  4676.3    .035       0  4730.9      .1       0
  4783.2    .035       0  4900.5     .05       0  4927.8    .035       0
  4953.5      .1       0  5163.1    .035       0  5228.5    .063       0
  5353.8     .12       0  5585.9    .063       0
Bank Sta=4900.5,4927.8
XS Rating Curve= 0 ,0
Exp/Cntr=0.3,0.1

Type RM Length L Ch R = 1 ,17387   ,673,673,673
BEGIN DESCRIPTION:
X18263
END DESCRIPTION:
XS GIS Cut Line= 4
      2246433.68     13808972.84      2245143.96     13808481.44
      2243460.39     13808696.18       2242783.3     13809234.38
#Sta/Elev= 30
  1778.9  657.84  1820.3  661.13  1864.3  656.48  2246.9  650.62    2334  649.86
  2437.6  642.63  2454.2  639.52  2489.1  641.49  2513.8  638.15  2825.1  635.07
  2941.2  633.32  3072.3  633.68  3290.7  630.19  3330.3     630  3789.1  630.65
  3892.6  630.38  4034.6  630.43  4450.8  628.98  4652.2  629.88  4775.5  622.96
  4945.2   622.4  4945.7   621.9  4972.6   622.4  5013.8  622.71  5072.6  623.11
  5269.9     691  5328.9  715.52  5467.9  732.79  5556.4   739.3  5721.2  742.88
#Mann= 20 ,-1 , 0
  1778.9    .094       0  1864.3    .063       0  2246.9    .094       0
  2437.6      .1       0  2454.2    .063       0  2825.1    .094       0
  2941.2    .063       0  3072.3    .035       0  3290.7    .063       0
  3330.3    .035       0  3789.1    .063       0  3892.6    .035       0
  4034.6    .063       0  4450.8    .035       0  4775.5    .033       0
  4945.2    .033       0  4972.6    .033       0  5013.8     .12       0
  5269.9    .063       0  5467.9    .035       0
Bank Sta=4945.2,4972.6
XS Rating Curve= 0 ,0
Exp/Cntr=0.3,0.1

Type RM Length L Ch R = 1 ,16714   ,570,570,570
BEGIN DESCRIPTION:
Blieders Creek 9.0
END DESCRIPTION:
XS GIS Cut Line= 5
      2246412.96     13808952.11      2245277.29     13808456.92
      2245063.92      13808288.8        2243075.       13808175.
      2242324.96     13808575.02
#Sta/Elev= 30
  1450.6  660.63  1517.4  656.83    1682  656.91  1903.9  650.43  1977.1  649.57
  2105.7  641.52  2486.4  635.18  2632.3  633.43  2739.9  631.64  2762.4  633.19
  2884.9  630.13  3084.2   629.4  3731.6  629.63  4712.7  627.35  4783.1  629.47
  4924.6  622.64  5266.8   621.7  5287.8  621.36  5288.3  620.86  5315.2  621.36
  5345.4  626.83    5373  636.98  5433.2     651  5499.1  676.73  5537.8  687.47
  5603.2  705.39  5633.4  707.07  5678.7  718.33    5758  744.61  5803.4  750.18
#Mann= 18 ,-1 , 0
  1450.6    .094       0  1517.4    .063       0  1903.9    .094       0
  1977.1      .1       0  2105.7    .063       0  2486.4    .094       0
  2632.3    .063       0  2739.9      .1       0  2762.4    .063       0
  2884.9    .035       0  3084.2    .063       0  3731.6    .035       0
  4712.7     .12       0  4924.6    .033       0  5266.8     .12       0
  5287.8    .033       0  5315.2     .12       0  5537.8    .035       0
Bank Sta=5287.8,5315.2
XS Rating Curve= 0 ,0
Exp/Cntr=0.3,0.1

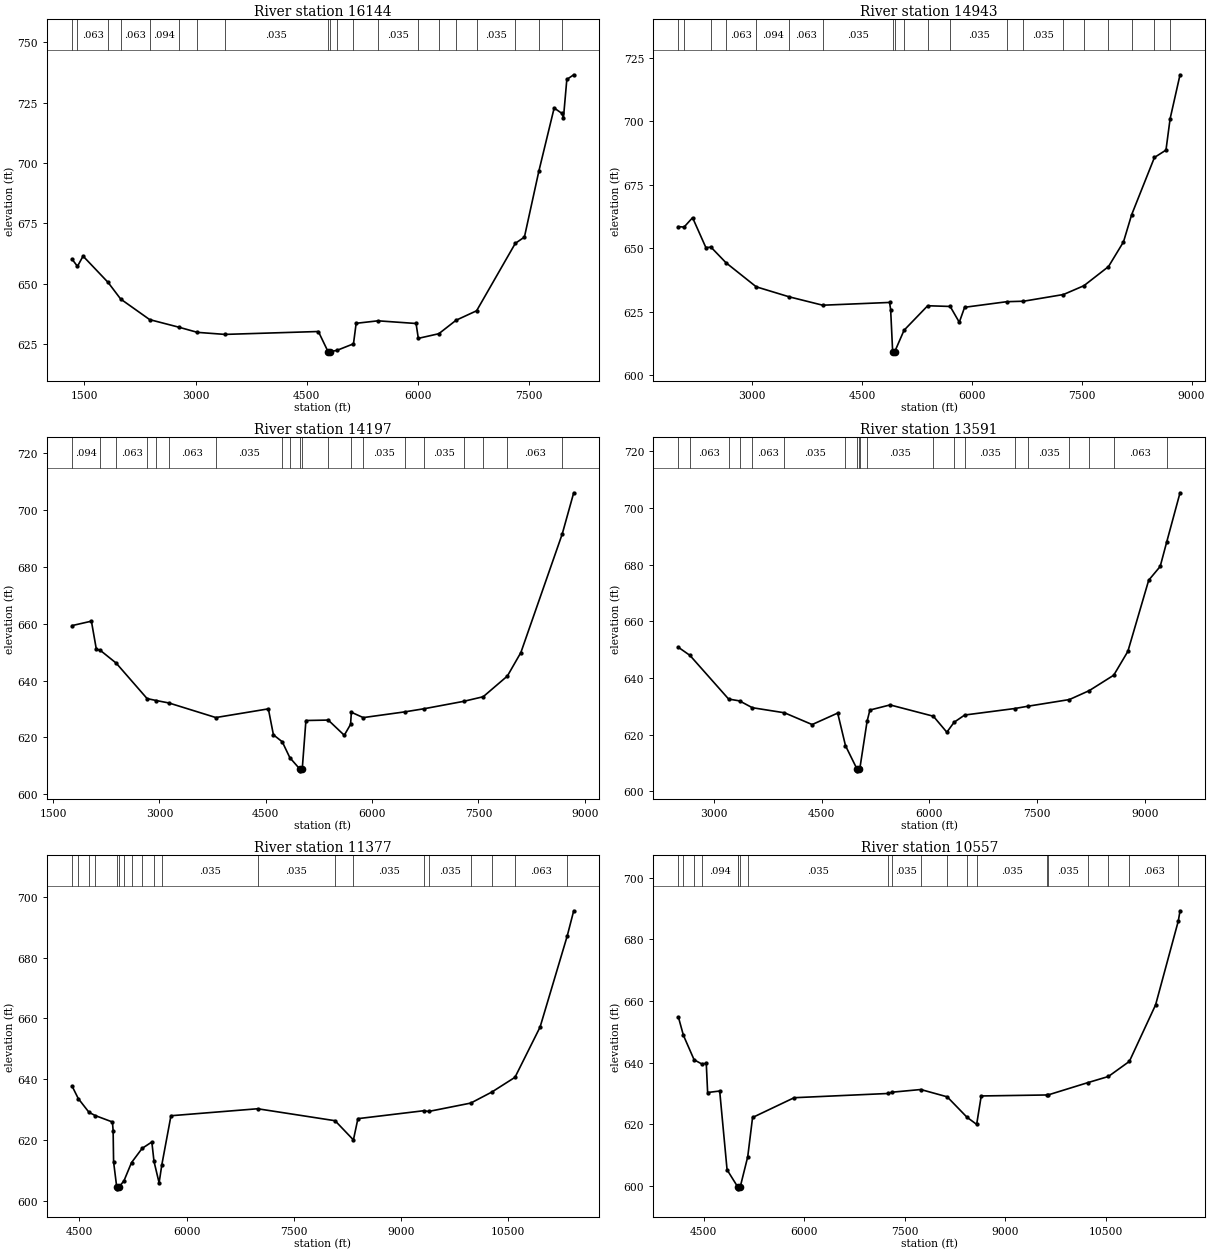
Type RM Length L Ch R = 1 ,16144   ,1201,1201,1201
BEGIN DESCRIPTION:
X18264
END DESCRIPTION:
XS GIS Cut Line= 6
       2246416.5       13808940.      2245295.78     13808442.72
      2245008.51     13808220.05      2242791.39     13807565.55
      2242383.05     13806823.38      2240372.62     13806594.21
#Sta/Elev= 30
  1332.9  660.11  1405.9  657.16  1481.5   661.4  1818.8  650.51  1989.5  643.59
    2381  635.07  2775.5  631.93  3024.2   629.8  3396.4  628.95  4657.7  630.15
  4788.4  621.81  4788.9  621.31  4817.4  621.81  4908.2  622.33  5131.8  625.05
  5167.8  633.55  5462.7  634.58  5976.7  633.47    6007  627.31  6283.5  629.23
  6517.3  634.83  6793.9  638.74  7316.2  666.68  7439.3  669.29  7634.1   696.6
  7840.6  722.77  7945.4  720.54  7965.9  718.62  8011.7   734.6  8104.7  736.54
#Mann= 20 ,-1 , 0
  1332.9    .094       0  1405.9    .063       0  1818.8      .1       0
  1989.5    .063       0    2381    .094       0  2775.5    .035       0
  3024.2    .063       0  3396.4    .035       0  4788.4    .033       0
  4817.4    .035       0  4908.2    .033       0  5131.8    .035       0
  5462.7    .035       0    6007    .063       0  6283.5    .035       0
  6517.3    .063       0  6793.9    .035       0  7316.2    .035       0
  7634.1    .094       0  7945.4    .035       0
Bank Sta=4788.4,4817.4
XS Rating Curve= 0 ,0
Exp/Cntr=0.3,0.1

Type RM Length L Ch R = 1 ,14943   ,746,746,746
BEGIN DESCRIPTION:
X18265
END DESCRIPTION:
XS GIS Cut Line= 6
      2246416.53     13808910.32      2245340.31     13808420.45
      2245025.08     13808158.11      2243512.47     13807064.24
      2242610.92     13806428.62      2240323.01     13806379.39
#Sta/Elev= 30
  1991.3  658.55  2069.1  658.36  2185.2  662.06  2366.5  650.31  2437.3  650.43
  2642.3  644.29  3054.5  634.83  3503.6  630.89  3962.5  627.58  4875.6  628.67
  4890.3  625.82  4917.5  609.32    4918  608.82  4946.6  609.32  5073.3  617.72
    5396  627.37  5703.2  627.09  5827.6  620.86  5900.2  626.76  6477.8  628.97
  6704.2  629.15  7250.1  631.79  7529.4  635.26  7865.1  642.79  8069.9  652.53
  8181.4  663.23  8492.6  685.78  8650.1  688.68  8706.7  701.04  8842.1  718.35
#Mann= 20 ,-1 , 0
  1991.3    .094       0  2069.1    .063       0  2437.3      .1       0
  2642.3    .063       0  3054.5    .094       0  3503.6    .063       0
  3962.5    .035       0  4917.5    .035       0  4946.6    .035       0
  5073.3      .1       0    5396    .094       0  5703.2    .035       0
  6477.8    .094       0  6704.2    .035       0  7250.1    .094       0
  7529.4    .035       0  7865.1    .063       0  8181.4    .063       0
  8492.6     .12       0  8706.7    .035       0
Bank Sta=4917.5,4946.6
XS Rating Curve= 0 ,0
Exp/Cntr=0.3,0.1

Type RM Length L Ch R = 1 ,14197   ,606,606,606
BEGIN DESCRIPTION:
X18266
END DESCRIPTION:
XS GIS Cut Line= 6
      2246401.68     13808850.94      2245332.89      13808368.5
      2245133.71     13808159.65      2244041.98     13806873.27
      2243778.11     13806439.34       2240360.1     13806334.86
#Sta/Elev= 30
  1767.2  659.38  2040.1  660.94  2109.5  651.07    2167  650.63  2389.3  646.17
  2825.4  633.67  2958.1  632.97  3134.3  632.12  3795.2  626.99    4536  630.05
  4607.4   620.9  4731.9  618.46  4839.1  612.85  4984.4  608.72  4984.9  608.22
  5013.5  608.72  5065.8  625.95  5380.6   626.1  5606.7  620.75  5695.5  624.59
  5706.7  628.86  5874.3  626.97  6459.7  628.99  6734.3   630.1  7290.5   632.7
  7566.2  634.32  7907.3  641.61  8097.9   649.9  8681.4  691.67  8843.1  706.16
#Mann= 20 ,-1 , 0
  1767.2    .094       0    2167      .1       0  2389.3    .063       0
  2825.4    .094       0  2958.1      .1       0  3134.3    .063       0
  3795.2    .035       0  4731.9      .1       0  4839.1    .035       0
  4984.4    .035       0  5013.5    .035       0  5380.6    .094       0
  5695.5    .035       0  5874.3    .035       0  6459.7    .094       0
  6734.3    .035       0  7290.5    .094       0  7566.2    .035       0
  7907.3    .063       0  8681.4    .035       0
Bank Sta=4984.4,5013.5
XS Rating Curve= 0 ,0
Exp/Cntr=0.3,0.1

Type RM Length L Ch R = 1 ,13591   ,2214,2214,2214
BEGIN DESCRIPTION:
X18267
END DESCRIPTION:
XS GIS Cut Line= 5
      2245986.05      13808640.9      2245355.15     13808329.16
       2244658.3     13807333.34      2244510.43     13806421.47
      2240368.74     13806302.98
#Sta/Elev= 30
  2504.8  650.79  2665.2  647.95  3204.4  632.53  3356.4  631.88  3534.4  629.48
  3982.7  627.68  4367.8  623.53  4723.4  627.58  4832.2  616.07  4995.3   607.7
  4995.8   607.2  5024.4   607.7  5032.6  608.11  5132.7  624.66  5171.9  628.65
  5453.2  630.46  6055.8  626.47  6243.5  620.83  6344.7  624.34    6492  626.89
  7187.2  629.18  7380.6  630.03  7950.2  632.35  8227.3  635.51    8568  640.95
  8764.5  649.35  9054.7  674.46  9214.7  679.31  9304.9  687.88  9491.1  705.31
#Mann= 20 ,-1 , 0
  2504.8      .1       0  2665.2    .063       0  3204.4      .1       0
  3356.4    .094       0  3534.4    .063       0  3982.7    .035       0
  4832.2      .1       0  4995.3    .035       0  5024.4    .035       0
  5032.6      .1       0  5132.7    .035       0  6055.8     .12       0
  6344.7    .035       0    6492    .035       0  7187.2    .094       0
  7380.6    .035       0  7950.2    .094       0  8227.3    .035       0
    8568    .063       0  9304.9    .035       0
Bank Sta=4995.3,5024.4
XS Rating Curve= 0 ,0
Exp/Cntr=0.3,0.1

Type RM Length L Ch R = 1 ,11377   ,820,820,820
BEGIN DESCRIPTION:
X18268
END DESCRIPTION:
XS GIS Cut Line= 5
      2245370.11     13808253.48      2245291.98     13807697.92
      2245658.42     13806795.39      2245496.17     13806369.74
      2240463.98     13806265.83
#Sta/Elev= 30
  4396.3   637.7    4483  633.59  4633.2  629.06  4720.4  627.99  4961.6  625.87
  4971.3  623.05  4977.7  612.77    5022  604.37  5022.5  603.87  5051.3  604.37
  5123.9  606.56  5228.9  612.51  5377.5  617.19  5513.3  619.29  5543.7  612.88
    5615  605.85  5653.5  611.82  5781.1  627.93  6994.3  630.23  8078.8  626.29
  8335.7  619.97  8398.5  626.97  9320.8  629.58  9389.4  629.34  9979.1   632.1
 10275.3  635.75   10598  640.58 10949.1  657.11 11328.1     687 11420.2  695.39
#Mann= 20 ,-1 , 0
  4396.3      .1       0    4483    .094       0  4633.2    .063       0
  4720.4    .094       0    5022     .05       0  5051.3    .094       0
  5123.9      .1       0  5228.9    .035       0  5377.5    .035       0
  5543.7     .12       0  5653.5    .035       0  6994.3    .035       0
  8078.8     .12       0  8335.7    .035       0  9320.8    .094       0
  9389.4    .035       0  9979.1    .094       0 10275.3    .035       0
   10598    .063       0 11328.1    .035       0
Bank Sta=5022,5051.3
XS Rating Curve= 0 ,0
Exp/Cntr=0.3,0.1

Type RM Length L Ch R = 1 ,10557   ,1094,1094,1094
BEGIN DESCRIPTION:
X18269
END DESCRIPTION:
XS GIS Cut Line= 4
      2246021.15     13808401.08      2246046.61     13806644.48
      2245926.65     13806340.06      2240530.87     13806250.99
#Sta/Elev= 30
  4123.4  654.84  4198.5  648.88  4357.8  640.95  4468.9  639.62  4539.5  639.75
  4559.5  630.32  4739.5   630.8  4849.6  605.23  5010.4  599.61  5014.9  599.55
  5015.4  599.05  5044.3  599.55  5157.5  609.46  5229.6  622.21  5849.7  628.63
  7245.7     630  7309.6  630.42    7738  631.29  8131.9  628.92  8427.3  622.29
  8571.2  619.97  8639.4   629.2  9617.8  629.52  9633.1  629.51 10231.7  633.54
 10535.7  635.52 10848.5  640.42 11239.7  658.78 11578.2     686 11603.9  689.31
#Mann= 20 ,-1 , 0
  4123.4      .1       0  4198.5    .094       0  4357.8      .1       0
  4468.9    .094       0  5010.4      .1       0  5014.9     .05       0
  5044.3      .1       0  5157.5    .035       0  7245.7    .063       0
  7309.6    .035       0    7738      .1       0  8131.9    .094       0
  8427.3     .12       0  8571.2    .035       0  9617.8    .094       0
  9633.1    .035       0 10231.7    .094       0 10535.7    .035       0
 10848.5    .063       0 11578.2    .035       0
Bank Sta=5014.9,5044.3
XS Rating Curve= 0 ,0
Exp/Cntr=0.3,0.1

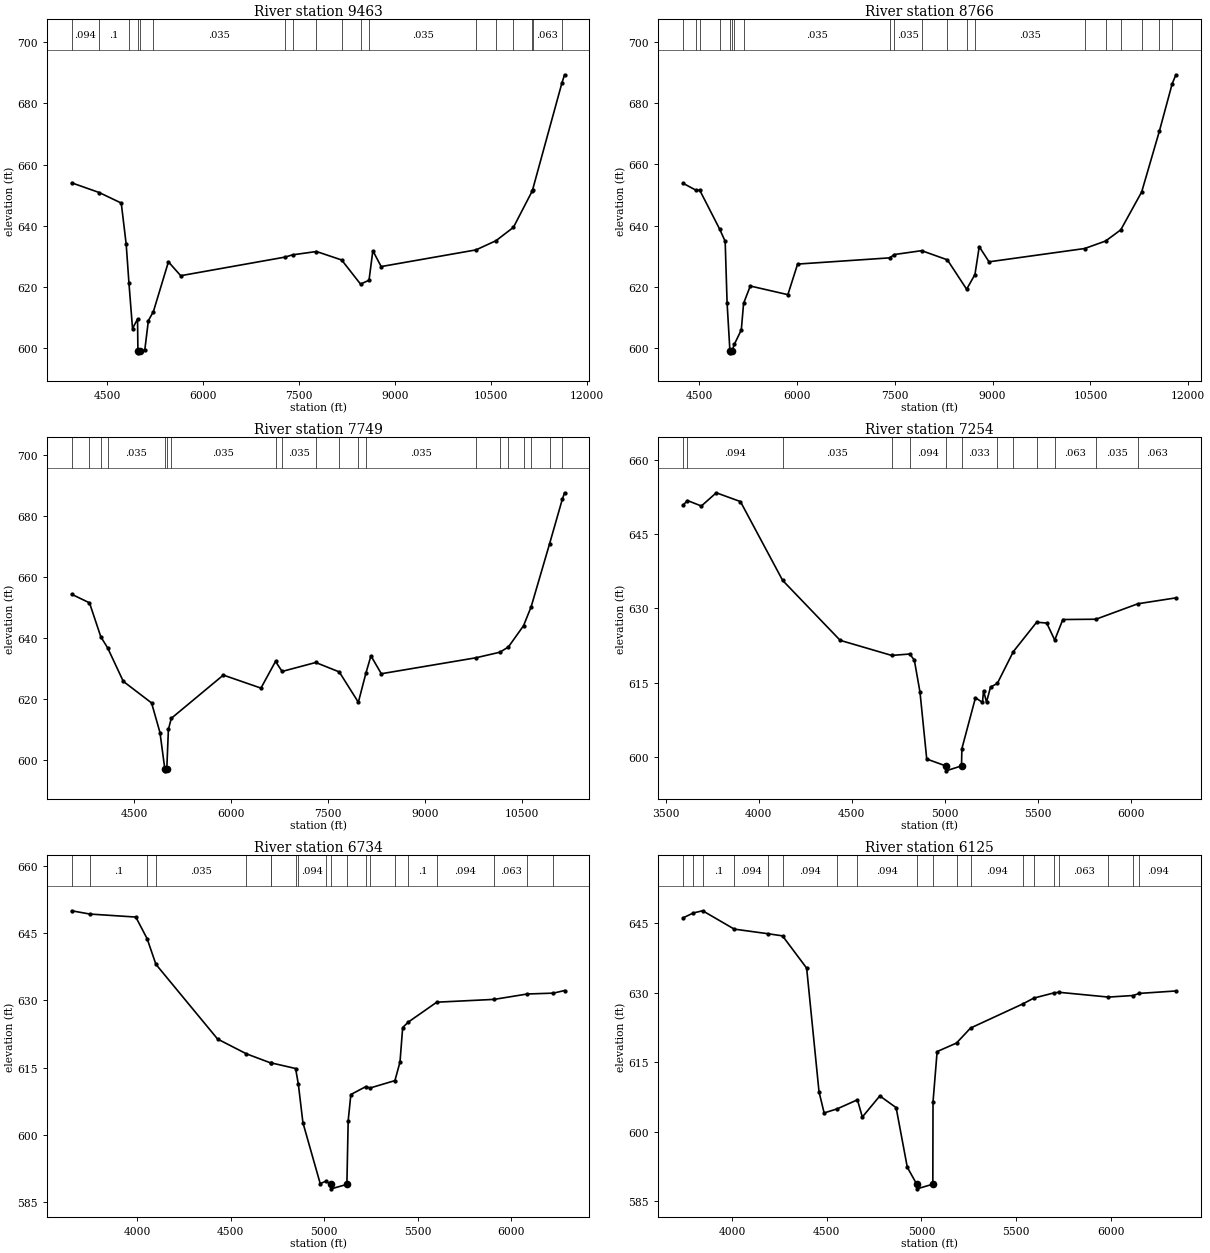
Type RM Length L Ch R = 1 ,9463    ,697,697,697
BEGIN DESCRIPTION:
X18270
END DESCRIPTION:
XS GIS Cut Line= 5
      2247166.99     13808218.78      2246863.16      13807437.5
      2246193.34     13806600.23      2245934.07     13806317.79
      2240516.01     13806228.73
#Sta/Elev= 30
  3940.5  654.03  4371.6  650.86  4717.1  647.42  4794.1  634.01  4837.3  621.38
  4893.4  606.48  4971.8  609.56  4977.9  599.05  4978.4  598.55  5007.3  599.05
  5085.5   599.5  5141.5  609.08    5220  612.01  5455.2  628.24  5647.3  623.72
  7279.5  629.79  7398.6  630.53  7771.8  631.61  8165.7  628.85  8461.1  620.98
  8593.9  622.24  8653.8  631.87  8783.8   626.7   10268  632.14 10580.6  635.14
 10853.2  639.49 11146.7  651.31 11153.2  651.74   11612  686.59 11653.2  689.28
#Mann= 18 ,-1 , 0
  3940.5    .094       0  4371.6      .1       0  4837.3    .063       0
  4977.9     .05       0  5007.3    .063       0    5220    .035       0
  7279.5    .063       0  7398.6    .035       0  7771.8      .1       0
  8165.7    .094       0  8461.1     .12       0  8593.9    .035       0
   10268    .094       0 10580.6    .035       0 10853.2    .063       0
 11146.7    .035       0 11153.2    .063       0   11612    .035       0
Bank Sta=4977.9,5007.3
XS Rating Curve= 0 ,0
Exp/Cntr=0.3,0.1

Type RM Length L Ch R = 1 ,8766    ,1017,1017,1017
BEGIN DESCRIPTION:
X18271
END DESCRIPTION:
XS GIS Cut Line= 4
      2247852.78     13807203.14      2246680.87     13806664.93
      2245926.65     13806295.52       2240501.1     13806206.46
#Sta/Elev= 30
  4254.7  653.85  4452.4  651.59  4512.2  651.55  4814.9  638.96  4901.5   634.9
  4931.1  614.71  4974.7  598.99  4975.2  598.49  5004.3  598.99  5041.7  601.26
  5148.9  605.98    5184  614.65  5286.6   620.3  5862.6  617.48  6011.6  627.46
  7421.1  629.49  7495.9  630.58  7913.4  631.84  8307.3  628.85  8602.7  619.25
  8730.3  624.05  8796.1  633.14  8946.1   628.2 10412.1  632.54 10733.3  634.99
 10965.7  638.64 11285.7  650.99 11556.7  670.81 11753.6  686.32 11810.4  689.25
#Mann= 20 ,-1 , 0
  4254.7    .063       0  4452.4    .094       0  4512.2    .063       0
  4814.9    .094       0  4974.7    .035       0  5004.3    .035       0
  5041.7      .1       0    5184    .035       0  7421.1    .063       0
  7495.9    .035       0  7913.4      .1       0  8307.3    .094       0
  8602.7     .12       0  8730.3    .035       0 10412.1    .094       0
 10733.3    .035       0 10965.7    .063       0 11285.7    .063       0
 11556.7    .094       0 11753.6    .035       0
Bank Sta=4974.7,5004.3
XS Rating Curve= 0 ,0
Exp/Cntr=0.3,0.1

Type RM Length L Ch R = 1 ,7749    ,495,495,495
BEGIN DESCRIPTION:
X18272
END DESCRIPTION:
XS GIS Cut Line= 4
      2248061.07     13806664.93      2247010.73     13806248.27
      2246481.22     13806248.27      2240523.42     13806176.77
#Sta/Elev= 30
  3533.9  654.32  3809.9  651.51  3985.5  640.38  4090.2  636.79  4332.4  625.83
  4769.6  618.77  4899.6  609.06  4974.8  597.06  4975.3  596.56  5004.4  597.06
  5029.6  610.09  5074.1  613.73  5878.5  627.88  6459.7  623.62  6684.9  632.35
    6787  629.07  7306.1     632  7669.7  628.92  7965.1  618.99  8083.9  628.67
  8159.8  634.17  8319.8  628.32  9779.8  633.53 10152.9  635.36 10283.5  637.07
 10517.8  644.02 10634.9  650.18 10919.3  670.75 11116.3  685.33 11151.6  687.51
#Mann= 20 ,-1 , 0
  3533.9    .094       0  3809.9    .063       0  3985.5    .094       0
  4090.2    .035       0  4974.8     .05       0  5004.4      .1       0
  5074.1    .035       0  6684.9    .063       0    6787    .035       0
  7306.1      .1       0  7669.7    .094       0  7965.1     .12       0
  8083.9    .035       0  9779.8    .094       0 10152.9    .035       0
 10283.5    .063       0 10517.8    .035       0 10634.9    .063       0
 10919.3    .094       0 11116.3    .035       0
Bank Sta=4974.8,5004.4
XS Rating Curve= 0 ,0
Exp/Cntr=0.3,0.1

Type RM Length L Ch R = 1 ,7254    ,520,520,520
BEGIN DESCRIPTION:
X18273
END DESCRIPTION:
XS GIS Cut Line= 3
       2248173.9     13806456.59      2246776.36     13805779.52
       2245821.5     13805241.32
#Sta/Elev= 30
  3592.3  650.86  3616.5  651.81  3691.1   650.7  3771.2  653.38  3901.1   651.6
    4128  635.65  4437.1  623.53  4713.7  620.48  4810.8  620.76  4835.6  619.54
  4866.1  613.05  4902.3  599.52  5004.3  598.13  5005.8  597.13  5089.2  598.13
  5091.2  601.62  5164.3  611.93  5201.9  610.96  5207.6  613.35  5223.5  611.04
  5245.2  614.08  5281.5   614.8  5367.7  621.25  5493.2   627.2  5547.2  627.02
  5590.1  623.59  5633.8  627.74  5811.5   627.8  6037.2  630.93  6241.3  632.12
#Mann= 13 ,-1 , 0
  3592.3    .063       0  3616.5    .094       0    4128    .035       0
  4713.7    .063       0  4810.8    .094       0  5004.3     .05       0
  5089.2    .033       0  5281.5    .035       0  5367.7      .1       0
  5493.2    .035       0  5590.1    .063       0  5811.5    .035       0
  6037.2    .063       0
Bank Sta=5004.3,5089.2
XS Rating Curve= 0 ,0
Exp/Cntr=0.3,0.1

Type RM Length L Ch R = 1 ,6734    ,609,609,609
BEGIN DESCRIPTION:
X18274
END DESCRIPTION:
XS GIS Cut Line= 3
      2248217.34      13806369.8      2247444.76     13805822.92
      2246351.79     13804539.11
#Sta/Elev= 30
  3650.9  649.98  3748.3  649.25  3993.7  648.58  4054.2  643.75    4101  638.04
  4430.6  621.37  4584.7  618.07  4714.2  616.04  4714.9  616.07  4847.1   614.8
  4861.7  611.33  4886.3   602.7  4978.6  589.12  5008.5  589.66  5036.1  588.96
  5037.6  587.96    5121  588.96    5128  603.15  5142.2     609  5222.3  610.76
  5244.6  610.45  5377.6   612.1  5404.7  616.25    5419  623.94  5448.9  625.15
    5601  629.59    5908  630.22  6084.7  631.42  6223.8  631.61  6283.5  632.19
#Mann= 20 ,-1 , 0
  3650.9    .094       0  3748.3      .1       0  4054.2    .094       0
    4101    .035       0  4584.7    .094       0  4714.2    .035       0
  4714.9    .063       0  4847.1    .035       0  4861.7    .094       0
  5008.5    .035       0  5036.1     .05       0    5121    .035       0
  5222.3    .094       0  5244.6    .035       0  5377.6    .094       0
  5448.9      .1       0    5601    .094       0    5908    .063       0
  6084.7      .1       0  6223.8    .094       0
Bank Sta=5036.1,5121
XS Rating Curve= 0 ,0
Exp/Cntr=0.3,0.1

Type RM Length L Ch R = 1 ,6125    ,761,761,761
BEGIN DESCRIPTION:
X18275
END DESCRIPTION:
XS GIS Cut Line= 3
      2248399.59     13806300.31      2247436.08     13804946.18
      2246750.29      13804303.8
#Sta/Elev= 30
  3741.6   646.2  3796.4  647.27  3845.6  647.74  4012.2  643.78  4188.9  642.79
    4267  642.32  4394.4  635.35  4459.6  608.66  4486.6  604.07  4556.3  604.97
  4662.3  606.91  4688.3  603.19  4780.5  607.75  4866.6  605.22  4925.6  592.34
  4975.4  588.68  4976.9  587.68  5060.3  588.68  5061.3  606.42    5083  617.33
  5185.3  619.17  5259.4  622.41  5535.5  627.63  5593.4  628.88  5697.4  629.98
  5724.6  630.14  5987.2   629.1  6118.5  629.44  6149.2  629.89  6343.2  630.42
#Mann= 19 ,-1 , 0
  3741.6    .035       0  3796.4    .063       0  3845.6      .1       0
  4012.2    .094       0  4188.9    .063       0    4267    .094       0
  4556.3      .1       0  4662.3    .094       0  4975.4     .05       0
  5060.3    .094       0  5185.3    .063       0  5259.4    .094       0
  5535.5    .063       0  5593.4    .094       0  5697.4    .035       0
  5724.6    .063       0  5987.2    .094       0  6118.5      .1       0
  6149.2    .094       0
Bank Sta=4975.4,5060.3
XS Rating Curve= 0 ,0
Exp/Cntr=0.3,0.1

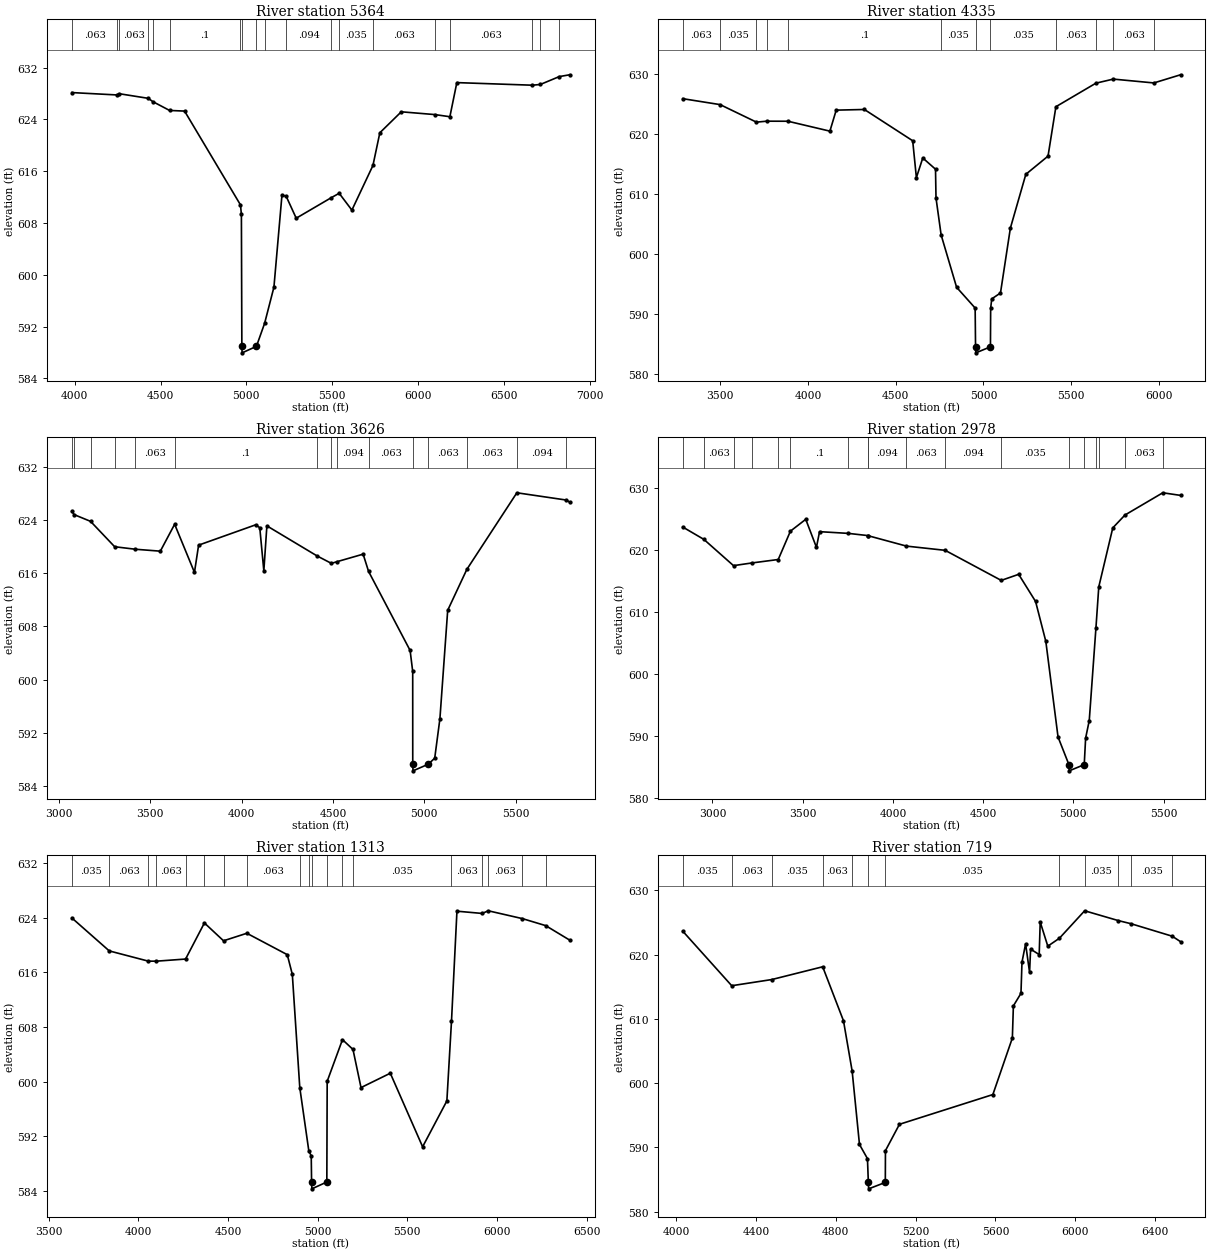
Type RM Length L Ch R = 1 ,5364    ,1029,1029,1029
BEGIN DESCRIPTION:
X18276
END DESCRIPTION:
XS GIS Cut Line= 3
      2248911.77     13806048.61      2248234.69     13805024.31
      2246768.84     13804217.66
#Sta/Elev= 30
  3983.1  628.15  4248.3  627.78  4257.5  627.98  4428.4  627.26    4455  626.75
  4552.5  625.39  4639.9  625.29  4965.6   610.8    4971  609.34  4973.7  588.94
  4975.2  587.94  5058.6  588.94  5106.3   592.5  5160.6  598.09  5207.5  612.34
  5232.1  612.12  5290.5  608.74    5496  611.93  5540.8  612.59  5614.9  609.99
  5737.6  616.89  5777.8  621.94  5902.8  625.18  6098.5  624.75  6185.9  624.42
  6226.5  629.69    6666  629.29  6712.8   629.4  6823.4  630.62  6884.1   630.9
#Mann= 19 ,-1 , 0
  3983.1    .063       0  4248.3    .035       0  4257.5    .063       0
  4428.4    .035       0    4455    .063       0  4552.5      .1       0
  4965.6    .094       0  4973.7     .05       0  5058.6    .094       0
  5106.3    .035       0  5232.1    .094       0    5496    .063       0
  5540.8    .035       0  5737.6    .063       0  6098.5    .035       0
  6185.9    .063       0    6666    .094       0  6712.8      .1       0
  6823.4    .094       0
Bank Sta=4973.7,5058.6
XS Rating Curve= 0 ,0
Exp/Cntr=0.3,0.1

Type RM Length L Ch R = 1 ,4335    ,709,709,709
BEGIN DESCRIPTION:
X18277
END DESCRIPTION:
XS GIS Cut Line= 3
      2249120.11     13805640.63      2248338.86     13804425.35
      2246975.97     13804138.88
#Sta/Elev= 30
  3285.7  625.94  3498.9  624.95  3705.9  622.03  3764.9  622.19  3885.6  622.18
  4124.6  620.53  4160.6  624.03  4321.1  624.14  4596.5  618.93  4617.6  612.79
    4654  616.06  4726.6  614.19  4729.4   609.4  4758.6  603.24  4846.8  594.52
  4952.5  591.06  4954.8   584.6  4956.3   583.6  5039.7   584.6  5040.9  591.01
  5047.1  592.59  5096.9  593.57  5153.3  604.38  5241.4  613.34  5367.9  616.37
  5412.8   624.6  5640.7  628.52  5739.9   629.2  5971.1  628.56  6123.1  629.92
#Mann= 12 ,-1 , 0
  3285.7    .063       0  3498.9    .035       0  3705.9    .063       0
  3764.9    .094       0  3885.6      .1       0  4758.6    .035       0
  4954.8    .035       0  5039.7    .035       0  5412.8    .063       0
  5640.7    .035       0  5739.9    .063       0  5971.1    .094       0
Bank Sta=4954.8,5039.7
XS Rating Curve= 0 ,0
Exp/Cntr=0.3,0.1

Type RM Length L Ch R = 1 ,3626    ,648,648,648
BEGIN DESCRIPTION:
X18278
END DESCRIPTION:
XS GIS Cut Line= 3
      2249111.45     13805501.78      2248390.94       13804000.
      2247601.01     13803296.88
#Sta/Elev= 30
  3071.8  625.36  3084.6  624.87    3174  623.86  3305.9  620.03  3419.7  619.65
  3555.7  619.36    3634  623.42  3742.4  616.16  3765.1  620.27  4077.5  623.34
  4099.7   622.9  4121.9   616.4  4138.6  623.18  4413.3  618.64  4491.5  617.52
  4524.1  617.79  4665.1  618.91  4694.8  616.31  4922.1  604.38  4936.3  601.21
  4936.5  587.22    4938  586.22  5021.4  587.22  5056.7  588.13  5085.1  594.08
  5127.7  610.44  5232.4  616.61  5506.1  628.17  5777.3  627.07    5795  626.75
#Mann= 15 ,-1 , 0
  3071.8    .063       0  3084.6    .035       0    3174    .063       0
  3305.9    .035       0  3419.7    .063       0    3634      .1       0
  4413.3    .094       0  4491.5      .1       0  4524.1    .094       0
  4694.8    .063       0  4936.5     .05       0  5021.4    .063       0
  5232.4    .063       0  5506.1    .094       0  5777.3      .1       0
Bank Sta=4936.5,5021.4
XS Rating Curve= 0 ,0
Exp/Cntr=0.3,0.1

Type RM Length L Ch R = 1 ,2978    ,1665,1665,1665
BEGIN DESCRIPTION:
X18279
END DESCRIPTION:
XS GIS Cut Line= 3
      2249163.51     13805449.65      2248555.87     13803921.88
      2248642.68     13802810.74
#Sta/Elev= 30
  2835.1  623.75  2952.6  621.75  3116.6  617.52  3217.6  617.95  3364.5  618.51
    3432  623.08  3516.9  624.99  3576.2  620.47  3593.4     623  3753.5  622.72
  3860.4  622.37  3860.8  622.36  4075.1  620.67  4289.5  619.99  4600.3  615.14
  4696.8  616.12  4790.6  611.74  4847.3  605.31    4915  589.89  4975.3  585.43
  4976.8  584.43  5060.2  585.43  5067.9  589.71    5088  592.54  5125.2  607.54
  5140.8   614.1  5218.4  623.61  5285.8  625.68  5495.5  629.27  5593.8  628.85
#Mann= 18 ,-1 , 0
  2835.1    .035       0  2952.6    .063       0  3116.6    .035       0
  3217.6    .063       0  3364.5    .094       0    3432      .1       0
  3753.5    .063       0  3860.4      .1       0  3860.8    .094       0
  4075.1    .063       0  4289.5    .094       0  4600.3    .035       0
  4975.3    .035       0  5060.2    .035       0  5125.2     .12       0
  5140.8    .035       0  5285.8    .063       0  5495.5      .1       0
Bank Sta=4975.3,5060.2
XS Rating Curve= 0 ,0
Exp/Cntr=0.3,0.1

Type RM Length L Ch R = 1 ,1313    ,594,594,594
BEGIN DESCRIPTION:
X18280
END DESCRIPTION:
XS GIS Cut Line= 3
      2249224.28     13805493.07      2248824.97     13804390.63
      2249528.01     13802949.83
#Sta/Elev= 30
  3629.3  623.94  3837.8  619.12  4056.1  617.62  4101.1  617.62  4263.3  617.93
  4368.3  623.21  4474.9   620.6  4604.9   621.7  4830.3  618.57  4858.5  615.69
  4900.1  599.12  4950.7  589.83  4963.9  589.17  4965.9  585.32  4967.4  584.32
  5050.9  585.32  5052.9  600.05  5138.1  606.14  5196.7  604.71  5241.5  599.13
  5404.8  601.23    5585  590.47  5720.2  597.18    5746  608.84  5776.4  624.93
  5917.5   624.6  5950.8  624.99  6141.9  623.84  6271.1  622.82    6405   620.7
#Mann= 19 ,-1 , 0
  3629.3    .035       0  3837.8    .063       0  4056.1    .035       0
  4101.1    .063       0  4263.3    .094       0  4368.3      .1       0
  4474.9    .094       0  4604.9    .063       0  4900.1    .094       0
  4950.7    .035       0  4965.9    .035       0  5050.9    .035       0
  5138.1    .063       0  5196.7    .035       0    5746    .063       0
  5917.5    .035       0  5950.8    .063       0  6141.9    .035       0
  6271.1    .063       0
Bank Sta=4965.9,5050.9
XS Rating Curve= 0 ,0
Exp/Cntr=0.3,0.1

Type RM Length L Ch R = 1 ,719     ,500,500,500
BEGIN DESCRIPTION:
X18281
END DESCRIPTION:
XS GIS Cut Line= 5
      2249237.69     13805499.71      2249273.08     13804600.74
        2249259.     13804260.42      2249532.65     13803054.62
      2249536.36     13803038.27
#Sta/Elev= 30
  4033.3  623.66  4278.8  615.16  4479.3  616.12  4734.4  618.11  4838.6   609.7
    4882  601.87  4918.7  590.44  4958.7  588.23  4963.1  584.53  4964.6  583.53
  5048.1  584.53  5048.8  589.48  5118.9  593.58  5586.8  598.21  5684.5  607.02
  5689.6  612.02  5727.6  613.97  5732.7  618.83  5750.8  621.69  5770.7  617.24
  5775.8  620.86  5818.9  620.01    5824  625.08    5862  621.32  5920.1  622.55
  6046.6  626.83  6215.3   625.3  6279.4  624.81  6485.2  622.87  6526.8  622.02
#Mann= 12 ,-1 , 0
  4033.3    .035       0  4278.8    .063       0  4479.3    .035       0
  4734.4    .063       0    4882    .035       0  4963.1    .035       0
  5048.1    .035       0  5920.1    .063       0  6046.6    .035       0
  6215.3    .063       0  6279.4    .035       0  6485.2    .063       0
Bank Sta=4963.1,5048.1
XS Rating Curve= 0 ,0
Exp/Cntr=0.3,0.1

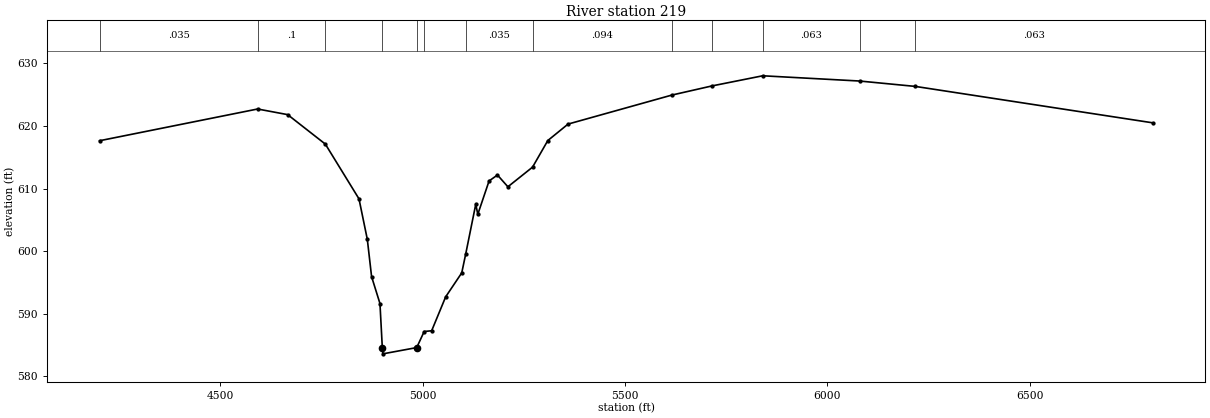
Type RM Length L Ch R = 1 ,219     ,0,0,0
BEGIN DESCRIPTION:
X18282
END DESCRIPTION:
XS GIS Cut Line= 3
       2249875.3     13805493.01      2249536.77     13804251.74
      2249719.04     13802949.85
#Sta/Elev= 30
  4202.2  617.64  4592.4  622.71  4666.6  621.81  4759.7   617.1  4842.8  608.35
  4863.4  601.87  4873.9  595.92  4894.6  591.62  4900.4  584.58  4901.9  583.58
  4985.4  584.58  5003.8  587.15  5022.3  587.27  5056.9  592.69  5096.6  596.52
  5106.6   599.6  5131.2  607.48  5136.3  605.89  5164.1  611.21  5184.8  612.16
  5210.6  610.28  5271.5  613.42  5309.2  617.67  5359.2   620.3  5615.8  624.94
  5714.8   626.4    5840  628.02  6079.5  627.18    6217  626.32  6803.4   620.5
#Mann= 13 ,-1 , 0
  4202.2    .035       0  4592.4      .1       0  4759.7    .063       0
  4900.4     .05       0  4985.4    .063       0  5003.8    .033       0
  5106.6    .035       0  5271.5    .094       0  5615.8    .063       0
  5714.8    .035       0    5840    .063       0  6079.5    .035       0
    6217    .063       0
Bank Sta=4900.4,4985.4
XS Rating Curve= 0 ,0
Exp/Cntr=0.3,0.1

Chan Stop Cuts=-1
Use User Specified Reach Order=0
Composite Channel Slope=5