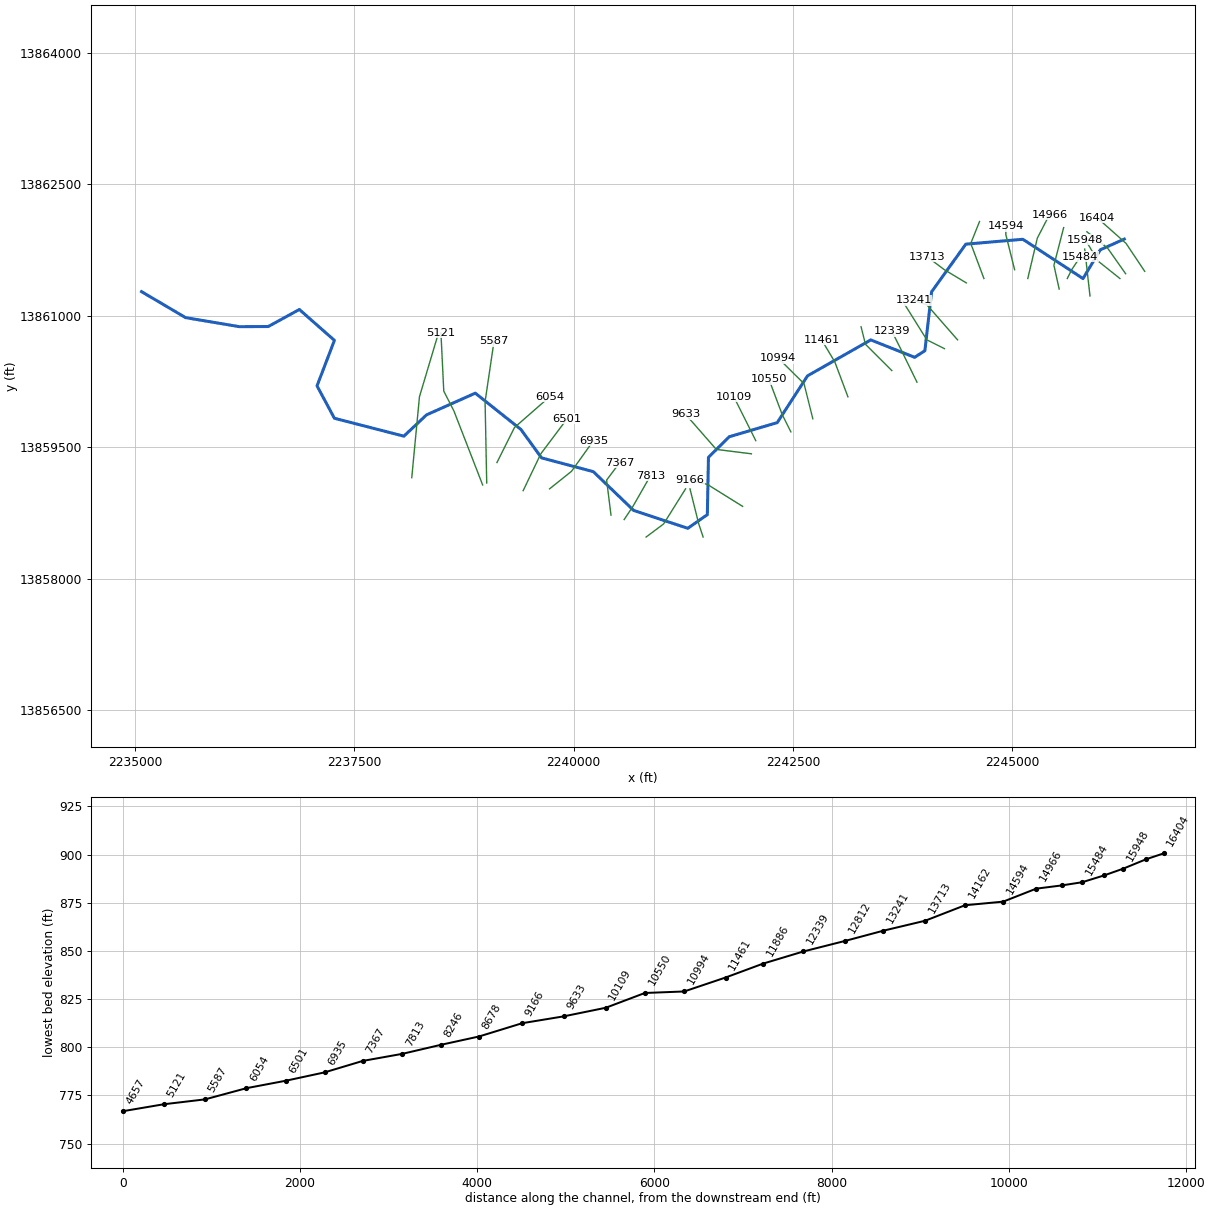
--- Cordovs Hollow.prj (project) ---

Proj Title=Cordovs Hollow Base Level Engineering
Current Plan=p01
Default Exp/Contr=0.3,0.1
English Units
Geom File=g01
Flow File=f01
Plan File=p01
Y Axis Title=Elevation
X Axis Title(PF)=Main Channel Distance
X Axis Title(XS)=Station
BEGIN DESCRIPTION:
Cordovs Hollow
END DESCRIPTION:
DSS Export Rating Curves= 0
DSS Export Rating Curve Sorted= 0
DSS Export Volume Flow Curves= 0
DXF OffsetX= 0
DXF OffsetY= 0
DXF ScaleX= 1
DXF ScaleY= 10

--- Cordovs Hollow.p01 (plan) ---

Plan Title=Multiple Run
Short Identifier=Multiple
Geom File=g01
Flow File=f01
Subcritical Flow
K Sum by GR= 0
Std Step Tol= 0.01
Critical Tol= 0.01
Num of Std Step Trials= 20
Max Error Tol= 0.3
Flow Tol Ratio= 0.001
Split Flow NTrial= 30
Split Flow Tol= 0.02
Split Flow Ratio= 0.02
Log Output Level= 0
Friction Slope Method= 1
Unsteady Friction Slope Method= 2
Unsteady Bridges Friction Slope Method= 1
Parabolic Critical Depth
Global Vel Dist=  1 , 1 , 1
Global Log Level= 0
CheckData=True
Encroach Param= -1, 0, 0, 0
BEGIN DESCRIPTION:
Multiple Run
END DESCRIPTION:

--- Cordovs Hollow.f01 (steady flow) ---

Flow Title=Multiple
Number of Profiles=7
Profile Names=10-year,25-year,50-year,1pct_min,100-year,1pct_plu,500-year
River Rch & RM= Cordovs Hollow,Reach-1,16404
    1508    2588    3628    2461    4910    9797    8899
River Rch & RM= Cordovs Hollow,Reach-1,15948
    1888    3270    4612    3144    6274   12518   11493
River Rch & RM= Cordovs Hollow,Reach-1,11461
    2277    3976    5636    3859    7700   15364   14232
River Rch & RM= Cordovs Hollow,Reach-1,6935
    2537    4436    6294    4311    8601   17162   15906
Boundary for River Rch & Prof#=Cordovs Hollow,Reach-1,1
Up Type=0
Dn Type=3
Dn Slope=0.005
Boundary for River Rch & Prof#=Cordovs Hollow,Reach-1,2
Up Type=0
Dn Type=3
Dn Slope=0.005
Boundary for River Rch & Prof#=Cordovs Hollow,Reach-1,3
Up Type=0
Dn Type=3
Dn Slope=0.005
Boundary for River Rch & Prof#=Cordovs Hollow,Reach-1,4
Up Type=0
Dn Type=3
Dn Slope=0.005
Boundary for River Rch & Prof#=Cordovs Hollow,Reach-1,5
Up Type=0
Dn Type=3
Dn Slope=0.005
Boundary for River Rch & Prof#=Cordovs Hollow,Reach-1,6
Up Type=0
Dn Type=3
Dn Slope=0.005
Boundary for River Rch & Prof#=Cordovs Hollow,Reach-1,7
Up Type=0
Dn Type=3
Dn Slope=0.005

--- Cordovs Hollow.g01 (geometry) ---

Geom Title=Existing Conditions
Program Version=4.10

River Reach=Cordovs Hollow  ,Reach-1
Reach XY= 30
        2246275.       13861875.      2246001.17     13861752.69
      2245804.58     13861424.43      2245119.06     13861872.73
      2244468.81     13861817.19      2244078.83     13861273.42
      2244002.16     13860601.41      2243885.71      13860525.7
      2243385.62      13860724.4      2242664.89     13860314.61
      2242319.39     13859780.59      2241772.57     13859619.48
      2241535.75     13859384.68      2241522.95     13858730.84
      2241300.08     13858574.76      2240683.49     13858778.54
      2240223.45     13859221.25      2239633.48     13859378.51
      2239398.84     13859702.14      2238878.32     13860116.96
       2238322.7     13859869.17      2238064.57     13859626.05
      2237272.57     13859830.52      2237074.59       13860200.
      2237272.86     13860719.04      2236873.27     13861071.69
      2236519.07     13860877.24      2236190.22     13860875.52
      2235576.55     13860978.75        2235075.       13861275.

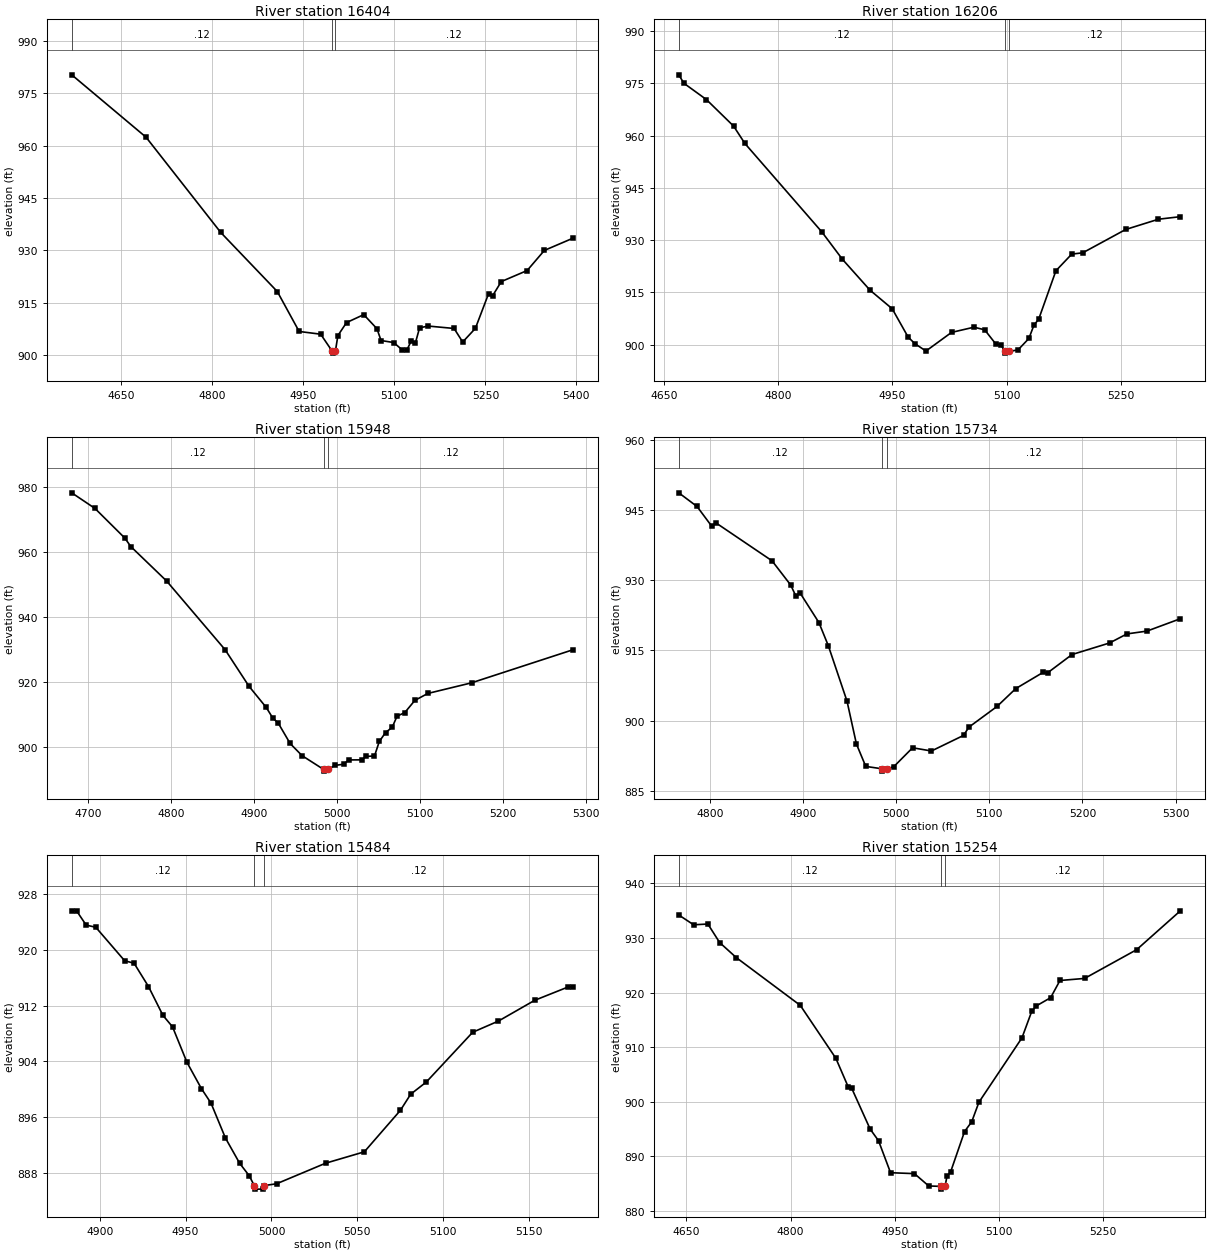
Type RM Length L Ch R = 1 ,16404   ,198,198,198
BEGIN DESCRIPTION:
Cordovs Hollow 36.0
END DESCRIPTION:
XS GIS Cut Line= 3
      2246507.34     13861507.22      2246294.93     13861825.83
      2245963.25     13862120.66
#Sta/Elev= 30
  4568.2  980.25  4690.7  962.39  4813.8  935.13    4907  918.22    4943  906.79
  4978.5  906.01  4997.7  901.09  4998.1  900.59  5002.7  901.09  5006.9  905.62
  5021.1  909.33  5049.5  911.61  5071.3  907.57    5078   904.2  5098.9  903.62
  5113.1  901.48  5120.6  901.47  5127.3  903.92  5134.8   903.6  5141.5  907.83
  5155.7  908.34  5198.4  907.65  5212.6  903.77  5233.5  907.68  5255.3  917.62
  5261.9  917.01  5276.2  921.07  5318.8  924.23  5347.2  929.99  5394.9  933.53
#Mann= 3 ,-1 , 0
  4568.2     .12       0  4997.7     .05       0  5002.7     .12       0
Bank Sta=4997.7,5002.7
XS Rating Curve= 0 ,0
Exp/Cntr=0.3,0.1

Type RM Length L Ch R = 1 ,16206   ,258,258,258
BEGIN DESCRIPTION:
X18554
END DESCRIPTION:
XS GIS Cut Line= 3
      2246290.33     13861479.49      2246082.53     13861775.03
       2245848.5     13861958.58
#Sta/Elev= 30
  4669.5  977.48  4676.2  975.06  4705.8  970.37  4741.5  962.75  4756.3  957.77
  4857.4  932.36  4884.4   924.5  4920.7  915.62  4949.8  910.29  4970.7  902.16
  4979.4   900.3  4994.1  898.15  5027.7   903.5  5057.2     905  5071.2  904.25
  5086.1   900.1  5092.5  899.89  5098.1  898.05  5098.5  897.55  5103.1  898.05
    5115  898.47  5129.3  901.76  5135.9  905.57  5142.2  907.31  5164.8  921.21
  5185.6  925.99    5200  926.36  5256.4  933.06  5299.5  936.01  5328.2  936.74
#Mann= 3 ,-1 , 0
  4669.5     .12       0  5098.1     .05       0  5103.1     .12       0
Bank Sta=5098.1,5103.1
XS Rating Curve= 0 ,0
Exp/Cntr=0.3,0.1

Type RM Length L Ch R = 1 ,15948   ,214,214,214
BEGIN DESCRIPTION:
Cordovs Hollow 35.0
END DESCRIPTION:
XS GIS Cut Line= 3
      2246224.99     13861425.01        2245975.       13861625.
      2245829.89     13861869.77
#Sta/Elev= 30
  4680.3  978.12  4708.3  973.33  4744.3  964.23  4751.5  961.63  4794.7  951.04
  4865.2  929.95    4894  918.73  4914.8  912.22  4922.8  908.93  4929.2  907.44
  4943.6  901.16    4958  897.42  4984.1  893.17  4984.5  892.67  4989.5  893.17
  4997.2  894.41  5008.3   894.8  5014.1  896.11  5029.7  896.13  5035.5   897.2
  5045.3  897.31  5051.1  901.77  5058.6   904.5  5066.7  906.14  5072.5  909.54
  5081.8  910.64    5094  914.39  5109.6  916.52  5162.3  919.78    5285  929.97
#Mann= 3 ,-1 , 0
  4680.3     .12       0  4984.1     .05       0  4989.5     .12       0
Bank Sta=4984.1,4989.5
XS Rating Curve= 0 ,0
Exp/Cntr=0.3,0.1

Type RM Length L Ch R = 1 ,15734   ,250,250,250
BEGIN DESCRIPTION:
X18553
END DESCRIPTION:
XS GIS Cut Line= 2
      2245883.98     13861225.52      2245824.02     13861760.57
#Sta/Elev= 30
  4766.7  948.63  4786.3  945.71  4801.9  941.54  4806.9  942.17  4866.8  934.11
  4886.9  928.92  4892.1  926.69  4897.1  927.18  4917.1  920.93  4927.2  915.99
  4947.3  904.13  4957.4  894.98  4967.4   890.2  4984.8  889.69  4985.3  889.19
  4990.3  889.69  4997.6  890.16  5017.7  894.18  5037.9  893.49  5072.4  896.82
  5078.1  898.58  5108.3     903  5128.4  906.81  5157.6  910.26  5162.6  910.18
  5188.8  914.09  5229.1  916.56  5247.8   918.5  5269.3   919.1  5305.1  921.74
#Mann= 3 ,-1 , 0
  4766.7     .12       0  4984.8     .05       0  4990.3     .12       0
Bank Sta=4984.8,4990.3
XS Rating Curve= 0 ,0
Exp/Cntr=0.3,0.1

Type RM Length L Ch R = 1 ,15484   ,230,230,230
BEGIN DESCRIPTION:
Cordovs Hollow 34.0
END DESCRIPTION:
XS GIS Cut Line= 3
      2245624.99     13861424.99        2245675.       13861525.
        2245775.     13861675.01
#Sta/Elev= 30
  4883.7  925.61  4886.5  925.61  4892.1  923.56  4897.7  923.25  4914.5  918.44
    4920  918.08  4928.4  914.73  4936.8  910.59  4942.4  908.94  4950.8  903.84
  4959.2  900.07  4964.8  897.98  4973.2  892.97  4981.5  889.33  4987.1  887.53
    4990  886.12  4990.4  885.62    4995  885.62  4995.5  886.12    5003  886.39
  5031.6  889.35  5054.1  890.98  5075.1  896.94  5081.1  899.26  5090.2  901.01
  5117.2  908.16  5132.2  909.77  5153.3  912.75  5172.8  914.67  5175.8  914.67
#Mann= 3 ,-1 , 0
  4883.7     .12       0    4990     .05       0  4995.5     .12       0
Bank Sta=4990,4995.5
XS Rating Curve= 0 ,0
Exp/Cntr=0.3,0.1

Type RM Length L Ch R = 1 ,15254   ,288,288,288
BEGIN DESCRIPTION:
X18555
END DESCRIPTION:
XS GIS Cut Line= 3
      2245533.04      13861304.1      2245473.02     13861576.48
      2245583.84      13862005.9
#Sta/Elev= 30
    4639  934.22  4660.4  932.42  4680.9  932.56  4697.9  929.16  4721.8  926.41
    4814  917.65  4865.2  907.96    4883  902.72  4888.1  902.45  4914.6  894.98
  4926.7  892.84    4944  886.98  4978.4  886.81    4999  884.55  5016.9  884.47
  5017.3  883.97  5022.5  884.47  5025.4   886.4  5030.5  887.12  5050.6  894.53
  5060.9  896.31  5071.3   899.9  5133.3   911.7  5147.4  916.57  5153.9  917.55
  5174.6  919.06    5188  922.21  5223.5  922.59  5298.5  927.86  5361.4  934.98
#Mann= 3 ,-1 , 0
    4639     .12       0  5016.9     .05       0  5022.5     .12       0
Bank Sta=5016.9,5022.5
XS Rating Curve= 0 ,0
Exp/Cntr=0.3,0.1

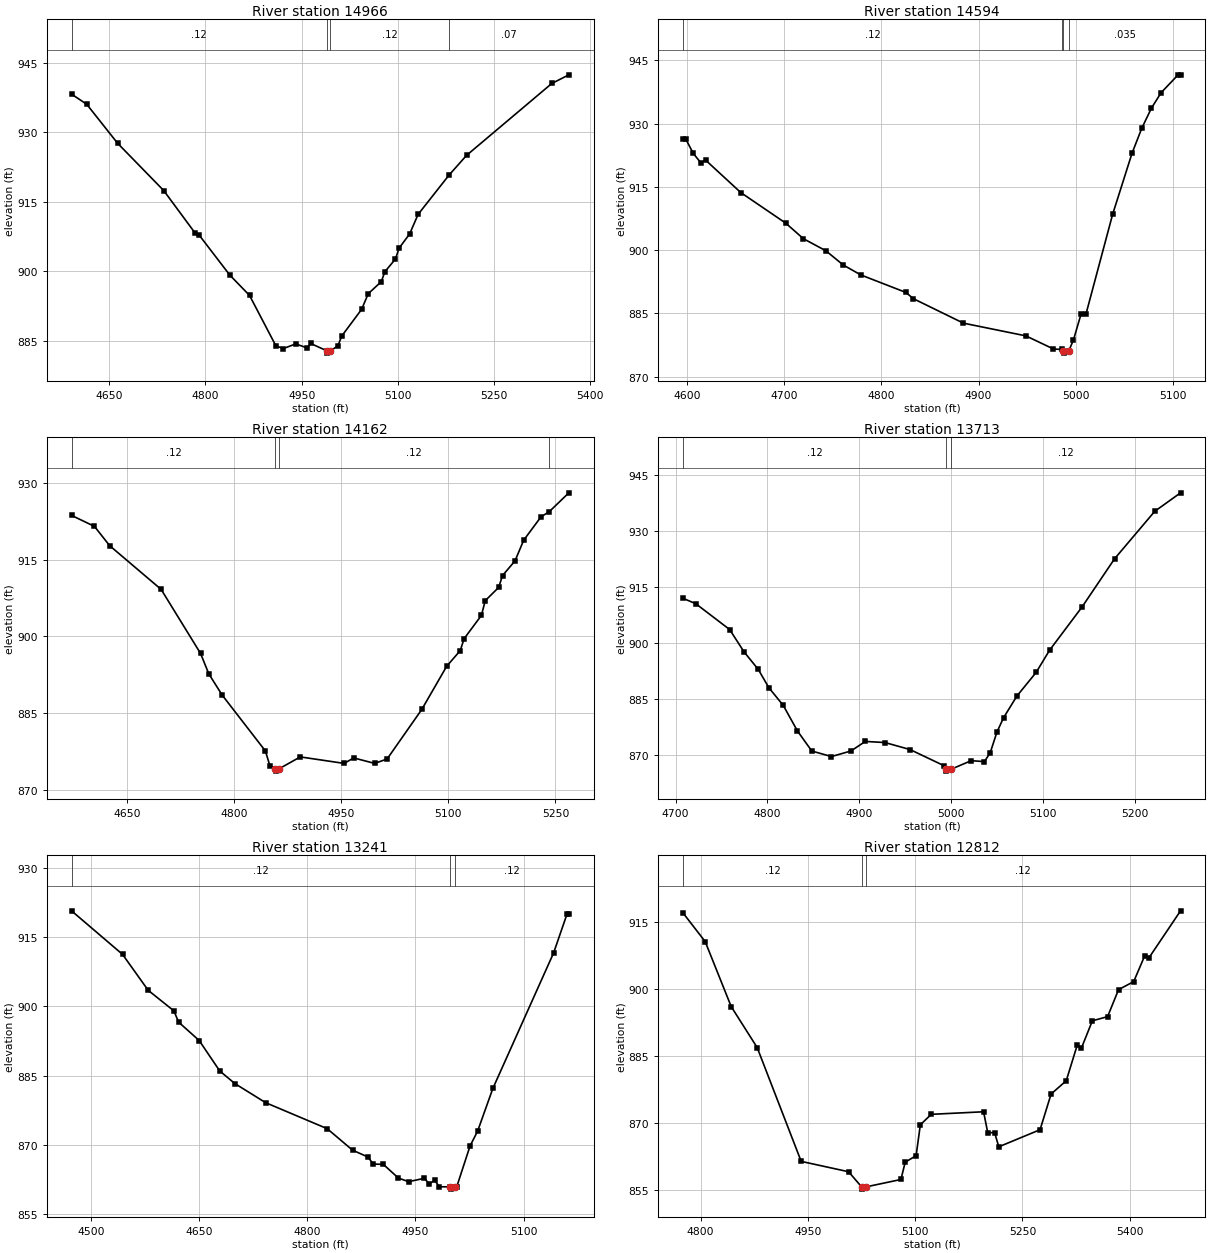
Type RM Length L Ch R = 1 ,14966   ,372,372,372
BEGIN DESCRIPTION:
Cordovs Hollow 33.0
END DESCRIPTION:
XS GIS Cut Line= 3
      2245175.01     13861425.03       2245283.7     13861885.85
      2245422.23     13862153.68
#Sta/Elev= 30
  4591.4  938.28  4615.1  936.08  4663.3  927.64  4735.2  917.41  4784.4  908.16
  4789.6  907.93    4838  899.17  4868.8  894.76  4909.9  883.85  4921.7  883.29
  4940.7  884.28  4958.9   883.4    4964  884.38  4989.3  882.79  4989.7  882.29
  4994.9  882.79  5006.3  883.84  5012.6  886.01  5043.4  891.74  5053.8  895.14
  5074.1  897.74  5079.7  899.89  5096.2  902.64  5101.8  904.97  5118.3  908.06
  5131.5  912.29  5179.6  920.76  5206.9  925.03  5339.8  940.58  5366.4  942.45
#Mann= 4 ,-1 , 0
  4591.4     .12       0  4989.3     .05       0  4994.9     .12       0
  5179.6     .07       0
Bank Sta=4989.3,4994.9
XS Rating Curve= 0 ,0
Exp/Cntr=0.3,0.1

Type RM Length L Ch R = 1 ,14594   ,432,432,432
BEGIN DESCRIPTION:
Cordovs Hollow 32.0
END DESCRIPTION:
XS GIS Cut Line= 3
        2245025.       13861525.        2244925.       13861925.
        2244925.     13862024.99
#Sta/Elev= 30
  4595.8  926.34  4598.4  926.34  4606.1  922.94  4613.8  920.74    4619   921.3
  4655.1  913.64  4701.5  906.37  4719.5  902.71  4742.7  899.84  4760.7  896.45
  4778.8   894.1  4825.2  889.95  4832.9  888.47  4884.4  882.67  4948.8  879.65
  4977.2  876.54  4985.5  876.43  4987.3  876.06  4987.7  875.56  4992.9  876.06
  4997.8   878.7  5005.5  884.75  5010.6  884.75  5038.1  908.45  5058.1  922.95
  5068.1  928.86  5078.1  933.66  5088.1  937.33  5105.6  941.56  5108.1  941.56
#Mann= 4 ,-1 , 0
  4595.8     .12       0  4985.5    .035       0  4987.3    .035       0
  4992.9    .035       0
Bank Sta=4987.3,4992.9
XS Rating Curve= 0 ,0
Exp/Cntr=0.3,0.1

Type RM Length L Ch R = 1 ,14162   ,449,449,449
BEGIN DESCRIPTION:
Cordovs Hollow 31.0
END DESCRIPTION:
XS GIS Cut Line= 3
      2244675.01     13861424.96        2244525.       13861825.
        2244625.       13862075.
#Sta/Elev= 30
  4572.3  923.66  4604.4  921.51  4625.7  917.74  4697.8  909.19    4753  896.67
  4764.6  892.67  4783.3  888.53  4843.8  877.61    4850  874.76  4857.9  874.17
  4858.3  873.67  4863.5  874.17  4892.7  876.45  4954.1  875.18  4967.5  876.25
  4996.9  875.18  5014.3  876.05  5062.8  885.72  5097.8  894.19  5116.7  897.23
  5122.1  899.56  5146.3  904.11  5151.7  906.99  5170.5  909.58  5175.9   911.9
  5193.4  914.77  5205.5   918.8  5229.8  923.38  5241.2  924.37  5268.8  928.07
#Mann= 4 ,-1 , 0
  4572.3     .12       0  4857.9     .05       0  4863.5     .12       0
  5241.2    .035       0
Bank Sta=4857.9,4863.5
XS Rating Curve= 0 ,0
Exp/Cntr=0.3,0.1

Type RM Length L Ch R = 1 ,13713   ,472,472,472
BEGIN DESCRIPTION:
Cordovs Hollow 30.0
END DESCRIPTION:
XS GIS Cut Line= 3
      2244475.03     13861374.98        2244225.       13861525.
      2244024.98     13861675.01
#Sta/Elev= 30
  4708.4  911.98    4722  910.58    4759  903.63  4774.5  897.69  4790.1  892.94
  4801.7  888.01  4817.3  883.29  4832.8  876.42  4848.4  871.04  4869.8  869.55
  4891.1  871.05  4906.7  873.61  4928.1  873.31  4955.3  871.44  4992.2  867.12
  4994.1  866.14  4994.6  865.64  5000.1  866.14  5021.9  868.44  5036.4   868.2
  5042.7  870.56    5050  876.09  5057.3  879.99  5071.9  885.83  5092.7  892.12
  5107.3  898.06  5142.7  909.68  5178.1  922.61  5221.9  935.36    5250  940.32
#Mann= 3 ,-1 , 0
  4708.4     .12       0  4994.1     .05       0  5000.1     .12       0
Bank Sta=4994.1,5000.1
XS Rating Curve= 0 ,0
Exp/Cntr=0.3,0.1

Type RM Length L Ch R = 1 ,13241   ,429,429,429
BEGIN DESCRIPTION:
Cordovs Hollow 29.0
END DESCRIPTION:
XS GIS Cut Line= 3
      2244374.99     13860725.01        2244025.       13861125.
      2243875.01       13861175.
#Sta/Elev= 30
  4473.2  920.69  4543.9  911.27  4579.5  903.49  4615.1  899.05  4621.7   896.6
  4650.2  892.63  4678.7  886.04  4699.6  883.32  4742.3  879.18  4827.7  873.55
  4862.8  868.91  4884.6  867.39  4891.3   865.9  4905.5  865.83  4926.4  862.87
  4940.6  862.08  4962.5  862.82  4969.1  861.59  4976.7  862.39  4983.3  860.98
  4998.3  860.97  4998.8  860.47  5004.4  860.97  5007.3  860.97  5025.8  869.81
  5036.3  873.03  5057.4  882.25  5141.7   911.6  5160.2  919.98  5162.8  919.98
#Mann= 3 ,-1 , 0
  4473.2     .12       0  4998.3     .05       0  5004.4     .12       0
Bank Sta=4998.3,5004.4
XS Rating Curve= 0 ,0
Exp/Cntr=0.3,0.1

Type RM Length L Ch R = 1 ,12812   ,473,473,473
BEGIN DESCRIPTION:
Cordovs Hollow 28.0
END DESCRIPTION:
XS GIS Cut Line= 3
      2244224.98     13860625.01        2244025.       13860725.
      2243774.99     13861125.02
#Sta/Elev= 30
  4775.8  916.94  4806.5  910.59  4842.9  896.03  4879.2  886.87  4940.7   861.4
    5007  859.08  5025.2  855.69  5025.7  855.19  5031.3  855.69  5080.2  857.35
  5086.1  861.21  5101.4  862.68  5107.3  869.59  5122.6  871.93  5195.7   872.5
  5201.6  867.79  5211.1  867.85    5217  864.66  5274.7  868.49  5290.1  876.47
  5311.3  879.45  5326.6  887.39  5332.5  886.74  5347.8  892.86  5369.1  893.79
  5384.4  899.83  5405.6  901.63    5421  907.41  5426.9  906.95  5471.1  917.47
#Mann= 3 ,-1 , 0
  4775.8     .12       0  5025.2     .05       0  5031.3     .12       0
Bank Sta=5025.2,5031.3
XS Rating Curve= 0 ,0
Exp/Cntr=0.3,0.1

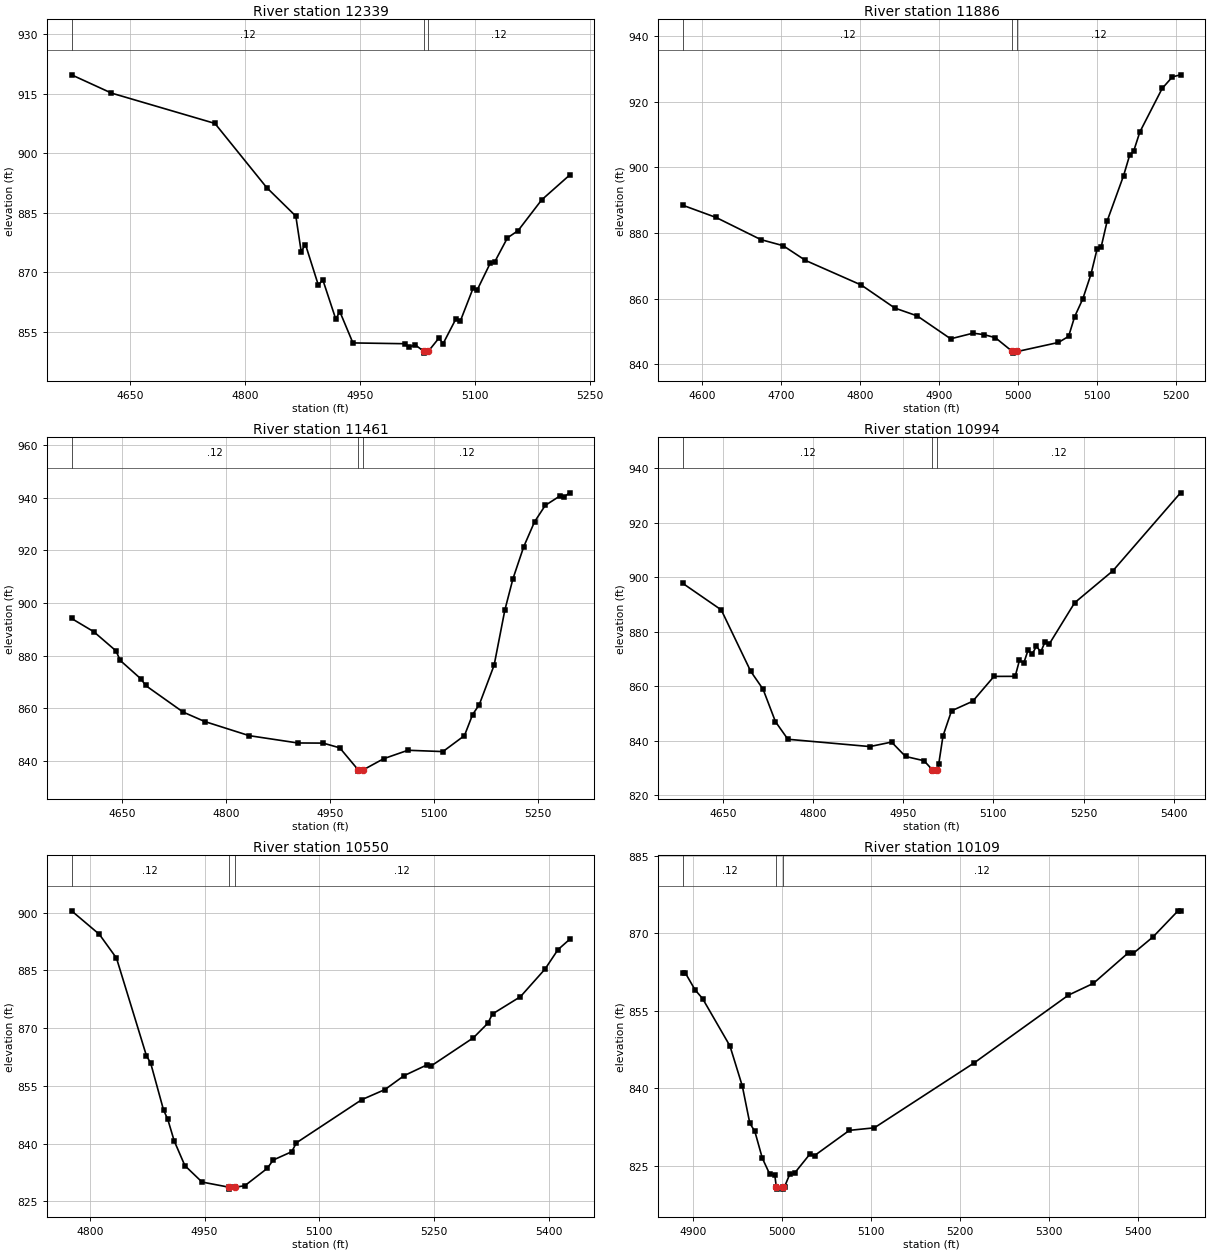
Type RM Length L Ch R = 1 ,12339   ,453,453,453
BEGIN DESCRIPTION:
Cordovs Hollow 27.0
END DESCRIPTION:
XS GIS Cut Line= 3
       2243912.3     13860242.04        2243725.       13860625.
      2243625.01     13860824.99
#Sta/Elev= 30
  4573.6  919.78  4625.7  915.18  4760.7  907.54  4828.3  891.38  4866.3  884.19
  4873.3  875.28  4878.9  877.04  4895.8  866.75  4901.4  868.23  4918.3  858.35
  4923.9  860.07  4940.8  852.26  5008.3  852.06  5013.9  851.24  5022.3  851.74
    5033  850.19  5033.5  849.69  5039.4  850.19    5053  853.46  5058.6   852.1
  5075.4  858.37    5081  857.76  5097.7  866.05  5103.3  865.71  5120.1  872.37
  5125.7   872.6  5142.5  878.72  5156.4  880.54  5187.2  888.29  5223.5   894.5
#Mann= 3 ,-1 , 0
  4573.6     .12       0    5033     .05       0  5039.4     .12       0
Bank Sta=5033,5039.4
XS Rating Curve= 0 ,0
Exp/Cntr=0.3,0.1

Type RM Length L Ch R = 1 ,11886   ,425,425,425
BEGIN DESCRIPTION:
Cordovs Hollow 26.0
END DESCRIPTION:
XS GIS Cut Line= 3
        2243625.       13860375.        2243325.       13860675.
        2243275.     13860874.99
#Sta/Elev= 30
  4575.7  888.49  4618.1  884.75  4674.7  878.01    4703  876.15  4731.3  871.66
    4802  864.15  4844.4  857.14  4872.7  854.76  4915.1  847.77  4943.4  849.49
  4957.5  849.04  4971.7  848.11  4993.2  843.91  4993.7  843.41  4999.6  843.91
  5051.5  846.66  5064.4  848.51  5072.1  854.53  5082.4  859.95  5092.7  867.43
  5100.5  875.16  5105.6  875.72  5113.3  883.73    5134  897.48  5141.7  903.71
  5146.8  904.98  5154.6  910.79  5182.9  924.07  5195.8  927.58  5206.1  928.21
#Mann= 3 ,-1 , 0
  4575.7     .12       0  4993.2     .05       0  4999.6     .12       0
Bank Sta=4993.2,4999.6
XS Rating Curve= 0 ,0
Exp/Cntr=0.3,0.1

Type RM Length L Ch R = 1 ,11461   ,467,467,467
BEGIN DESCRIPTION:
Cordovs Hollow 25.0
END DESCRIPTION:
XS GIS Cut Line= 3
      2243124.98     13860075.04        2242975.       13860475.
        2242825.       13860725.
#Sta/Elev= 30
    4577  894.13    4609  889.11    4641  881.86  4647.3  878.18  4677.5  871.09
  4683.8   868.7    4738  858.59  4769.2     855  4833.3  849.64  4903.6  846.86
  4940.1  846.81  4964.1  845.01  4990.6  836.67  4991.1  836.17  4998.1  836.67
  5027.5  840.89  5062.5  844.09    5113  843.59  5144.1  849.66  5155.8  857.62
  5165.5  861.44  5186.9  876.39  5202.4  897.34  5214.1  909.23  5229.6  921.35
  5245.2  930.81  5260.7  937.06  5282.1  940.67  5287.9  940.24  5295.7  941.83
#Mann= 3 ,-1 , 0
    4577     .12       0  4990.6     .05       0  4998.1     .12       0
Bank Sta=4990.6,4998.1
XS Rating Curve= 0 ,0
Exp/Cntr=0.3,0.1

Type RM Length L Ch R = 1 ,10994   ,444,444,444
BEGIN DESCRIPTION:
Cordovs Hollow 24.0
END DESCRIPTION:
XS GIS Cut Line= 3
        2242725.     13859824.98        2242625.       13860225.
      2242329.24     13860518.36
#Sta/Elev= 30
  4582.6   897.8    4647  888.02    4696  865.53  4716.6  858.94  4737.2  847.06
  4757.9  840.61  4894.4  837.93  4930.5  839.58  4953.7  834.31  4984.6  832.73
  4998.3  829.43  4998.8  828.93  5005.8  829.43    5009  831.52  5016.1  841.82
  5030.3  851.03  5065.6  854.54    5101  863.65  5136.3  863.67  5143.4  869.56
  5150.5   868.5  5157.6  873.19  5164.6  871.86  5171.7  874.71  5178.8  872.59
  5185.9  876.26  5192.9  875.48  5235.3  890.65    5299  902.37  5411.5  930.93
#Mann= 3 ,-1 , 0
  4582.6     .12       0  4998.3     .05       0  5005.8     .12       0
Bank Sta=4998.3,5005.8
XS Rating Curve= 0 ,0
Exp/Cntr=0.3,0.1

Type RM Length L Ch R = 1 ,10550   ,441,441,441
BEGIN DESCRIPTION:
Cordovs Hollow 23.0
END DESCRIPTION:
XS GIS Cut Line= 3
      2242474.99     13859675.01        2242375.       13859875.
        2242225.     13860275.01
#Sta/Elev= 30
  4776.2   900.5  4812.5  894.39  4834.9  888.21    4874  862.86  4879.6   860.9
  4896.4  848.72    4902  846.26  4910.3   840.7  4924.3  834.25  4946.7  829.98
    4982  828.64  4982.5  828.14  4989.6  828.64  5002.5  829.01  5031.8  833.51
  5039.8  835.71  5063.9  837.86  5070.1  840.19  5155.5   851.4  5185.8  854.03
  5210.7  857.63    5241  860.47  5246.3  860.19  5301.5  867.51  5320.2  871.26
  5326.4  873.69  5362.9  878.18    5395  885.35  5411.9   890.4    5427  893.05
#Mann= 3 ,-1 , 0
  4776.2     .12       0    4982     .05       0  4989.6     .12       0
Bank Sta=4982,4989.6
XS Rating Curve= 0 ,0
Exp/Cntr=0.3,0.1

Type RM Length L Ch R = 1 ,10109   ,476,476,476
BEGIN DESCRIPTION:
Cordovs Hollow 22.0
END DESCRIPTION:
XS GIS Cut Line= 3
      2242075.02     13859574.96        2242025.       13859675.
      2241824.98     13860075.03
#Sta/Elev= 30
  4888.5  862.41  4891.3  862.41  4902.5  859.06  4910.9  857.38  4941.7  848.19
  4955.6  840.41    4964  833.22  4969.6  831.67    4978  826.48  4986.4  823.35
    4992  823.25  4993.7  820.97  4994.2  820.47  5000.9  820.47  5001.4  820.97
  5003.1  820.97  5008.7  823.31  5014.3  823.58  5031.1  827.18  5036.7  826.97
  5075.8  831.85  5103.8  832.34  5215.6  844.88  5321.8  858.04  5349.7  860.31
  5388.9  866.22  5394.5  866.12  5416.8  869.32  5444.8  874.36  5447.6  874.36
#Mann= 3 ,-1 , 0
  4888.5     .12       0  4993.7     .05       0  5001.4     .12       0
Bank Sta=4993.7,5001.4
XS Rating Curve= 0 ,0
Exp/Cntr=0.3,0.1

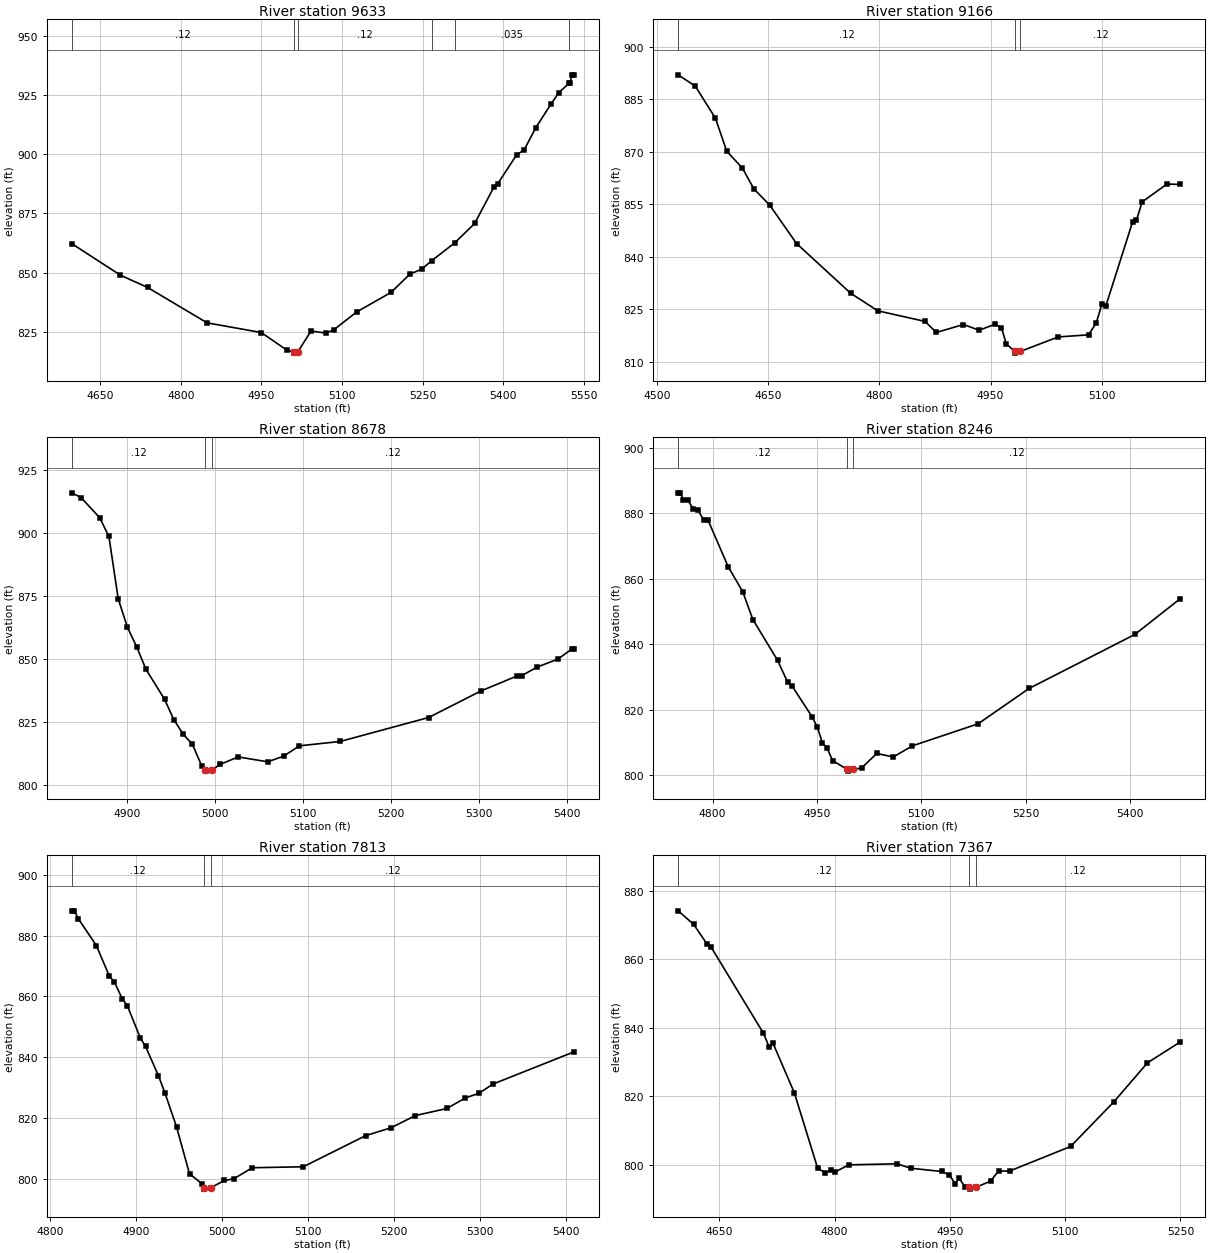
Type RM Length L Ch R = 1 ,9633    ,467,467,467
BEGIN DESCRIPTION:
Cordovs Hollow 21.0
END DESCRIPTION:
XS GIS Cut Line= 3
      2242024.95     13859425.01        2241625.       13859475.
      2241274.98     13859875.02
#Sta/Elev= 30
  4596.9  862.21  4687.6  848.88  4737.9  843.74  4848.8  828.78  4949.6   824.7
  4997.4  817.25  5009.9   816.5  5010.4     816  5017.6   816.5  5042.2  825.31
  5070.7  824.45  5084.9  825.89  5127.6  833.44  5191.2  841.62  5226.3  849.34
  5248.2  851.45  5267.3  855.07  5310.4  862.67  5346.9  870.74  5382.9  886.16
  5389.6  887.41  5425.2  899.77  5438.9  901.74  5460.8   911.2  5489.2   921.2
  5503.5  925.91  5522.1  929.81  5524.4  930.13  5528.1  933.46  5531.5  933.46
#Mann= 6 ,-1 , 0
  4596.9     .12       0  5009.9     .05       0  5017.6     .12       0
  5267.3     .07       0  5310.4    .035       0  5522.1     .12       0
Bank Sta=5009.9,5017.6
XS Rating Curve= 0 ,0
Exp/Cntr=0.3,0.1

Type RM Length L Ch R = 1 ,9166    ,488,488,488
BEGIN DESCRIPTION:
Cordovs Hollow 20.0
END DESCRIPTION:
XS GIS Cut Line= 3
      2241925.03     13858824.98        2241525.       13859075.
      2241324.99       13859125.
#Sta/Elev= 30
  4528.3  892.02  4551.3  888.79  4578.5  879.63  4593.8  870.19    4615  865.34
  4630.3  859.43  4651.6  854.83  4688.1  843.78  4761.2  829.56  4797.8  824.55
  4861.5  821.53  4876.8  818.37  4913.4  820.64  4934.6  819.01  4955.8  820.71
  4964.7  819.78  4971.1  815.17  4982.5  812.96    4983  812.46  4990.4  812.96
  5041.3  817.09  5082.5  817.69  5092.8  821.19  5100.5  826.54  5105.7  825.99
  5141.8     850  5146.9  850.38  5154.6  855.68  5188.1  860.79  5206.2  860.69
#Mann= 3 ,-1 , 0
  4528.3     .12       0  4982.5     .05       0  4990.4     .12       0
Bank Sta=4982.5,4990.4
XS Rating Curve= 0 ,0
Exp/Cntr=0.3,0.1

Type RM Length L Ch R = 1 ,8678    ,432,432,432
BEGIN DESCRIPTION:
Cordovs Hollow 19.0
END DESCRIPTION:
XS GIS Cut Line= 3
      2241475.01     13858474.96        2241425.       13858625.
      2241324.99     13859025.03
#Sta/Elev= 30
  4837.5  916.06  4848.1  914.17  4869.2  906.19  4879.7  898.72  4890.3  873.91
  4900.8  862.63  4911.3  854.85  4921.9  845.91    4943  834.03  4953.5  825.96
    4964  820.26  4974.6  816.17  4985.1  807.67    4989  806.05  4989.5  805.55
    4997  806.05    5006  808.21  5026.6  811.19  5060.1  809.25  5078.1  811.47
  5096.2   815.6  5142.5  817.33    5243  826.84  5302.3  837.36  5343.5  843.34
  5348.7  843.48  5366.7  846.91  5389.9  850.05  5405.4  853.95    5408  853.95
#Mann= 3 ,-1 , 0
  4837.5     .12       0    4989     .05       0    4997     .12       0
Bank Sta=4989,4997
XS Rating Curve= 0 ,0
Exp/Cntr=0.3,0.1

Type RM Length L Ch R = 1 ,8246    ,433,433,433
BEGIN DESCRIPTION:
Cordovs Hollow 18.0
END DESCRIPTION:
XS GIS Cut Line= 3
      2240824.97     13858474.98        2241025.       13858625.
      2241274.98     13859024.97
#Sta/Elev= 30
  4750.5  886.22  4753.7  886.22  4757.8   884.1  4764.1  883.96  4772.4  881.27
  4778.7  880.97    4787  877.95  4793.2  877.93  4822.4  863.61  4843.2  856.01
  4857.8  847.52  4893.2  835.08  4907.8  828.34  4914.1  827.23  4943.2   817.7
  4950.5  814.61  4957.8  809.81  4964.1  808.42  4972.4  804.45  4993.4  801.71
  4993.9  801.21  5001.5  801.71  5014.1  802.19  5035.9   806.6  5059.5  805.53
  5087.2  808.94  5181.5  815.66  5254.7  826.45  5406.8  842.95  5472.2   853.9
#Mann= 3 ,-1 , 0
  4750.5     .12       0  4993.4     .05       0  5001.5     .12       0
Bank Sta=4993.4,5001.5
XS Rating Curve= 0 ,0
Exp/Cntr=0.3,0.1

Type RM Length L Ch R = 1 ,7813    ,446,446,446
BEGIN DESCRIPTION:
Cordovs Hollow 17.0
END DESCRIPTION:
XS GIS Cut Line= 3
      2240574.97     13858674.96        2240675.       13858825.
      2240874.98     13859174.97
#Sta/Elev= 30
  4825.3  888.12  4828.4  888.12  4832.9  885.52  4853.9  876.69  4868.9  866.69
  4874.9  864.63  4883.9  859.23  4889.9  856.85    4905  846.25    4911  843.52
    4926  833.88  4933.5  828.26    4947  817.07  4962.1   801.6  4977.1  798.21
    4979  797.05  4979.5  796.55  4987.1  797.05  5002.6  799.39  5013.5  799.95
  5035.1  803.59  5094.2   803.9  5166.9  814.16  5196.4  816.75  5224.5  820.75
  5261.2  823.09  5282.8  826.58  5298.6  828.09  5314.4  831.08  5408.7   841.7
#Mann= 3 ,-1 , 0
  4825.3     .12       0    4979     .05       0  4987.1     .12       0
Bank Sta=4979,4987.1
XS Rating Curve= 0 ,0
Exp/Cntr=0.3,0.1

Type RM Length L Ch R = 1 ,7367    ,432,432,432
BEGIN DESCRIPTION:
Cordovs Hollow 16.0
END DESCRIPTION:
XS GIS Cut Line= 3
      2240424.99     13858725.05        2240375.       13859125.
      2240525.02     13859325.03
#Sta/Elev= 30
  4596.7  874.09  4616.8  870.12  4634.4  864.32  4639.5  863.47  4707.5  838.39
  4715.1  834.32  4720.1  835.38  4747.8  820.95  4778.1  798.94  4788.1  797.65
  4795.7  798.47  4800.7  797.87  4818.4  799.96  4881.4  800.28    4899  798.98
  4939.3  798.03  4949.4  797.02  4956.9   794.5    4962  796.08  4969.5  793.61
  4975.5  793.38    4976  792.88  4983.7  793.38  5002.9  795.21  5013.3  798.15
  5027.9  798.17  5107.1  805.33  5163.3  818.34  5207.1  829.75  5249.8  835.83
#Mann= 3 ,-1 , 0
  4596.7     .12       0  4975.5     .05       0  4983.7     .12       0
Bank Sta=4975.5,4983.7
XS Rating Curve= 0 ,0
Exp/Cntr=0.3,0.1

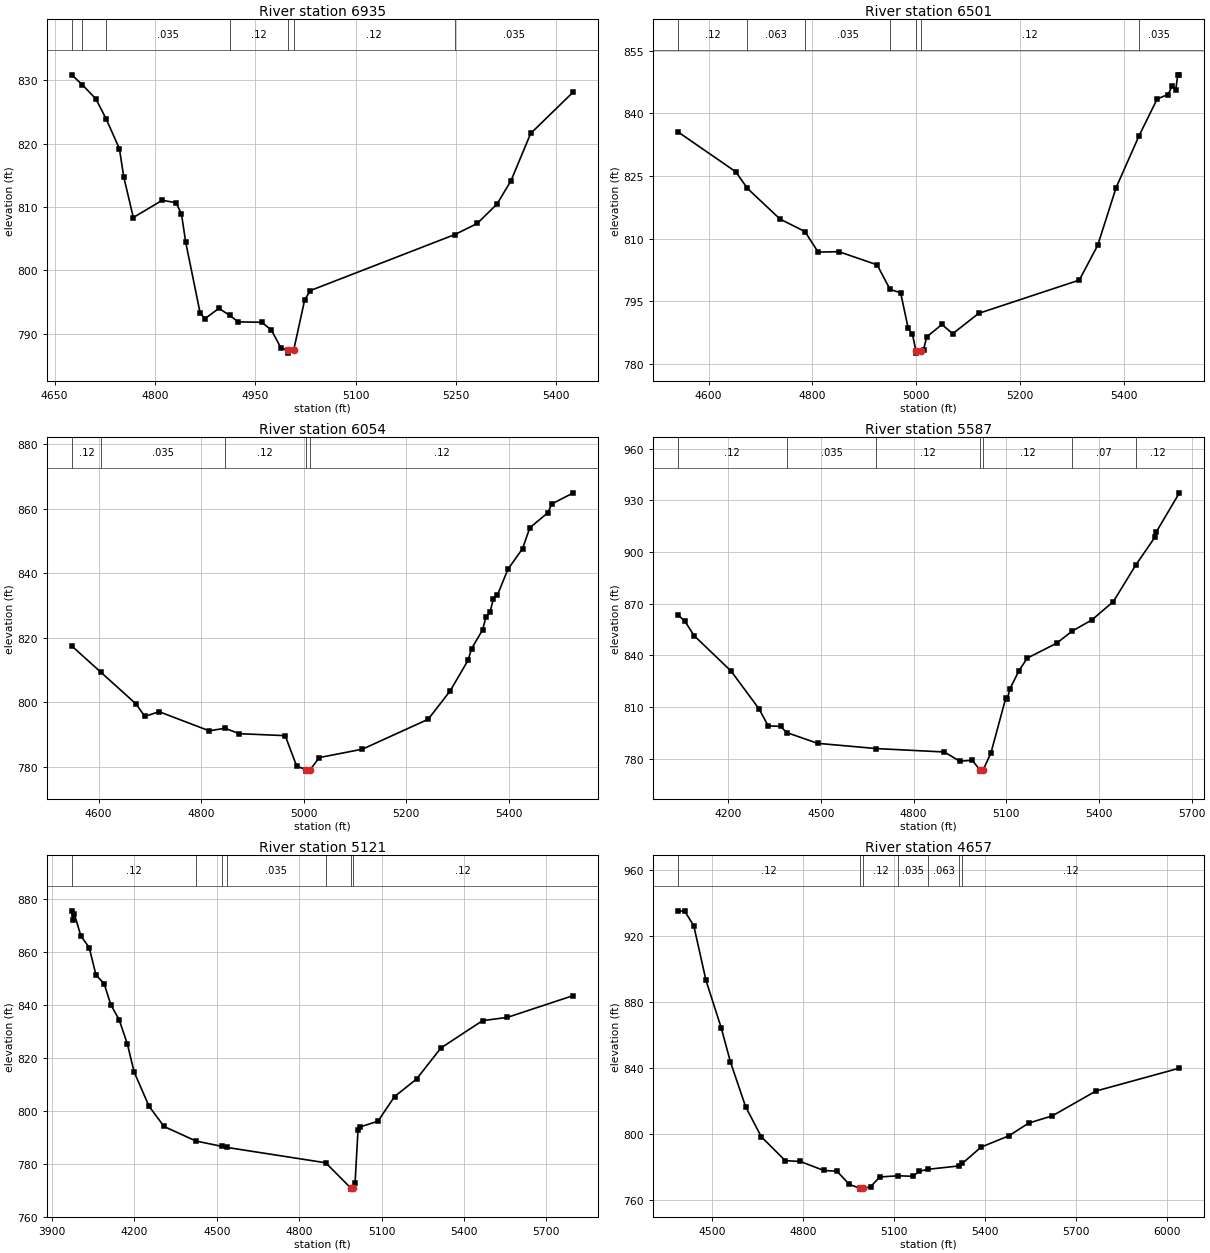
Type RM Length L Ch R = 1 ,6935    ,434,434,434
BEGIN DESCRIPTION:
Cordovs Hollow 15.0
END DESCRIPTION:
XS GIS Cut Line= 3
      2239724.99     13859024.99        2239975.       13859225.
      2240225.01     13859575.01
#Sta/Elev= 30
  4675.6  830.84  4691.3  829.28  4711.6  827.05  4726.8  823.94  4746.9  819.18
  4753.3  814.77  4767.7  808.32  4810.9  811.04  4831.7  810.65  4839.7  808.86
  4846.1  804.39  4867.7  793.21  4874.9  792.37  4895.7  793.98    4912  792.87
  4924.5  791.85  4959.8  791.79  4974.2  790.56  4988.6  787.71  4998.7  787.42
  4999.2  786.92  5007.6  787.42    5024  795.33  5032.6   796.8  5248.5  805.63
  5282.1  807.38  5311.6  810.44  5332.5  814.11    5362  821.59  5425.9  828.15
#Mann= 7 ,-1 , 0
  4675.6    .035       0  4691.3    .063       0  4726.8    .035       0
    4912     .12       0  4998.7     .05       0  5007.6     .12       0
  5248.5    .035       0
Bank Sta=4998.7,5007.6
XS Rating Curve= 0 ,0
Exp/Cntr=0.3,0.1

Type RM Length L Ch R = 1 ,6501    ,447,447,447
BEGIN DESCRIPTION:
Cordovs Hollow 14.0
END DESCRIPTION:
XS GIS Cut Line= 3
       2239424.1     13859004.52        2239625.       13859425.
        2239925.     13859824.99
#Sta/Elev= 30
  4540.6  835.63  4652.3  826.05  4674.8  822.06  4737.5  814.72  4785.4  811.74
    4811  806.81  4850.9  806.91  4924.5  803.76  4949.5  797.87  4969.8  797.07
  4984.4  788.56  4992.5  787.17  4999.3  783.12  4999.8  782.62  5008.3  783.12
  5013.9  783.47  5020.1  786.52  5049.3  789.48  5070.1  787.27  5120.1  792.14
  5313.9  800.11  5349.3  808.44  5384.7  822.23    5429  834.69  5463.9   843.5
  5484.7  844.54  5493.1  846.66  5499.3  845.53  5503.5  849.26  5506.6  849.26
#Mann= 7 ,-1 , 0
  4540.6     .12       0  4674.8    .063       0  4785.4    .035       0
  4949.5     .12       0  4999.3     .05       0  5008.3     .12       0
    5429    .035       0
Bank Sta=4999.3,5008.3
XS Rating Curve= 0 ,0
Exp/Cntr=0.3,0.1

Type RM Length L Ch R = 1 ,6054    ,467,467,467
BEGIN DESCRIPTION:
Cordovs Hollow 13.0
END DESCRIPTION:
XS GIS Cut Line= 3
      2239125.01     13859325.03        2239325.       13859725.
      2239725.01     13860075.01
#Sta/Elev= 30
  4547.8  817.51    4605  809.31  4673.5   799.5  4690.3  795.68  4718.3  797.14
  4816.1  791.21  4846.6  792.01  4874.8  790.33  4964.2  789.72  4986.6  780.29
  5004.2  779.23  5004.7  778.73  5013.3  779.23  5030.6  782.92    5115  785.54
  5243.2   794.8  5285.9  803.54    5321  813.07  5327.7  816.62  5349.5  822.55
  5356.1  826.63  5363.7  827.95  5370.4  832.05    5378  833.18  5398.8  841.28
  5427.3  847.66  5441.5  854.14  5476.7  858.79  5484.3   861.5  5526.5  864.95
#Mann= 5 ,-1 , 0
  4547.8     .12       0    4605    .035       0  4846.6     .12       0
  5004.2     .05       0  5013.3     .12       0
Bank Sta=5004.2,5013.3
XS Rating Curve= 0 ,0
Exp/Cntr=0.3,0.1

Type RM Length L Ch R = 1 ,5587    ,466,466,466
BEGIN DESCRIPTION:
X18552
END DESCRIPTION:
XS GIS Cut Line= 3
      2239008.54     13859092.28      2238990.07     13860020.39
      2239091.66     13860708.44
#Sta/Elev= 30
  4036.6  863.62  4059.3  859.99  4089.3  851.54  4209.4  830.92  4299.4  809.09
  4329.4  799.16  4369.4  798.88  4389.3  795.29  4489.4  789.04  4679.4     786
  4899.5  784.02  4949.5  778.63  4989.8  779.26  5015.5  773.42    5016  772.92
  5024.7  773.42  5050.4  783.46  5098.6  815.45  5103.7  814.63  5111.1  820.42
  5141.4  831.26  5168.2  838.49  5262.7  847.06  5313.6  854.16  5377.1  860.61
  5446.7  871.28  5518.8  892.34  5580.8   908.5  5586.2  911.82  5660.4  934.33
#Mann= 7 ,-1 , 0
  4036.6     .12       0  4389.3    .035       0  4679.4     .12       0
  5015.5     .05       0  5024.7     .12       0  5313.6     .07       0
  5518.8     .12       0
Bank Sta=5015.5,5024.7
XS Rating Curve= 0 ,0
Exp/Cntr=0.3,0.1

Type RM Length L Ch R = 1 ,5121    ,464,464,464
BEGIN DESCRIPTION:
X18551
END DESCRIPTION:
XS GIS Cut Line= 4
      2238962.38     13859069.16      2238634.52     13859914.19
      2238519.09     13860140.44      2238486.77     13860805.36
#Sta/Elev= 30
  3972.2  875.62  3975.9  872.14  3981.3  874.51  4005.3  866.19  4035.8  861.69
  4060.3   851.4  4090.2  848.01  4114.8  840.03  4144.7  834.44  4174.6  825.29
  4199.1  814.74  4253.6   801.7  4308.1  794.07  4424.1  788.58  4520.8   786.5
  4537.2  786.15  4896.7  780.34  4987.1  770.88  4987.6  770.38  4996.4  770.88
  5003.6  772.83  5014.2  792.67  5020.2  793.82  5086.9  796.08  5147.2  805.37
  5227.3     812  5316.1  823.76  5467.6  834.09  5557.7  835.32  5798.3  843.59
#Mann= 7 ,-1 , 0
  3972.2     .12       0  4424.1    .035       0  4520.8     .12       0
  4537.2    .035       0  4896.7     .12       0  4987.1     .05       0
  4996.4     .12       0
Bank Sta=4987.1,4996.4
XS Rating Curve= 0 ,0
Exp/Cntr=0.3,0.1

Type RM Length L Ch R = 1 ,4657    ,515,515,515
BEGIN DESCRIPTION:
X18550
END DESCRIPTION:
XS GIS Cut Line= 3
      2238154.31     13859152.33      2238242.04      13860075.8
      2238449.38     13860771.53
#Sta/Elev= 30
  4387.3  935.12  4410.1  934.92  4440.2  926.08  4480.4  893.02  4530.6  864.34
  4560.8  843.82    4611  816.62  4662.6  798.48  4741.6  783.99  4791.8  783.48
  4868.8  778.04  4912.3  777.59  4952.5  769.65    4988  767.26  4988.5  766.76
  4997.4  767.26  5022.8  768.14    5053  774.12  5113.3  774.83  5163.5   774.5
  5183.1  777.58  5212.4  778.76  5315.1  780.81  5325.8  782.41  5387.1  792.16
  5479.3  799.05  5543.7  806.68  5622.4  811.12  5765.5  826.08  6040.9  839.94
#Mann= 7 ,-1 , 0
  4387.3     .12       0    4988     .05       0  4997.4     .12       0
  5113.3    .035       0  5212.4    .063       0  5315.1    .035       0
  5325.8     .12       0
Bank Sta=4988,4997.4
XS Rating Curve= 0 ,0
Exp/Cntr=0.3,0.1