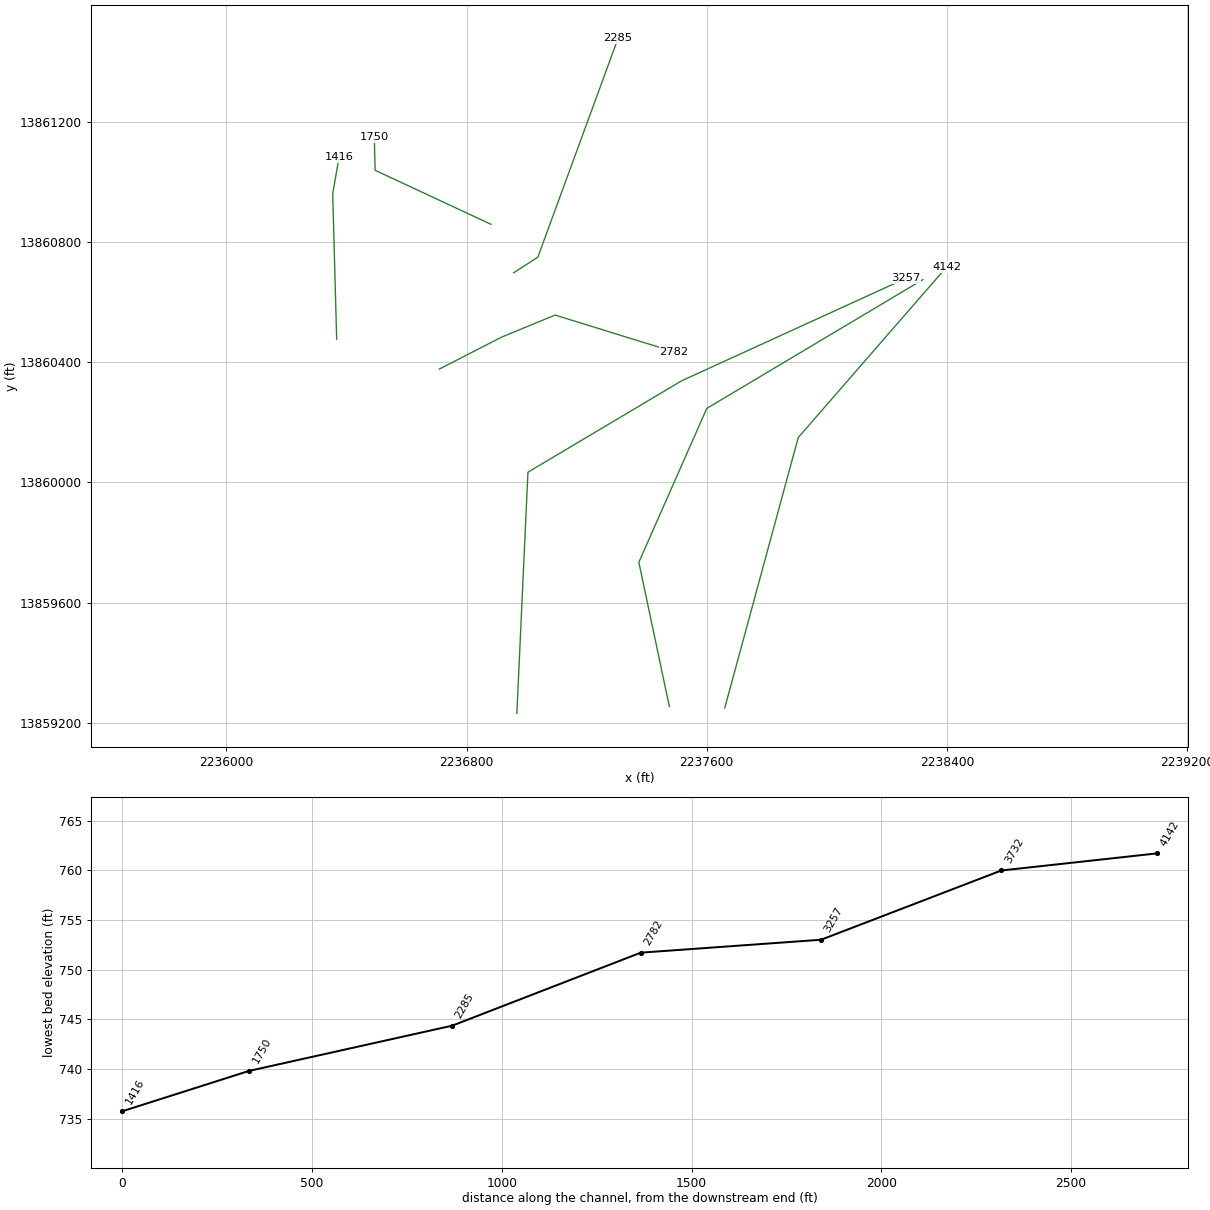
HEC-RAS study Cordovs Hollow.prj: Cordovs Hollow Base Level Engineering

--- Cordovs Hollow.g01 (geometry) --- (continued)

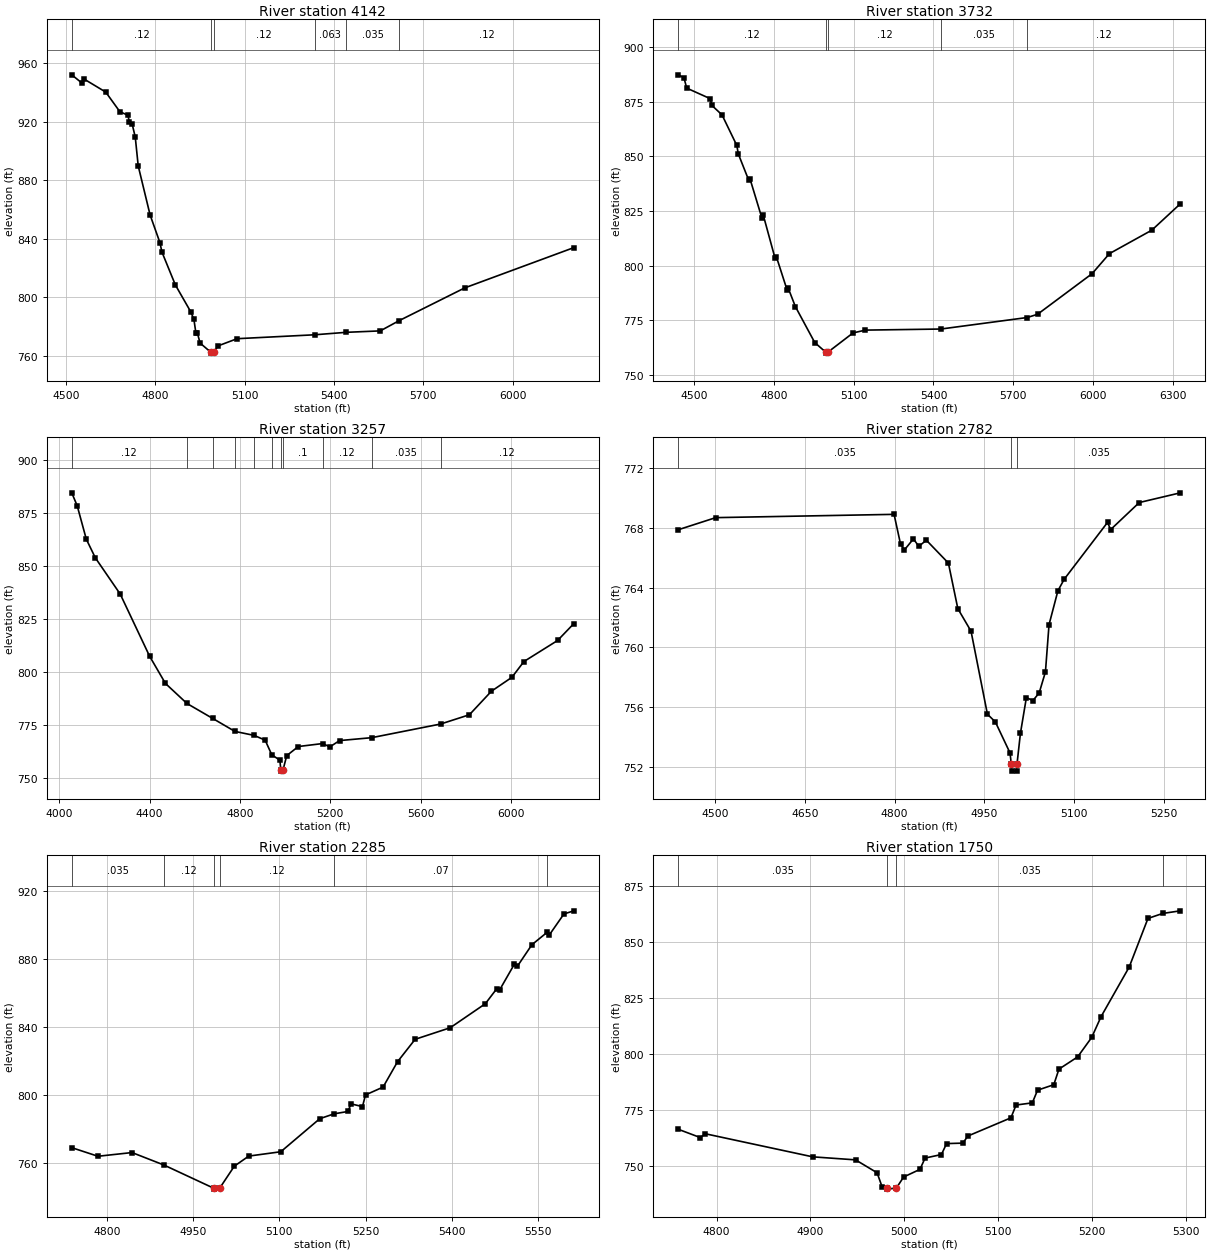
Type RM Length L Ch R = 1 ,4142    ,410,410,410
BEGIN DESCRIPTION:
X18549
END DESCRIPTION:
XS GIS Cut Line= 3
      2237660.23     13859249.26      2237904.96     13860149.68
      2238399.06     13860717.66
#Sta/Elev= 30
  4519.2  952.17  4553.7  946.48  4558.9  949.48  4633.3  940.35  4680.6  926.96
  4707.7  924.51  4712.9  919.64    4722  918.47  4732.4  909.56  4742.3  889.84
  4782.1  856.34  4815.3  837.27  4821.9  830.93  4867.1  808.36  4918.9  789.93
  4929.3  784.78  4936.1  775.39  4941.3  775.22    4950  768.61  4986.7  762.21
  4987.2  761.71  4996.2  762.21  5010.5  766.68  5074.4  771.59  5334.5  774.26
  5440.8  775.95  5555.1  776.93  5618.5  783.94    5839  806.38  6205.1  833.92
#Mann= 6 ,-1 , 0
  4519.2     .12       0  4986.7     .05       0  4996.2     .12       0
  5334.5    .063       0  5440.8    .035       0  5618.5     .12       0
Bank Sta=4986.7,4996.2
XS Rating Curve= 0 ,0
Exp/Cntr=0.3,0.1

Type RM Length L Ch R = 1 ,3732    ,475,475,475
BEGIN DESCRIPTION:
X18548
END DESCRIPTION:
XS GIS Cut Line= 4
      2237475.54     13859253.89      2237373.95     13859734.11
      2237600.21     13860246.65      2238320.26     13860675.91
#Sta/Elev= 30
  4439.4  887.28    4461  885.92  4471.2  881.21  4560.4  876.34  4565.5  873.35
  4604.1  868.97  4659.9  854.96  4665.4  851.13  4704.5  839.11  4709.6  839.66
  4754.2  821.77  4759.3  823.16  4803.9  803.31    4809  803.98  4848.5  789.05
  4853.6  789.62  4880.1   781.3  4953.1  764.84  4993.8  760.49  4994.3  759.99
  5003.3  760.49  5097.2  769.23  5143.8  770.52  5427.7  771.01  5752.7  776.28
  5791.5  777.75  5996.7  796.32  6062.1   805.5  6221.7  816.24  6328.8  828.28
#Mann= 5 ,-1 , 0
  4439.4     .12       0  4993.8     .05       0  5003.3     .12       0
  5427.7    .035       0  5752.7     .12       0
Bank Sta=4993.8,5003.3
XS Rating Curve= 0 ,0
Exp/Cntr=0.3,0.1

Type RM Length L Ch R = 1 ,3257    ,475,475,475
BEGIN DESCRIPTION:
X18547
END DESCRIPTION:
XS GIS Cut Line= 4
      2236967.61     13859230.81      2237004.55     13860034.24
      2237517.09       13860339.      2238264.35     13860680.33
#Sta/Elev= 30
  4055.8  884.49    4080  878.31  4120.1  862.59  4160.1  853.78  4270.2  836.66
  4400.4  807.28  4470.4  794.44  4565.4  784.99  4678.9  777.95  4777.7  771.79
  4862.5  769.91  4911.7  767.65  4940.9  760.76  4976.9  758.17    4981  753.52
  4981.5  753.02  4990.6  753.52  5007.2  760.34  5058.4  764.64  5166.2  766.05
    5198  764.46  5240.9  767.45    5383  768.82  5688.5  775.28  5815.6  779.65
  5913.2  790.78  6003.8  797.34  6056.9  804.79    6206  814.74  6277.9  822.72
#Mann= 11 ,-1 , 0
  4055.8     .12       0  4565.4     .07       0  4678.9     .12       0
  4777.7     .07       0  4862.5     .12       0  4940.9      .1       0
    4981     .05       0  4990.6      .1       0  5166.2     .12       0
    5383    .035       0  5688.5     .12       0
Bank Sta=4981,4990.6
XS Rating Curve= 0 ,0
Exp/Cntr=0.3,0.1

Type RM Length L Ch R = 1 ,2782    ,497,497,497
BEGIN DESCRIPTION:
X18546
END DESCRIPTION:
XS GIS Cut Line= 4
      2236709.19     13860377.78      2236917.75     13860484.67
      2237095.03     13860557.66      2237490.67     13860435.33
#Sta/Elev= 30
  4437.8  767.87  4500.5  768.68    4799   768.9  4809.8  766.91  4816.3  766.52
  4831.4  767.26  4840.3  766.76    4853  767.17  4889.9  765.64  4905.7  762.59
  4927.8  761.08  4955.2  755.53  4968.5  755.01    4993  752.94  4995.1  752.22
  4995.6  751.72  5004.3  751.72  5004.8  752.22  5010.4  754.24  5020.4  756.64
  5031.3  756.44  5041.8  756.95  5052.3  758.36  5058.3  761.52  5073.2  763.79
  5083.7  764.56  5156.2  768.36  5161.4  767.88  5209.3  769.69    5278  770.34
#Mann= 3 ,-1 , 0
  4437.8    .035       0  4995.1    .035       0  5004.8    .035       0
Bank Sta=4995.1,5004.8
XS Rating Curve= 0 ,0
Exp/Cntr=0.3,0.1

Type RM Length L Ch R = 1 ,2285    ,535,535,535
BEGIN DESCRIPTION:
X18545
END DESCRIPTION:
XS GIS Cut Line= 3
      2236956.86     13860698.44      2237037.54     13860750.63
      2237304.69     13861479.52
#Sta/Elev= 30
  4739.2  768.77  4784.7  763.71  4843.9  765.89  4899.1  758.59  4986.1  744.87
  4986.6  744.37  4996.1  744.87  5021.6  757.86  5046.7  763.81  5102.4  766.37
  5170.1  785.81    5195  788.68  5219.1  790.07  5224.4  794.55  5244.3  792.93
  5249.6   799.8  5280.1  804.41  5305.3  819.37  5335.8  832.53  5396.8  839.34
  5457.8  853.47  5477.7  862.33    5483  861.81  5508.2  876.71  5513.5  875.53
  5538.7  888.19  5564.8  895.39  5569.2  894.06  5594.4   906.3  5611.6  908.14
#Mann= 6 ,-1 , 0
  4739.2    .035       0  4899.1     .12       0  4986.1     .05       0
  4996.1     .12       0    5195     .07       0  5564.8     .12       0
Bank Sta=4986.1,4996.1
XS Rating Curve= 0 ,0
Exp/Cntr=0.3,0.1

Type RM Length L Ch R = 1 ,1750    ,334,334,334
BEGIN DESCRIPTION:
X18544
END DESCRIPTION:
XS GIS Cut Line= 3
      2236881.29     13860860.06      2236495.42     13861039.96
      2236492.81     13861149.48
#Sta/Elev= 30
  4759.1  766.56  4782.6  762.85  4788.1  764.54  4902.5  754.24  4948.2  752.89
  4971.1  747.13  4976.6  740.67  4981.7  740.32  4982.2  739.82  4991.7  740.32
  4999.4  745.23  5016.8  748.65  5022.3   753.7  5039.7  755.27  5045.2  760.16
  5062.5  760.37    5068  763.56  5113.8  771.67  5119.3  777.39  5136.6  778.35
  5142.2  784.02  5159.5  786.46    5165  793.42  5184.9  798.87  5199.9  807.56
  5209.9  816.86  5239.9  839.02  5259.9  860.73  5275.6  862.96  5294.4  864.13
#Mann= 4 ,-1 , 0
  4759.1    .035       0  4981.7    .035       0  4991.7    .035       0
  5275.6     .12       0
Bank Sta=4981.7,4991.7
XS Rating Curve= 0 ,0
Exp/Cntr=0.3,0.1

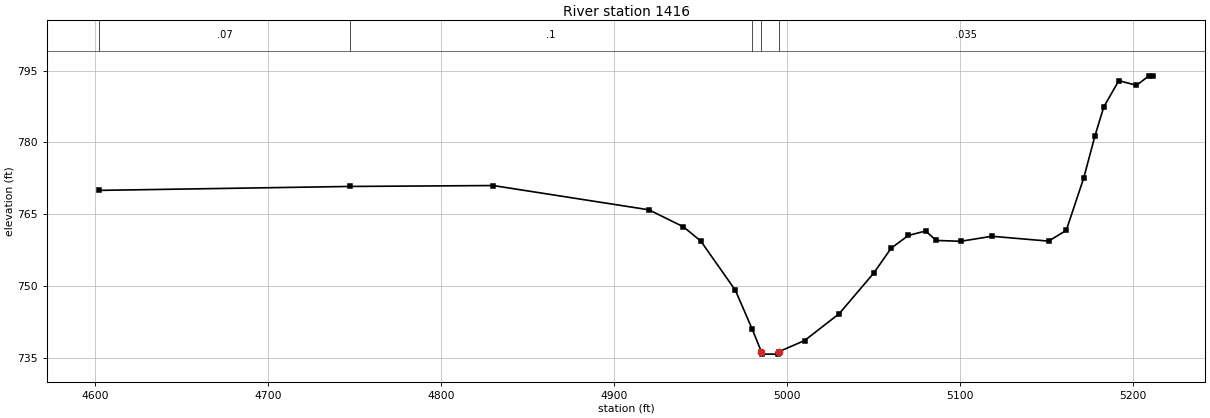
Type RM Length L Ch R = 1 ,1416    ,0,0,0
BEGIN DESCRIPTION:
X18543
END DESCRIPTION:
XS GIS Cut Line= 3
      2236367.34     13860477.53      2236354.13     13860961.81
       2236375.5      13861084.3
#Sta/Elev= 30
  4602.4  769.97  4747.1  770.79    4830  770.98    4920  765.91    4940  762.35
    4950  759.38    4970  749.09  4979.6  741.08    4985  736.26  4985.5  735.76
  4994.6  735.76  4995.1  736.26    5010   738.6    5030  744.21    5050  752.71
    5060  757.89    5070  760.56    5080  761.48    5086  759.51  5100.2  759.33
  5118.2  760.38    5151  759.37  5161.2   761.6  5171.3  772.54  5177.8  781.35
  5182.9  787.41  5191.6   792.9  5201.8  791.91    5209   793.9  5211.2   793.9
#Mann= 5 ,-1 , 0
  4602.4     .07       0  4747.1      .1       0  4979.6    .035       0
    4985    .035       0  4995.1    .035       0
Bank Sta=4985,4995.1
XS Rating Curve= 0 ,0
Exp/Cntr=0.3,0.1

Chan Stop Cuts=-1
Use User Specified Reach Order=0
Composite Channel Slope=5