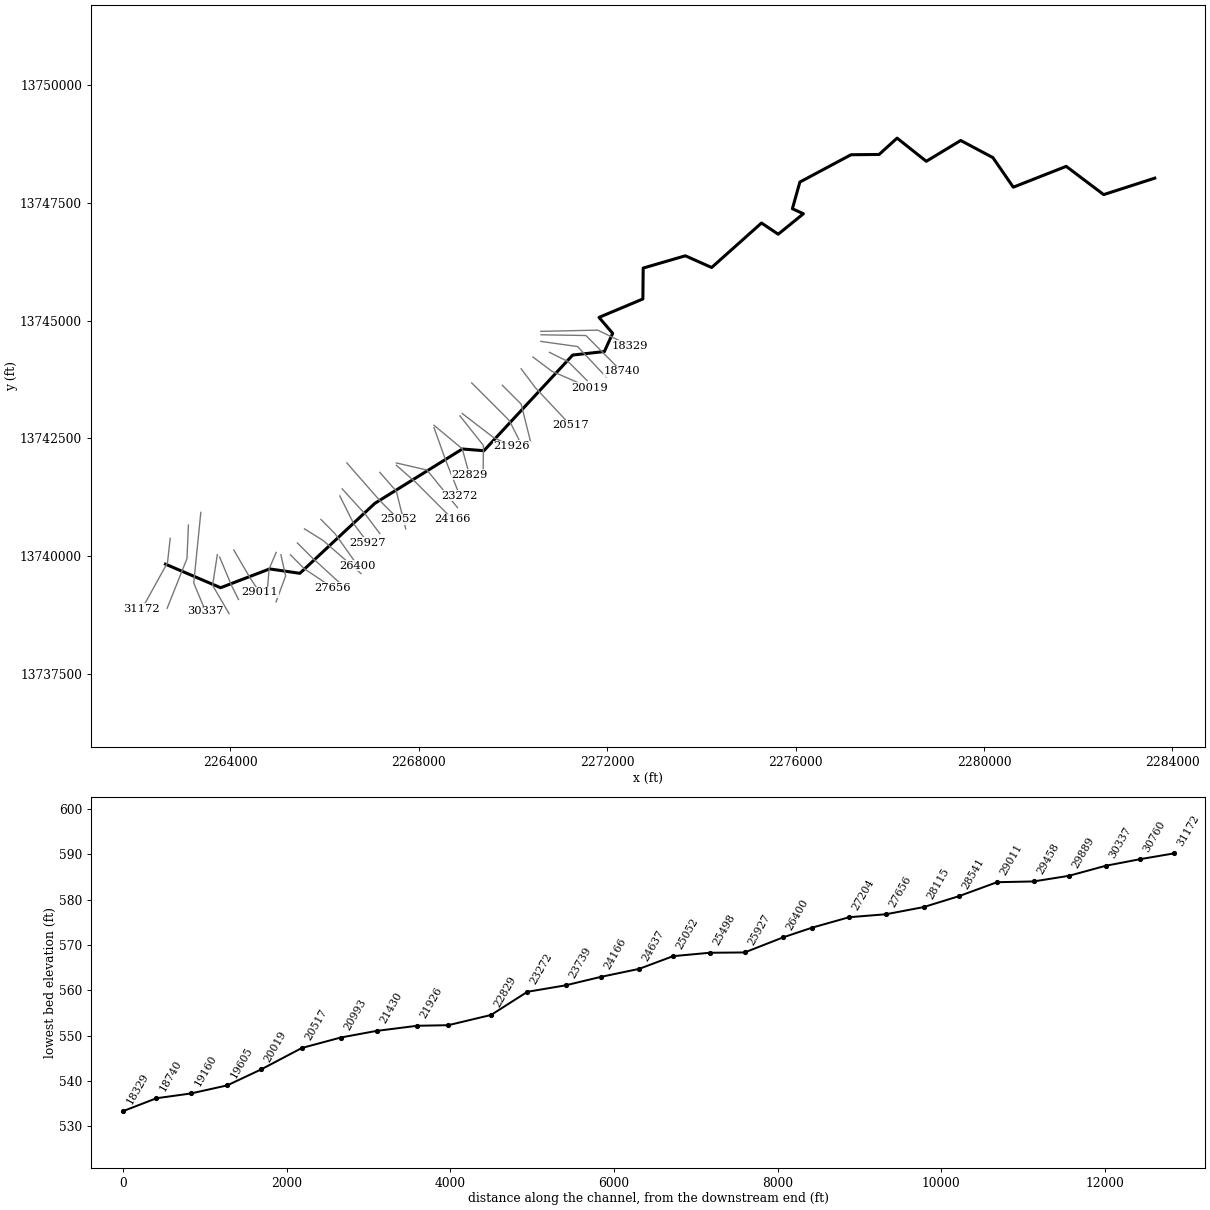
--- DEADMAN CREEK.prj (project) ---

Proj Title=DEADMAN CREEK Base Level Engineering
Current Plan=p01
Default Exp/Contr=0.3,0.1
English Units
Geom File=g01
Flow File=f01
Plan File=p01
Y Axis Title=Elevation
X Axis Title(PF)=Main Channel Distance
X Axis Title(XS)=Station
BEGIN DESCRIPTION:
DEADMAN CREEK
END DESCRIPTION:
DSS Export Rating Curves= 0
DSS Export Rating Curve Sorted= 0
DSS Export Volume Flow Curves= 0
DXF OffsetX= 0
DXF OffsetY= 0
DXF ScaleX= 1
DXF ScaleY= 10

--- DEADMAN CREEK.p01 (plan) ---

Plan Title=Multiple Run
Program Version=4.10
Short Identifier=Multiple
Geom File=g01
Flow File=f01
Subcritical Flow
K Sum by GR= 0
Std Step Tol= 0.01
Critical Tol= 0.01
Num of Std Step Trials= 20
Max Error Tol= 0.3
Flow Tol Ratio= 0.001
Split Flow NTrial= 30
Split Flow Tol= 0.02
Split Flow Ratio= 0.02
Log Output Level= 0
Friction Slope Method= 1
Unsteady Friction Slope Method= 2
Unsteady Bridges Friction Slope Method= 1
Parabolic Critical Depth
Global Vel Dist= 1 , 1 , 1
Global Log Level= 0
CheckData=True
Encroach Param=-1 ,0,0, 0
BEGIN DESCRIPTION:
Multiple Run
END DESCRIPTION:
Computation Interval=1HOUR
Output Interval=1HOUR
Run HTab= 0
Run UNet= 0
Run PostProcess= 0
Run WQNet= 0
UNET Theta= 1
UNET Theta Warmup= 1
UNET ZTol= 0.02
UNET ZSATol= 0.05
UNET MxIter= 20
UNET MaxInSteps= 0
UNET DtIC= 0
UNET DtMin= 0
UNET MaxCRTS= 20
UNET WFStab= 2
UNET SFStab= 1
UNET WFX= 1
UNET SFX= 1
UNET DSS MLevel= 4
UNET DZMax Abort= 100
UNET Convert EG Bridges= 0
UNET Use Existing IB Tables=-1
UNET Froude Reduction=False
UNET Froude Limit= 1
UNET Froude Power= 10
UNET Time Slicing=0,0, 5
UNET Junction Losses=0
Instantaneous Interval=1HOUR
Write IC File= 0
Write IC File at Sim End=0
Echo Input=False
Echo Parameters=False
Echo Output=False
Write Detailed= 0
WQ AD Non Conservative
WQ ULTIMATE=-1
WQ Max Comp Step=1HOUR
WQ Output Interval=15MIN
WQ Output Selected Increments= 0
WQ Output face flow=0
WQ Output face velocity=0
WQ Output face area=0
WQ Output face dispersion=0
WQ Output cell volume=0
WQ Output cell surface area=0
WQ Output cell continuity=0
WQ Output cumulative cell continuity=0
WQ Output face conc=0
WQ Output face dconc_dx=0
WQ Output face courant=0
WQ Output face peclet=0
WQ Output face adv mass=0
WQ Output face disp mass=0
WQ Output cell mass=0
WQ Output cell source sink temp=0
WQ Output cell source sink nsm=0
WQ Output MaxMinRange=-1
WQ Daily Max Min Mean=-1
WQ Daily Range=0
WQ Daily Time=0
WQ Create Restart=0
WQ Fixed Restart=0
WQ System Summary=0
WQ Use Fixed Temperature=0
Sorting and Armoring Iterations= 10
XS Update Threshold= 0.02
Hydraulics Update Threshold= 0.02
Energy Slope Method= 1
Volume Change Method= 0
XS Weighting Method= 0
Number of US Weighted Cross Sections= 1
Number of DS Weighted Cross Sections= 1
Upstream XS Weight=0.25
Main XS Weight=0.5
Downstream XS Weight=0.25
Number of DS XS's Weighted with US Boundary= 1
Upstream Boundary Weight= 1
Weight of XSs Associated with US Boundary= 0
Number of US XS's Weighted with DS Boundary= 1
Downstream Boundary Weight= 0.5
Weight of XSs Associated with DS Boundary= 0.5
Sediment Output Level= 4
Mass or Volume Output= 0
Output Increment Type= 1
Profile and TS Output Increment= 10
XS Output Flag= 0
XS Output Increment= 10
Disregard all LS=0
Disregard all Conn=0
Disregard all Breaches=0
Disregard all Pumps=0

--- DEADMAN CREEK.f01 (steady flow) ---

Flow Title=Multiple
Program Version=4.10
Number of Profiles= 7
Profile Names=10-year,25-year,50-year,1pct_min,100-year,1pct_plu,500-year
River Rch & RM=DEADMAN CREEK,Reach-1         ,31172
     200     296     374     230     458     914     679
River Rch & RM=DEADMAN CREEK,Reach-1         ,30337
     423     658     861     546    1089    2172    1721
River Rch & RM=DEADMAN CREEK,Reach-1         ,27656
    1024    1684    2289    1503    2998    5983    5097
River Rch & RM=DEADMAN CREEK,Reach-1         ,21926
    1236    2051    2806    1852    3695    7373    6352
River Rch & RM=DEADMAN CREEK,Reach-1         ,19605
    1427    2386    3280    2175    4339    8658    7528
River Rch & RM=DEADMAN CREEK,Reach-1         ,15557
    1710    2886    3991    2661    5310   10595    9316
River Rch & RM=DEADMAN CREEK,Reach-1         ,15121
    1741    2939    4068    2714    5415   10805    9511
River Rch & RM=DEADMAN CREEK,Reach-1         ,14657
    1997    3391    4709    3152    6288   12547   11114
River Rch & RM=DEADMAN CREEK,Reach-1         ,9635
    2474    4233    5908    3971    7923   15808   14123
River Rch & RM=DEADMAN CREEK,Reach-1         ,4452
    2642    4523    6317    4247    8474   16908   15114
River Rch & RM=DEADMAN CREEK,Reach-1         ,1500
    2821    4838    6763    4550    9078   18113   16214
Boundary for River Rch & Prof#=DEADMAN CREEK,Reach-1         , 1
Up Type= 0
Dn Type= 3
Dn Slope=0.0001
Boundary for River Rch & Prof#=DEADMAN CREEK,Reach-1         , 2
Up Type= 0
Dn Type= 3
Dn Slope=0.0001
Boundary for River Rch & Prof#=DEADMAN CREEK,Reach-1         , 3
Up Type= 0
Dn Type= 3
Dn Slope=0.0001
Boundary for River Rch & Prof#=DEADMAN CREEK,Reach-1         , 4
Up Type= 0
Dn Type= 3
Dn Slope=0.0001
Boundary for River Rch & Prof#=DEADMAN CREEK,Reach-1         , 5
Up Type= 0
Dn Type= 3
Dn Slope=0.0001
Boundary for River Rch & Prof#=DEADMAN CREEK,Reach-1         , 6
Up Type= 0
Dn Type= 3
Dn Slope=0.0001
Boundary for River Rch & Prof#=DEADMAN CREEK,Reach-1         , 7
Up Type= 0
Dn Type= 3
Dn Slope=0.0001
DSS Import GetInterval= 0
DSS Import GetPeak= 0
DSS Import FillOption= 0

--- DEADMAN CREEK.g01 (geometry) ---

Geom Title=Existing Conditions
Program Version=4.10

River Reach=DEADMAN CREEK   ,Reach-1
Reach XY= 30
        2262625.       13739825.      2263795.18     13739324.72
      2264835.69     13739724.24      2265477.42     13739630.54
      2267068.94     13741116.86      2268926.47     13742271.46
      2269384.42     13742234.95      2271268.79      13744267.2
      2271941.79     13744341.39      2272117.21     13744728.43
      2271827.92     13745067.03      2272758.79     13745458.29
      2272765.17     13746114.54       2273659.8     13746375.49
      2274218.89     13746126.79      2275276.74     13747071.69
      2275631.68     13746833.96      2276166.13     13747268.49
      2275932.22     13747374.65      2276091.43     13747941.77
      2277176.39     13748521.97      2277773.58     13748528.04
       2278154.9      13748875.1        2278775.     13748382.56
      2279504.96     13748824.95      2280188.32     13748461.63
      2280621.59     13747832.82      2281745.16     13748275.47
      2282540.41     13747675.01        2283625.       13748025.

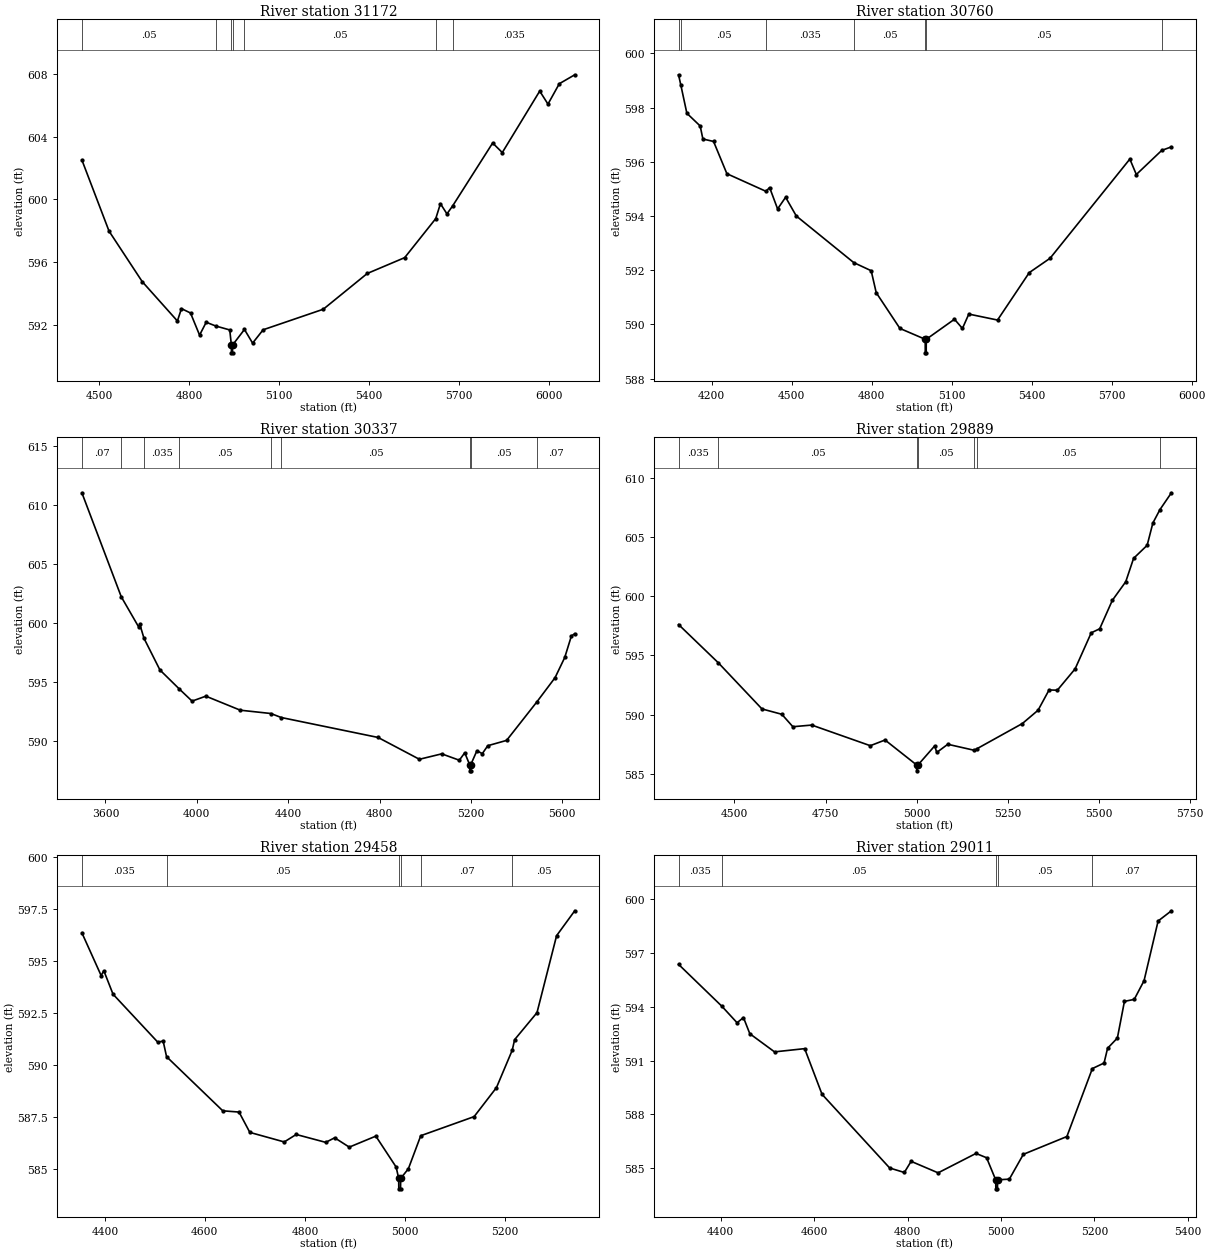
Type RM Length L Ch R = 1 ,31172   ,412,412,412
BEGIN DESCRIPTION:
DEADMAN CREEK 51.0
END DESCRIPTION:
XS GIS Cut Line= 3
        2262725.     13740375.01      2262668.05     13739857.38
      2262125.02     13738875.03
#Sta/Elev= 30
  4442.6  602.52  4533.2  597.98  4643.8  594.76  4761.1  592.25  4774.6  593.04
  4804.8  592.76    4835  591.35  4857.1  592.17  4889.1  591.93  4935.6  591.68
    4941  590.72  4941.3  590.22  4944.8  590.22    4945  590.72  4984.6  591.71
  5011.8  590.84  5046.9  591.69  5247.4     593    5394  595.28  5518.8  596.29
  5622.4  598.78    5638  599.73  5659.7  599.08  5678.4  599.58  5812.1   603.6
  5844.2  602.99    5969  606.91  5996.5  606.08  6034.3  607.38  6085.8  607.95
#Mann= 7 ,-1 , 0
  4442.6     .05       0  4889.1     .07       0    4941     .05       0
    4945     .07       0  4984.6     .05       0  5622.4     .07       0
  5678.4    .035       0
Bank Sta=4941,4945
XS Rating Curve= 0 ,0
Exp/Cntr=0.3,0.1

Type RM Length L Ch R = 1 ,30760   ,423,423,423
BEGIN DESCRIPTION:
X18768
END DESCRIPTION:
XS GIS Cut Line= 3
      2263111.81     13740656.17      2263080.94     13739942.27
      2262660.55     13738889.36
#Sta/Elev= 30
  4075.8  599.21  4084.4  598.83    4107  597.79    4157  597.32  4167.1  596.84
  4207.1  596.75  4257.1  595.56  4403.6  594.91  4417.3  595.05  4447.3  594.26
  4477.3  594.69  4517.4     594  4732.8  592.28  4798.2  591.98  4817.1  591.17
    4906  589.85  5000.8  589.45    5001  588.95  5004.5  588.95  5004.8  589.45
  5110.5  590.19  5140.4  589.85  5164.3  590.38    5272  590.16    5391  591.91
  5469.1  592.44  5768.2   596.1  5792.5  595.53  5887.8  596.42  5924.1  596.55
#Mann= 7 ,-1 , 0
  4075.8     .07       0  4084.4     .05       0  4403.6    .035       0
  4732.8     .05       0  5000.8     .05       0  5004.8     .05       0
  5887.8     .07       0
Bank Sta=5000.8,5004.8
XS Rating Curve= 0 ,0
Exp/Cntr=0.3,0.1

Type RM Length L Ch R = 1 ,30337   ,448,448,448
BEGIN DESCRIPTION:
DEADMAN CREEK 50.0
END DESCRIPTION:
XS GIS Cut Line= 3
        2263375.     13740925.04        2263225.       13739425.
      2263474.99     13738825.02
#Sta/Elev= 30
    3497  611.05  3669.5  602.23  3745.8  599.67  3750.8  599.89  3768.8  598.72
  3838.7  596.03  3923.4  594.42  3979.4  593.39  4039.7  593.81  4190.5  592.62
  4324.2  592.34  4369.8     592  4793.5  590.31  4974.4  588.46  5072.2  588.92
  5149.1  588.38    5173  589.01  5194.8  587.98  5195.1  587.48  5198.6  587.48
  5198.8  587.98  5226.1  589.18  5249.9  588.94  5273.7  589.61  5356.1  590.06
  5488.9  593.33  5568.4  595.38  5610.7  597.09  5639.9  598.92  5654.5   599.1
#Mann= 9 ,-1 , 0
    3497     .07       0  3669.5     .05       0  3768.8    .035       0
  3923.4     .05       0  4324.2    .035       0  4369.8     .05       0
  5194.8     .05       0  5198.8     .05       0  5488.9     .07       0
Bank Sta=5194.8,5198.8
XS Rating Curve= 0 ,0
Exp/Cntr=0.3,0.1

Type RM Length L Ch R = 1 ,29889   ,431,431,431
BEGIN DESCRIPTION:
DEADMAN CREEK 49.0
END DESCRIPTION:
XS GIS Cut Line= 3
        2263725.     13740025.02        2263625.       13739375.
        2263975.     13738774.99
#Sta/Elev= 30
  4346.7  597.61  4455.9  594.38  4575.6  590.49    4630  590.04  4660.4  588.99
  4712.2  589.13  4872.8  587.39  4913.3  587.87  4999.8  585.77  5000.1  585.27
  5003.8  585.77  5049.4  587.37  5055.2  586.82  5085.4  587.51  5158.5     587
  5165.2  587.13  5290.1  589.26  5333.1  590.38  5363.3  592.09    5386  592.07
  5434.8  593.87    5479  596.91  5502.2  597.25  5536.9  599.65  5573.7  601.22
  5595.2  603.19  5632.4  604.29  5648.1  606.17  5667.5   607.3    5699  608.72
#Mann= 7 ,-1 , 0
  4346.7    .035       0  4455.9     .05       0  4999.8     .05       0
  5003.8     .05       0  5158.5     .07       0  5165.2     .05       0
  5667.5     .07       0
Bank Sta=4999.8,5003.8
XS Rating Curve= 0 ,0
Exp/Cntr=0.3,0.1

Type RM Length L Ch R = 1 ,29458   ,447,447,447
BEGIN DESCRIPTION:
DEADMAN CREEK 48.0
END DESCRIPTION:
XS GIS Cut Line= 3
        2263775.       13739975.        2264025.       13739375.
        2264175.     13739075.01
#Sta/Elev= 30
  4354.1  596.37  4392.6  594.31    4398  594.54  4416.4  593.41  4505.8   591.1
  4516.6  591.15  4523.4   590.4  4635.8  587.79  4668.3  587.73  4689.9  586.75
  4758.7  586.29  4782.6  586.65  4841.6  586.27  4859.5  586.49  4888.7  586.04
  4941.8  586.57  4982.4  585.08  4987.5  584.53  4987.7  584.03  4991.2  584.03
  4991.5  584.53  5006.9     585  5031.6  586.59  5138.3  587.51    5183  588.91
  5214.5  590.71  5219.3  591.22    5264  592.52  5303.2  596.23  5339.5  597.43
#Mann= 6 ,-1 , 0
  4354.1    .035       0  4523.4     .05       0  4987.5     .05       0
  4991.5     .05       0  5031.6     .07       0  5214.5     .05       0
Bank Sta=4987.5,4991.5
XS Rating Curve= 0 ,0
Exp/Cntr=0.3,0.1

Type RM Length L Ch R = 1 ,29011   ,470,470,470
BEGIN DESCRIPTION:
DEADMAN CREEK 47.0
END DESCRIPTION:
XS GIS Cut Line= 3
      2264074.98     13740125.04        2264425.       13739525.
      2264624.99     13739225.02
#Sta/Elev= 30
  4309.7  596.35  4402.4  594.02    4435   593.1  4448.7  593.39  4462.3  592.49
  4515.2  591.48  4579.7  591.66  4616.9  589.12  4761.7  585.02  4793.1  584.77
  4807.6  585.39  4865.4  584.75  4946.5  585.83  4969.2  585.59  4988.7  584.36
    4989  583.86  4992.5  583.86  4992.7  584.36  5017.9   584.4  5047.9  585.78
  5141.1  586.77  5195.6  590.55  5220.7  590.86  5228.2  591.68  5249.2  592.25
  5264.3  594.29  5285.3   594.4  5306.3  595.44  5336.4  598.76  5364.9  599.33
#Mann= 5 ,-1 , 0
  4309.7    .035       0  4402.4     .05       0  4988.7     .05       0
  4992.7     .05       0  5195.6     .07       0
Bank Sta=4988.7,4992.7
XS Rating Curve= 0 ,0
Exp/Cntr=0.3,0.1

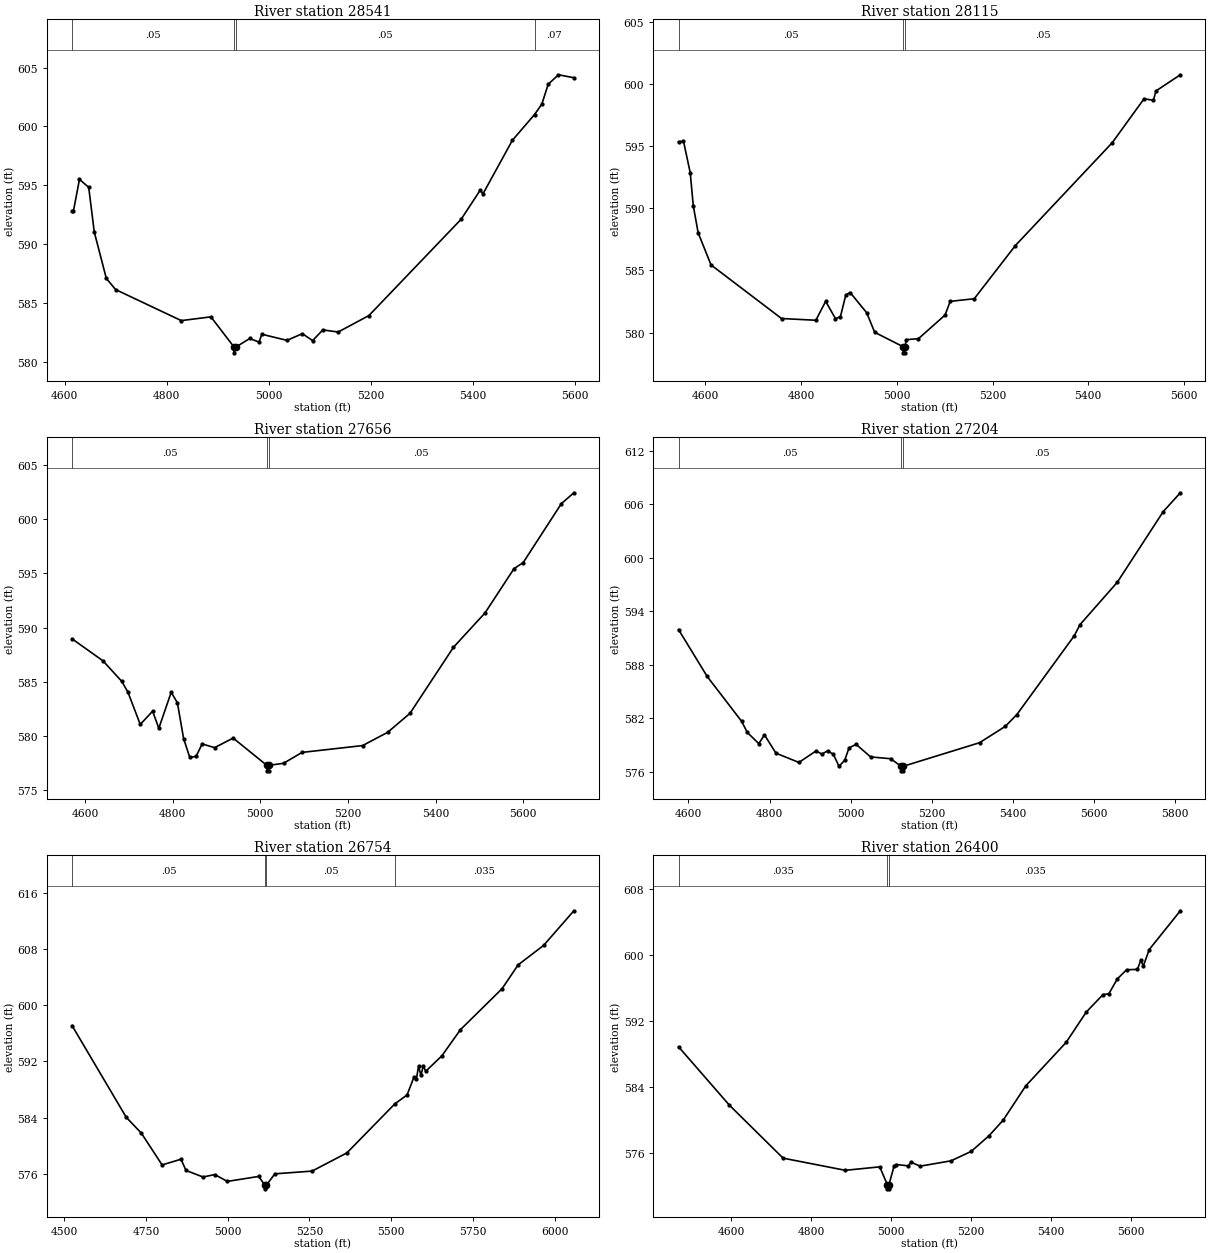
Type RM Length L Ch R = 1 ,28541   ,426,426,426
BEGIN DESCRIPTION:
DEADMAN CREEK 46.0
END DESCRIPTION:
XS GIS Cut Line= 3
      2264974.98     13740074.96        2264825.       13739725.
        2264775.     13739125.02
#Sta/Elev= 30
  4614.8  592.81  4617.5  592.81  4629.3   595.5  4647.4  594.82  4658.3  591.02
  4681.8  587.09    4700  586.13  4828.7  583.49  4886.7  583.81  4931.9  581.25
  4932.1  580.75  4935.9  581.25  4962.9  581.97    4981  581.66  4986.5  582.33
  5035.7  581.81  5065.8  582.38  5085.9  581.79  5105.9   582.7    5136  582.52
  5196.2  583.92  5376.9  592.11  5414.5   594.6  5419.5  594.26  5477.2  598.82
  5520.6  601.01  5534.9   601.9  5547.4  603.59  5567.5  604.39  5597.6  604.14
#Mann= 4 ,-1 , 0
  4614.8     .05       0  4931.9     .05       0  4935.9     .05       0
  5520.6     .07       0
Bank Sta=4931.9,4935.9
XS Rating Curve= 0 ,0
Exp/Cntr=0.3,0.1

Type RM Length L Ch R = 1 ,28115   ,459,459,459
BEGIN DESCRIPTION:
DEADMAN CREEK 45.0
END DESCRIPTION:
XS GIS Cut Line= 3
      2265074.99     13740025.04        2265175.       13739575.
      2264971.77      13739023.9
#Sta/Elev= 30
  4543.9  595.34  4554.2   595.4  4568.3  592.86  4574.7   590.2  4584.9  588.02
  4611.8  585.44  4759.1  581.13  4830.8  580.99  4851.3  582.51  4871.7  581.13
    4882  581.26  4893.5  583.04  4902.5  583.22  4937.1  581.59  4953.7  580.02
  5012.8  578.87  5013.1  578.37  5016.6  578.37  5016.8  578.87  5020.1  579.43
  5045.2  579.51  5100.8  581.41  5111.5  582.51  5161.7  582.72  5247.7     587
  5450.1  595.27  5516.5   598.8  5536.1  598.68  5541.4  599.43  5592.3  600.73
#Mann= 3 ,-1 , 0
  4543.9     .05       0  5012.8     .05       0  5016.8     .05       0
Bank Sta=5012.8,5016.8
XS Rating Curve= 0 ,0
Exp/Cntr=0.3,0.1

Type RM Length L Ch R = 1 ,27656   ,452,452,452
BEGIN DESCRIPTION:
DEADMAN CREEK 44.0
END DESCRIPTION:
XS GIS Cut Line= 3
      2265274.98     13740025.02        2265575.       13739725.
      2266174.99       13739325.
#Sta/Elev= 30
  4570.2  588.96  4640.9  586.93  4683.4  585.05  4697.5  584.07  4725.8  581.07
  4754.1  582.29  4768.2  580.71  4796.5  584.04  4810.7  583.05  4824.8  579.76
  4838.9  578.03  4853.1  578.12  4867.2  579.27  4895.5  578.93  4937.9  579.81
    5015  577.29  5015.3  576.79  5018.8  576.79    5019  577.29  5053.1  577.49
  5095.2  578.49  5233.4  579.12  5290.5  580.34  5341.5  582.09  5440.7  588.18
  5512.8  591.35  5578.9  595.43  5599.9  595.99  5687.1  601.43  5715.6  602.43
#Mann= 3 ,-1 , 0
  4570.2     .05       0    5015     .05       0    5019     .05       0
Bank Sta=5015,5019
XS Rating Curve= 0 ,0
Exp/Cntr=0.3,0.1

Type RM Length L Ch R = 1 ,27204   ,450,450,450
BEGIN DESCRIPTION:
DEADMAN CREEK 43.0
END DESCRIPTION:
XS GIS Cut Line= 3
      2265424.99     13740275.01        2265725.       13739975.
      2266324.99     13739425.01
#Sta/Elev= 30
  4575.5  591.95  4646.2   586.7  4731.1  581.68  4745.2  580.43  4773.5  579.18
  4787.6  580.15  4815.9  578.11  4872.5  577.07  4914.9  578.36  4929.1  578.01
  4943.2  578.36  4957.4  577.99  4971.5  576.64  4985.6  577.32  4996.2   578.7
  5013.7   579.1  5049.4  577.69  5098.7  577.49  5125.1  576.63  5125.4  576.13
  5128.9  576.13  5129.1  576.63  5318.3  579.28  5381.8  581.11  5410.1  582.42
    5552  591.26  5566.1   592.5    5658  597.24  5771.5  605.16  5813.7  607.27
#Mann= 3 ,-1 , 0
  4575.5     .05       0  5125.1     .05       0  5129.1     .05       0
Bank Sta=5125.1,5129.1
XS Rating Curve= 0 ,0
Exp/Cntr=0.3,0.1

Type RM Length L Ch R = 1 ,26754   ,354,354,354
BEGIN DESCRIPTION:
DEADMAN CREEK 42.0
END DESCRIPTION:
XS GIS Cut Line= 3
      2265574.96     13740575.02        2265975.       13740325.
      2266775.03     13739624.97
#Sta/Elev= 30
  4524.2  597.11  4689.9  584.04  4735.9  581.79  4799.6  577.25  4857.4  578.06
  4872.7  576.46  4924.6  575.53  4960.6  575.87  4999.3   574.9  5095.1  575.61
    5114  574.34  5114.3  573.84  5118.1  574.34  5144.5  575.98  5258.4  576.37
  5364.7  578.96  5511.6  585.96  5548.8  587.22  5569.7  589.74  5577.3  589.45
  5583.9  591.31  5591.5     590  5598.2   591.4  5605.8  590.59  5655.1  592.79
  5712.1  596.53  5839.2  602.36  5888.6  605.77  5966.4  608.54    6059  613.48
#Mann= 4 ,-1 , 0
  4524.2     .05       0    5114     .05       0  5118.1     .05       0
  5511.6    .035       0
Bank Sta=5114,5118.1
XS Rating Curve= 0 ,0
Exp/Cntr=0.3,0.1

Type RM Length L Ch R = 1 ,26400   ,473,473,473
BEGIN DESCRIPTION:
DEADMAN CREEK 41.0
END DESCRIPTION:
XS GIS Cut Line= 3
      2265925.04     13740774.96      2266222.02     13740474.79
      2266704.39     13739795.62
#Sta/Elev= 30
  4468.9  588.88  4596.1  581.82  4730.5  575.41  4886.1  573.94  4972.3  574.36
  4991.2   572.2  4991.4   571.7    4995   571.7  4995.3   572.2    5008  574.44
  5014.1  574.64  5043.7  574.48  5050.4  574.92  5073.2  574.44  5150.7  575.09
  5201.1  576.23  5245.4  578.11  5281.1  580.01  5337.6  584.16  5438.5  589.41
  5488.9  593.08  5530.7  595.19  5545.5   595.3  5566.4  597.08  5589.8   598.2
  5616.9  598.24  5625.5  599.36  5631.6  598.64  5646.4  600.64  5724.2  605.33
#Mann= 3 ,-1 , 0
  4468.9    .035       0  4991.2    .035       0  4995.3    .035       0
Bank Sta=4991.2,4995.3
XS Rating Curve= 0 ,0
Exp/Cntr=0.3,0.1

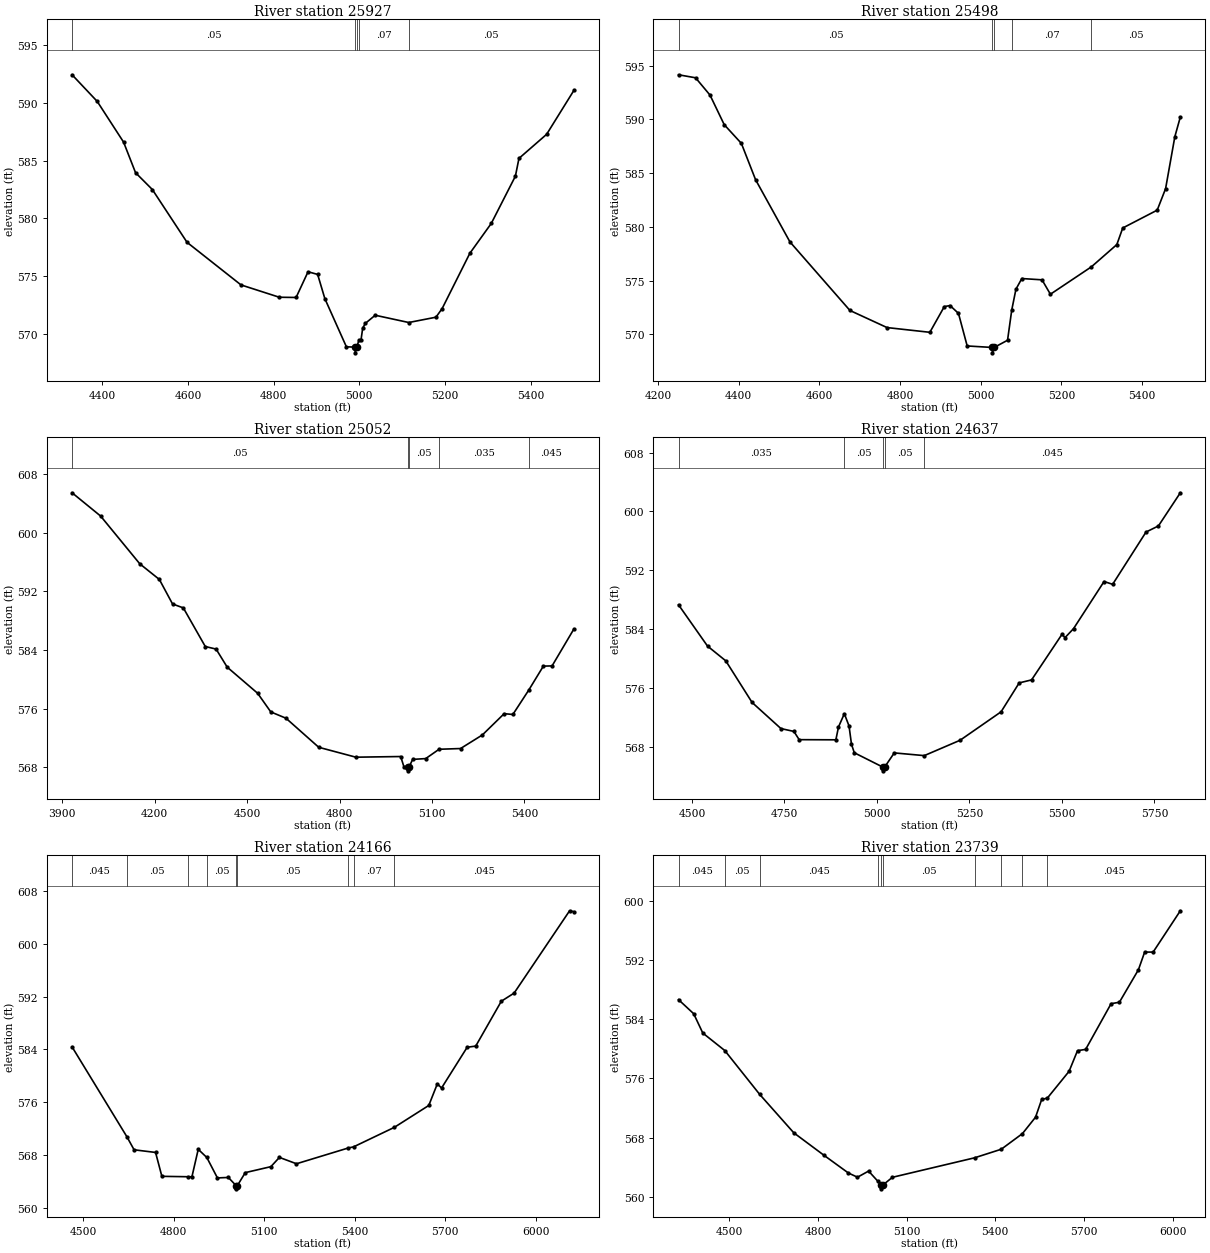
Type RM Length L Ch R = 1 ,25927   ,429,429,429
BEGIN DESCRIPTION:
DEADMAN CREEK 40.0
END DESCRIPTION:
XS GIS Cut Line= 3
        2266325.     13741275.01        2266625.       13740675.
      2266924.98     13740275.02
#Sta/Elev= 30
  4329.7  592.46  4388.4  590.15  4449.9  586.62  4477.8  583.97    4517  582.51
    4598  577.93  4723.8  574.24  4813.3  573.17  4852.4  573.15  4880.3  575.38
  4902.7  575.15  4919.5  573.05  4969.8  568.87    4990  568.85  4990.3  568.35
  4994.2  568.85  4998.7  569.42  5003.7  569.42  5007.8  570.49  5014.1  570.91
    5037  571.61  5115.3  570.98  5178.7  571.44  5193.2  572.19  5257.8  576.98
  5307.8  579.57  5364.1  583.67  5372.4  585.21    5437   587.3  5500.5   591.1
#Mann= 5 ,-1 , 0
  4329.7     .05       0    4990     .05       0  4994.2     .05       0
  4998.7     .07       0  5115.3     .05       0
Bank Sta=4990,4994.2
XS Rating Curve= 0 ,0
Exp/Cntr=0.3,0.1

Type RM Length L Ch R = 1 ,25498   ,446,446,446
BEGIN DESCRIPTION:
DEADMAN CREEK 39.0
END DESCRIPTION:
XS GIS Cut Line= 3
      2266375.02     13741424.98        2266875.       13740875.
      2267175.01     13740474.98
#Sta/Elev= 30
  4251.2  594.14  4293.4  593.86  4329.2  592.25  4364.4   589.5  4406.9  587.76
  4442.1  584.38  4527.2   578.6  4675.9  572.22  4767.8  570.63  4873.9  570.19
  4909.7  572.58  4923.9  572.68  4944.8  571.95  4966.4  568.92  5028.8  568.78
  5029.1  568.28  5033.1  568.78  5066.4  569.45  5076.8  572.26  5087.2   574.2
  5101.8  575.19  5151.8  575.07  5172.6  573.73  5274.2  576.28  5337.2  578.35
  5351.8  579.89  5437.2  581.55    5458  583.55  5480.9  588.38  5494.5  590.21
#Mann= 5 ,-1 , 0
  4251.2     .05       0  5028.8     .05       0  5033.1     .05       0
  5076.8     .07       0  5274.2     .05       0
Bank Sta=5028.8,5033.1
XS Rating Curve= 0 ,0
Exp/Cntr=0.3,0.1

Type RM Length L Ch R = 1 ,25052   ,415,415,415
BEGIN DESCRIPTION:
DEADMAN CREEK 38.0
END DESCRIPTION:
XS GIS Cut Line= 3
      2266474.98     13741975.03        2267175.       13741175.
      2267574.98     13740775.02
#Sta/Elev= 30
  3931.9  605.42  4024.5  602.25  4151.7  595.74  4215.2  593.61    4258  590.27
  4293.1  589.73  4364.3  584.47  4399.4  584.12  4435.4  581.66  4534.2   578.1
  4576.9  575.56  4626.2   574.7  4732.5  570.74  4853.1  569.39  4998.5  569.48
  5009.1  568.08    5021  568.03  5021.3  567.53  5025.4  568.03  5037.4  569.09
  5079.8   569.2  5123.1  570.47  5192.9  570.57  5263.6  572.42  5334.4  575.32
  5362.6  575.21    5414  578.52  5461.6   581.8  5489.9  581.83  5560.6  586.85
#Mann= 5 ,-1 , 0
  3931.9     .05       0    5021     .05       0  5025.4     .05       0
  5123.1    .035       0    5414    .045       0
Bank Sta=5021,5025.4
XS Rating Curve= 0 ,0
Exp/Cntr=0.3,0.1

Type RM Length L Ch R = 1 ,24637   ,471,471,471
BEGIN DESCRIPTION:
DEADMAN CREEK 37.0
END DESCRIPTION:
XS GIS Cut Line= 3
        2267175.       13741775.        2267525.       13741375.
      2267724.99     13740575.03
#Sta/Elev= 30
  4463.9   587.3  4542.2  581.69  4591.6  579.68  4662.7  574.02  4740.6  570.47
  4775.7  570.08  4789.9  568.96  4889.1  568.94  4896.2  570.69    4912  572.49
  4924.7  570.82  4931.3  568.34  4938.9  567.18  5016.4  565.22  5016.7  564.72
  5020.8  565.22  5046.9  567.16    5128  566.79  5224.8  568.88  5335.6  572.75
  5384.5  576.68    5418  577.09  5500.5  583.31  5508.2  582.83  5531.4  584.06
  5613.9  590.47  5637.1  590.09  5727.3   597.2  5760.8  598.03    5820  602.54
#Mann= 5 ,-1 , 0
  4463.9    .035       0    4912     .05       0  5016.4     .05       0
  5020.8     .05       0    5128    .045       0
Bank Sta=5016.4,5020.8
XS Rating Curve= 0 ,0
Exp/Cntr=0.3,0.1

Type RM Length L Ch R = 1 ,24166   ,427,427,427
BEGIN DESCRIPTION:
DEADMAN CREEK 36.0
END DESCRIPTION:
XS GIS Cut Line= 3
      2267524.97     13741925.03        2267925.       13741575.
      2268724.99     13740775.01
#Sta/Elev= 30
  4463.4  584.39  4645.1  570.81  4668.9  568.84  4740.1  568.44    4761  564.83
  4846.4  564.77  4860.6  564.76  4881.5  568.91  4909.9  567.68  4945.1  564.59
  4981.2  564.66  5006.8  563.44  5007.1  562.94  5011.3  563.44  5037.4  565.39
  5122.2  566.29  5150.5  567.69  5207.1  566.73  5379.2  569.12  5396.1  569.28
  5531.3  572.23  5645.5  575.54  5673.8   578.8  5687.9  578.18  5772.8  584.34
  5801.1  584.51  5885.9  591.29  5928.3  592.52  6112.2  604.96  6126.3  604.82
#Mann= 9 ,-1 , 0
  4463.4    .045       0  4645.1     .05       0  4846.4    .045       0
  4909.9     .05       0  5006.8     .05       0  5011.3     .05       0
  5379.2    .045       0  5396.1     .07       0  5531.3    .045       0
Bank Sta=5006.8,5011.3
XS Rating Curve= 0 ,0
Exp/Cntr=0.3,0.1

Type RM Length L Ch R = 1 ,23739   ,467,467,467
BEGIN DESCRIPTION:
DEADMAN CREEK 35.0
END DESCRIPTION:
XS GIS Cut Line= 3
        2267525.       13741975.        2268175.       13741825.
      2268825.02     13741024.97
#Sta/Elev= 30
  4328.5  586.65  4379.8  584.75  4410.6  582.14  4484.9  579.78  4602.7  573.87
  4718.5  568.66  4821.1  565.61  4903.2  563.23    4934  562.66  4971.6  563.49
  5002.4  562.14  5014.8  561.59  5015.2  561.09  5019.4  561.59  5052.3  562.65
    5330  565.28  5420.5  566.44  5492.1  568.55  5536.5  570.77  5557.3  573.17
  5576.4  573.35    5650  576.97  5678.5  579.76    5706  579.93  5792.2  586.11
  5820.2   586.3  5884.6  590.69  5905.7  593.08  5934.4  593.08  6026.4  598.66
#Mann= 10 ,-1 , 0
  4328.5    .045       0  4484.9     .05       0  4602.7    .045       0
  5002.4     .05       0  5014.8    .045       0  5019.4     .05       0
    5330    .035       0  5420.5    .045       0  5492.1    .035       0
  5576.4    .045       0
Bank Sta=5014.8,5019.4
XS Rating Curve= 0 ,0
Exp/Cntr=0.3,0.1

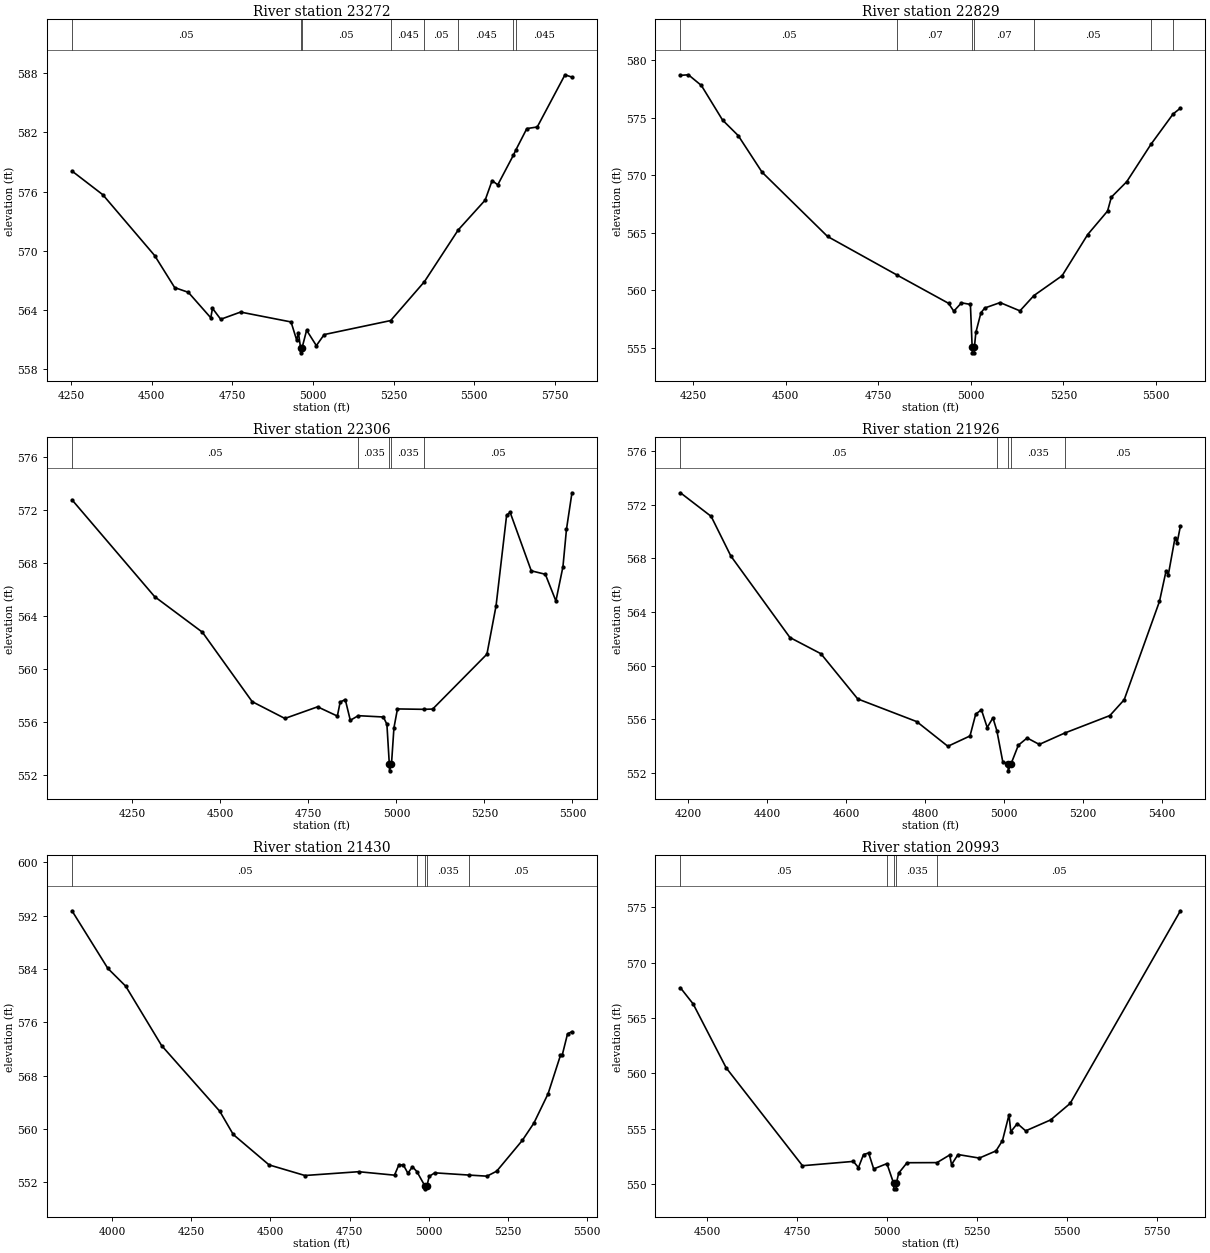
Type RM Length L Ch R = 1 ,23272   ,443,443,443
BEGIN DESCRIPTION:
DEADMAN CREEK 34.0
END DESCRIPTION:
XS GIS Cut Line= 3
        2268325.     13742725.01        2268575.       13742025.
      2268875.01     13741274.99
#Sta/Elev= 30
  4252.4  578.08    4348  575.68  4508.8  569.52    4571  566.27  4613.4  565.79
    4683  563.21  4688.3  564.17  4713.8  563.06  4775.4  563.79    4932  562.79
  4949.5  560.95  4954.8  561.71  4961.6  560.16  4961.9  559.66  4966.2  560.16
  4980.3  561.95  5010.5  560.39  5034.8  561.51  5241.1  562.93  5345.8  566.87
  5450.6  572.11  5534.2  575.13  5555.8  577.11  5573.3  576.68  5621.4  579.66
    5630  580.25  5663.5  582.38  5695.8  582.54  5781.9  587.83  5803.5  587.59
#Mann= 8 ,-1 , 0
  4252.4     .05       0  4961.6     .05       0  4966.2     .05       0
  5241.1    .045       0  5345.8     .05       0  5450.6    .045       0
  5621.4    .035       0    5630    .045       0
Bank Sta=4961.6,4966.2
XS Rating Curve= 0 ,0
Exp/Cntr=0.3,0.1

Type RM Length L Ch R = 1 ,22829   ,523,523,523
BEGIN DESCRIPTION:
DEADMAN CREEK 33.0
END DESCRIPTION:
XS GIS Cut Line= 3
      2268325.02     13742774.99        2268925.       13742275.
        2269075.     13741724.99
#Sta/Elev= 30
  4215.1  578.68  4236.6  578.73  4271.7   577.8    4329  574.79  4371.3  573.44
  4435.7  570.26  4612.7  564.67  4799.6  561.33  4939.5  558.86  4953.8  558.17
  4974.6   558.9  4998.7  558.76  5003.4  555.05  5003.9  554.55    5009  554.55
  5009.5  555.05  5013.4  556.32  5027.2  558.04  5037.6  558.45    5079  558.92
  5132.6   558.2  5170.3  559.53  5246.6  561.26  5315.7  564.84  5369.3  566.88
  5379.6  568.09  5421.1  569.43  5486.7  572.69  5546.4  575.32  5566.2  575.83
#Mann= 7 ,-1 , 0
  4215.1     .05       0  4799.6     .07       0  5003.4     .05       0
  5009.5     .07       0  5170.3     .05       0  5486.7     .07       0
  5546.4    .035       0
Bank Sta=5003.4,5009.5
XS Rating Curve= 0 ,0
Exp/Cntr=0.3,0.1

Type RM Length L Ch R = 1 ,22306   ,380,380,380
BEGIN DESCRIPTION:
DEADMAN CREEK 32.0
END DESCRIPTION:
XS GIS Cut Line= 3
      2268875.02     13742974.98      2269374.68     13742346.32
      2269366.97     13741729.41
#Sta/Elev= 30
  4078.6  572.78  4313.3  565.46    4449  562.77  4590.4  557.52  4683.3  556.25
  4776.2  557.13  4832.3  556.43  4840.3  557.49  4854.7  557.68  4869.1  556.11
  4891.6  556.46    4963  556.36    4973  555.81  4979.9  552.79  4980.4  552.29
    4986  552.79    4993  555.54    5003  556.97  5077.2  556.94    5103  556.96
  5257.1  561.11    5283  564.76    5313  571.61    5323  571.83    5383  567.41
    5423  567.15    5453  565.13    5473  567.72    5483  570.55  5498.6  573.31
#Mann= 5 ,-1 , 0
  4078.6     .05       0  4891.6    .035       0  4979.9    .035       0
    4986    .035       0  5077.2     .05       0
Bank Sta=4979.9,4986
XS Rating Curve= 0 ,0
Exp/Cntr=0.3,0.1

Type RM Length L Ch R = 1 ,21926   ,496,496,496
BEGIN DESCRIPTION:
DEADMAN CREEK 31.0
END DESCRIPTION:
XS GIS Cut Line= 3
      2268925.02     13743024.98        2269575.       13742525.
      2269974.96     13742325.02
#Sta/Elev= 30
    4180  572.89  4257.9  571.13  4307.7  568.18  4457.5   562.1  4536.1  560.89
  4629.4  557.52  4778.9  555.83  4857.8  553.99  4913.9  554.76  4928.4  556.39
  4942.9  556.71  4957.5  555.39    4972  556.11    4982  555.15  4996.9  552.85
  5010.3  552.66  5010.8  552.16  5017.7  552.66  5036.4  554.07  5058.7  554.61
  5089.5  554.13  5154.2  554.98  5268.4  556.28  5304.7  557.46  5394.1  564.79
  5410.9  567.07  5416.5  566.77  5433.3   569.5  5438.9  569.17  5447.2  570.41
#Mann= 5 ,-1 , 0
    4180     .05       0    4982    .035       0  5010.3    .035       0
  5017.7    .035       0  5154.2     .05       0
Bank Sta=5010.3,5017.7
XS Rating Curve= 0 ,0
Exp/Cntr=0.3,0.1

Type RM Length L Ch R = 1 ,21430   ,437,437,437
BEGIN DESCRIPTION:
DEADMAN CREEK 30.0
END DESCRIPTION:
XS GIS Cut Line= 3
      2269124.97     13743675.03        2269925.       13742875.
      2270124.99     13742475.02
#Sta/Elev= 30
  3873.4  592.73  3986.6  584.09  4043.1  581.42  4156.3  572.52  4340.1  562.66
  4382.6  559.18  4495.7  554.62  4608.8  553.03  4778.5   553.6  4891.7  553.08
  4905.8  554.66    4920  554.58  4934.1  553.36  4948.2  554.35  4962.3  553.62
  4986.9  551.53  4987.4  551.03  4994.4  551.53  5001.3   552.9  5018.8  553.43
  5128.4  553.09  5183.7  552.93  5214.4  553.68  5295.5  558.31  5331.8  560.89
  5376.6  565.29  5415.7  571.05  5421.3  571.09    5438  574.27    5452  574.61
#Mann= 5 ,-1 , 0
  3873.4     .05       0  4962.3    .035       0  4986.9    .035       0
  4994.4    .035       0  5128.4     .05       0
Bank Sta=4986.9,4994.4
XS Rating Curve= 0 ,0
Exp/Cntr=0.3,0.1

Type RM Length L Ch R = 1 ,20993   ,476,476,476
BEGIN DESCRIPTION:
DEADMAN CREEK 29.0
END DESCRIPTION:
XS GIS Cut Line= 3
      2269774.99     13743625.01        2270175.       13743225.
        2270375.     13742425.02
#Sta/Elev= 30
  4425.8  567.74  4461.2  566.28  4553.1   560.5  4765.2  551.66  4906.6  552.05
  4920.8  551.49  4934.9  552.67  4949.1  552.81  4963.2  551.37    5000  551.85
  5018.6  550.07  5019.1  549.57  5025.7  549.57  5026.2  550.07  5032.7  550.99
  5055.9  551.93  5139.2  551.94  5174.5  552.63  5179.6  551.76  5197.7  552.67
  5256.9  552.35  5303.3     553  5321.3  553.93  5339.4  556.25  5344.5  554.73
  5362.6  555.47  5385.8  554.81  5455.3   555.8  5509.5  557.29  5816.1   574.7
#Mann= 5 ,-1 , 0
  4425.8     .05       0    5000    .035       0  5018.6     .05       0
  5026.2    .035       0  5139.2     .05       0
Bank Sta=5018.6,5026.2
XS Rating Curve= 0 ,0
Exp/Cntr=0.3,0.1

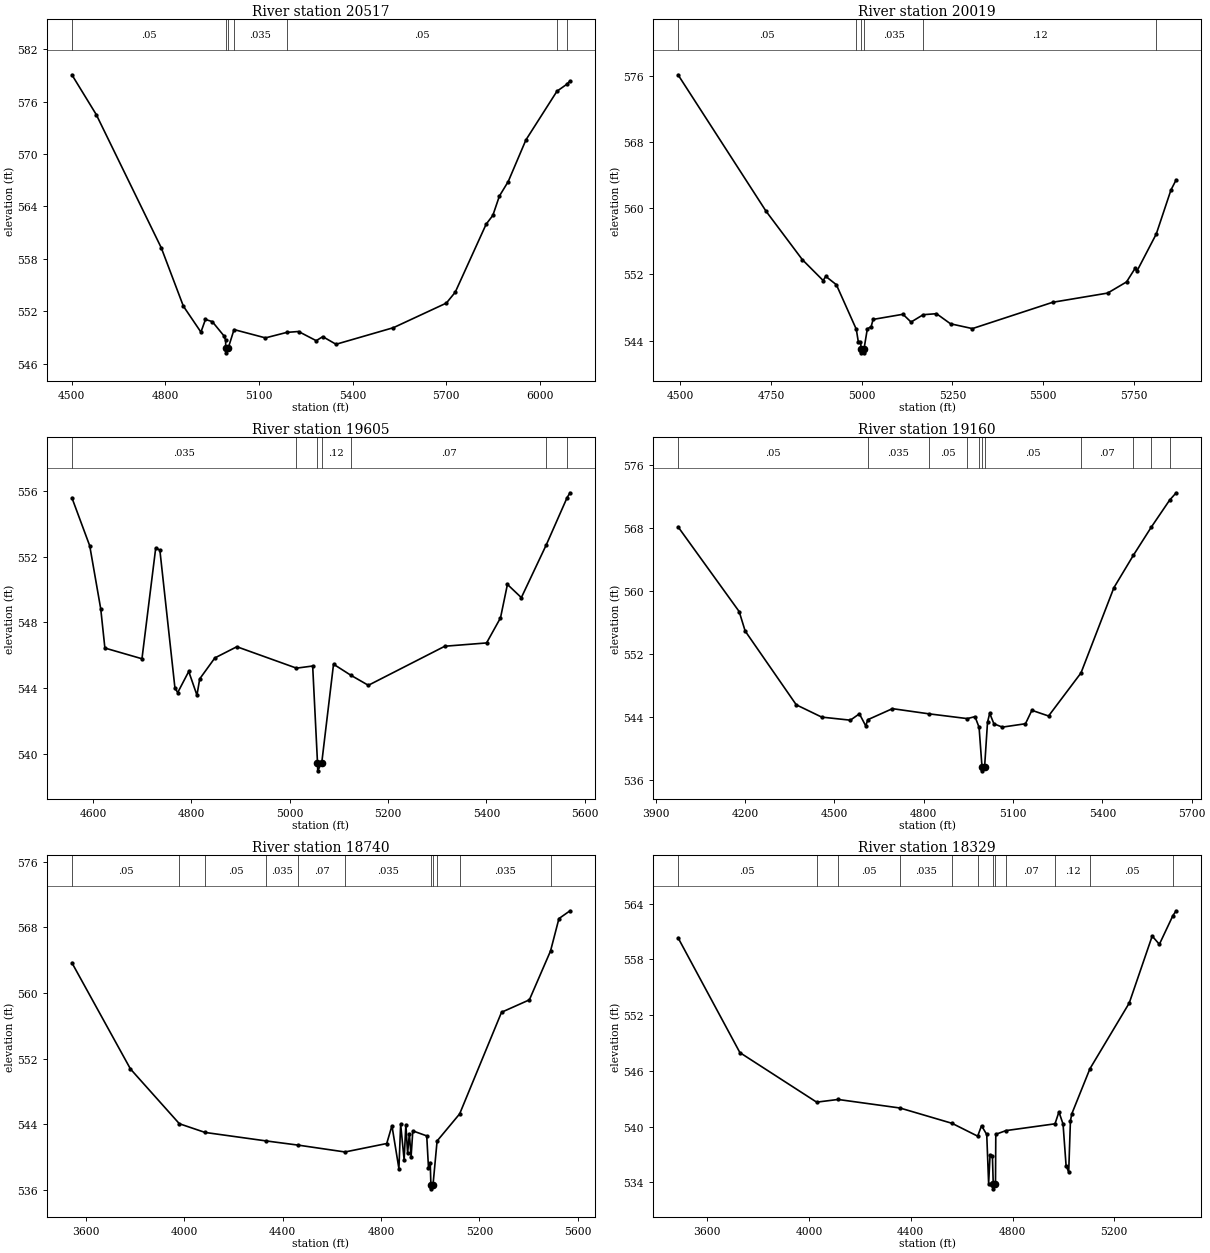
Type RM Length L Ch R = 1 ,20517   ,498,498,498
BEGIN DESCRIPTION:
DEADMAN CREEK 28.0
END DESCRIPTION:
XS GIS Cut Line= 3
      2270174.99     13743975.02        2270475.       13743575.
        2271225.       13742775.
#Sta/Elev= 30
  4500.2  579.06  4578.3  574.51  4786.7  559.27  4857.5   552.6  4913.8  549.63
  4928.3  551.08  4950.2  550.83  4986.7  549.24  4992.9  548.73  4993.3  547.76
  4993.8  547.26  5000.9  547.76  5019.9  549.92  5120.6  548.97  5189.2   549.6
  5226.6   549.7  5283.3  548.65  5304.3  549.11  5346.8  548.24  5530.9  550.14
  5700.4  552.95  5728.8  554.19  5827.9  561.97  5849.4  562.98  5870.4  565.19
  5898.7  566.85  5955.4  571.61  6054.9  577.18  6085.5  577.95  6096.8  578.34
#Mann= 7 ,-1 , 0
  4500.2     .05       0  4993.3     .05       0  5000.9     .05       0
  5019.9    .035       0  5189.2     .05       0  6054.9    .035       0
  6085.5     .05       0
Bank Sta=4993.3,5000.9
XS Rating Curve= 0 ,0
Exp/Cntr=0.3,0.1

Type RM Length L Ch R = 1 ,20019   ,414,414,414
BEGIN DESCRIPTION:
DEADMAN CREEK 27.0
END DESCRIPTION:
XS GIS Cut Line= 3
      2270424.99     13744225.01        2270825.       13743925.
      2271624.98     13743575.01
#Sta/Elev= 30
  4493.6  576.12  4736.3  559.63  4836.3  553.78  4893.6  551.26  4900.9  551.76
  4930.1  550.75    4985  545.37  4990.5  543.87  4996.3  543.87  4998.7  543.02
  4999.2  542.52  5005.9  542.52  5006.4  543.02  5015.4  545.41    5026   545.7
  5031.4  546.56  5113.7  547.18  5135.9  546.24  5169.5  547.13  5206.1  547.25
  5244.7  546.03  5305.1  545.45  5526.5  548.63  5677.8  549.74    5730  551.09
  5753.4  552.72  5758.8  552.41    5812  556.89  5852.4   562.2  5866.8  563.43
#Mann= 6 ,-1 , 0
  4493.6     .05       0    4985    .035       0  4998.7    .035       0
  5006.4    .035       0  5169.5     .12       0    5812     .07       0
Bank Sta=4998.7,5006.4
XS Rating Curve= 0 ,0
Exp/Cntr=0.3,0.1

Type RM Length L Ch R = 1 ,19605   ,445,445,445
BEGIN DESCRIPTION:
DEADMAN CREEK 26.0
END DESCRIPTION:
XS GIS Cut Line= 3
      2270775.02     13744324.99        2271175.       13744125.
      2271575.02     13743724.98
#Sta/Elev= 30
    4557  555.57  4593.3  552.65  4615.7  548.82  4624.1  546.45  4699.5   545.8
  4727.5  552.53  4735.9  552.39  4766.6  544.01  4772.2  543.75  4794.6  545.03
  4811.3  543.59  4816.9  544.58  4847.7  545.85  4892.4  546.53  5013.7  545.23
  5046.6  545.36  5056.4   539.5  5056.9     539  5065.1   539.5    5089  545.47
  5124.2   544.8  5159.8  544.19  5315.3  546.56  5400.2  546.76  5428.5  548.28
  5442.6  550.31  5470.9  549.51  5521.9  552.73    5564  555.58  5569.9  555.87
#Mann= 7 ,-1 , 0
    4557    .035       0  5013.7     .12       0  5056.4    .035       0
  5065.1     .12       0  5124.2     .07       0  5521.9     .12       0
    5564     .07       0
Bank Sta=5056.4,5065.1
XS Rating Curve= 0 ,0
Exp/Cntr=0.3,0.1

Type RM Length L Ch R = 1 ,19160   ,420,420,420
BEGIN DESCRIPTION:
X18772
END DESCRIPTION:
XS GIS Cut Line= 3
      2270591.72     13744556.87      2271372.93      13744447.5
      2271977.09     13743801.67
#Sta/Elev= 30
  3974.9  568.14  4180.2   557.4  4200.4  554.93    4372  545.58  4457.5  544.02
  4553.8  543.63  4584.1  544.44  4605.4   542.9  4612.2  543.69  4695.1  545.09
  4816.6  544.44  4946.5  543.83  4972.4  544.08  4986.1  542.72  4995.9  537.71
  4996.4  537.21  5004.6  537.71  5014.4  543.35  5021.7  544.51  5035.9  543.17
  5064.2  542.75  5141.9  543.18  5163.4  544.88  5219.5  544.16  5328.4  549.62
  5438.9  560.42    5504  564.51  5564.4  568.09  5626.1  571.52  5648.1  572.45
#Mann= 11 ,-1 , 0
  3974.9     .05       0  4612.2    .035       0  4816.6     .05       0
  4946.5     .12       0  4986.1     .05       0  4995.9     .05       0
  5004.6     .05       0  5328.4     .07       0    5504    .045       0
  5564.4     .07       0  5626.1    .045       0
Bank Sta=4995.9,5004.6
XS Rating Curve= 0 ,0
Exp/Cntr=0.3,0.1

Type RM Length L Ch R = 1 ,18740   ,411,411,411
BEGIN DESCRIPTION:
X18771
END DESCRIPTION:
XS GIS Cut Line= 3
      2270596.92      13744697.5      2271550.01     13744681.88
       2272305.2     13743921.48
#Sta/Elev= 30
  3543.5   563.7  3781.6  550.76  3980.4  544.09  4084.8  543.03  4332.3     542
  4464.6  541.48  4653.7  540.65  4823.3  541.68  4844.5  543.85  4872.8  538.63
  4879.9  544.03    4894  539.69  4901.1  543.98  4908.2  540.49  4915.2  542.86
  4922.3  540.06  4929.3  543.22  4985.9  542.61    4993  538.75  5000.1  539.36
  5002.8  536.66  5003.3  536.16  5011.5  536.66    5028  541.99  5119.7  545.29
    5290  557.67  5403.1  559.18  5489.2  565.14  5523.3  569.08  5568.4  570.03
#Mann= 11 ,-1 , 0
  3543.5     .05       0  3980.4     .07       0  4084.8     .05       0
  4332.3    .035       0  4464.6     .07       0  4653.7    .035       0
  5002.8    .035       0  5011.5    .035       0    5028     .12       0
  5119.7    .035       0  5489.2     .07       0
Bank Sta=5002.8,5011.5
XS Rating Curve= 0 ,0
Exp/Cntr=0.3,0.1

Type RM Length L Ch R = 1 ,18329   ,894,894,894
BEGIN DESCRIPTION:
X18770
END DESCRIPTION:
XS GIS Cut Line= 3
       2270591.7     13744770.42      2271800.01     13744796.46
       2272475.4     13744469.16
#Sta/Elev= 30
  3484.6  560.32    3728  547.95  4029.8  542.62  4113.9  542.91  4357.6  541.99
  4562.4  540.34    4663  538.96  4678.2  540.08  4698.7  539.14  4706.1  533.86
  4711.7  536.89    4721  536.83  4724.3  533.79  4724.8  533.29  4733.1  533.79
  4734.3  539.16  4774.5  539.56  4967.2  540.29  4982.6  541.57  4998.8  540.26
  5010.8  535.75    5021   535.1  5027.8  540.61  5033.3  541.37  5104.4  546.21
  5259.1  553.29  5349.4   560.5  5377.6  559.61    5431  562.71  5443.7  563.22
#Mann= 12 ,-1 , 0
  3484.6     .05       0  4029.8     .07       0  4113.9     .05       0
  4357.6    .035       0  4562.4     .07       0    4663     .12       0
  4724.3     .05       0  4733.1     .12       0  4774.5     .07       0
  4967.2     .12       0  5104.4     .05       0    5431     .07       0
Bank Sta=4724.3,4733.1
XS Rating Curve= 0 ,0
Exp/Cntr=0.3,0.1