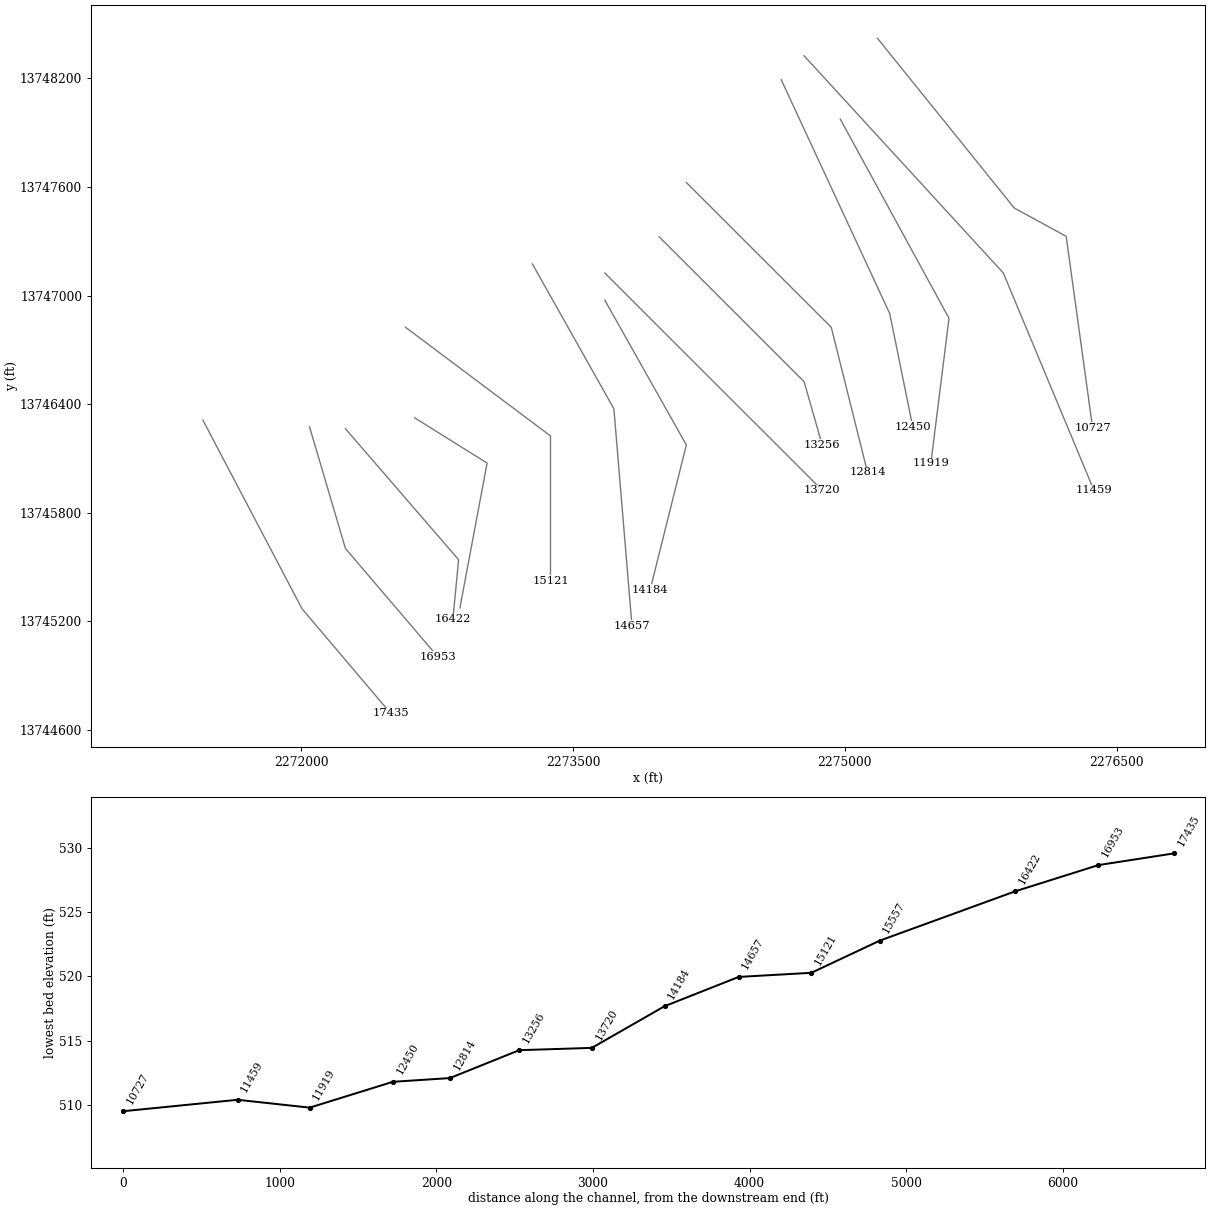
HEC-RAS study DEADMAN CREEK.prj: DEADMAN CREEK Base Level Engineering

--- DEADMAN CREEK.g01 (geometry) --- (continued)

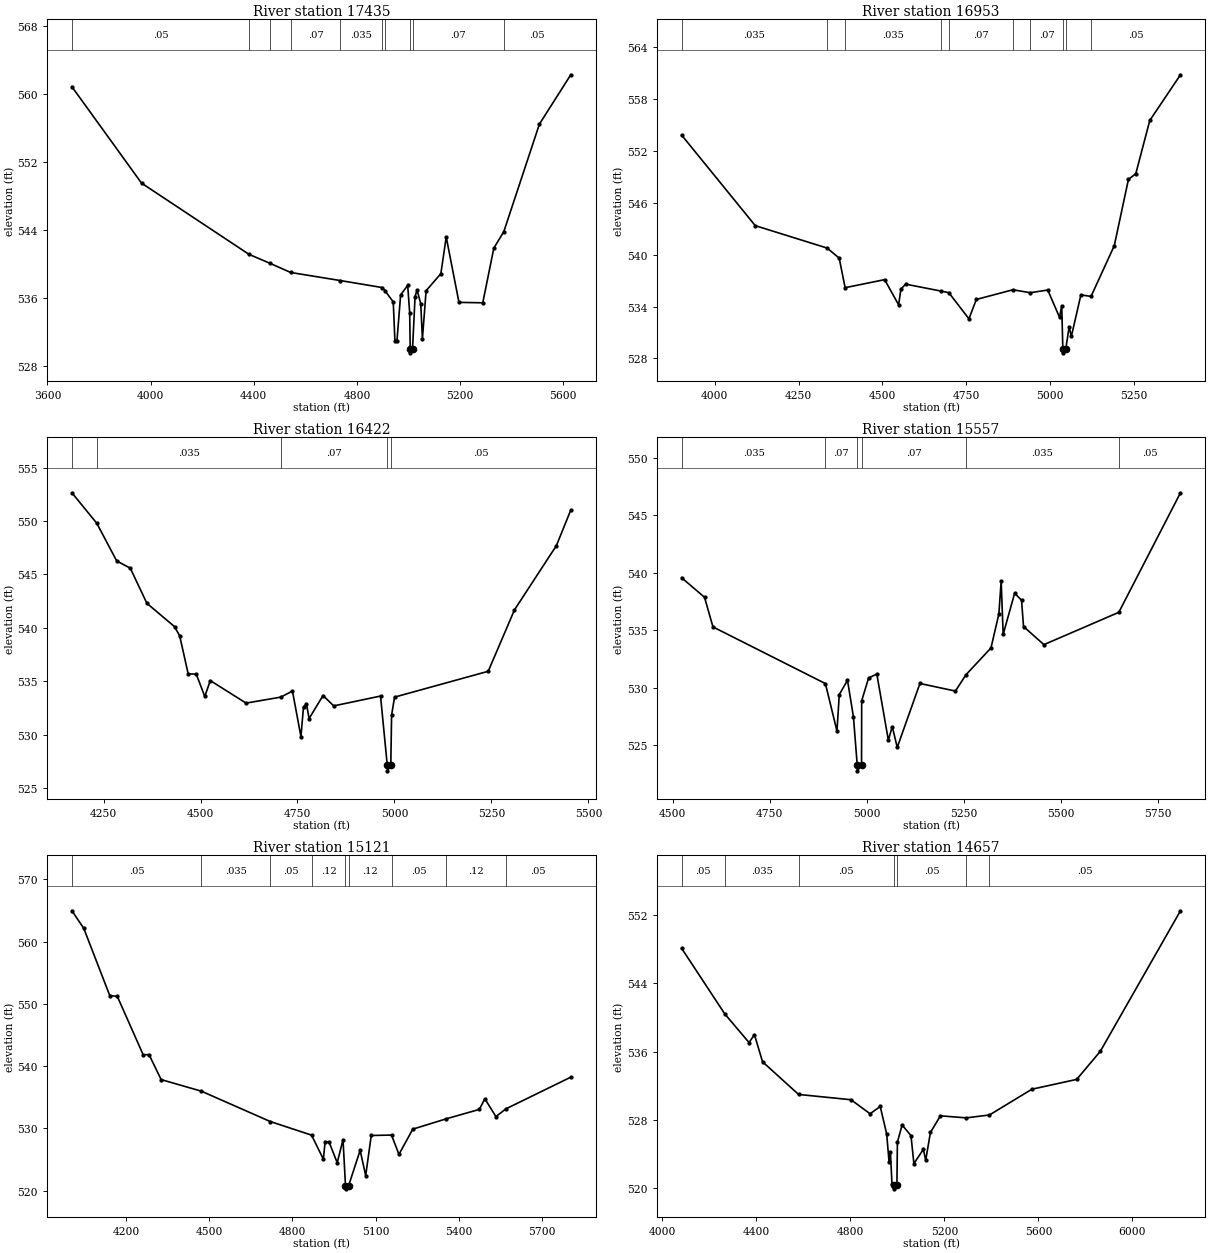
Type RM Length L Ch R = 1 ,17435   ,482,482,482
BEGIN DESCRIPTION:
X18769
END DESCRIPTION:
XS GIS Cut Line= 3
      2271456.25     13746312.11      2272003.14     13745270.42
      2272492.72     13744692.29
#Sta/Elev= 30
  3694.8  560.88  3964.6  549.54  4381.5  541.15    4461  540.12  4542.9  539.02
  4735.3  538.07  4898.7  537.24  4908.6  536.87  4940.6  535.56  4947.2  530.91
  4954.9  530.94  4969.2  536.37  4996.6  537.51  5004.3  534.26  5006.4  530.06
  5006.9  529.56  5015.4  530.06  5025.2  536.17  5032.9  536.97  5047.2  535.34
  5053.7  531.21    5068  536.87  5125.2  538.88    5146  543.19  5195.4   535.5
  5287.7  535.45  5330.6  541.89  5369.2  543.82  5507.4  556.49  5628.9  562.29
#Mann= 10 ,-1 , 0
  3694.8     .05       0  4381.5     .07       0    4461     .05       0
  4542.9     .07       0  4735.3    .035       0  4898.7     .05       0
  4908.6     .07       0  5006.4     .05       0  5015.4     .07       0
  5369.2     .05       0
Bank Sta=5006.4,5015.4
XS Rating Curve= 0 ,0
Exp/Cntr=0.3,0.1

Type RM Length L Ch R = 1 ,16953   ,531,531,531
BEGIN DESCRIPTION:
DEADMAN CREEK 25.0
END DESCRIPTION:
XS GIS Cut Line= 3
       2272044.8     13746275.63      2272242.72     13745603.75
      2272753.16     13745004.77
#Sta/Elev= 30
  3901.4  553.82    4121  543.35  4335.3  540.76  4371.2   539.6  4388.9  536.18
  4506.7  537.11  4548.4   534.2  4555.2  536.02  4569.3  536.59  4675.8  535.78
    4698  535.61  4758.1  532.58  4780.1  534.82  4889.1  535.94  4940.8   535.6
  4993.1  535.91  5028.3  532.75  5034.8   534.1    5038  529.15  5038.5  528.65
    5047  529.15  5056.8  531.65  5063.4  530.54  5091.9  535.35  5122.1  535.17
  5191.4  541.03  5233.6  548.69  5255.6  549.36  5297.3  555.51  5388.8  560.79
#Mann= 10 ,-1 , 0
  3901.4    .035       0  4335.3     .05       0  4388.9    .035       0
  4675.8     .05       0    4698     .07       0  4889.1     .05       0
  4940.8     .07       0    5038     .05       0    5047     .07       0
  5122.1     .05       0
Bank Sta=5038,5047
XS Rating Curve= 0 ,0
Exp/Cntr=0.3,0.1

Type RM Length L Ch R = 1 ,16422   ,865,865,865
BEGIN DESCRIPTION:
DEADMAN CREEK 24.0
END DESCRIPTION:
XS GIS Cut Line= 3
      2272242.72     13746265.21      2272867.72     13745541.25
      2272836.47     13745213.16
#Sta/Elev= 30
  4168.5  552.64  4232.7  549.78  4283.9  546.26    4319  545.58  4361.8  542.29
    4433  540.11  4446.3  539.25  4468.2  535.69  4489.1  535.66    4511  533.57
  4525.2  535.06  4617.4  532.95  4706.9  533.51    4737  534.08  4758.9  529.81
  4765.5  532.59  4773.2  532.88  4779.8   531.5  4815.9  533.66  4843.4  532.69
  4964.1  533.61  4981.5  527.11    4982  526.61  4990.5  527.11  4992.6  531.82
  5000.2  533.51  5241.7  535.93  5309.4  541.68  5417.4  547.69  5454.5  551.02
#Mann= 5 ,-1 , 0
  4168.5     .07       0  4232.7    .035       0  4706.9     .07       0
  4981.5     .05       0  4990.5     .05       0
Bank Sta=4981.5,4990.5
XS Rating Curve= 0 ,0
Exp/Cntr=0.3,0.1

Type RM Length L Ch R = 1 ,15557   ,436,436,436
BEGIN DESCRIPTION:
DEADMAN CREEK 23.0
END DESCRIPTION:
XS GIS Cut Line= 3
      2272624.98     13746325.01        2273025.       13746075.
      2272874.99     13745274.97
#Sta/Elev= 30
  4523.4  539.57  4582.4  537.87  4604.2  535.29    4894  530.36  4923.8  526.23
  4929.7   529.4  4950.9  530.65  4966.2  527.47    4976  523.27  4976.5  522.77
  4987.1  523.27  4987.5  528.87  5005.3  530.85  5026.5  531.19  5056.2  525.44
  5066.3  526.62  5079.1  524.81  5137.6  530.37  5229.1  529.71    5256  531.12
  5320.7  533.46    5341  536.41    5347  539.28  5352.1  534.64  5381.7  538.22
  5399.5  537.61  5404.6  535.32  5457.2  533.75  5650.2  536.56  5809.1  546.96
#Mann= 6 ,-1 , 0
  4523.4    .035       0    4894     .07       0    4976     .05       0
  4987.1     .07       0    5256    .035       0  5650.2     .05       0
Bank Sta=4976,4987.1
XS Rating Curve= 0 ,0
Exp/Cntr=0.3,0.1

Type RM Length L Ch R = 1 ,15121   ,464,464,464
BEGIN DESCRIPTION:
DEADMAN CREEK 22.0
END DESCRIPTION:
XS GIS Cut Line= 3
      2272574.96     13746825.03        2273375.       13746225.
        2273375.     13745425.04
#Sta/Elev= 30
  4004.5  564.94  4047.3  562.11    4141  551.32  4168.1   551.2  4261.8  541.79
  4282.7  541.84  4326.4  537.82  4471.5  535.96  4720.4  531.08  4869.1   528.9
  4911.8  525.03  4918.1  527.86  4932.7  527.75  4961.8  524.46  4982.7  528.18
  4991.6  520.77  4992.1  520.27  5002.9  520.77  5044.5  526.46  5064.5  522.39
  5084.5  528.84  5157.7  528.91  5184.5  525.81  5234.5  529.86  5354.6  531.51
  5474.5  533.03  5494.5  534.73  5534.5  531.87    5570  533.11  5804.5  538.21
#Mann= 9 ,-1 , 0
  4004.5     .05       0  4471.5    .035       0  4720.4     .05       0
  4869.1     .12       0  4991.6     .05       0  5002.9     .12       0
  5157.7     .05       0  5354.6     .12       0    5570     .05       0
Bank Sta=4991.6,5002.9
XS Rating Curve= 0 ,0
Exp/Cntr=0.3,0.1

Type RM Length L Ch R = 1 ,14657   ,473,473,473
BEGIN DESCRIPTION:
DEADMAN CREEK 21.0
END DESCRIPTION:
XS GIS Cut Line= 3
        2273275.       13747175.        2273725.       13746375.
        2273825.     13745175.04
#Sta/Elev= 30
  4082.3  548.08  4266.4  540.39  4369.1  537.06  4392.1  537.98  4426.5  534.81
  4579.8  530.99  4802.9  530.37  4883.9  528.73  4927.2  529.58  4954.6  526.35
  4964.8  523.06  4970.5  524.22  4977.2  520.47  4986.4  520.45  4986.9  519.95
  4998.1  520.45  5000.2  525.41  5020.3  527.42  5057.9  526.17  5070.4   522.9
  5110.6  524.57  5120.6  523.29  5140.7  526.55  5183.3  528.49  5293.2  528.25
  5391.8  528.59  5572.2   531.6  5762.8  532.75  5863.2  536.03  6204.3  552.47
#Mann= 7 ,-1 , 0
  4082.3     .05       0  4266.4    .035       0  4579.8     .05       0
  4986.4     .05       0  4998.1     .05       0  5293.2     .07       0
  5391.8     .05       0
Bank Sta=4986.4,4998.1
XS Rating Curve= 0 ,0
Exp/Cntr=0.3,0.1

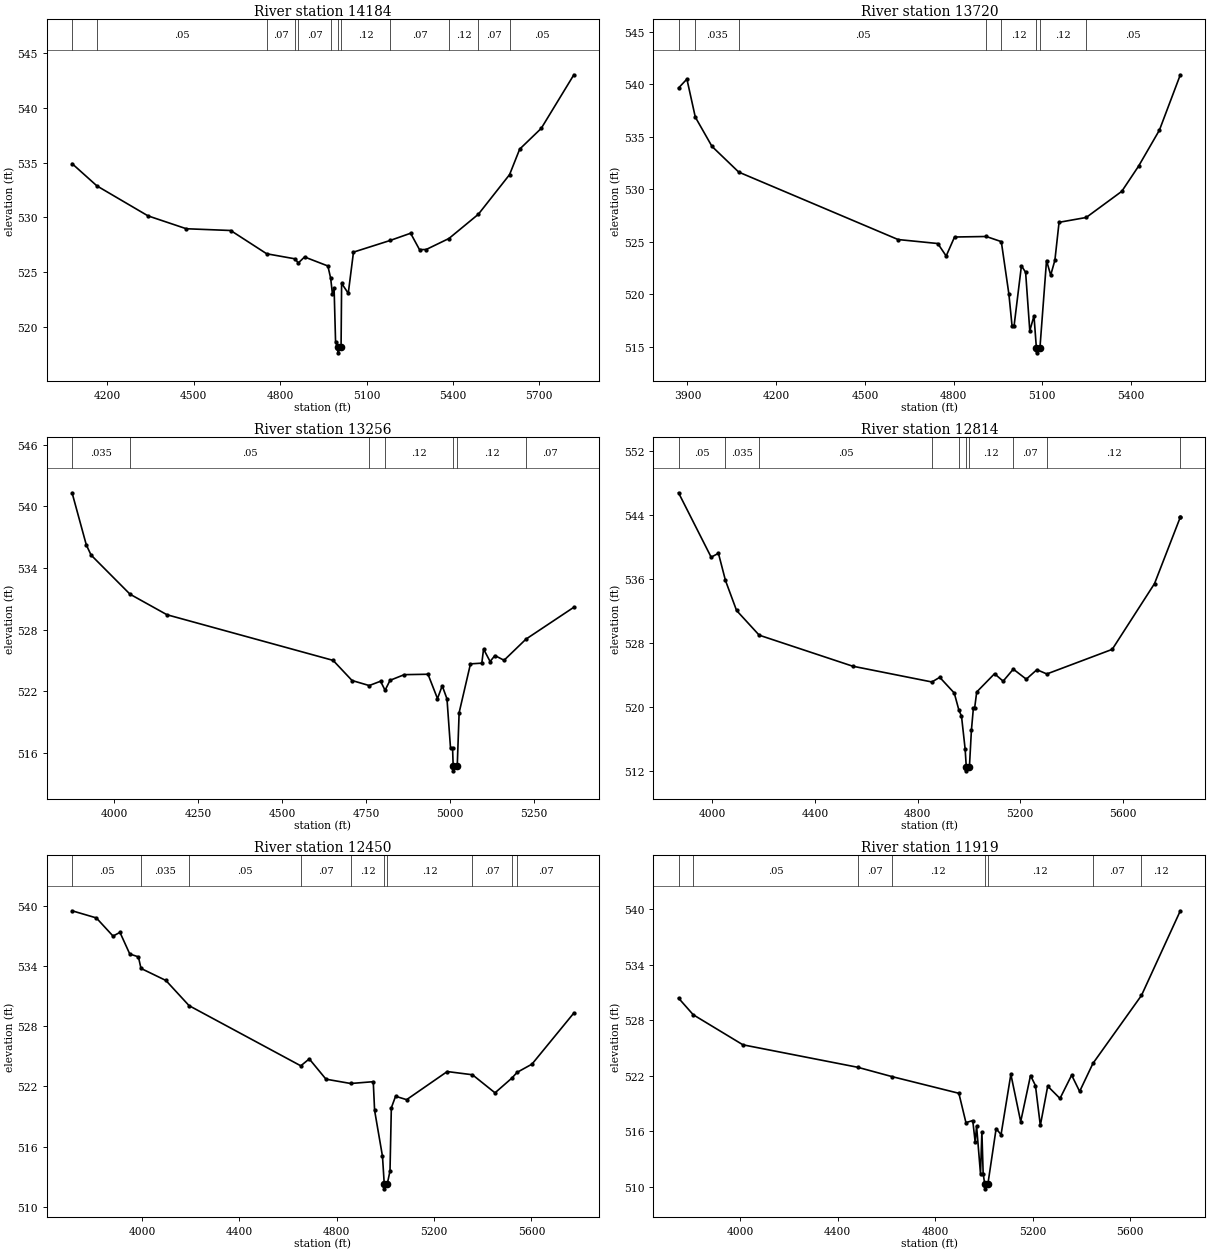
Type RM Length L Ch R = 1 ,14184   ,464,464,464
BEGIN DESCRIPTION:
DEADMAN CREEK 20.0
END DESCRIPTION:
XS GIS Cut Line= 3
      2273674.98     13746975.03        2274125.       13746175.
      2273925.01     13745375.03
#Sta/Elev= 30
  4077.4   534.9  4163.8  532.87  4341.3  530.14  4474.2  528.97  4628.2  528.81
  4753.3  526.69  4851.7  526.23  4862.9  525.85  4884.7   526.4  4965.7  525.58
  4975.5  524.45  4981.6     523  4987.3  523.56  4992.4  518.69  4999.8  518.17
  5000.3  517.67  5011.5  518.17  5013.4     524  5036.5  523.09  5054.6  526.84
  5181.6   527.9    5253  528.56  5283.9  527.07  5307.1  527.08    5386  528.08
  5488.3  530.29  5596.7   533.9  5631.8  536.22  5706.6  538.11  5819.9  542.99
#Mann= 12 ,-1 , 0
  4077.4    .035       0  4163.8     .05       0  4753.3     .07       0
  4851.7     .05       0  4862.9     .07       0  4975.5     .12       0
  4999.8     .05       0  5011.5     .12       0  5181.6     .07       0
    5386     .12       0  5488.3     .07       0  5596.7     .05       0
Bank Sta=4999.8,5011.5
XS Rating Curve= 0 ,0
Exp/Cntr=0.3,0.1

Type RM Length L Ch R = 1 ,13720   ,464,464,464
BEGIN DESCRIPTION:
DEADMAN CREEK 19.0
END DESCRIPTION:
XS GIS Cut Line= 3
      2273675.01     13747124.99        2274475.       13746325.
      2274874.97     13745925.03
#Sta/Elev= 30
  3869.8  539.65  3898.1   540.5  3926.5  536.88  3982.9  534.09  4073.5  531.64
  4612.2  525.22  4746.6  524.84  4774.9  523.65  4803.2  525.46  4910.4  525.51
  4961.4  525.02    4987  520.03  4997.6  517.03  5004.7  517.03  5029.4  522.72
  5043.6   522.1  5057.7  516.53  5071.9  517.95  5079.9  514.93  5080.4  514.43
  5092.1  514.93  5114.3  523.22  5128.4  521.83  5142.6  523.25  5156.7  526.86
  5248.4  527.32  5368.8  529.81  5425.4   532.2  5496.1  535.64  5566.8  540.91
#Mann= 8 ,-1 , 0
  3869.8     .05       0  3926.5    .035       0  4073.5     .05       0
  4910.4     .07       0  4961.4     .12       0  5079.9     .05       0
  5092.1     .12       0  5248.4     .05       0
Bank Sta=5079.9,5092.1
XS Rating Curve= 0 ,0
Exp/Cntr=0.3,0.1

Type RM Length L Ch R = 1 ,13256   ,442,442,442
BEGIN DESCRIPTION:
DEADMAN CREEK 18.0
END DESCRIPTION:
XS GIS Cut Line= 3
      2273974.97     13747325.03        2274775.       13746525.
        2274875.     13746175.02
#Sta/Elev= 30
  3873.6  541.31  3916.1  536.23  3930.2  535.25  4046.3  531.44  4156.5  529.44
  4651.5     525    4708  523.04  4759.1  522.55  4792.9  522.97  4806.4  522.09
  4821.2  523.06  4863.6  523.61  4934.3  523.65  4962.6  521.28  4976.7  522.53
  4990.9  521.25  5001.5  516.43  5007.6  516.43  5009.3  514.75  5009.8  514.25
  5021.5  514.75  5027.1  519.91  5060.9  524.66  5094.7  524.73  5099.9   526.1
  5119.4  524.89  5133.7  525.47    5161  525.01  5226.4  527.07    5369  530.17
#Mann= 7 ,-1 , 0
  3873.6    .035       0  4046.3     .05       0  4759.1     .07       0
  4806.4     .12       0  5009.3     .05       0  5021.5     .12       0
  5226.4     .07       0
Bank Sta=5009.3,5021.5
XS Rating Curve= 0 ,0
Exp/Cntr=0.3,0.1

Type RM Length L Ch R = 1 ,12814   ,364,364,364
BEGIN DESCRIPTION:
DEADMAN CREEK 17.0
END DESCRIPTION:
XS GIS Cut Line= 3
      2274125.03     13747624.97        2274925.       13746825.
      2275125.01     13746024.96
#Sta/Elev= 30
  3868.3  546.78  3995.5  538.74  4023.8  539.23  4051.2  535.84  4094.5  532.09
  4182.7  529.01  4547.1  525.14  4855.9  523.17  4886.5  523.75  4943.1  521.79
  4961.2  519.65  4971.3  518.91  4985.5   514.8  4989.9  512.58  4990.4  512.08
  5002.2  512.58  5009.9  517.13  5017.7  519.93  5022.8  519.98  5030.6  521.92
  5100.1   524.2  5133.6  523.27  5173.2  524.77  5223.8  523.52  5265.1   524.7
    5304  524.17  5558.8  527.24  5723.8  535.45  5823.9  543.71  5824.3  543.71
#Mann= 10 ,-1 , 0
  3868.3     .05       0  4051.2    .035       0  4182.7     .05       0
  4855.9     .07       0  4961.2     .12       0  4989.9     .05       0
  5002.2     .12       0  5173.2     .07       0    5304     .12       0
  5823.9     .07       0
Bank Sta=4989.9,5002.2
XS Rating Curve= 0 ,0
Exp/Cntr=0.3,0.1

Type RM Length L Ch R = 1 ,12450   ,531,531,531
BEGIN DESCRIPTION:
DEADMAN CREEK 16.0
END DESCRIPTION:
XS GIS Cut Line= 3
      2274648.96     13748192.31      2275247.93     13746900.63
        2275375.       13746275.
#Sta/Elev= 30
  3712.3  539.48    3812  538.77  3880.7  536.96  3909.1  537.33  3949.4  535.18
  3984.9  534.89  3995.6  533.74  4097.9  532.54  4193.3  530.03  4652.3  524.04
  4687.1  524.73  4755.8  522.71  4857.3  522.28  4950.1  522.46  4955.6   519.6
    4988  515.03  4995.2  512.29  4995.7  511.79  5007.8  512.29  5018.9  513.57
  5024.4  519.86  5041.8  521.01  5087.2  520.67  5254.1  523.47  5357.8  523.15
  5450.5  521.35  5519.4  522.81  5541.3  523.39  5602.4  524.21  5774.5   529.3
#Mann= 10 ,-1 , 0
  3712.3     .05       0  3995.6    .035       0  4193.3     .05       0
  4652.3     .07       0  4857.3     .12       0  4995.2     .05       0
  5007.8     .12       0  5357.8     .07       0  5519.4     .12       0
  5541.3     .07       0
Bank Sta=4995.2,5007.8
XS Rating Curve= 0 ,0
Exp/Cntr=0.3,0.1

Type RM Length L Ch R = 1 ,11919   ,460,460,460
BEGIN DESCRIPTION:
DEADMAN CREEK 15.0
END DESCRIPTION:
XS GIS Cut Line= 3
      2274975.02     13747974.96        2275575.       13746875.
        2275475.     13746074.98
#Sta/Elev= 30
    3747   530.4  3807.3   528.6  4011.3  525.35  4482.6  522.92    4622  521.92
  4897.4  520.11  4926.4  516.94  4954.4  517.16  4964.4  514.82  4970.1  516.57
  4986.2   511.4  4991.9  515.92  4997.1  511.42  5003.7  510.28  5004.2  509.78
  5016.4  510.28  5050.3  516.29  5070.5  515.64  5110.8  522.16  5151.1  517.04
  5191.4  522.03  5211.6  520.95  5231.7  516.63    5262  520.88  5312.4  519.55
  5360.2  522.07    5393  520.31  5447.6  523.34  5646.8  530.69  5806.2  539.84
#Mann= 8 ,-1 , 0
    3747    .035       0  3807.3     .05       0  4482.6     .07       0
    4622     .12       0  5003.7     .05       0  5016.4     .12       0
  5447.6     .07       0  5646.8     .12       0
Bank Sta=5003.7,5016.4
XS Rating Curve= 0 ,0
Exp/Cntr=0.3,0.1

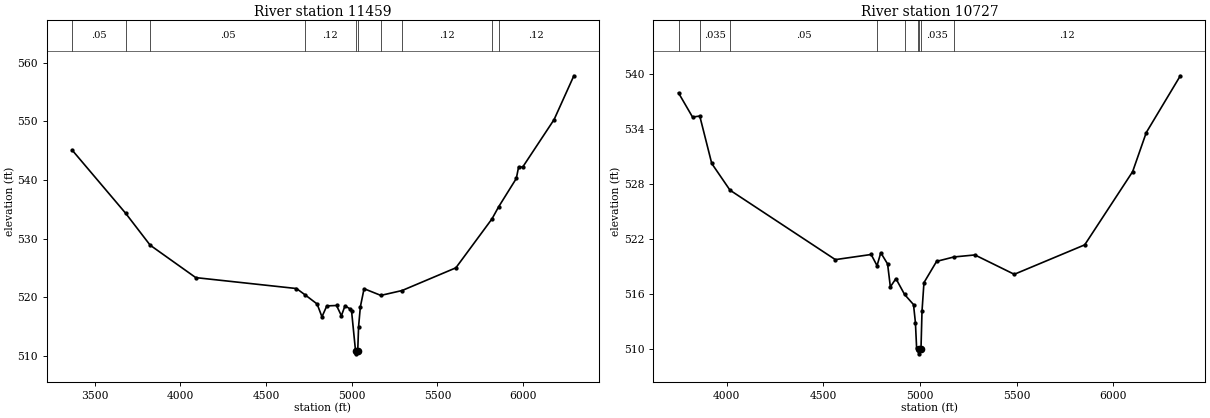
Type RM Length L Ch R = 1 ,11459   ,732,732,732
BEGIN DESCRIPTION:
DEADMAN CREEK 14.0
END DESCRIPTION:
XS GIS Cut Line= 3
      2274774.97     13748325.04        2275875.       13747125.
      2276374.99     13745925.03
#Sta/Elev= 30
  3367.8  545.13  3680.1  534.36  3823.4  528.91  4089.6  523.38  4677.2  521.52
  4728.5  520.42  4797.5  518.89  4825.9   516.7  4854.2  518.56  4910.9  518.63
  4939.3  516.88  4960.3  518.58  4988.6  518.07  4998.4  517.75  5021.8  510.89
  5022.3  510.39  5034.6  510.89  5039.6  515.03  5049.9   518.4  5071.6  521.49
  5169.4  520.35  5293.4  521.18  5607.3  525.05  5817.9  533.39    5856  535.41
  5959.9  540.28  5973.4  542.25  5997.3  542.23  6180.4  550.32  6295.7  557.78
#Mann= 10 ,-1 , 0
  3367.8     .05       0  3680.1    .035       0  3823.4     .05       0
  4728.5     .12       0  5021.8     .05       0  5034.6     .12       0
  5169.4    .035       0  5293.4     .12       0  5817.9     .07       0
    5856     .12       0
Bank Sta=5021.8,5034.6
XS Rating Curve= 0 ,0
Exp/Cntr=0.3,0.1

Type RM Length L Ch R = 1 ,10727   ,586,586,586
BEGIN DESCRIPTION:
X18773
END DESCRIPTION:
XS GIS Cut Line= 4
      2275180.21     13748421.47      2275935.43     13747483.96
      2276221.89     13747327.71      2276367.73     13746270.38
#Sta/Elev= 30
  3750.3  537.94  3822.8  535.31  3860.2  535.42  3922.2  530.25  4016.7  527.34
  4562.1  519.77  4747.4  520.33  4777.9  519.11  4797.2  520.52  4832.4   519.3
  4846.8   516.8  4875.6   517.7  4920.5  515.97  4966.6  514.87  4976.5  512.91
  4982.7  510.14  4987.7  510.07  4992.5     510    4993   509.5  5005.3     510
  5010.6  514.14  5020.7  517.26  5086.2  519.58  5175.8  520.06  5284.4  520.28
  5488.2  518.17  5852.8  521.38  6100.9  529.36  6171.5  533.62  6347.8  539.81
#Mann= 9 ,-1 , 0
  3750.3     .05       0  3860.2    .035       0  4016.7     .05       0
  4777.9    .035       0  4920.5     .12       0  4987.7    .035       0
  4992.5    .035       0  5005.3    .035       0  5175.8     .12       0
Bank Sta=4992.5,5005.3
XS Rating Curve= 0 ,0
Exp/Cntr=0.3,0.1