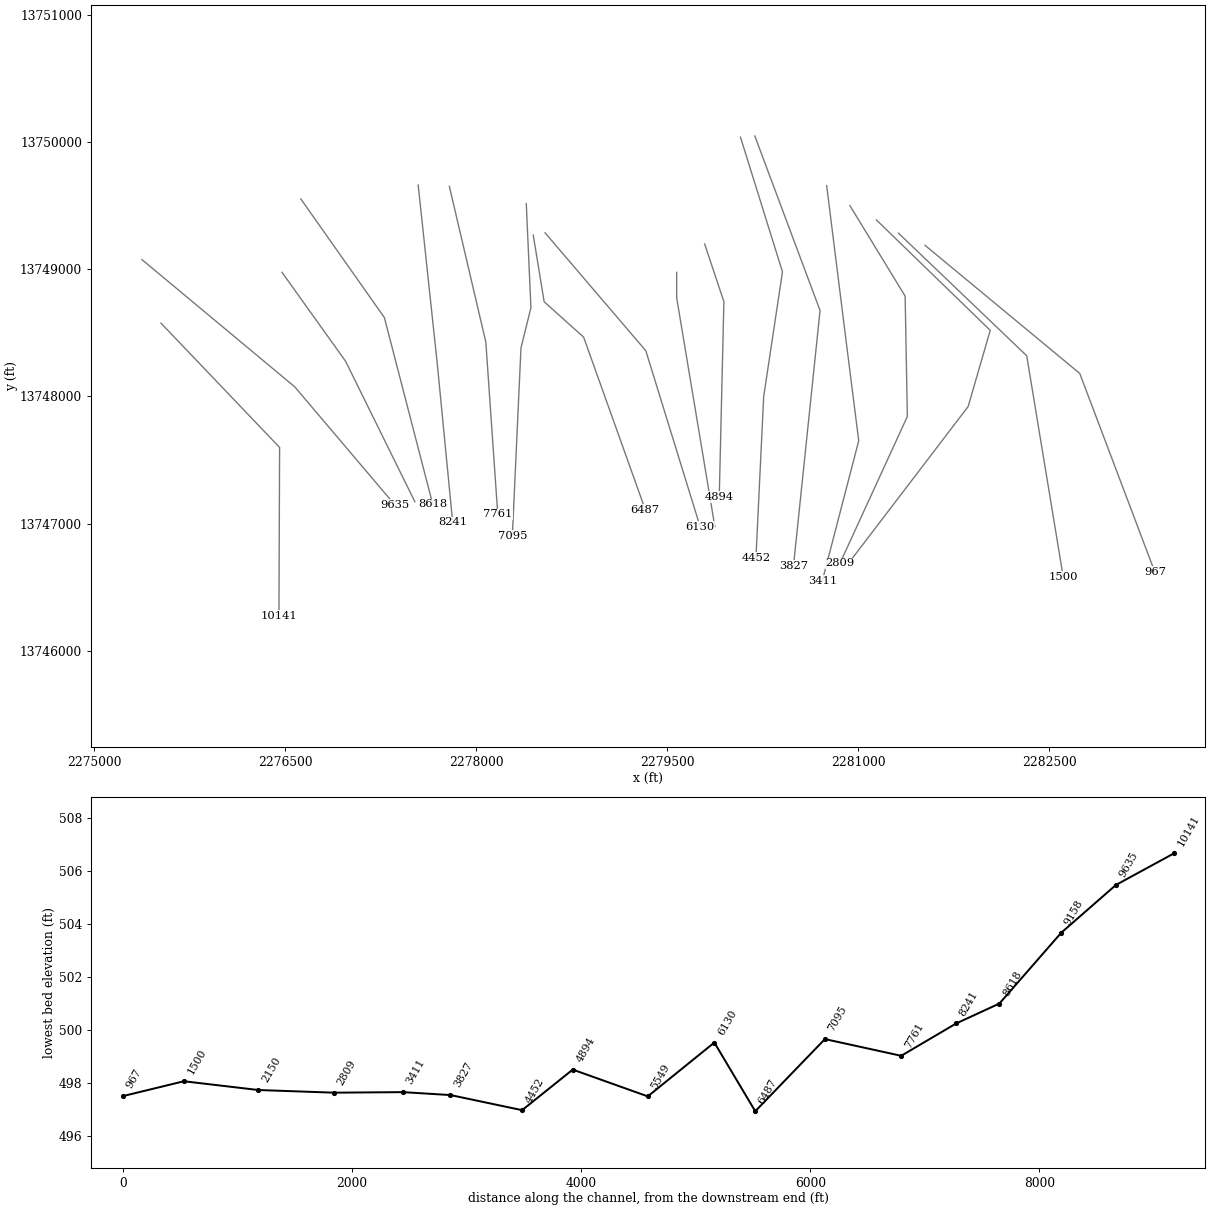
HEC-RAS study DEADMAN CREEK.prj: DEADMAN CREEK Base Level Engineering

--- DEADMAN CREEK.g01 (geometry) --- (continued)

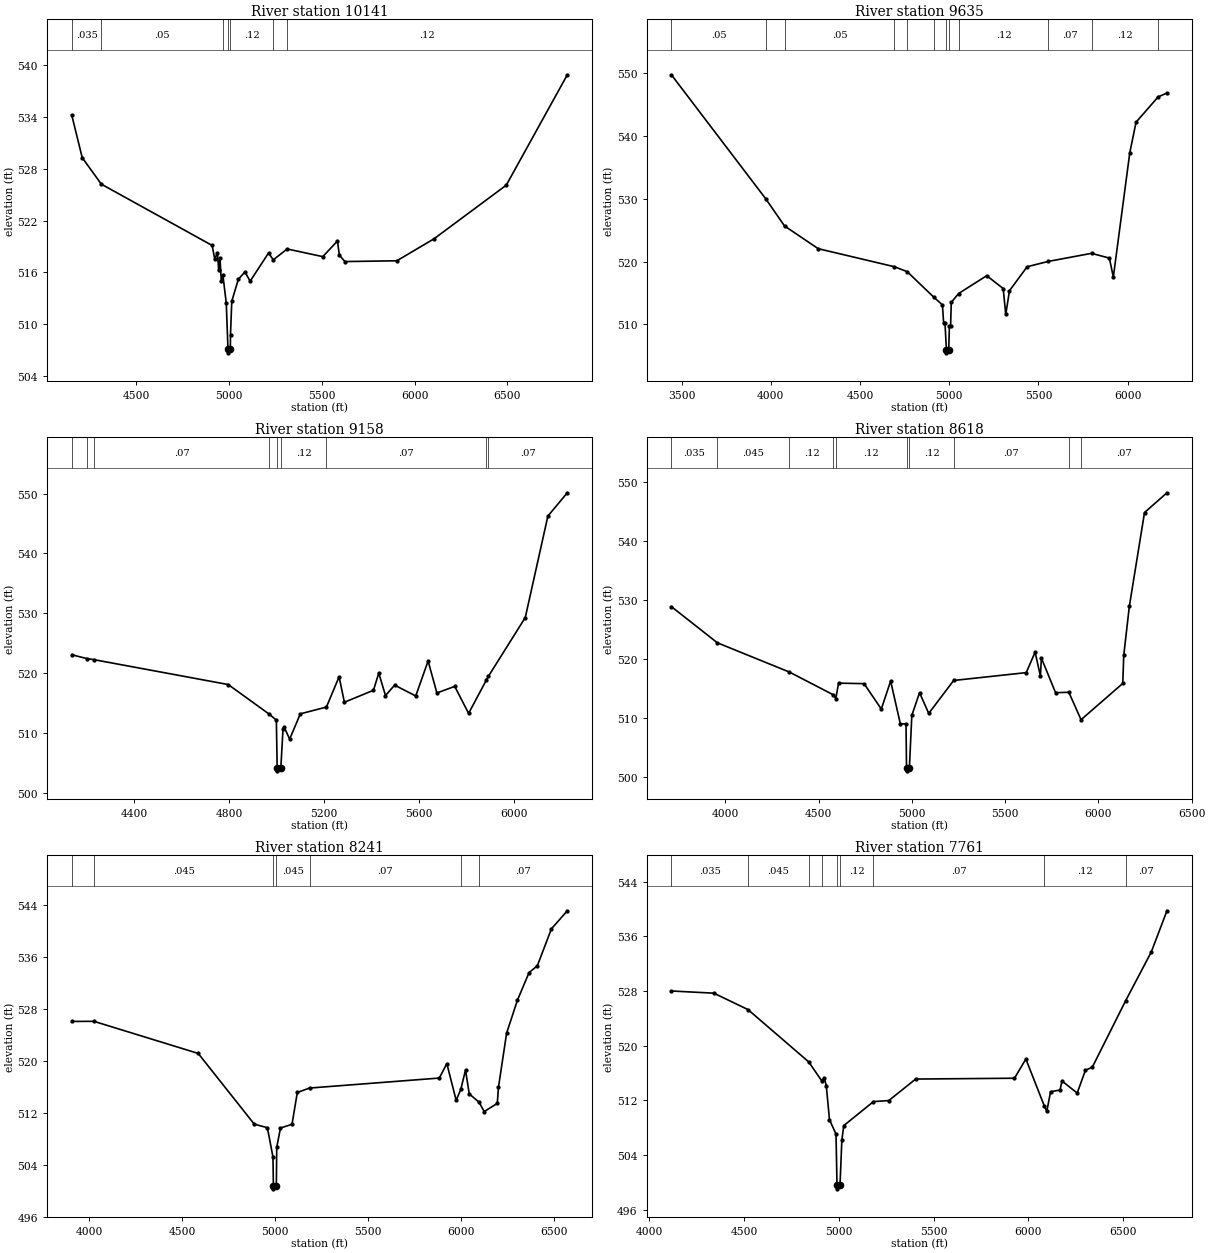
Type RM Length L Ch R = 1 ,10141   ,506,506,506
BEGIN DESCRIPTION:
DEADMAN CREEK 13.0
END DESCRIPTION:
XS GIS Cut Line= 3
      2275524.97     13748575.03      2276456.26     13747598.54
      2276451.05     13746275.63
#Sta/Elev= 30
  4151.6  534.22  4208.1  529.29  4311.2  526.22  4908.5  519.12  4922.7  517.54
  4936.9  518.28  4943.8  516.28    4951  517.64  4957.9  515.02  4966.4  515.71
  4984.8  512.42  4993.9  507.17  4994.4  506.67  5006.8  507.17  5007.6  508.79
  5014.5  512.65  5049.9   515.2  5085.3  516.04  5113.6  514.98  5212.7  518.24
  5238.5  517.45    5313  518.71  5505.3  517.82  5584.5  519.64  5594.5  517.99
  5624.5  517.25  5904.5  517.34  6104.5  519.88  6494.5   526.1  6823.9   538.9
#Mann= 7 ,-1 , 0
  4151.6    .035       0  4311.2     .05       0  4966.4     .12       0
  4993.9     .05       0  5006.8     .12       0  5238.5     .07       0
    5313     .12       0
Bank Sta=4993.9,5006.8
XS Rating Curve= 0 ,0
Exp/Cntr=0.3,0.1

Type RM Length L Ch R = 1 ,9635    ,477,477,477
BEGIN DESCRIPTION:
DEADMAN CREEK 12.0
END DESCRIPTION:
XS GIS Cut Line= 3
      2275374.97     13749075.03        2276575.       13748075.
      2277361.28     13747146.88
#Sta/Elev= 30
  3442.4  549.69  3971.2  529.98  4076.9  525.65  4265.8  522.04  4692.8  519.17
  4764.4  518.39  4912.9  514.35  4962.2   513.1  4968.7  510.23  4976.5  510.19
  4984.3  505.98  4984.8  505.48  4997.3  505.98  5001.2  509.68  5007.8  509.68
  5011.6   513.5  5052.7  514.91  5210.5  517.75  5302.8   515.7  5317.1  511.58
  5337.9  515.35    5437  519.17  5556.2  520.02    5798   521.3  5898.2  520.54
  5920.2  517.52  6012.5  537.29  6047.6  542.15  6171.6  546.18  6220.9  546.78
#Mann= 12 ,-1 , 0
  3442.4     .05       0  3971.2    .035       0  4076.9     .05       0
  4692.8     .07       0  4764.4     .12       0  4912.9      .1       0
  4984.3     .05       0  4997.3      .1       0  5052.7     .12       0
  5556.2     .07       0    5798     .12       0  6171.6     .07       0
Bank Sta=4984.3,4997.3
XS Rating Curve= 0 ,0
Exp/Cntr=0.3,0.1

Type RM Length L Ch R = 1 ,9158    ,540,540,540
BEGIN DESCRIPTION:
DEADMAN CREEK 11.0
END DESCRIPTION:
XS GIS Cut Line= 3
      2276475.02     13748974.97        2276975.       13748275.
      2277518.75     13747171.49
#Sta/Elev= 30
  4136.1  523.07  4201.9  522.42    4228  522.27    4796   518.1  4969.8  513.13
  4999.1  512.15  5002.6  504.18  5003.1  503.68    5018  504.18  5027.2  510.63
  5032.8  510.93  5055.2  508.98  5100.2   513.2  5210.4  514.34  5263.8   519.4
  5286.1  515.14  5408.8  517.14  5431.1  520.02  5459.5  516.26    5498     518
  5587.1  516.19  5639.2  522.04  5676.3  516.69  5751.5  517.79  5810.1  513.28
  5884.1  518.78  5893.5  519.47  6049.1  529.29  6144.5  546.25  6226.5  550.14
#Mann= 9 ,-1 , 0
  4136.1     .07       0  4201.9     .05       0    4228     .07       0
  4969.8     .12       0  5002.6     .05       0    5018     .12       0
  5210.4     .07       0  5884.1     .12       0  5893.5     .07       0
Bank Sta=5002.6,5018
XS Rating Curve= 0 ,0
Exp/Cntr=0.3,0.1

Type RM Length L Ch R = 1 ,8618    ,377,377,377
BEGIN DESCRIPTION:
X18774
END DESCRIPTION:
XS GIS Cut Line= 3
      2276622.95     13749551.63      2277279.18     13748619.38
      2277659.38     13747150.65
#Sta/Elev= 30
  3710.3  528.83  3957.1   522.7  4343.4  517.74  4579.2  513.88  4591.9  513.26
  4606.8  515.87  4743.5  515.78  4835.9  511.48  4885.9  516.22  4938.1  508.95
  4968.3  508.98  4971.1  501.51  4971.6  501.01  4986.5  501.51  4999.5   510.4
  5040.8  514.25  5090.2  510.74  5223.8  516.32    5613  517.65  5660.6  521.12
    5689  517.06  5694.2  520.12  5770.2  514.25  5841.4  514.32  5906.8  509.67
  6130.6  515.82  6135.8  520.56    6166  528.93  6247.2  544.77  6367.5  548.12
#Mann= 10 ,-1 , 0
  3710.3    .035       0  3957.1    .045       0  4343.4     .12       0
  4579.2     .07       0  4591.9     .12       0  4971.1     .05       0
  4986.5     .12       0  5223.8     .07       0  5841.4     .12       0
  5906.8     .07       0
Bank Sta=4971.1,4986.5
XS Rating Curve= 0 ,0
Exp/Cntr=0.3,0.1

Type RM Length L Ch R = 1 ,8241    ,480,480,480
BEGIN DESCRIPTION:
X18775
END DESCRIPTION:
XS GIS Cut Line= 3
       2277544.8     13749661.09      2277695.85     13748244.38
      2277815.64     13747010.02
#Sta/Elev= 30
  3907.5  526.02  4026.2  526.04  4587.4   521.1  4889.1  510.21  4959.5  509.67
  4989.4  505.16  4991.8  500.76  4992.3  500.26  5007.6  500.76  5009.8  506.65
  5029.9  509.62  5091.9  510.19  5120.4  515.09  5186.2  515.77  5884.2  517.31
  5924.4  519.54  5974.6  513.88  5999.6  515.57  6024.9  518.54    6045  514.87
  6098.2  513.58  6125.3  512.15  6195.7  513.41  6202.1  515.89  6245.9  524.22
  6304.1  529.29  6366.5  533.53  6411.1  534.59    6487  540.28  6572.4  543.05
#Mann= 7 ,-1 , 0
  3907.5    .094       0  4026.2    .045       0  4991.8     .05       0
  5007.6    .045       0  5186.2     .07       0  5999.6     .12       0
  6098.2     .07       0
Bank Sta=4991.8,5007.6
XS Rating Curve= 0 ,0
Exp/Cntr=0.3,0.1

Type RM Length L Ch R = 1 ,7761    ,666,666,666
BEGIN DESCRIPTION:
X18776
END DESCRIPTION:
XS GIS Cut Line= 3
      2277789.58     13749650.67      2278076.05     13748426.67
       2278169.8     13747072.49
#Sta/Elev= 30
    4117     528  4340.9  527.68    4521  525.28  4841.2  517.63  4909.2  514.89
  4923.9  515.26  4934.2  514.15  4951.1  509.16  4985.5  507.05  4990.8  499.54
  4991.3  499.04  5006.6  499.54  5016.3  506.17  5026.6   508.3  5183.3  511.81
  5263.9  511.96  5405.8  515.11  5927.1  515.23  5987.2  518.04  6084.4  511.18
  6097.5  510.38  6117.5  513.25  6167.6  513.51  6177.7  514.83  6257.9  513.06
  6301.5   516.4    6338  516.86  6513.1  526.55  6648.8  533.71  6731.5  539.74
#Mann= 9 ,-1 , 0
    4117    .035       0    4521    .045       0  4841.2     .07       0
  4909.2     .12       0  4990.8     .05       0  5006.6     .12       0
  5183.3     .07       0  6084.4     .12       0  6513.1     .07       0
Bank Sta=4990.8,5006.6
XS Rating Curve= 0 ,0
Exp/Cntr=0.3,0.1

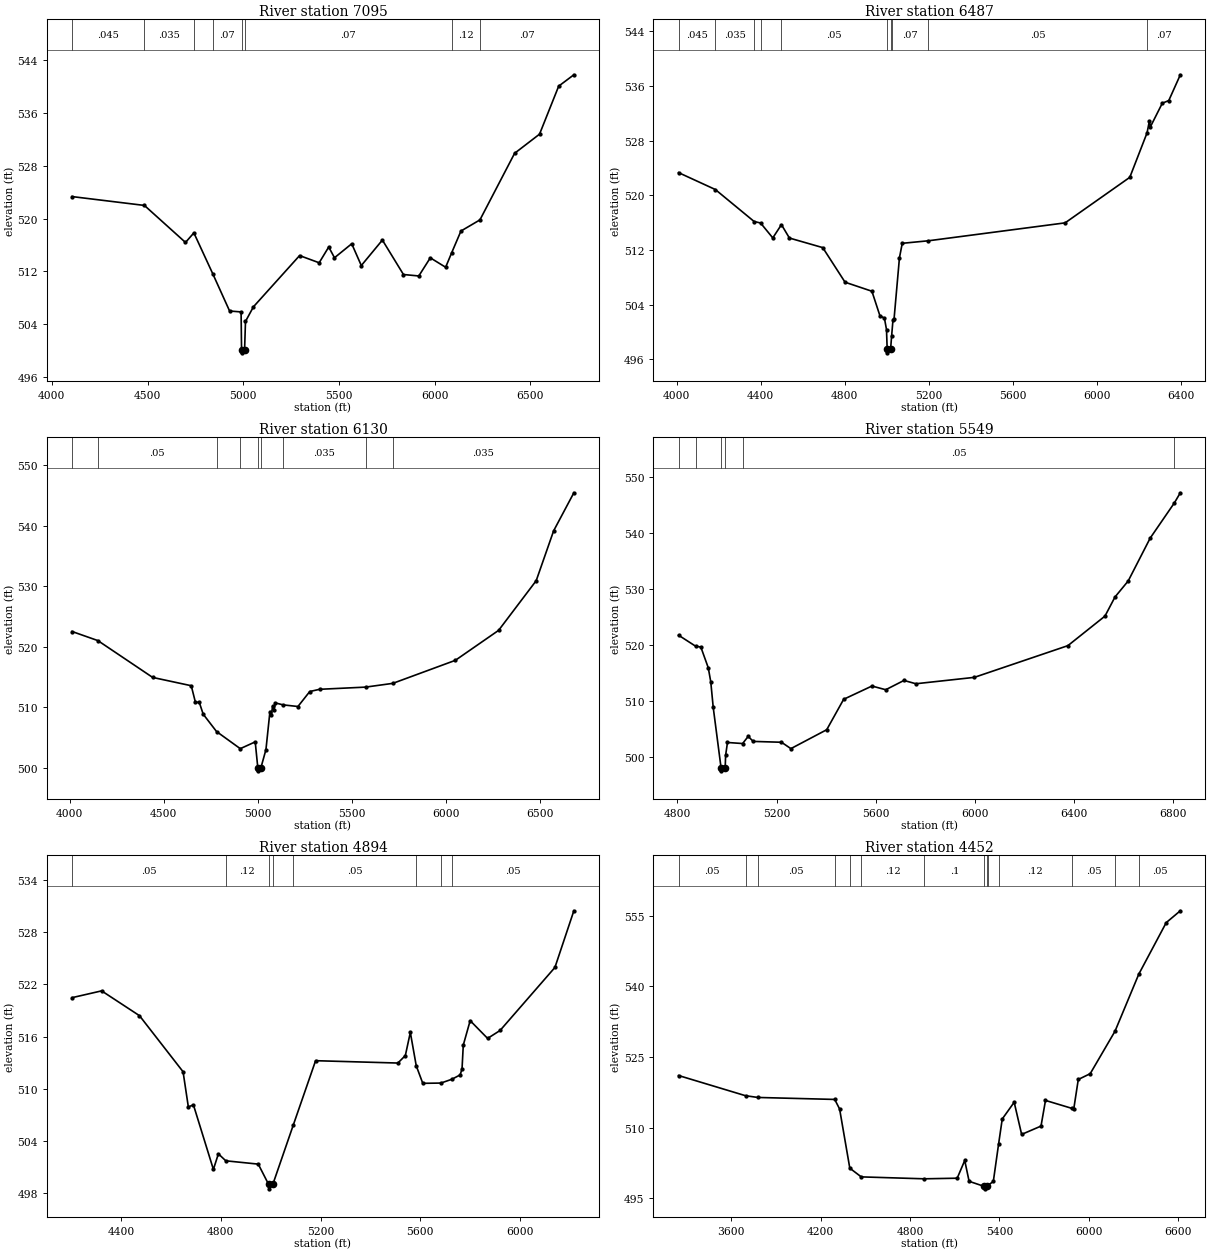
Type RM Length L Ch R = 1 ,7095    ,608,608,608
BEGIN DESCRIPTION:
X18777
END DESCRIPTION:
XS GIS Cut Line= 4
      2278393.76     13749515.24      2278430.22      13748697.5
       2278352.1     13748379.79      2278284.39     13746905.87
#Sta/Elev= 30
  4105.6  523.35  4483.5  522.01  4698.1   516.4  4741.9  517.85  4840.3  511.67
  4928.5  506.01  4988.5  505.87  4990.9  500.17  4991.4  499.67  5006.8  500.17
  5011.5  504.43  5053.1  506.65  5294.1  514.41  5396.3  513.32  5446.3  515.71
  5476.4  514.08  5566.4   516.2  5616.5   512.9  5726.6  516.76  5836.7  511.54
  5916.8  511.32  5976.9  514.07    6057  512.64  6088.9  514.86    6137  518.13
  6236.2  519.82  6417.3  529.91  6547.5  532.81  6647.6  540.09  6726.8  541.81
#Mann= 8 ,-1 , 0
  4105.6    .045       0  4483.5    .035       0  4741.9     .12       0
  4840.3     .07       0  4990.9     .05       0  5006.8     .07       0
  6088.9     .12       0  6236.2     .07       0
Bank Sta=4990.9,5006.8
XS Rating Curve= 0 ,0
Exp/Cntr=0.3,0.1

Type RM Length L Ch R = 1 ,6487    ,357,357,357
BEGIN DESCRIPTION:
X18778
END DESCRIPTION:
XS GIS Cut Line= 4
      2278448.51     13749267.64      2278534.08     13748743.54
      2278844.25     13748465.46      2279328.61     13747108.53
#Sta/Elev= 30
  4009.5  523.31  4184.5  520.84  4369.3  516.16    4400  515.94  4458.1  513.76
  4499.3   515.7  4537.3  513.74  4695.9  512.34  4802.1  507.28  4929.9  505.96
  4968.2  502.36  4989.5  502.03  4999.4  500.34  5002.6  497.45  5003.1  496.95
  5018.7  497.45  5023.9  499.46  5030.2  501.75  5035.5  501.96    5061  510.86
  5074.4  512.97  5198.7  513.34  5849.5  515.96  6157.4  522.62  6239.6  529.13
  6250.5  530.84  6255.8  530.03  6312.1  533.46  6342.9  533.85  6397.9  537.62
#Mann= 10 ,-1 , 0
  4009.5    .045       0  4184.5    .035       0  4369.3     .05       0
    4400    .035       0  4499.3     .05       0  5002.6     .05       0
  5018.7     .05       0  5023.9     .07       0  5198.7     .05       0
  6239.6     .07       0
Bank Sta=5002.6,5018.7
XS Rating Curve= 0 ,0
Exp/Cntr=0.3,0.1

Type RM Length L Ch R = 1 ,6130    ,581,581,581
BEGIN DESCRIPTION:
DEADMAN CREEK 7.0
END DESCRIPTION:
XS GIS Cut Line= 3
      2278541.18     13749285.48      2279332.68      13748358.5
      2279760.25     13746972.46
#Sta/Elev= 30
  4012.2  522.54  4149.4  521.04  4440.9  514.96  4646.2  513.59  4668.2  510.88
    4689  510.84  4709.8  508.89  4780.7  506.03    4907   503.2  4986.5  504.32
  5000.3  500.04  5000.8  499.54  5016.7  500.04  5043.6  503.05  5064.8  509.33
  5072.2  508.68  5078.7  510.21  5086.4  509.58    5093  510.76  5134.5  510.43
  5213.8  510.16  5276.6  512.63    5329     513  5573.5  513.36  5718.4  513.98
    6051  517.78  6281.3  522.73  6481.3  530.93    6574  539.16  6681.6  545.44
#Mann= 9 ,-1 , 0
  4012.2    .045       0  4149.4     .05       0  4780.7     .07       0
    4907     .12       0  5000.3     .05       0  5016.7     .12       0
  5134.5    .035       0  5573.5     .05       0  5718.4    .035       0
Bank Sta=5000.3,5016.7
XS Rating Curve= 0 ,0
Exp/Cntr=0.3,0.1

Type RM Length L Ch R = 1 ,5549    ,655,655,655
BEGIN DESCRIPTION:
DEADMAN CREEK 6.0
END DESCRIPTION:
XS GIS Cut Line= 3
        2279575.     13748974.97        2279575.       13748775.
        2279875.       13746975.
#Sta/Elev= 30
  4804.6  521.76  4873.2   519.8  4894.6  519.64  4924.6  515.93  4934.6  513.44
  4944.6  508.84  4976.3  498.01  4976.8  497.51  4992.8  498.01  4994.6  500.29
  5002.1  502.58  5063.2  502.39  5085.7  503.67    5106  502.77    5220  502.62
    5258  501.48  5402.5  504.86  5470.9   510.3    5585  512.67  5640.7  512.01
  5714.2  513.67  5762.4  513.08  5998.1  514.22  6375.7  519.89  6525.3  525.17
  6565.8  528.59    6619  531.45  6707.7  539.11  6805.5  545.42  6829.4  547.22
#Mann= 6 ,-1 , 0
  4804.6     .05       0  4873.2     .12       0  4976.3     .05       0
  4992.8     .12       0  5063.2     .05       0  6805.5    .035       0
Bank Sta=4976.3,4992.8
XS Rating Curve= 0 ,0
Exp/Cntr=0.3,0.1

Type RM Length L Ch R = 1 ,4894    ,442,442,442
BEGIN DESCRIPTION:
X18779
END DESCRIPTION:
XS GIS Cut Line= 3
      2279794.79     13749197.53      2279945.85     13748744.38
      2279909.41     13747208.97
#Sta/Elev= 30
  4203.1  520.48  4321.7  521.26  4473.6  518.41  4648.5  511.97  4669.6  507.94
  4690.1  508.16  4770.2  500.75  4790.2  502.54  4819.9  501.74  4950.2  501.36
    4992  499.02  4992.5  498.52  5008.5  499.02  5091.4   505.9  5180.3  513.24
  5510.4  512.97  5540.4  513.83  5560.4  516.49  5584.2  512.65  5610.4  510.64
    5683  510.67  5727.3  511.11  5760.4  511.61  5767.9  512.31  5772.9  515.03
  5800.5  517.84  5870.5   515.8  5920.5  516.71  6140.6  523.95  6216.6  530.46
#Mann= 8 ,-1 , 0
  4203.1     .05       0  4819.9     .12       0    4992     .05       0
  5008.5     .12       0  5091.4     .05       0  5584.2     .12       0
    5683    .033       0  5727.3     .05       0
Bank Sta=4992,5008.5
XS Rating Curve= 0 ,0
Exp/Cntr=0.3,0.1

Type RM Length L Ch R = 1 ,4452    ,625,625,625
BEGIN DESCRIPTION:
X18786
END DESCRIPTION:
XS GIS Cut Line= 4
      2280076.07     13750037.73      2280405.92     13748978.75
      2280258.35     13747997.85      2280197.58     13746730.51
#Sta/Elev= 30
  3245.2  521.06  3695.2  516.77  3777.7   516.4  4294.1  515.98  4326.9  513.95
  4395.4  501.38  4472.2  499.53  4895.3  499.12  5116.6  499.25  5167.2  503.01
  5196.6  498.59  5299.8  497.49  5300.3  496.99  5317.7  497.49  5321.2  497.69
  5359.2  498.55  5394.7  506.52  5419.2  511.83  5499.3  515.38  5549.4  508.55
  5679.5  510.32  5709.6  515.77  5888.2  514.07  5899.8  514.03  5929.8  520.22
  6009.9  521.45  6176.5  530.47    6336  542.58  6520.5  553.54  6615.1  556.05
#Mann= 14 ,-1 , 0
  3245.2     .05       0  3695.2     .07       0  3777.7     .05       0
  4294.1     .07       0  4395.4      .1       0  4472.2     .12       0
  4895.3      .1       0  5299.8     .05       0  5317.7      .1       0
  5321.2      .1       0  5394.7     .12       0  5888.2     .05       0
  6176.5    .035       0    6336     .05       0
Bank Sta=5299.8,5317.7
XS Rating Curve= 0 ,0
Exp/Cntr=0.3,0.1

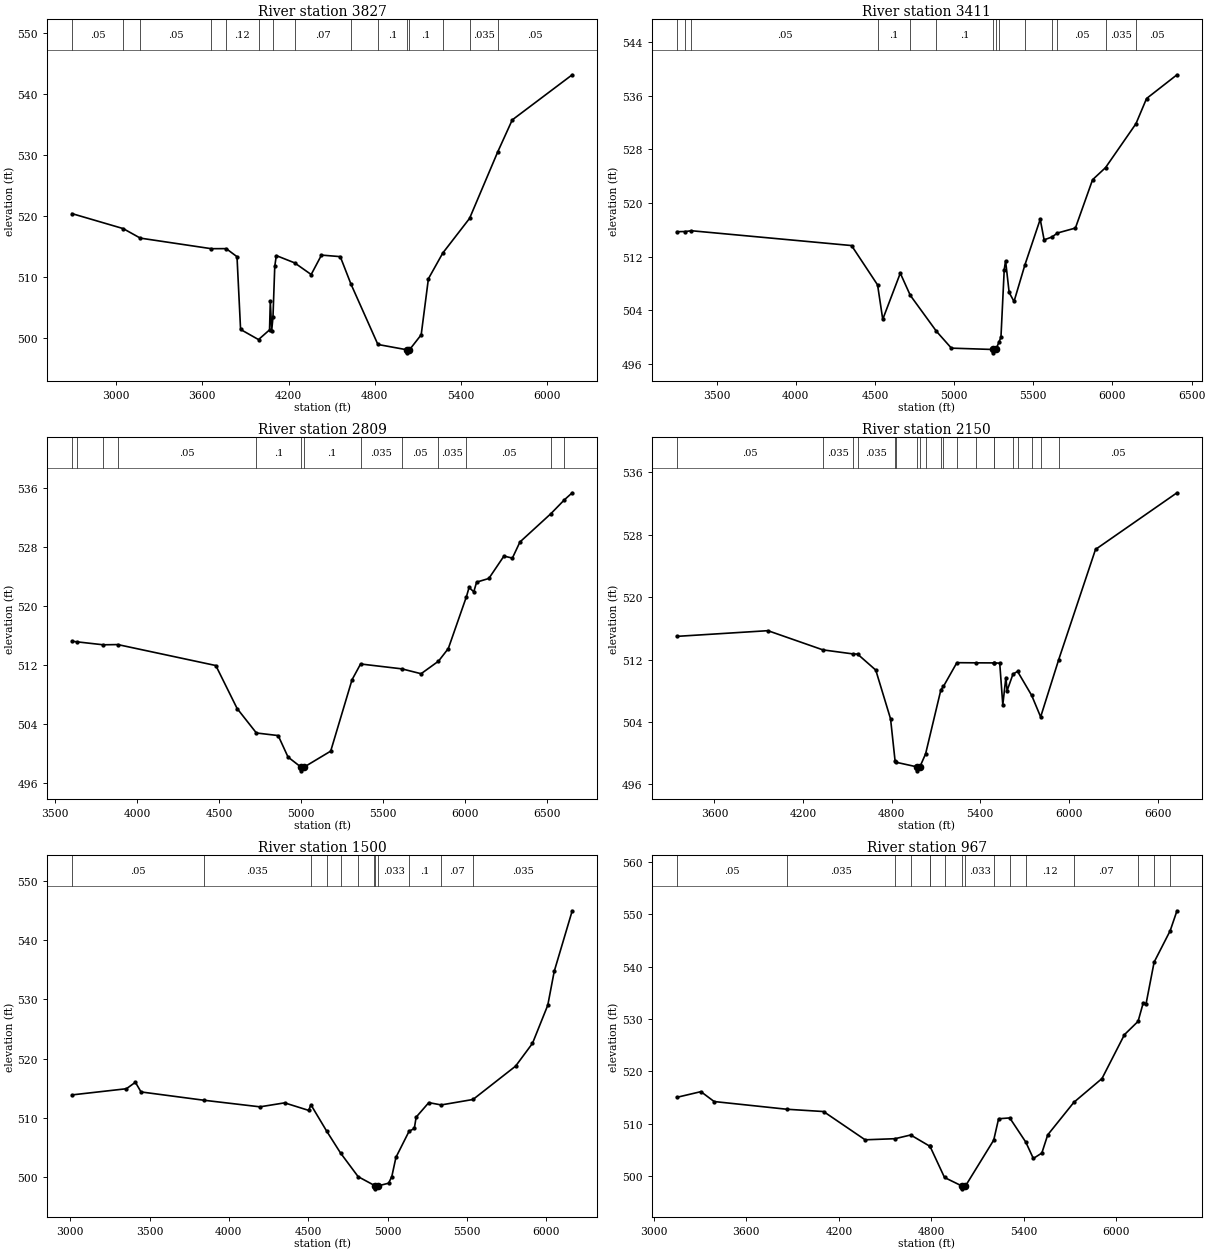
Type RM Length L Ch R = 1 ,3827    ,416,416,416
BEGIN DESCRIPTION:
X18785
END DESCRIPTION:
XS GIS Cut Line= 3
      2280188.88      13750046.5      2280701.05     13748674.93
      2280492.74      13746669.9
#Sta/Elev= 30
  2693.3  520.35  3049.3   517.9  3168.6  516.34  3662.1  514.61    3766  514.62
  3841.2   513.3  3866.1  501.39  3990.9  499.73  4067.6  501.32  4072.9  506.01
  4082.6  501.21  4091.4  503.38  4103.9  511.71  4114.6  513.48  4242.1  512.29
  4357.2  510.38  4428.8  513.56  4559.6  513.31  4633.7  508.83  4821.3  498.93
    5023  498.06  5023.5  497.56    5041  498.06  5122.5  500.51  5172.7  509.69
  5272.8   513.9    5459  519.57  5655.4  530.48  5755.9  535.69  6173.2  543.08
#Mann= 15 ,-1 , 0
  2693.3     .05       0  3049.3     .07       0  3168.6     .05       0
  3662.1     .07       0    3766     .12       0  3990.9      .1       0
  4091.4     .05       0  4242.1     .07       0  4633.7     .05       0
  4821.3      .1       0    5023     .05       0    5041      .1       0
  5272.8     .05       0    5459    .035       0  5655.4     .05       0
Bank Sta=5023,5041
XS Rating Curve= 0 ,0
Exp/Cntr=0.3,0.1

Type RM Length L Ch R = 1 ,3411    ,602,602,602
BEGIN DESCRIPTION:
X18784
END DESCRIPTION:
XS GIS Cut Line= 4
      2280753.14      13749655.8      2280900.71     13748475.28
      2281004.87     13747650.63      2280718.66     13746549.12
#Sta/Elev= 30
  3248.4  515.74  3300.9  515.76  3341.2  515.88  4352.3  513.67  4516.7   507.8
  4549.3  502.67  4660.1  509.55  4723.1  506.25  4888.4  500.88  4982.7  498.37
  5245.8  498.17  5246.3  497.67  5263.8  498.17  5282.3  499.22  5295.8  500.01
  5316.5  510.09    5325  511.41  5347.5  506.67  5378.4  505.33  5447.5  510.82
  5543.8  517.59  5568.3  514.52  5618.3  514.95  5652.5  515.54  5765.9  516.28
  5874.4  523.49  5956.1  525.29  6148.3  531.84  6215.3   535.6  6407.4  539.14
#Mann= 14 ,-1 , 0
  3248.4     .05       0  3300.9     .07       0  3341.2     .05       0
  4516.7      .1       0  4723.1     .05       0  4888.4      .1       0
  5245.8     .05       0  5263.8      .1       0  5282.3    .035       0
  5447.5     .05       0  5618.3    .035       0  5652.5     .05       0
  5956.1    .035       0  6148.3     .05       0
Bank Sta=5245.8,5263.8
XS Rating Curve= 0 ,0
Exp/Cntr=0.3,0.1

Type RM Length L Ch R = 1 ,2809    ,659,659,659
BEGIN DESCRIPTION:
X18783
END DESCRIPTION:
XS GIS Cut Line= 4
      2280935.42     13749499.59      2281369.46     13748787.78
      2281386.82      13747841.6      2280857.97     13746688.54
#Sta/Elev= 30
  3603.8  515.21  3634.7  515.13  3794.4  514.73  3882.9  514.76  4480.3  511.92
  4610.3  506.09  4727.6  502.78  4860.4  502.43  4920.4  499.52  4999.7  498.15
  5000.2  497.65  5017.8  498.15  5180.4  500.32  5310.4  509.99  5362.6  512.13
    5614  511.47  5731.3  510.81  5837.3  512.51  5897.2  514.22  6007.9  521.27
  6023.8   522.5  6052.3  521.91  6069.8  523.22  6144.3  523.72  6236.2  526.75
  6287.7  526.48  6333.7  528.66  6522.5   532.5  6604.8  534.38  6652.4  535.33
#Mann= 13 ,-1 , 0
  3603.8     .07       0  3634.7     .05       0  3794.4     .07       0
  3882.9     .05       0  4727.6      .1       0  4999.7     .05       0
  5017.8      .1       0  5362.6    .035       0    5614     .05       0
  5837.3    .035       0  6007.9     .05       0  6522.5    .035       0
  6604.8     .05       0
Bank Sta=4999.7,5017.8
XS Rating Curve= 0 ,0
Exp/Cntr=0.3,0.1

Type RM Length L Ch R = 1 ,2150    ,650,650,650
BEGIN DESCRIPTION:
X18782
END DESCRIPTION:
XS GIS Cut Line= 4
      2281143.76     13749386.74      2282037.86     13748518.68
      2281864.25     13747919.72      2280944.11     13746713.12
#Sta/Elev= 30
  3344.7  514.98    3962  515.71  4334.3  513.25  4538.7  512.73    4569  512.71
  4692.3  510.66  4792.5  504.41    4823  499.03    4830  498.85  4972.7  498.25
  4973.2  497.75  4990.8  498.25  5029.8  499.93  5133.2  508.13  5150.9  508.58
  5241.5  511.61  5368.2  511.59  5494.7  511.58  5496.1  511.59  5531.7  511.54
  5552.5  506.21  5573.3  509.71  5581.6  508.02  5621.5  510.15  5652.4  510.49
  5748.2  507.41  5808.7  504.66  5930.7  511.98  6180.2  526.12  6731.9  533.38
#Mann= 20 ,-1 , 0
  3344.7     .05       0  4334.3    .035       0  4538.7      .1       0
    4569    .035       0    4823      .1       0    4830    .033       0
  4972.7    .033       0  4990.8    .033       0  5029.8    .035       0
  5133.2      .1       0  5150.9     .07       0  5241.5     .05       0
  5368.2     .07       0  5494.7      .1       0  5496.1     .07       0
  5621.5     .12       0  5652.4     .07       0  5748.2     .12       0
  5808.7     .07       0  5930.7     .05       0
Bank Sta=4972.7,4990.8
XS Rating Curve= 0 ,0
Exp/Cntr=0.3,0.1

Type RM Length L Ch R = 1 ,1500    ,533,533,533
BEGIN DESCRIPTION:
X18781
END DESCRIPTION:
XS GIS Cut Line= 3
      2281317.37     13749282.58      2282324.32     13748319.03
      2282610.78     13746582.89
#Sta/Elev= 30
  3011.1  513.91  3354.1  514.95  3410.7  516.04  3446.3  514.41    3843  513.01
    4196   511.9  4351.4  512.57  4503.1   511.3  4517.1  512.25  4616.4  507.81
  4703.9  504.12    4815  500.13  4914.3   498.7  4921.4  498.58  4921.9  498.08
  4940.5  498.58  5006.9  499.03  5027.1  500.15  5053.2  503.39  5135.9  507.78
    5169  508.25  5180.5  510.16  5260.2  512.61  5338.4  512.22    5539  513.14
  5807.5  518.76  5913.9   522.6  6010.2  529.02  6050.8  534.72  6164.4  544.94
#Mann= 12 ,-1 , 0
  3011.1     .05       0    3843    .035       0  4517.1     .12       0
  4616.4      .1       0  4703.9     .12       0    4815      .1       0
  4914.3    .033       0  4921.4    .033       0  4940.5    .033       0
  5135.9      .1       0  5338.4     .07       0    5539    .035       0
Bank Sta=4921.4,4940.5
XS Rating Curve= 0 ,0
Exp/Cntr=0.3,0.1

Type RM Length L Ch R = 1 ,967     ,0,0,0
BEGIN DESCRIPTION:
X18780
END DESCRIPTION:
XS GIS Cut Line= 3
      2281525.74     13749187.06      2282740.98     13748180.14
      2283330.17     13746620.52
#Sta/Elev= 30
  3148.4     515  3305.2  516.09  3391.1   514.2    3862  512.73  4100.9  512.29
  4370.5  506.89  4564.4   507.1  4666.2  507.81  4788.5  505.69  4791.9  505.62
  4885.6  499.69  5001.5  498.02    5002  497.52  5020.6  498.02  5204.8  506.83
  5236.5  510.91  5308.9  511.07  5412.9  506.45  5461.9  503.32    5517  504.36
  5555.2  507.83  5725.1  514.06  5907.4   518.6    6053  526.98  6141.4  529.52
  6175.2  533.09  6193.2  532.87  6245.5  540.84  6349.6  546.83  6393.8  550.65
#Mann= 16 ,-1 , 0
  3148.4     .05       0    3862    .035       0  4564.4    .033       0
  4666.2      .1       0  4788.5    .035       0  4791.9      .1       0
  4885.6    .033       0  5001.5    .033       0  5020.6    .033       0
  5204.8     .12       0  5308.9    .035       0  5412.9     .12       0
  5725.1     .07       0  6141.4     .12       0  6245.5     .07       0
  6349.6     .12       0
Bank Sta=5001.5,5020.6
XS Rating Curve= 0 ,0
Exp/Cntr=0.3,0.1

Chan Stop Cuts=-1
Use User Specified Reach Order=0
Composite Channel Slope=5