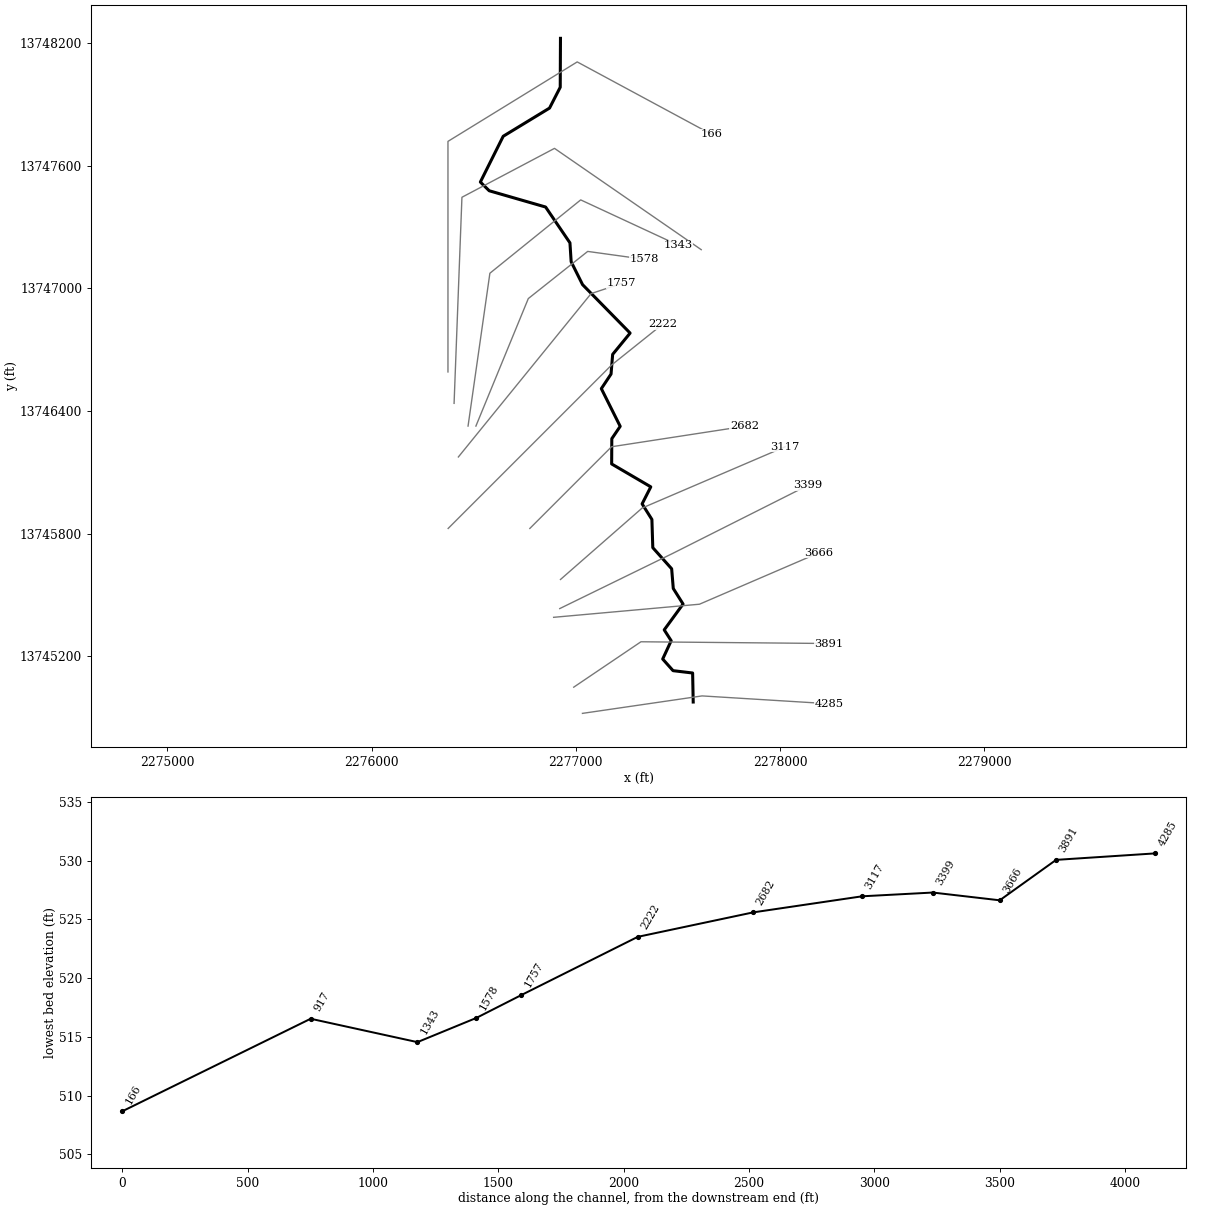
--- DEADMAN TRIBUTARY 3.prj (project) ---

Proj Title=DEADMAN TRIBUTARY 3 Base Level Engineering
Current Plan=p01
Default Exp/Contr=0.3,0.1
English Units
Geom File=g01
Flow File=f01
Plan File=p01
BEGIN DESCRIPTION:
DEADMAN TRIBUTARY 3
END DESCRIPTION:

--- DEADMAN TRIBUTARY 3.p01 (plan) ---

Plan Title=Multiple Run
Short Identifier=Multiple
Geom File=g01
Flow File=f01
Subcritical Flow
K Sum by GR= 0
Std Step Tol= 0.01
Critical Tol= 0.01
Num of Std Step Trials= 20
Max Error Tol= 0.3
Flow Tol Ratio= 0.001
Split Flow NTrial= 30
Split Flow Tol= 0.02
Split Flow Ratio= 0.02
Log Output Level= 0
Friction Slope Method= 1
Unsteady Friction Slope Method= 2
Unsteady Bridges Friction Slope Method= 1
Parabolic Critical Depth
Global Vel Dist=  1 , 1 , 1
Global Log Level= 0
CheckData=True
Encroach Param= -1, 0, 0, 0
BEGIN DESCRIPTION:
Multiple Run
END DESCRIPTION:

--- DEADMAN TRIBUTARY 3.f01 (steady flow) ---

Flow Title=Multiple
Number of Profiles=7
Profile Names=10-year,25-year,50-year,1pct_min,100-year,1pct_plu,500-year
River Rch & RM= DEADMAN TRIBUTAR,Reach-1,4285
     865    1426    1944    1281    2557    5102    4380
Boundary for River Rch & Prof#=DEADMAN TRIBUTAR,Reach-1,1
Up Type=0
Dn Type=3
Dn Slope=0.005
Boundary for River Rch & Prof#=DEADMAN TRIBUTAR,Reach-1,2
Up Type=0
Dn Type=3
Dn Slope=0.005
Boundary for River Rch & Prof#=DEADMAN TRIBUTAR,Reach-1,3
Up Type=0
Dn Type=3
Dn Slope=0.005
Boundary for River Rch & Prof#=DEADMAN TRIBUTAR,Reach-1,4
Up Type=0
Dn Type=3
Dn Slope=0.005
Boundary for River Rch & Prof#=DEADMAN TRIBUTAR,Reach-1,5
Up Type=0
Dn Type=3
Dn Slope=0.005
Boundary for River Rch & Prof#=DEADMAN TRIBUTAR,Reach-1,6
Up Type=0
Dn Type=3
Dn Slope=0.005
Boundary for River Rch & Prof#=DEADMAN TRIBUTAR,Reach-1,7
Up Type=0
Dn Type=3
Dn Slope=0.005

--- DEADMAN TRIBUTARY 3.g01 (geometry) ---

Geom Title=Existing Conditions

River Reach=DEADMAN TRIBUTAR,Reach-1
Reach XY= 30
      2277575.00     13744975.00      2277572.13     13745117.10
      2277476.30     13745128.56      2277425.57     13745185.47
      2277467.16     13745275.09      2277433.01     13745328.33
      2277525.35     13745454.79      2277477.38     13745530.97
      2277469.46     13745627.42      2277377.08     13745730.86
      2277372.70     13745869.07      2277324.79     13745945.21
      2277367.28     13746028.66      2277175.64     13746140.83
      2277176.37     13746264.55      2277217.47     13746325.01
      2277125.09     13746509.60      2277172.62     13746580.97
      2277180.55     13746677.43      2277266.04     13746781.67
      2277033.14     13747018.94      2276977.33     13747130.97
      2276971.38     13747223.50      2276852.19     13747398.95
      2276576.02     13747478.61      2276532.65     13747521.31
      2276644.62     13747745.47      2276871.49     13747883.48
      2276923.81     13747985.48      2276925.00     13748225.00

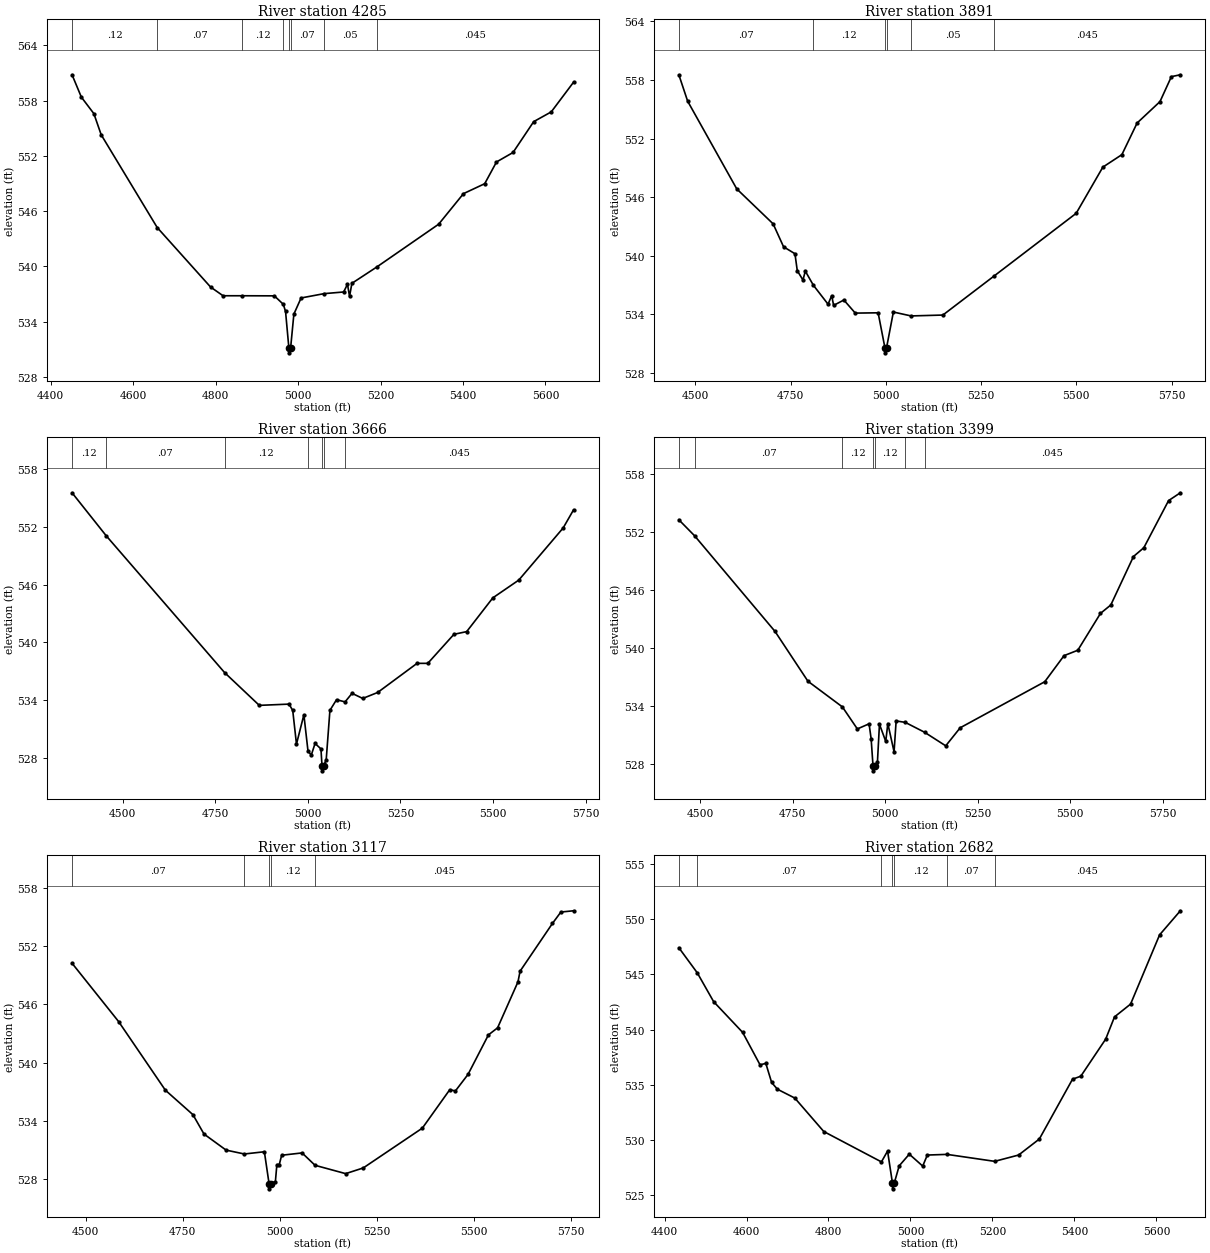
Type RM Length L Ch R = 1,4285,394,394,394
BEGIN DESCRIPTION:
X18790
END DESCRIPTION:
XS GIS Cut Line= 3
      2277032.64     13744919.41      2277618.47     13745004.93
      2278241.44     13744966.53
#Sta/Elev= 30
  4451.8  560.81  4474.4  558.38  4504.7  556.59  4522.5  554.29  4658.3  544.22
  4787.7  537.76  4818.0  536.81  4865.1  536.81  4942.4  536.80  4964.2  535.88
  4969.6  535.10  4977.7  531.11  4978.0  530.61  4981.8  531.11  4989.8  534.82
  5007.3  536.57  5063.2  537.04  5110.5  537.22  5119.8  538.06  5124.8  536.74
  5130.5  538.16  5190.4  539.92  5340.9  544.58  5401.1  547.90  5452.6  548.98
  5481.2  551.34  5521.3  552.37  5571.4  555.72  5614.0  556.78  5668.0  560.00
#Mann=8,-1,0
  4451.8    0.12       0  4658.3    0.07       0  4865.1    0.12       0
  4964.2    0.07       0  4977.7    0.05       0  4981.8    0.07       0
  5063.2    0.05       0  5190.4   0.045       0
Bank Sta=4977.7,4981.8
Exp/Cntr=0.3,0.1

Type RM Length L Ch R = 1,3891,225,225,225
BEGIN DESCRIPTION:
DEADMAN TRIBUTARY 3 6.0
END DESCRIPTION:
XS GIS Cut Line= 3
      2276989.88     13745047.71      2277319.13     13745270.07
      2278238.49     13745261.51
#Sta/Elev= 30
  4456.4  558.53  4479.5  555.83  4608.4  546.85  4703.9  543.27  4731.3  540.92
  4761.2  540.21  4767.3  538.47  4782.2  537.52  4788.4  538.43  4809.6  536.98
  4848.1  535.04  4857.7  535.92  4862.7  534.92  4889.6  535.47  4919.6  534.13
  4979.6  534.16  4997.5  530.56  4997.8  530.06  5001.6  530.56  5019.6  534.24
  5066.0  533.84  5149.6  533.93  5284.1  537.93  5499.6  544.35  5569.6  549.08
  5619.6  550.36  5659.6  553.60  5719.6  555.79  5749.6  558.35  5773.1  558.54
#Mann=6,-1,0
  4456.4    0.07       0  4809.6    0.12       0  4997.5    0.05       0
  5001.6    0.12       0  5066.0    0.05       0  5284.1   0.045       0
Bank Sta=4997.5,5001.6
Exp/Cntr=0.3,0.1

Type RM Length L Ch R = 1,3666,267,267,267
BEGIN DESCRIPTION:
X18791
END DESCRIPTION:
XS GIS Cut Line= 3
      2276891.48     13745389.80      2277605.64     13745453.95
      2278190.75     13745705.93
#Sta/Elev= 30
  4363.5  555.54  4455.7  551.07  4775.4  536.84  4869.1  533.43  4949.4  533.56
  4959.4  532.90  4969.5  529.40  4989.5  532.45  5000.7  528.65  5009.6  528.27
  5019.7  529.47  5035.6  528.90  5038.5  527.12  5038.8  526.62  5042.6  527.12
  5049.8  527.78  5059.8  532.91  5077.7  534.02  5100.7  533.79  5119.5  534.68
  5148.5  534.15  5188.7  534.77  5295.1  537.80  5324.1  537.80  5394.7  540.82
  5429.1  541.10  5499.7  544.61  5569.8  546.46  5689.6  551.88  5717.6  553.76
#Mann=7,-1,0
  4363.5    0.12       0  4455.7    0.07       0  4775.4    0.12       0
  5000.7   0.035       0  5038.5    0.05       0  5042.6   0.035       0
  5100.7   0.045       0
Bank Sta=5038.5,5042.6
Exp/Cntr=0.3,0.1

Type RM Length L Ch R = 1,3399,282,282,282
BEGIN DESCRIPTION:
DEADMAN TRIBUTARY 3 5.0
END DESCRIPTION:
XS GIS Cut Line= 3
      2276921.39     13745432.55      2277473.08     13745701.97
      2278135.92     13746035.53
#Sta/Elev= 30
  4442.2  553.28  4484.6  551.63  4702.2  541.72  4791.2  536.56  4884.4  533.90
  4924.8  531.62  4956.5  532.15  4962.1  530.60  4967.2  527.78  4967.5  527.28
  4971.3  527.78  4979.1  528.16  4984.6  532.11  5001.6  530.33  5007.2  532.18
  5024.1  529.25  5029.7  532.45  5054.3  532.30  5106.4  531.28  5163.8  529.87
  5202.9  531.74  5431.6  536.51  5483.7  539.21  5520.9  539.77  5582.3  543.59
  5610.2  544.46  5671.5  549.48  5699.5  550.39  5766.4  555.27  5798.2  556.08
#Mann=7,-1,0
  4442.2    0.12       0  4484.6    0.07       0  4884.4    0.12       0
  4967.2    0.05       0  4971.3    0.12       0  5054.3   0.035       0
  5106.4   0.045       0
Bank Sta=4967.2,4971.3
Exp/Cntr=0.3,0.1

Type RM Length L Ch R = 1,3117,435,435,435
BEGIN DESCRIPTION:
DEADMAN TRIBUTARY 3 4.0
END DESCRIPTION:
XS GIS Cut Line= 3
      2276925.03     13745575.03      2277325.00     13745925.00
      2278024.96     13746224.98
#Sta/Elev= 30
  4464.7  550.26  4584.7  544.24  4705.3  537.15  4776.4  534.62  4804.9  532.62
  4861.9  530.96  4908.9  530.56  4960.6  530.79  4972.8  527.46  4973.0  526.96
  4976.9  527.46  4989.0  527.71  4992.8  529.46  4998.9  529.46  5005.2  530.43
  5057.8  530.67  5091.3  529.39  5170.2  528.53  5215.6  529.12  5367.9  533.23
  5438.6  537.20  5453.1  537.07  5485.7  538.78  5538.3  542.86  5561.9  543.59
  5614.5  548.34  5619.9  549.44  5703.3  554.37  5725.1  555.55  5757.7  555.68
#Mann=5,-1,0
  4464.7    0.07       0  4908.9    0.12       0  4972.8    0.05       0
  4976.9    0.12       0  5091.3   0.045       0
Bank Sta=4972.8,4976.9
Exp/Cntr=0.3,0.1

Type RM Length L Ch R = 1,2682,460,460,460
BEGIN DESCRIPTION:
DEADMAN TRIBUTARY 3 3.0
END DESCRIPTION:
XS GIS Cut Line= 3
      2276775.01     13745825.01      2277175.00     13746225.00
      2277824.98     13746325.00
#Sta/Elev= 30
  4435.0  547.42  4479.9  545.15  4519.8  542.54  4590.5  539.76  4633.0  536.82
  4647.1  536.95  4661.3  535.22  4675.4  534.61  4717.8  533.81  4788.5  530.78
  4929.1  528.03  4944.1  529.01  4956.1  526.09  4956.4  525.59  4960.3  526.09
  4972.4  527.67  4997.1  528.73  5029.8  527.65  5041.1  528.65  5089.1  528.71
  5205.3  528.08  5263.7  528.65  5314.3  530.10  5395.3  535.52  5415.5  535.79
  5476.2  539.15  5497.7  541.16  5536.9  542.32  5607.7  548.59  5658.3  550.77
#Mann=7,-1,0
  4435.0    0.12       0  4479.9    0.07       0  4929.1    0.12       0
  4956.1    0.05       0  4960.3    0.12       0  5089.1    0.07       0
  5205.3   0.045       0
Bank Sta=4956.1,4960.3
Exp/Cntr=0.3,0.1

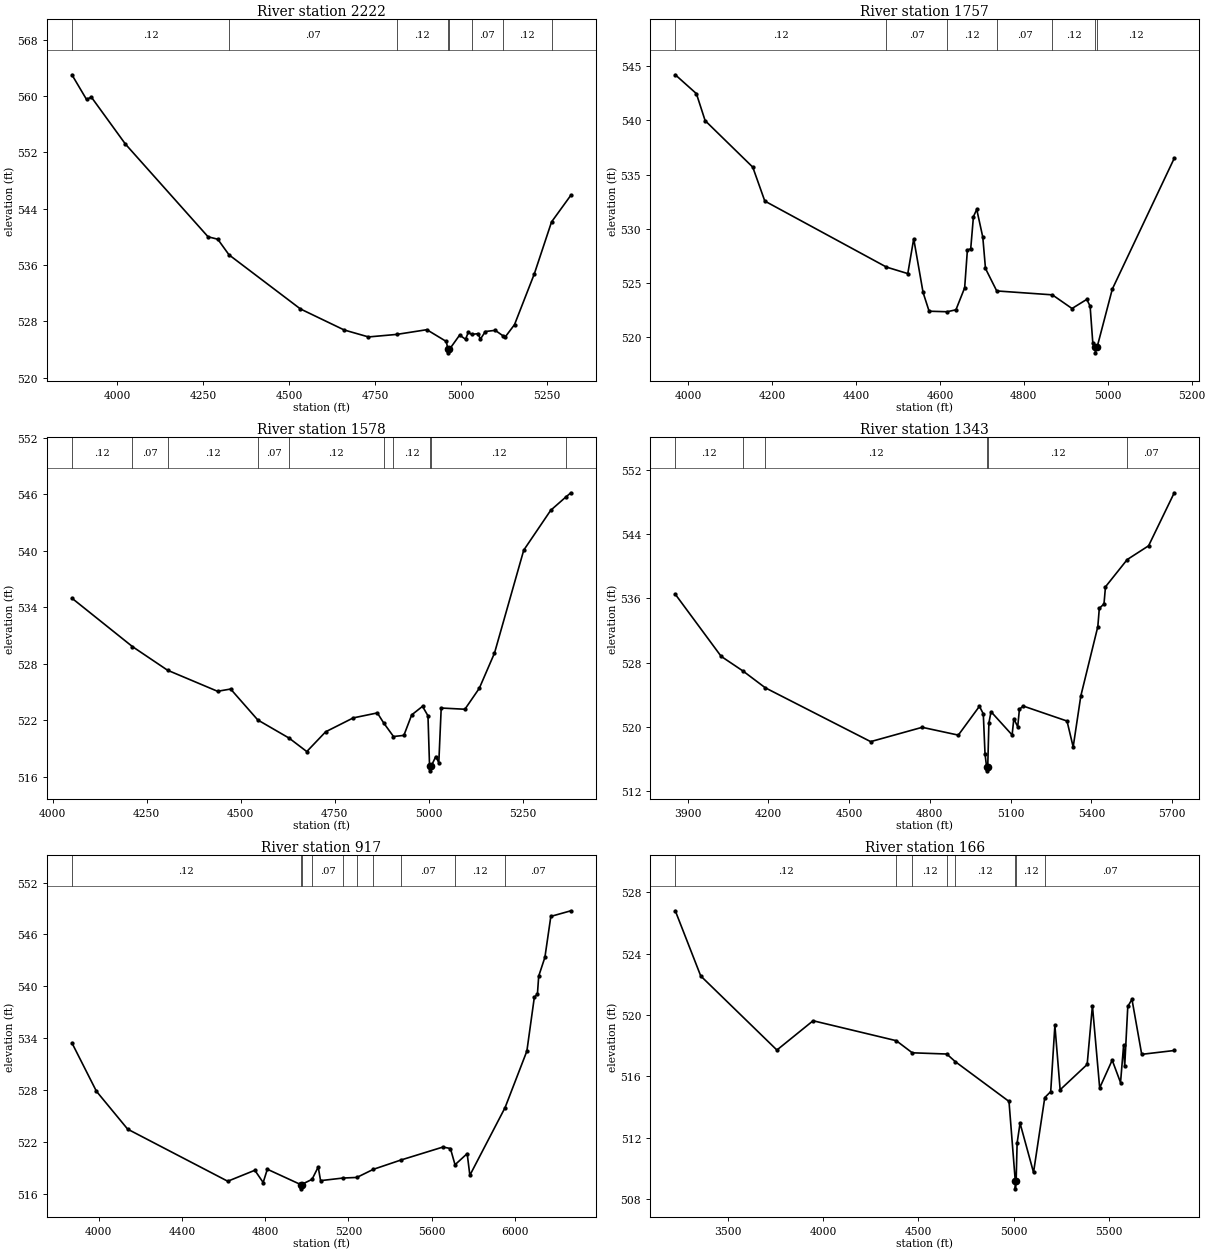
Type RM Length L Ch R = 1,2222,465,465,465
BEGIN DESCRIPTION:
DEADMAN TRIBUTARY 3 2.0
END DESCRIPTION:
XS GIS Cut Line= 3
      2276375.00     13745825.00      2277175.00     13746625.00
      2277424.98     13746824.98
#Sta/Elev= 30
  3868.7  563.04  3911.1  559.54  3925.3  559.86  4024.3  553.19  4264.7  540.01
  4293.0  539.66  4325.7  537.44  4533.4  529.75  4660.7  526.76  4731.4  525.77
  4813.5  526.13  4901.1  526.80  4957.6  525.13  4962.6  524.01  4962.9  523.51
  4966.9  524.01  4996.5  526.03  5013.7  525.44  5021.7  526.42  5031.3  526.13
  5050.5  526.24  5056.9  525.45  5071.3  526.54  5100.1  526.71  5121.5  525.97
  5128.1  525.70  5156.2  527.52  5213.8  534.74  5263.9  542.12  5320.2  545.92
#Mann=8,-1,0
  3868.7    0.12       0  4325.7    0.07       0  4813.5    0.12       0
  4962.6    0.05       0  4966.9    0.12       0  5031.3    0.07       0
  5121.5    0.12       0  5263.9    0.07       0
Bank Sta=4962.6,4966.9
Exp/Cntr=0.3,0.1

Type RM Length L Ch R = 1,1757,179,179,179
BEGIN DESCRIPTION:
DEADMAN TRIBUTARY 3 1.0
END DESCRIPTION:
XS GIS Cut Line= 3
      2276425.02     13746175.02      2277075.00     13746975.00
      2277225.04     13747025.01
#Sta/Elev= 30
  3969.5  544.20  4019.8  542.46  4040.6  539.97  4154.1  535.68  4182.8  532.55
  4472.7  526.46  4523.5  525.86  4537.6  529.07  4559.9  524.12  4574.3  522.39
  4617.0  522.34  4638.2  522.52  4659.0  524.55  4665.5  528.04  4673.4  528.14
  4679.9  531.12  4687.8  531.78  4702.2  529.22  4708.6  526.33  4735.4  524.26
  4867.9  523.90  4914.8  522.64  4949.9  523.48  4957.9  522.86  4964.3  519.47
  4970.1  519.05  4970.4  518.55  4974.4  519.05  5010.8  524.43  5158.4  536.50
#Mann=7,-1,0
  3969.5    0.12       0  4472.7    0.07       0  4617.0    0.12       0
  4735.4    0.07       0  4867.9    0.12       0  4970.1    0.05       0
  4974.4    0.12       0
Bank Sta=4970.1,4974.4
Exp/Cntr=0.3,0.1

Type RM Length L Ch R = 1,1578,235,235,235
BEGIN DESCRIPTION:
X18792
END DESCRIPTION:
XS GIS Cut Line= 4
      2276510.90     13746326.31      2276767.48     13746950.66
      2277058.27     13747181.58      2277336.28     13747143.09
#Sta/Elev= 30
  4051.2  534.97  4212.2  529.82  4305.5  527.31  4438.5  525.07  4473.3  525.31
  4545.5  522.02  4628.8  520.09  4675.8  518.66  4725.9  520.76  4799.4  522.24
  4863.5  522.77  4880.0  521.72  4906.4  520.26  4934.0  520.38  4954.8  522.56
  4983.6  523.47  4998.1  522.46  5002.3  517.11  5002.6  516.61  5006.6  517.11
  5018.9  518.13  5026.9  517.47  5033.3  523.29  5096.3  523.16  5134.6  525.39
  5175.0  529.13  5252.8  540.08  5324.6  544.32  5365.9  545.77  5378.2  546.18
#Mann=10,-1,0
  4051.2    0.12       0  4212.2    0.07       0  4305.5    0.12       0
  4545.5    0.07       0  4628.8    0.12       0  4880.0    0.07       0
  4906.4    0.12       0  5002.3    0.05       0  5006.6    0.12       0
  5365.9    0.07       0
Bank Sta=5002.3,5006.6
Exp/Cntr=0.3,0.1

Type RM Length L Ch R = 1,1343,426,426,426
BEGIN DESCRIPTION:
X18789
END DESCRIPTION:
XS GIS Cut Line= 4
      2276472.41     13746326.28      2276579.33     13747074.67
      2277024.06     13747433.88      2277501.53     13747212.20
#Sta/Elev= 30
  3854.0  536.50  4024.4  528.78  4105.9  526.95  4188.5  524.87  4580.0  518.18
  4771.4  519.96  4905.7  518.99  4984.1  522.57  4998.5  521.64  5004.9  516.67
  5010.7  515.05  5011.0  514.55  5015.0  515.05  5019.3  520.49  5027.2  521.90
  5105.6  519.01  5112.0  521.03  5126.4  520.03  5132.8  522.22  5147.2  522.60
  5309.6  520.74  5332.5  517.52  5360.9  523.86  5424.1  532.48  5429.6  534.75
  5447.0  535.29  5452.5  537.42  5533.3  540.81  5612.7  542.52  5708.1  549.11
#Mann=6,-1,0
  3854.0    0.12       0  4105.9    0.07       0  4188.5    0.12       0
  5010.7    0.05       0  5015.0    0.12       0  5533.3    0.07       0
Bank Sta=5010.7,5015
Exp/Cntr=0.3,0.1

Type RM Length L Ch R = 1,917,751,751,751
BEGIN DESCRIPTION:
X18788
END DESCRIPTION:
XS GIS Cut Line= 4
      2276404.00     13746437.48      2276442.48     13747446.71
      2276895.77     13747686.18      2277614.23     13747190.11
#Sta/Elev= 30
  3872.2  533.44  3989.8  527.84  4139.9  523.45  4620.3  517.42  4750.4  518.69
  4790.4  517.27  4810.4  518.81  4970.1  517.04  4970.4  516.54  4974.5  517.04
  5025.1  517.64  5054.7  519.07  5066.0  517.49  5173.6  517.79  5240.1  517.86
  5319.5  518.80  5450.8  519.87  5653.6  521.38  5689.5  521.21  5711.6  519.33
  5769.9  520.62  5782.8  518.11  5951.9  525.95  6056.5  532.49  6092.4  538.73
  6107.2  539.09  6113.3  541.17  6143.1  543.35  6171.6  548.09  6267.9  548.74
#Mann=10,-1,0
  3872.2    0.12       0  4970.1    0.05       0  4974.5    0.12       0
  5025.1    0.07       0  5173.6    0.12       0  5240.1    0.07       0
  5319.5    0.12       0  5450.8    0.07       0  5711.6    0.12       0
  5951.9    0.07       0
Bank Sta=4970.1,4974.5
Exp/Cntr=0.3,0.1

Type RM Length L Ch R = 1,166,0,0,0
BEGIN DESCRIPTION:
X18787
END DESCRIPTION:
XS GIS Cut Line= 4
      2276374.06     13746591.42      2276374.06     13747720.39
      2277006.96     13748109.54      2277665.47     13747754.62
#Sta/Elev= 30
  3224.1  526.80  3357.7  522.55  3757.7  517.72  3947.7  519.63  4384.3  518.33
  4468.4  517.54  4649.6  517.46  4694.6  516.96  4976.3  514.37  5009.4  509.17
  5009.7  508.67  5013.8  509.17  5019.0  511.66  5034.4  512.95  5105.2  509.74
  5164.2  514.62  5195.4  515.01  5217.3  519.33  5244.9  515.13  5386.8  516.78
  5414.4  520.61  5452.5  515.25  5518.2  517.06  5562.0  515.60  5578.2  518.04
  5583.9  516.67  5600.1  520.56  5622.0  521.03  5673.2  517.44  5844.1  517.69
#Mann=8,-1,0
  3224.1    0.12       0  4384.3    0.07       0  4468.4    0.12       0
  4649.6    0.07       0  4694.6    0.12       0  5009.4    0.05       0
  5013.8    0.12       0  5164.2    0.07       0
Bank Sta=5009.4,5013.8
Exp/Cntr=0.3,0.1

Chan Stop Cuts=-1