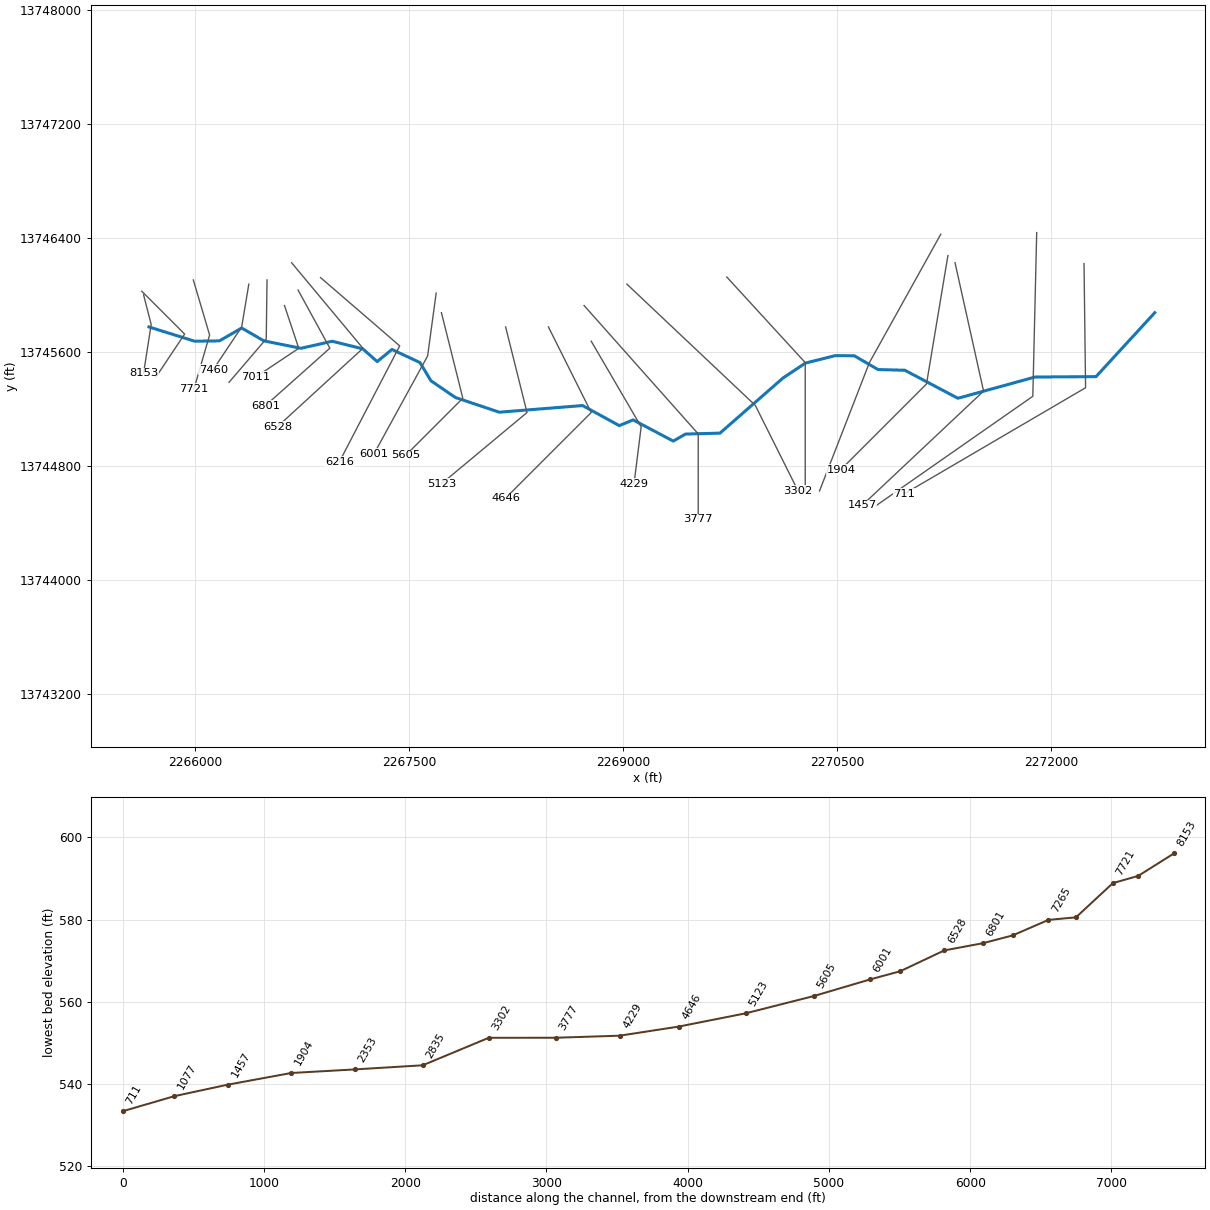
--- DEADMAN TRIBUTARY 6.prj (project) ---

Proj Title=DEADMAN TRIBUTARY 6 Base Level Engineering
Current Plan=p01
Default Exp/Contr=0.3,0.1
English Units
Geom File=g01
Flow File=f01
Plan File=p01
BEGIN DESCRIPTION:
DEADMAN TRIBUTARY 6
END DESCRIPTION:

--- DEADMAN TRIBUTARY 6.p01 (plan) ---

Plan Title=Multiple Run
Short Identifier=Multiple
Geom File=g01
Flow File=f01
Subcritical Flow
K Sum by GR= 0
Std Step Tol= 0.01
Critical Tol= 0.01
Num of Std Step Trials= 20
Max Error Tol= 0.3
Flow Tol Ratio= 0.001
Split Flow NTrial= 30
Split Flow Tol= 0.02
Split Flow Ratio= 0.02
Log Output Level= 0
Friction Slope Method= 1
Unsteady Friction Slope Method= 2
Unsteady Bridges Friction Slope Method= 1
Parabolic Critical Depth
Global Vel Dist=  1 , 1 , 1
Global Log Level= 0
CheckData=True
Encroach Param= -1, 0, 0, 0
BEGIN DESCRIPTION:
Multiple Run
END DESCRIPTION:

--- DEADMAN TRIBUTARY 6.f01 (steady flow) ---

Flow Title=Multiple
Number of Profiles=7
Profile Names=10-year,25-year,50-year,1pct_min,100-year,1pct_plu,500-year
River Rch & RM= DEADMAN TRIBUTAR,Reach-1,8153
     137     201     253     155     310     618     458
River Rch & RM= DEADMAN TRIBUTAR,Reach-1,6001
     621    1001    1343     873    1743    3477    2902
Boundary for River Rch & Prof#=DEADMAN TRIBUTAR,Reach-1,1
Up Type=0
Dn Type=3
Dn Slope=0.005
Boundary for River Rch & Prof#=DEADMAN TRIBUTAR,Reach-1,2
Up Type=0
Dn Type=3
Dn Slope=0.005
Boundary for River Rch & Prof#=DEADMAN TRIBUTAR,Reach-1,3
Up Type=0
Dn Type=3
Dn Slope=0.005
Boundary for River Rch & Prof#=DEADMAN TRIBUTAR,Reach-1,4
Up Type=0
Dn Type=3
Dn Slope=0.005
Boundary for River Rch & Prof#=DEADMAN TRIBUTAR,Reach-1,5
Up Type=0
Dn Type=3
Dn Slope=0.005
Boundary for River Rch & Prof#=DEADMAN TRIBUTAR,Reach-1,6
Up Type=0
Dn Type=3
Dn Slope=0.005
Boundary for River Rch & Prof#=DEADMAN TRIBUTAR,Reach-1,7
Up Type=0
Dn Type=3
Dn Slope=0.005

--- DEADMAN TRIBUTARY 6.g01 (geometry) ---

Geom Title=Existing Conditions

River Reach=DEADMAN TRIBUTAR,Reach-1
Reach XY= 30
      2265675.00     13745775.00      2265995.03     13745675.07
      2266169.07     13745677.24      2266325.00     13745767.50
      2266480.93     13745677.24      2266740.27     13745625.38
      2266959.73     13745674.62      2267173.53     13745621.43
      2267275.00     13745532.11      2267378.23     13745617.15
      2267575.00     13745525.00      2267651.14     13745397.84
      2267822.58     13745280.54      2268130.94     13745177.26
      2268714.50     13745223.80      2268971.69     13745083.07
      2269068.95     13745123.33      2269350.00     13744974.60
      2269435.50     13745023.76      2269677.45     13745030.46
      2270118.95     13745416.84      2270276.47     13745521.45
      2270485.51     13745573.79      2270619.07     13745572.77
      2270785.50     13745476.20      2270973.45     13745471.25
      2271345.09     13745274.89      2271885.50     13745423.78
      2272313.17     13745426.62      2272725.00     13745875.00

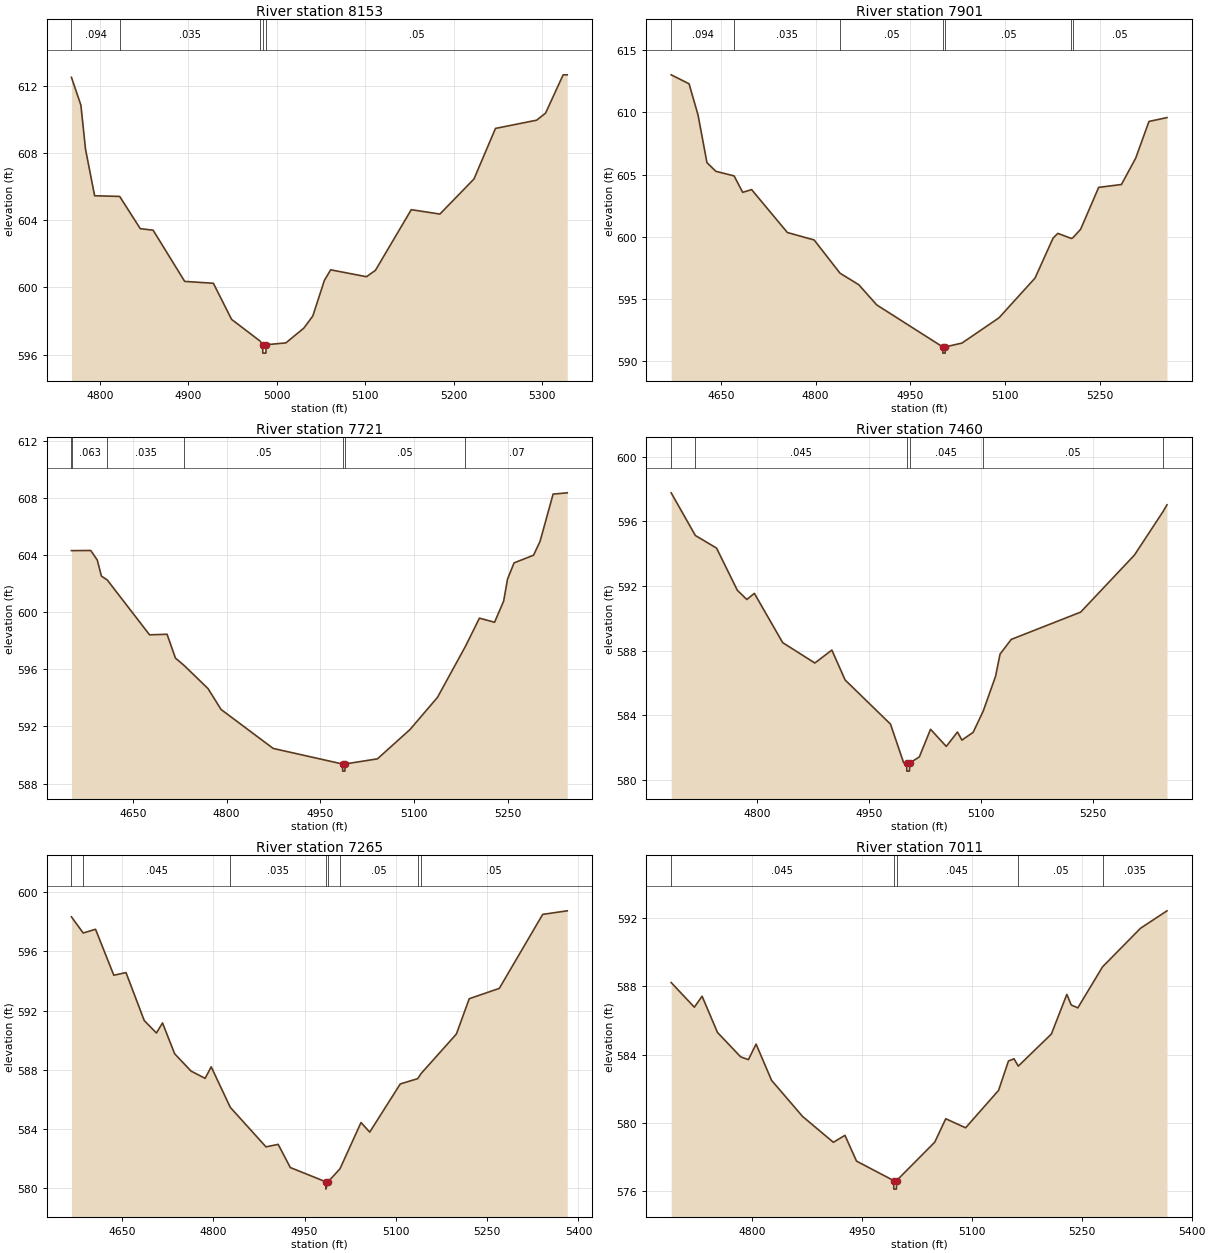
Type RM Length L Ch R = 1,8153,252,252,252
BEGIN DESCRIPTION:
X18800
END DESCRIPTION:
XS GIS Cut Line= 3
      2265637.35     13746000.39      2265690.64     13745792.23
      2265637.35     13745450.84
#Sta/Elev= 30
  4767.8  612.51  4778.5  610.85  4783.7  608.23  4794.0  605.46  4822.3  605.42
  4845.6  603.50  4860.1  603.41  4895.8  600.36  4928.2  600.25  4948.8  598.10
  4981.2  596.80  4983.9  596.59  4984.1  596.09  4987.6  596.09  4987.9  596.59
  5010.2  596.70  5030.5  597.58  5040.6  598.30  5053.7  600.42  5060.8  601.05
  5101.3  600.64  5111.4  601.02  5151.9  604.63  5184.3  604.37  5222.8  606.46
  5247.1  609.47  5293.6  609.96  5303.7  610.38  5323.6  612.66  5328.2  612.66
#Mann=5,-1,0
  4767.8   0.094       0  4822.3   0.035       0  4981.2    0.05       0
  4983.9    0.05       0  4987.9    0.05       0
Bank Sta=4983.9,4987.9
Exp/Cntr=0.3,0.1

Type RM Length L Ch R = 1,7901,180,180,180
BEGIN DESCRIPTION:
DEADMAN TRIBUTARY 6 14.0
END DESCRIPTION:
XS GIS Cut Line= 3
      2265624.98     13746025.02      2265925.00     13745725.00
      2265725.03     13745425.04
#Sta/Elev= 30
  4571.4  613.02  4599.7  612.30  4613.9  609.79  4628.0  605.96  4642.1  605.26
  4671.0  604.89  4684.6  603.57  4698.7  603.79  4755.3  600.34  4797.7  599.74
  4838.6  597.07  4868.4  596.14  4896.7  594.52  5001.2  591.14  5001.5  590.64
  5005.0  590.64  5005.2  591.14  5031.7  591.45  5090.3  593.48  5147.4  596.68
  5176.0  599.90  5183.5  600.27  5204.9  599.86  5207.2  599.92  5219.5  600.60
  5248.1  603.97  5284.1  604.20  5306.7  606.32  5327.7  609.27  5356.2  609.58
#Mann=7,-1,0
  4571.4   0.094       0  4671.0   0.035       0  4838.6    0.05       0
  5001.2    0.05       0  5005.2    0.05       0  5204.9    0.07       0
  5207.2    0.05       0
Bank Sta=5001.2,5005.2
Exp/Cntr=0.3,0.1

Type RM Length L Ch R = 1,7721,261,261,261
BEGIN DESCRIPTION:
X18799
END DESCRIPTION:
XS GIS Cut Line= 3
      2265985.97     13746104.59      2266100.18     13745718.47
      2265991.42     13745343.26
#Sta/Elev= 30
  4551.9  604.32  4553.1  604.32  4582.8  604.33  4593.2  603.66  4599.9  602.53
  4609.1  602.27  4676.9  598.42  4704.9  598.46  4718.3  596.79  4732.3  596.27
  4770.5  594.65  4791.3  593.19  4874.7  590.46  4985.6  589.37  4985.9  588.87
  4989.4  588.87  4989.6  589.37  5041.5  589.73  5093.5  591.78  5137.6  594.04
  5182.4  597.62  5204.7  599.59  5228.9  599.30  5243.5  600.79  5249.7  602.33
  5260.1  603.46  5291.3  604.00  5301.7  604.97  5322.6  608.28  5345.2  608.37
#Mann=7,-1,0
  4551.9   0.094       0  4553.1   0.063       0  4609.1   0.035       0
  4732.3    0.05       0  4985.6    0.05       0  4989.6    0.05       0
  5182.4    0.07       0
Bank Sta=4985.6,4989.6
Exp/Cntr=0.3,0.1

Type RM Length L Ch R = 1,7460,195,195,195
BEGIN DESCRIPTION:
DEADMAN TRIBUTARY 6 13.0
END DESCRIPTION:
XS GIS Cut Line= 3
      2266375.00     13746075.01      2266325.00     13745775.00
      2266125.00     13745475.01
#Sta/Elev= 30
  4684.8  597.76  4717.2  595.12  4745.6  594.34  4773.5  591.73  4786.2  591.16
  4796.3  591.54  4834.3  588.49  4877.4  587.23  4900.2  588.03  4918.0  586.18
  4978.8  583.45  4996.5  581.05  5000.5  581.04  5000.7  580.54  5004.2  580.54
  5004.5  581.04  5017.5  581.42  5032.5  583.13  5053.6  582.07  5068.6  582.96
  5074.6  582.46  5089.6  582.94  5103.0  584.24  5119.7  586.41  5125.7  587.78
  5140.7  588.69  5233.8  590.38  5305.9  593.91  5344.5  596.62  5349.5  597.02
#Mann=6,-1,0
  4684.8   0.035       0  4717.2   0.045       0  5000.5   0.045       0
  5004.5   0.045       0  5103.0    0.05       0  5344.5    0.07       0
Bank Sta=5000.5,5004.5
Exp/Cntr=0.3,0.1

Type RM Length L Ch R = 1,7265,254,254,254
BEGIN DESCRIPTION:
X18798
END DESCRIPTION:
XS GIS Cut Line= 3
      2266502.61     13746104.60      2266497.17     13745691.27
      2266236.11     13745386.71
#Sta/Elev= 30
  4567.1  598.34  4586.4  597.25  4606.7  597.50  4636.7  594.39  4656.7  594.57
  4686.7  591.32  4706.7  590.48  4716.7  591.16  4736.7  589.07  4763.6  587.90
  4786.7  587.41  4796.7  588.19  4828.0  585.45  4886.7  582.77  4906.7  582.94
  4926.7  581.37  4984.8  580.41  4985.1  579.91  4988.8  580.41  5008.3  581.29
  5042.8  584.42  5057.1  583.77  5107.3  587.03  5136.0  587.39  5141.4  587.73
  5199.5  590.41  5220.6  592.80  5270.0  593.50  5341.3  598.51  5381.6  598.75
#Mann=8,-1,0
  4567.1   0.035       0  4586.4   0.045       0  4828.0   0.035       0
  4984.8   0.035       0  4988.8   0.035       0  5008.3    0.05       0
  5136.0   0.035       0  5141.4    0.05       0
Bank Sta=4984.8,4988.8
Exp/Cntr=0.3,0.1

Type RM Length L Ch R = 1,7011,210,210,210
BEGIN DESCRIPTION:
DEADMAN TRIBUTARY 6 12.0
END DESCRIPTION:
XS GIS Cut Line= 3
      2266625.00     13745925.00      2266725.00     13745625.00
      2266424.98     13745424.99
#Sta/Elev= 30
  4689.5  588.21  4721.1  586.77  4731.7  587.41  4752.7  585.29  4784.4  583.86
  4794.9  583.70  4805.4  584.61  4826.5  582.49  4868.7  580.38  4910.9  578.86
  4926.7  579.27  4942.5  577.76  4993.2  576.62  4993.4  576.12  4996.9  576.12
  4997.2  576.62  5049.3  578.87  5064.3  580.24  5091.4  579.71  5136.4  581.90
  5149.9  583.62  5157.5  583.75  5163.3  583.32  5208.5  585.20  5229.6  587.52
  5235.6  586.90  5244.6  586.73  5278.3  589.13  5330.2  591.39  5366.3  592.41
#Mann=5,-1,0
  4689.5   0.045       0  4993.2   0.045       0  4997.2   0.045       0
  5163.3    0.05       0  5278.3   0.035       0
Bank Sta=4993.2,4997.2
Exp/Cntr=0.3,0.1

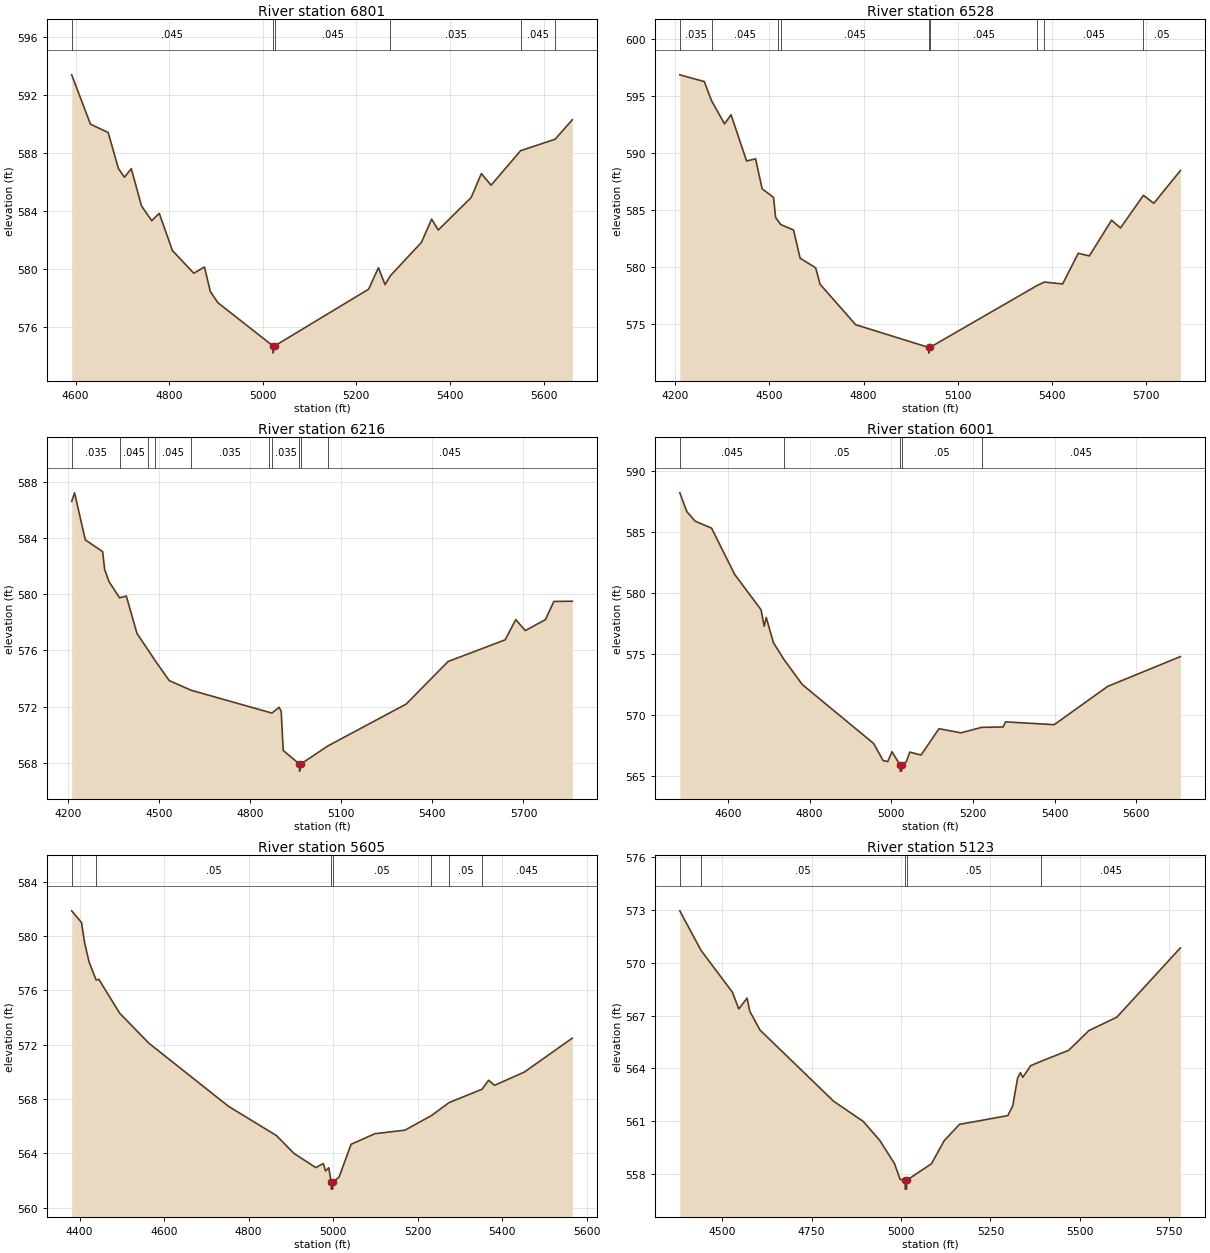
Type RM Length L Ch R = 1,6801,273,273,273
BEGIN DESCRIPTION:
X18797
END DESCRIPTION:
XS GIS Cut Line= 3
      2266720.12     13746033.93      2266943.11     13745626.01
      2266491.74     13745223.59
#Sta/Elev= 30
  4591.8  593.42  4631.9  590.02  4669.8  589.44  4691.6  586.96  4704.5  586.36
  4719.1  586.95  4741.0  584.38  4762.8  583.36  4778.9  583.87  4807.1  581.30
  4852.7  579.74  4875.5  580.17  4888.0  578.48  4904.1  577.71  5021.7  574.73
  5021.9  574.23  5025.7  574.73  5226.3  578.64  5247.2  580.12  5261.4  578.95
  5272.8  579.57  5339.2  581.87  5360.9  583.47  5375.1  582.72  5445.4  584.96
  5467.1  586.61  5488.0  585.81  5551.0  588.19  5624.8  588.98  5661.4  590.32
#Mann=6,-1,0
  4591.8   0.045       0  5021.7   0.045       0  5025.7   0.045       0
  5272.8   0.035       0  5551.0   0.045       0  5624.8    0.05       0
Bank Sta=5021.7,5025.7
Exp/Cntr=0.3,0.1

Type RM Length L Ch R = 1,6528,312,312,312
BEGIN DESCRIPTION:
DEADMAN TRIBUTARY 6 11.0
END DESCRIPTION:
XS GIS Cut Line= 3
      2266675.01     13746224.99      2267175.00     13745625.00
      2266575.03     13745075.03
#Sta/Elev= 30
  4214.6  596.87  4292.7  596.28  4315.8  594.60  4357.1  592.57  4377.9  593.37
  4427.4  589.32  4456.0  589.51  4476.9  586.88  4513.3  586.13  4519.8  584.38
  4528.6  584.03  4536.9  583.74  4577.1  583.27  4597.9  580.80  4647.4  579.96
  4661.7  578.51  4775.0  574.97  5007.5  572.98  5007.7  572.48  5011.5  572.98
  5352.6  578.40  5376.3  578.71  5434.3  578.54  5484.0  581.23  5519.4  581.00
  5590.3  584.13  5618.7  583.45  5691.6  586.31  5724.8  585.61  5809.5  588.48
#Mann=9,-1,0
  4214.6   0.035       0  4315.8   0.045       0  4528.6   0.035       0
  4536.9   0.045       0  5007.5   0.045       0  5011.5   0.045       0
  5352.6   0.035       0  5376.3   0.045       0  5691.6    0.05       0
Bank Sta=5007.5,5011.5
Exp/Cntr=0.3,0.1

Type RM Length L Ch R = 1,6216,215,215,215
BEGIN DESCRIPTION:
X18796
END DESCRIPTION:
XS GIS Cut Line= 3
      2266877.87     13746120.88      2267432.56     13745642.33
      2267010.09     13744829.90
#Sta/Elev= 30
  4212.5  586.60  4221.9  587.21  4257.4  583.86  4314.4  583.03  4321.0  581.76
  4335.2  580.90  4370.1  579.74  4392.3  579.87  4427.4  577.21  4463.4  576.05
  4488.3  575.24  4533.8  573.85  4604.9  573.17  4862.0  571.60  4871.8  571.54
  4895.5  571.95  4902.4  571.66  4909.0  568.88  4962.6  567.91  4962.9  567.41
  4966.6  567.91  5055.9  569.20  5313.8  572.18  5452.0  575.21  5639.8  576.75
  5674.7  578.19  5706.1  577.41  5772.4  578.19  5800.2  579.48  5860.8  579.50
#Mann=10,-1,0
  4212.5   0.035       0  4370.1   0.045       0  4463.4   0.035       0
  4488.3   0.045       0  4604.9   0.035       0  4862.0   0.045       0
  4871.8   0.035       0  4962.6   0.035       0  4966.6   0.035       0
  5055.9   0.045       0
Bank Sta=4962.6,4966.6
Exp/Cntr=0.3,0.1

Type RM Length L Ch R = 1,6001,396,396,396
BEGIN DESCRIPTION:
X18795
END DESCRIPTION:
XS GIS Cut Line= 3
      2267688.16     13746012.17      2267628.33     13745571.63
      2267253.10     13744886.43
#Sta/Elev= 30
  4482.3  588.21  4499.6  586.67  4519.8  585.89  4560.2  585.31  4616.5  581.53
  4681.3  578.62  4688.9  577.27  4694.0  577.99  4711.6  575.92  4737.7  574.53
  4782.2  572.49  4957.2  567.65  4980.1  566.26  4991.5  566.17  5001.9  566.98
  5021.7  565.89  5022.0  565.39  5025.5  565.39  5025.7  565.89  5037.1  566.17
  5045.5  566.95  5073.1  566.71  5116.9  568.87  5170.7  568.53  5221.6  568.98
  5274.1  569.01  5279.8  569.43  5399.2  569.20  5530.1  572.34  5708.1  574.78
#Mann=5,-1,0
  4482.3   0.045       0  4737.7    0.05       0  5021.7    0.05       0
  5025.7    0.05       0  5221.6   0.045       0
Bank Sta=5021.7,5025.7
Exp/Cntr=0.3,0.1

Type RM Length L Ch R = 1,5605,482,482,482
BEGIN DESCRIPTION:
DEADMAN TRIBUTARY 6 10.0
END DESCRIPTION:
XS GIS Cut Line= 3
      2267725.00     13745874.98      2267875.00     13745275.00
      2267475.02     13744875.02
#Sta/Elev= 30
  4381.5  581.85  4404.7  580.99  4412.4  579.45  4422.7  578.08  4439.1  576.77
  4445.9  576.80  4494.9  574.32  4564.4  572.10  4752.6  567.46  4865.9  565.31
  4907.2  564.00  4958.7  562.96  4976.8  563.25  4981.9  562.71  4989.6  562.94
  4995.4  561.87  4995.6  561.37  4999.1  561.37  4999.4  561.87  5014.1  562.27
  5042.4  564.67  5098.9  565.45  5169.7  565.71  5232.4  566.78  5274.3  567.74
  5352.1  568.72  5367.6  569.38  5381.8  569.01  5452.5  569.99  5565.6  572.48
#Mann=7,-1,0
  4381.5   0.045       0  4439.1    0.05       0  4995.4    0.05       0
  4999.4    0.05       0  5232.4   0.045       0  5274.3    0.05       0
  5352.1   0.045       0
Bank Sta=4995.4,4999.4
Exp/Cntr=0.3,0.1

Type RM Length L Ch R = 1,5123,477,477,477
BEGIN DESCRIPTION:
DEADMAN TRIBUTARY 6 9.0
END DESCRIPTION:
XS GIS Cut Line= 3
      2268175.00     13745775.00      2268325.00     13745175.00
      2267724.99     13744674.99
#Sta/Elev= 30
  4381.5  572.94  4440.8  570.70  4528.4  568.33  4546.4  567.38  4569.6  567.99
  4577.3  567.24  4605.7  566.18  4811.8  562.14  4894.3  561.00  4940.7  559.92
  4981.9  558.60  4997.4  557.71  5011.6  557.66  5011.9  557.16  5015.4  557.16
  5015.6  557.66  5085.2  558.60  5120.4  559.90  5163.3  560.83  5298.7  561.33
  5312.4  561.89  5326.0  563.47  5333.8  563.77  5340.4  563.50  5362.5  564.16
  5391.7  564.41  5468.6  565.03  5525.2  566.15  5603.3  566.91  5781.0  570.84
#Mann=5,-1,0
  4381.5   0.035       0  4440.8    0.05       0  5011.6    0.05       0
  5015.6    0.05       0  5391.7   0.045       0
Bank Sta=5011.6,5015.6
Exp/Cntr=0.3,0.1

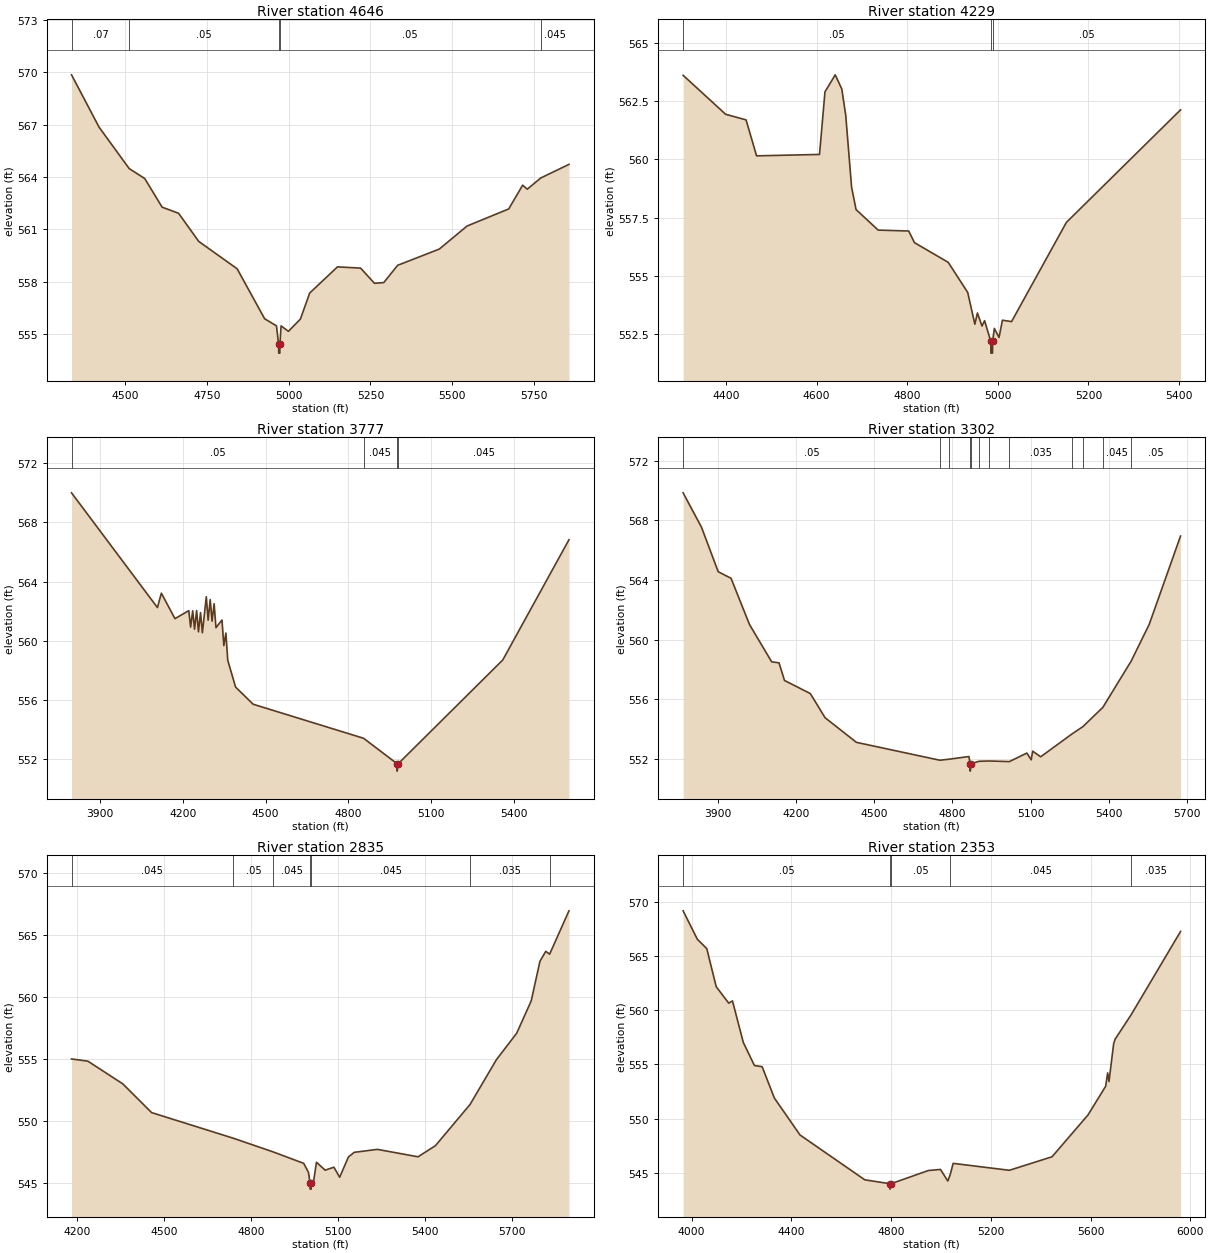
Type RM Length L Ch R = 1,4646,417,417,417
BEGIN DESCRIPTION:
DEADMAN TRIBUTARY 6 8.0
END DESCRIPTION:
XS GIS Cut Line= 3
      2268474.99     13745775.02      2268775.00     13745175.00
      2268174.98     13744574.98
#Sta/Elev= 30
  4336.9  569.85  4420.8  566.86  4513.0  564.48  4560.5  563.91  4613.6  562.27
  4663.9  561.92  4725.4  560.31  4842.8  558.74  4926.7  555.88  4963.0  555.47
  4969.4  554.41  4969.7  553.91  4973.2  553.91  4973.4  554.41  4977.0  555.47
  4999.4  555.16  5036.0  555.86  5064.3  557.35  5149.2  558.85  5219.9  558.78
  5262.3  557.91  5290.6  557.95  5333.0  558.94  5460.3  559.87  5545.1  561.19
  5672.4  562.17  5714.9  563.53  5729.0  563.30  5770.0  563.94  5856.3  564.72
#Mann=5,-1,0
  4336.9    0.07       0  4513.0    0.05       0  4969.4    0.05       0
  4973.4    0.05       0  5770.0   0.045       0
Bank Sta=4969.4,4973.4
Exp/Cntr=0.3,0.1

Type RM Length L Ch R = 1,4229,452,452,452
BEGIN DESCRIPTION:
DEADMAN TRIBUTARY 6 7.0
END DESCRIPTION:
XS GIS Cut Line= 3
      2268775.01     13745674.99      2269125.00     13745075.00
      2269075.00     13744675.02
#Sta/Elev= 30
  4305.5  563.60  4399.3  561.93  4444.4  561.69  4467.6  560.15  4606.5  560.21
  4618.5  562.89  4641.2  563.62  4655.7  563.01  4664.4  561.88  4677.2  558.82
  4687.1  557.85  4735.9  556.97  4803.3  556.93  4816.1  556.43  4890.5  555.59
  4933.5  554.30  4949.3  552.94  4955.0  553.42  4965.0  552.86  4970.8  553.09
  4984.5  552.20  4984.7  551.70  4988.2  551.70  4988.5  552.20  4992.3  552.76
  5002.6  552.37  5010.2  553.11  5030.3  553.05  5151.3  557.30  5403.2  562.12
#Mann=3,-1,0
  4305.5    0.05       0  4984.5    0.05       0  4988.5    0.05       0
Bank Sta=4984.5,4988.5
Exp/Cntr=0.3,0.1

Type RM Length L Ch R = 1,3777,475,475,475
BEGIN DESCRIPTION:
DEADMAN TRIBUTARY 6 6.0
END DESCRIPTION:
XS GIS Cut Line= 3
      2268724.97     13745925.03      2269525.00     13745025.00
      2269525.00     13744425.00
#Sta/Elev= 30
  3795.9  570.00  4107.4  562.25  4121.7  563.22  4171.0  561.50  4221.2  562.04
  4227.9  560.93  4235.4  562.03  4242.1  560.79  4249.6  562.05  4256.3  560.61
  4263.8  561.91  4270.5  560.55  4284.7  562.98  4291.4  561.40  4298.9  562.79
  4305.6  561.33  4313.1  562.51  4319.8  560.89  4341.6  561.41  4348.3  559.68
  4355.8  560.53  4362.5  558.69  4390.9  556.88  4454.5  555.72  4855.1  553.42
  4976.8  551.70  4977.0  551.20  4980.8  551.70  5360.1  558.71  5600.1  566.83
#Mann=4,-1,0
  3795.9    0.05       0  4855.1   0.045       0  4976.8   0.045       0
  4980.8   0.045       0
Bank Sta=4976.8,4980.8
Exp/Cntr=0.3,0.1

Type RM Length L Ch R = 1,3302,467,467,467
BEGIN DESCRIPTION:
DEADMAN TRIBUTARY 6 5.0
END DESCRIPTION:
XS GIS Cut Line= 3
      2269024.97     13746075.03      2269925.00     13745225.00
      2270225.00     13744625.00
#Sta/Elev= 30
  3766.9  569.84  3837.5  567.53  3901.5  564.55  3950.8  564.11  4021.6  561.01
  4106.6  558.51  4134.9  558.44  4155.9  557.26  4255.0  556.38  4311.7  554.76
  4431.8  553.11  4752.2  551.91  4787.8  551.98  4863.5  552.16  4868.4  551.68
  4868.6  551.18  4872.4  551.68  4902.3  551.84  4942.5  551.86  5018.8  551.82
  5085.9  552.39  5102.7  551.94  5108.3  552.52  5139.0  552.14  5259.7  553.68
  5300.8  554.16  5377.8  555.46  5486.3  558.56  5555.5  561.02  5675.7  566.94
#Mann=12,-1,0
  3766.9    0.05       0  4752.2   0.035       0  4787.8   0.045       0
  4868.4    0.05       0  4872.4   0.045       0  4902.3   0.035       0
  4942.5    0.05       0  5018.8   0.035       0  5259.7   0.045       0
  5300.8    0.05       0  5377.8   0.045       0  5486.3    0.05       0
Bank Sta=4868.4,4872.4
Exp/Cntr=0.3,0.1

Type RM Length L Ch R = 1,2835,482,482,482
BEGIN DESCRIPTION:
DEADMAN TRIBUTARY 6 4.0
END DESCRIPTION:
XS GIS Cut Line= 3
      2269725.01     13746124.99      2270275.00     13745525.00
      2270275.00     13744625.02
#Sta/Elev= 30
  4181.8  555.00  4238.2  554.82  4358.4  552.99  4457.7  550.67  4739.2  548.60
  4877.2  547.49  4981.8  546.57  4998.2  545.84  5003.7  544.99  5004.0  544.49
  5007.5  544.49  5007.7  544.99  5015.7  545.09  5025.7  546.66  5055.7  546.02
  5085.7  546.26  5105.7  545.45  5135.7  547.08  5155.7  547.46  5235.7  547.70
  5375.7  547.10  5435.7  548.00  5554.8  551.32  5645.7  554.94  5715.7  557.08
  5765.7  559.69  5795.7  562.88  5815.7  563.69  5829.1  563.46  5895.7  566.96
#Mann=7,-1,0
  4181.8   0.045       0  4739.2    0.05       0  4877.2   0.045       0
  5003.7   0.045       0  5007.7   0.045       0  5554.8   0.035       0
  5829.1    0.05       0
Bank Sta=5003.7,5007.7
Exp/Cntr=0.3,0.1

Type RM Length L Ch R = 1,2353,449,449,449
BEGIN DESCRIPTION:
DEADMAN TRIBUTARY 6 3.0
END DESCRIPTION:
XS GIS Cut Line= 3
      2271225.00     13746425.00      2270725.00     13745525.00
      2270375.01     13744625.02
#Sta/Elev= 30
  3965.9  569.19  4023.1  566.56  4060.8  565.70  4098.6  562.18  4148.9  560.66
  4163.8  560.87  4207.3  557.03  4251.9  554.90  4282.8  554.79  4332.0  551.89
  4434.9  548.48  4694.6  544.34  4795.6  543.98  4795.8  543.48  4799.6  543.98
  4949.7  545.20  4998.1  545.30  5027.6  544.23  5037.1  544.81  5049.1  545.86
  5274.4  545.22  5445.7  546.47  5589.8  550.33  5660.7  552.98  5668.7  554.22
  5674.1  553.42  5692.9  556.93  5698.6  557.33  5763.0  559.59  5961.1  567.28
#Mann=5,-1,0
  3965.9    0.05       0  4795.6    0.05       0  4799.6    0.05       0
  5037.1   0.045       0  5763.0   0.035       0
Bank Sta=4795.6,4799.6
Exp/Cntr=0.3,0.1

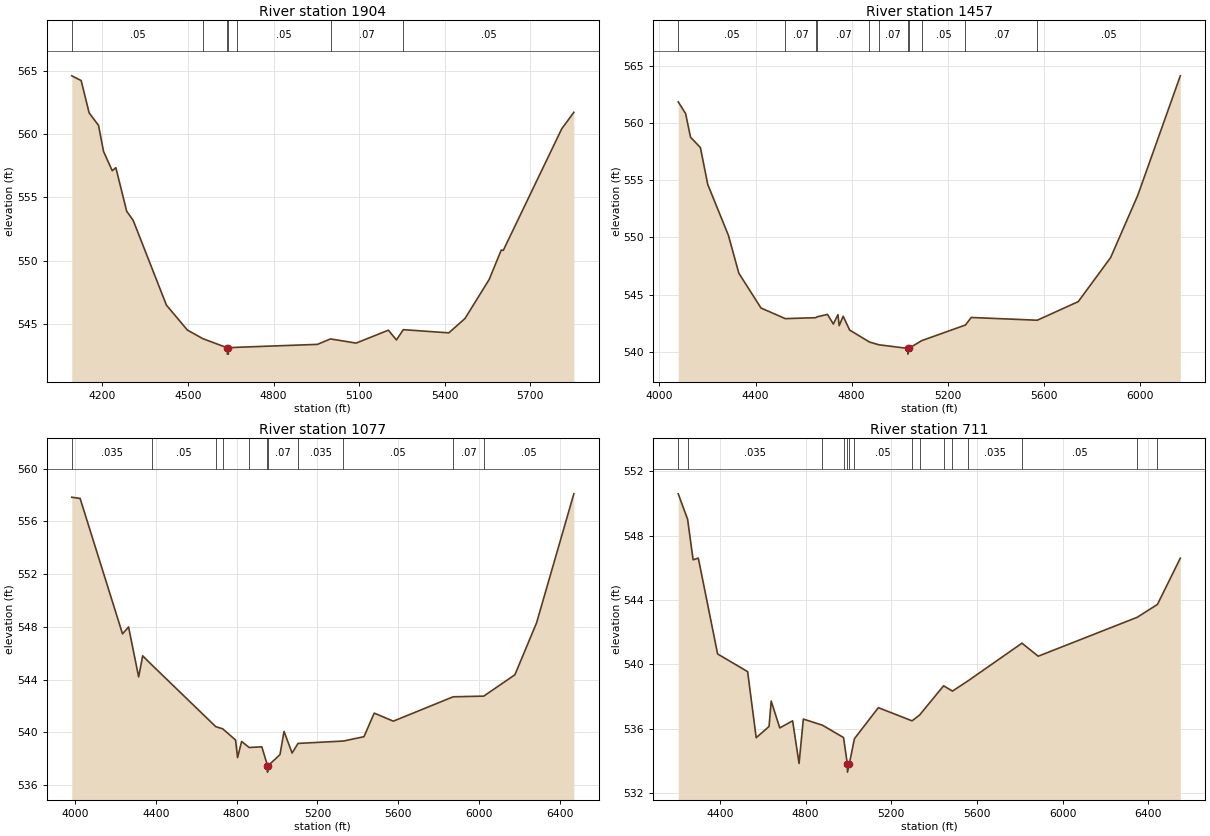
Type RM Length L Ch R = 1,1904,447,447,447
BEGIN DESCRIPTION:
DEADMAN TRIBUTARY 6 2.0
END DESCRIPTION:
XS GIS Cut Line= 3
      2271275.00     13746274.98      2271125.00     13745375.00
      2270525.01     13744775.01
#Sta/Elev= 30
  4092.3  564.58  4125.2  564.21  4153.1  561.66  4186.1  560.67  4203.8  558.61
  4234.2  557.09  4246.9  557.33  4284.9  553.89  4307.7  553.17  4424.3  546.48
  4497.8  544.51  4552.1  543.83  4637.7  543.11  4638.0  542.61  4641.5  542.61
  4641.7  543.11  4673.5  543.15  4954.0  543.38  4999.8  543.81  5089.5  543.48
  5202.7  544.50  5231.0  543.73  5255.0  544.54  5414.8  544.29  5471.4  545.42
  5556.2  548.50  5598.7  550.83  5605.7  550.80  5810.8  560.40  5853.2  561.70
#Mann=7,-1,0
  4092.3    0.05       0  4552.1    0.07       0  4637.7    0.05       0
  4641.7    0.07       0  4673.5    0.05       0  4999.8    0.07       0
  5255.0    0.05       0
Bank Sta=4637.7,4641.7
Exp/Cntr=0.3,0.1

Type RM Length L Ch R = 1,1457,380,380,380
BEGIN DESCRIPTION:
DEADMAN TRIBUTARY 6 1.0
END DESCRIPTION:
XS GIS Cut Line= 3
      2271325.00     13746224.99      2271525.00     13745325.00
      2270675.00     13744525.00
#Sta/Elev= 30
  4078.4  561.88  4109.1  560.85  4129.6  558.78  4170.6  557.88  4201.3  554.64
  4287.1  550.19  4330.6  546.87  4422.8  543.82  4523.9  542.89  4649.6  542.97
  4656.8  543.05  4699.4  543.26  4723.8  542.42  4743.0  543.24  4748.1  542.27
  4764.7  543.10  4791.6  541.89  4874.1  540.84  4912.8  540.60  5033.7  540.28
  5034.0  539.78  5037.7  540.28  5091.3  540.96  5273.6  542.33  5297.5  542.99
  5572.4  542.75  5743.0  544.38  5877.7  548.24  5990.6  553.69  6167.6  564.16
#Mann=11,-1,0
  4078.4    0.05       0  4523.9    0.07       0  4649.6    0.05       0
  4656.8    0.07       0  4874.1    0.05       0  4912.8    0.07       0
  5033.7    0.05       0  5037.7    0.07       0  5091.3    0.05       0
  5273.6    0.07       0  5572.4    0.05       0
Bank Sta=5033.7,5037.7
Exp/Cntr=0.3,0.1

Type RM Length L Ch R = 1,1077,366,366,366
BEGIN DESCRIPTION:
X18794
END DESCRIPTION:
XS GIS Cut Line= 3
      2271897.39     13746436.29      2271870.20     13745288.84
      2270771.63     13744522.02
#Sta/Elev= 30
  3983.0  557.84  4024.3  557.75  4234.4  547.47  4264.4  547.99  4314.4  544.20
  4334.4  545.80  4379.1  545.12  4696.6  540.42  4730.6  540.26  4794.5  539.41
  4804.5  538.07  4824.5  539.30  4861.9  538.84  4924.6  538.89  4952.6  537.47
  4952.8  536.97  4956.6  537.47  5014.6  538.30  5034.6  540.06  5074.6  538.42
  5104.0  539.15  5328.7  539.33  5430.8  539.66  5481.4  541.45  5576.1  540.84
  5872.9  542.69  6024.1  542.74  6178.4  544.36  6285.7  548.30  6470.5  558.10
#Mann=11,-1,0
  3983.0   0.035       0  4379.1    0.05       0  4696.6    0.07       0
  4730.6    0.05       0  4861.9    0.07       0  4952.6    0.05       0
  4956.6    0.07       0  5104.0   0.035       0  5328.7    0.05       0
  5872.9    0.07       0  6024.1    0.05       0
Bank Sta=4952.6,4956.6
Exp/Cntr=0.3,0.1

Type RM Length L Ch R = 1,711,0,0,0
BEGIN DESCRIPTION:
X18793
END DESCRIPTION:
XS GIS Cut Line= 3
      2272229.13     13746218.83      2272240.00     13745348.66
      2270968.70     13744604.35
#Sta/Elev= 30
  4205.9  550.60  4249.6  549.02  4275.3  546.50  4299.7  546.60  4389.7  540.64
  4529.8  539.54  4569.8  535.43  4629.8  536.13  4639.8  537.71  4679.8  536.04
  4739.8  536.48  4769.8  533.83  4789.8  536.59  4878.9  536.21  4977.4  535.44
  4995.4  533.79  4995.9  533.29  5004.2  533.79  5028.3  535.37  5139.9  537.30
  5297.2  536.48  5332.3  536.84  5444.5  538.66  5485.9  538.33  5556.6  538.95
  5810.2  541.31  5886.1  540.50  6348.0  542.92  6442.6  543.72  6549.3  546.60
#Mann=15,-1,0
  4205.9    0.07       0  4249.6   0.035       0  4878.9    0.05       0
  4977.4    0.07       0  4995.4    0.05       0  5004.2    0.07       0
  5028.3    0.05       0  5297.2    0.07       0  5332.3    0.05       0
  5444.5   0.035       0  5485.9    0.05       0  5556.6   0.035       0
  5810.2    0.05       0  6348.0    0.07       0  6442.6    0.05       0
Bank Sta=4995.4,5004.2
Exp/Cntr=0.3,0.1

Chan Stop Cuts=-1