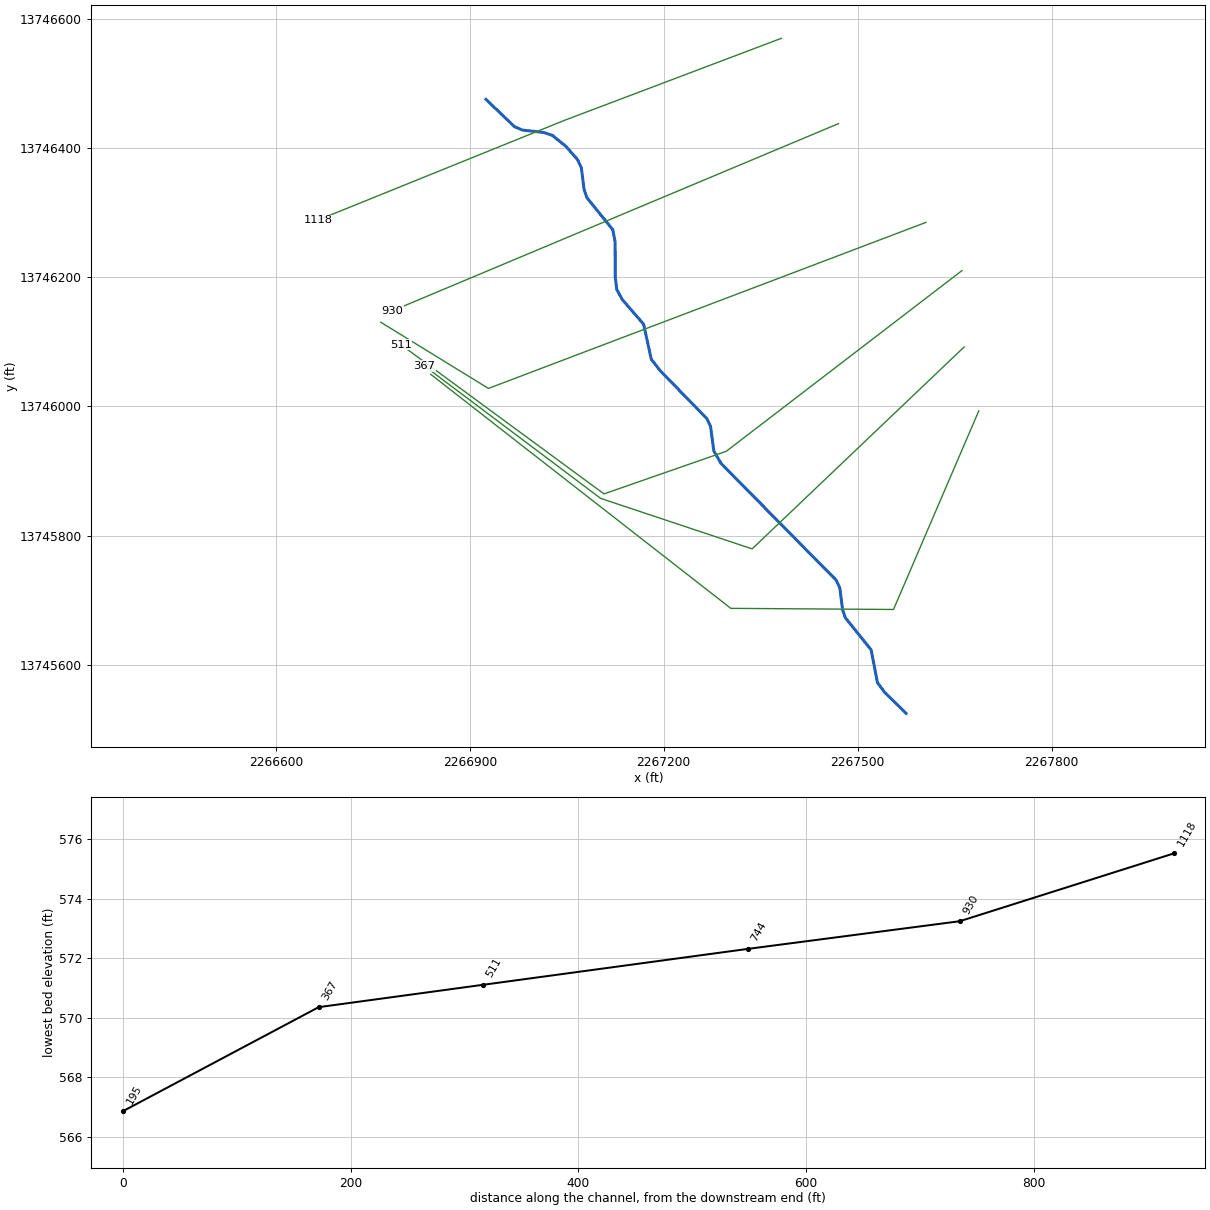
--- DEADMAN TRIBUTARY 6F.prj (project) ---

Proj Title=DEADMAN TRIBUTARY 6F Base Level Engineering
Current Plan=p01
Default Exp/Contr=0.3,0.1
English Units
Geom File=g01
Flow File=f01
Plan File=p01
BEGIN DESCRIPTION:
DEADMAN TRIBUTARY 6F
END DESCRIPTION:

--- DEADMAN TRIBUTARY 6F.p01 (plan) ---

Plan Title=Multiple Run
Short Identifier=Multiple
Geom File=g01
Flow File=f01
Subcritical Flow
K Sum by GR= 0
Std Step Tol= 0.01
Critical Tol= 0.01
Num of Std Step Trials= 20
Max Error Tol= 0.3
Flow Tol Ratio= 0.001
Split Flow NTrial= 30
Split Flow Tol= 0.02
Split Flow Ratio= 0.02
Log Output Level= 0
Friction Slope Method= 1
Unsteady Friction Slope Method= 2
Unsteady Bridges Friction Slope Method= 1
Parabolic Critical Depth
Global Vel Dist=  1 , 1 , 1
Global Log Level= 0
CheckData=True
Encroach Param= -1, 0, 0, 0
BEGIN DESCRIPTION:
Multiple Run
END DESCRIPTION:

--- DEADMAN TRIBUTARY 6F.f01 (steady flow) ---

Flow Title=Multiple
Number of Profiles=7
Profile Names=10-year,25-year,50-year,1pct_min,100-year,1pct_plu,500-year
River Rch & RM= DEADMAN TRIBUTAR,Reach-1,1118
     180     269     343     213     425     848     645
Boundary for River Rch & Prof#=DEADMAN TRIBUTAR,Reach-1,1
Up Type=0
Dn Type=3
Dn Slope=0.005
Boundary for River Rch & Prof#=DEADMAN TRIBUTAR,Reach-1,2
Up Type=0
Dn Type=3
Dn Slope=0.005
Boundary for River Rch & Prof#=DEADMAN TRIBUTAR,Reach-1,3
Up Type=0
Dn Type=3
Dn Slope=0.005
Boundary for River Rch & Prof#=DEADMAN TRIBUTAR,Reach-1,4
Up Type=0
Dn Type=3
Dn Slope=0.005
Boundary for River Rch & Prof#=DEADMAN TRIBUTAR,Reach-1,5
Up Type=0
Dn Type=3
Dn Slope=0.005
Boundary for River Rch & Prof#=DEADMAN TRIBUTAR,Reach-1,6
Up Type=0
Dn Type=3
Dn Slope=0.005
Boundary for River Rch & Prof#=DEADMAN TRIBUTAR,Reach-1,7
Up Type=0
Dn Type=3
Dn Slope=0.005

--- DEADMAN TRIBUTARY 6F.g01 (geometry) ---

Geom Title=Existing Conditions

River Reach=DEADMAN TRIBUTAR,Reach-1
Reach XY= 30
      2266925.00     13746475.00      2266968.89     13746432.95
      2266981.11     13746427.58      2267014.62     13746423.75
      2267027.61     13746419.39      2267048.87     13746402.17
      2267066.99     13746381.34      2267072.58     13746369.15
      2267076.73     13746335.76      2267081.15     13746322.85
      2267121.18     13746273.42      2267124.77     13746254.91
      2267124.99     13746200.00      2267127.33     13746180.97
      2267135.84     13746165.35      2267168.86     13746127.17
      2267180.84     13746072.71      2267194.82     13746054.93
      2267266.82     13745981.04      2267272.46     13745968.95
      2267277.53     13745931.05      2267288.63     13745911.79
      2267466.86     13745731.06      2267472.50     13745718.97
      2267476.70     13745685.70      2267481.10     13745672.81
      2267520.96     13745623.33      2267530.67     13745572.64
      2267541.41     13745558.07      2267575.00     13745525.00

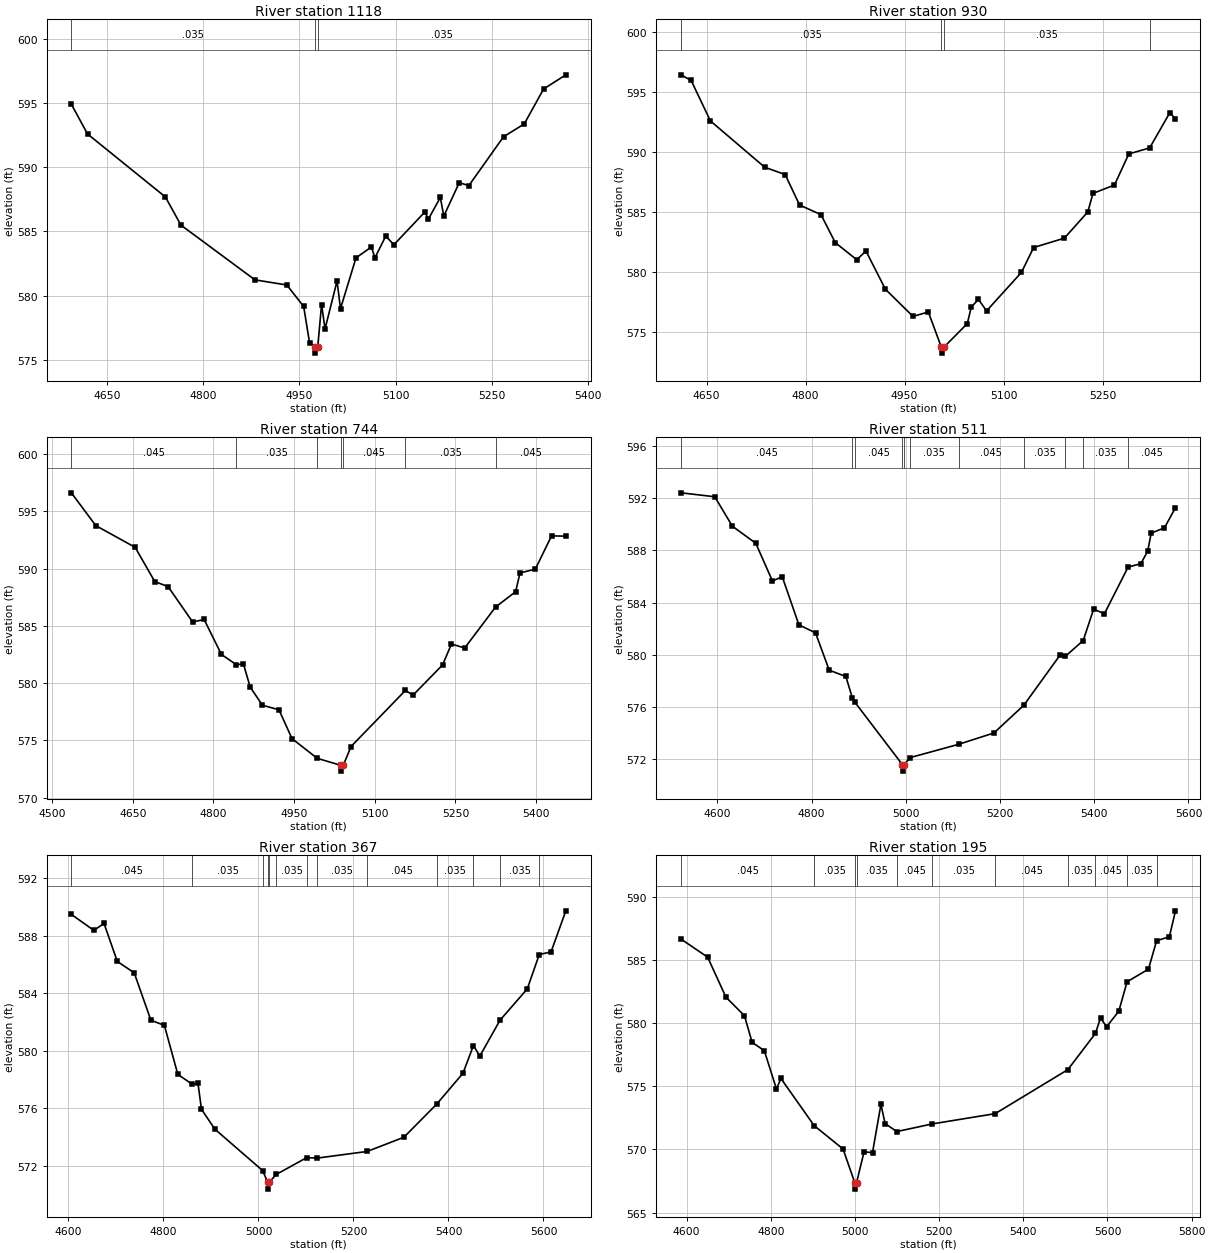
Type RM Length L Ch R = 1,1118,188,188,188
BEGIN DESCRIPTION:
DEADMAN TRIBUTARY 6F3093
END DESCRIPTION:
XS GIS Cut Line= 3
      2267381.93     13746569.44      2267046.88     13746442.71
      2266664.97     13746288.21
#Sta/Elev= 30
  4594.7  594.89  4619.8  592.58  4741.1  587.68  4765.3  585.49  4880.6  581.23
  4930.3  580.83  4956.5  579.16  4965.7  576.34  4974.5  576.03  4974.8  575.53
  4978.5  576.03  4984.4  579.31  4989.8  577.41  5008.5  581.14  5013.9  578.99
  5038.0  582.94  5062.1  583.79  5067.5  582.94  5084.4  584.64  5097.0  583.96
  5145.3  586.51  5150.7  585.95  5169.4  587.64  5174.8  586.19  5198.9  588.79
  5213.8  588.56  5267.8  592.36  5300.1  593.36  5330.3  596.08  5364.9  597.18
#Mann=3,-1,0
  4594.7   0.035       0  4974.5   0.035       0  4978.5   0.035       0
Bank Sta=4974.5,4978.5
Exp/Cntr=0.3,0.1

Type RM Length L Ch R = 1,930,186,186,186
BEGIN DESCRIPTION:
DEADMAN TRIBUTARY 6F10507
END DESCRIPTION:
XS GIS Cut Line= 2
      2267470.44     13746437.48      2266779.78     13746147.68
#Sta/Elev= 30
  4611.4  596.44  4626.7  595.97  4655.9  592.60  4738.1  588.74  4769.1  588.13
  4791.0  585.59  4823.4  584.79  4845.0  582.46  4877.6  581.03  4891.5  581.76
  4921.0  578.57  4962.8  576.31  4986.0  576.68  5005.7  573.75  5006.0  573.25
  5009.7  573.75  5045.0  575.71  5051.1  577.09  5061.9  577.73  5074.2  576.77
  5127.1  579.98  5145.5  582.05  5192.1  582.83  5227.6  585.02  5235.4  586.56
  5268.0  587.26  5289.7  589.85  5321.3  590.35  5351.9  593.29  5360.4  592.76
#Mann=4,-1,0
  4611.4   0.035       0  5005.7   0.035       0  5009.7   0.035       0
  5321.3   0.045       0
Bank Sta=5005.7,5009.7
Exp/Cntr=0.3,0.1

Type RM Length L Ch R = 1,744,233,233,233
BEGIN DESCRIPTION:
DEADMAN TRIBUTARY 6F10506
END DESCRIPTION:
XS GIS Cut Line= 3
      2267605.88     13746284.71      2266928.82     13746027.78
      2266762.32     13746130.11
#Sta/Elev= 30
  4535.8  596.62  4581.1  593.76  4654.4  591.86  4690.9  588.87  4715.7  588.43
  4761.3  585.34  4782.7  585.56  4814.8  582.51  4842.8  581.61  4855.7  581.69
  4868.3  579.66  4891.2  578.07  4921.8  577.68  4946.1  575.16  4992.9  573.44
  5037.4  572.82  5037.7  572.32  5041.4  572.82  5055.9  574.47  5157.1  579.37
  5171.1  578.95  5226.1  581.59  5242.7  583.42  5267.3  583.07  5324.6  586.64
  5362.0  587.99  5370.1  589.62  5398.7  589.96  5428.8  592.86  5455.4  592.84
#Mann=7,-1,0
  4535.8   0.045       0  4842.8   0.035       0  4992.9   0.045       0
  5037.4   0.045       0  5041.4   0.045       0  5157.1   0.035       0
  5324.6   0.045       0
Bank Sta=5037.4,5041.4
Exp/Cntr=0.3,0.1

Type RM Length L Ch R = 1,511,144,144,144
BEGIN DESCRIPTION:
DEADMAN TRIBUTARY 6F10505
END DESCRIPTION:
XS GIS Cut Line= 4
      2267661.42     13746210.04      2267296.88     13745930.56
      2267107.64     13745864.58      2266793.41     13746095.48
#Sta/Elev= 30
  4522.7  592.40  4594.3  592.10  4631.6  589.85  4681.4  588.54  4716.7  585.66
  4737.6  585.98  4772.9  582.30  4808.2  581.69  4837.3  578.83  4872.6  578.35
  4886.4  576.71  4892.0  576.37  4992.6  571.61  4992.9  571.11  4996.6  571.61
  5008.7  572.14  5111.9  573.16  5187.0  574.03  5250.4  576.15  5327.6  580.00
  5338.5  579.89  5376.5  581.10  5398.6  583.50  5421.5  583.15  5471.8  586.72
  5498.9  586.98  5513.5  587.95  5520.8  589.32  5549.0  589.72  5572.4  591.27
#Mann=11,-1,0
  4522.7   0.045       0  4886.4   0.035       0  4892.0   0.045       0
  4992.6   0.045       0  4996.6   0.045       0  5008.7   0.035       0
  5111.9   0.045       0  5250.4   0.035       0  5338.5   0.045       0
  5376.5   0.035       0  5471.8   0.045       0
Bank Sta=4992.6,4996.6
Exp/Cntr=0.3,0.1

Type RM Length L Ch R = 1,367,172,172,172
BEGIN DESCRIPTION:
X18801
END DESCRIPTION:
XS GIS Cut Line= 4
      2267664.91     13746091.99      2267336.81     13745779.51
      2267102.43     13745857.64      2266829.96     13746062.43
#Sta/Elev= 30
  4606.1  589.47  4653.4  588.36  4674.8  588.84  4702.8  586.20  4738.3  585.41
  4773.5  582.11  4801.9  581.75  4830.2  578.34  4860.8  577.65  4872.6  577.73
  4879.9  575.92  4908.2  574.53  5008.7  571.65  5019.1  570.86  5019.3  570.36
  5023.1  570.86  5037.4  571.38  5101.4  572.55  5124.0  572.52  5228.8  572.98
  5306.2  573.97  5375.1  576.27  5430.5  578.42  5452.6  580.35  5465.9  579.61
  5508.5  582.11  5565.9  584.29  5591.1  586.68  5615.9  586.86  5647.1  589.72
#Mann=13,-1,0
  4606.1   0.045       0  4860.8   0.035       0  5008.7   0.045       0
  5019.1   0.035       0  5023.1   0.045       0  5037.4   0.035       0
  5101.4   0.045       0  5124.0   0.035       0  5228.8   0.045       0
  5375.1   0.035       0  5452.6   0.045       0  5508.5   0.035       0
  5591.1   0.045       0
Bank Sta=5019.1,5023.1
Exp/Cntr=0.3,0.1

Type RM Length L Ch R = 1,195,0,0,0
BEGIN DESCRIPTION:
DEADMAN TRIBUTARY 6F10504
END DESCRIPTION:
XS GIS Cut Line= 4
      2267687.51     13745993.08      2267555.56     13745685.76
      2267303.82     13745687.50      2266839.51     13746049.59
#Sta/Elev= 30
  4586.6  586.67  4649.8  585.24  4693.3  582.07  4737.3  580.60  4755.5  578.49
  4784.5  577.83  4813.4  574.79  4823.9  575.63  4903.0  571.89  4971.6  570.04
  4999.6  567.36  4999.9  566.86  5003.6  567.36  5021.6  569.82  5041.6  569.75
  5061.6  573.57  5071.6  572.05  5099.4  571.42  5184.0  572.03  5333.2  572.84
  5505.9  576.33  5571.4  579.20  5583.4  580.42  5597.9  579.73  5626.8  580.95
  5646.6  583.29  5697.4  584.29  5716.7  586.54  5747.1  586.86  5761.6  588.91
#Mann=11,-1,0
  4586.6   0.045       0  4903.0   0.035       0  4999.6   0.035       0
  5003.6   0.035       0  5099.4   0.045       0  5184.0   0.035       0
  5333.2   0.045       0  5505.9   0.035       0  5571.4   0.045       0
  5646.6   0.035       0  5716.7   0.045       0
Bank Sta=4999.6,5003.6
Exp/Cntr=0.3,0.1

Chan Stop Cuts=-1