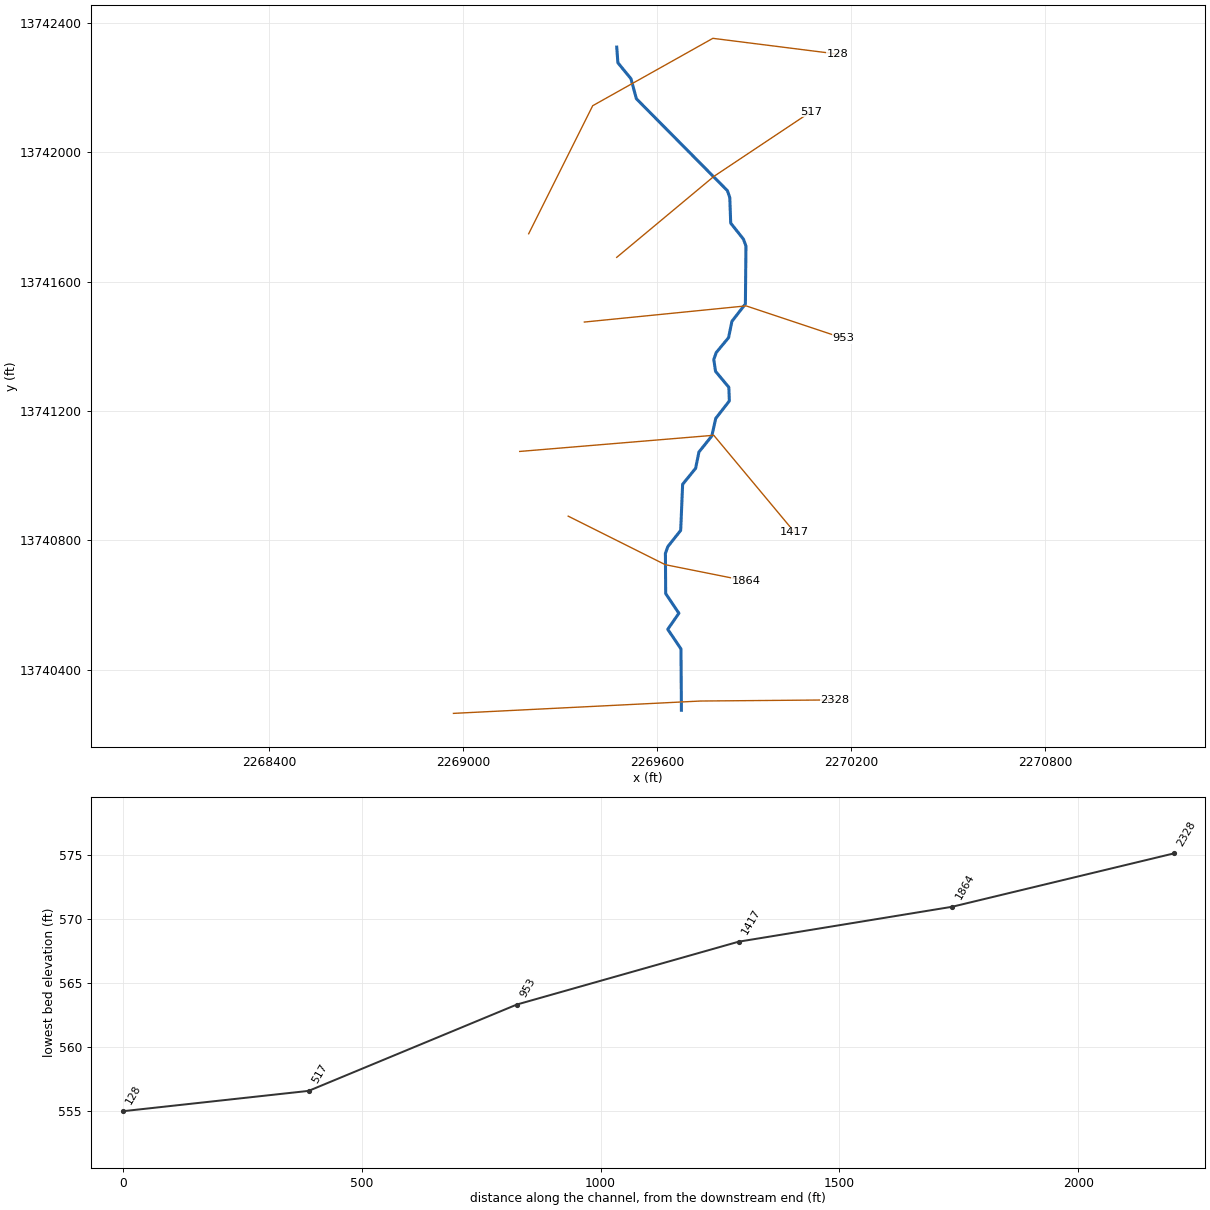
--- DEADMAN TRIBUTARY 7.prj (project) ---

Proj Title=DEADMAN TRIBUTARY 7 Base Level Engineering
Current Plan=p01
Default Exp/Contr=0.3,0.1
English Units
Geom File=g01
Flow File=f01
Plan File=p01
BEGIN DESCRIPTION:
DEADMAN TRIBUTARY 7
END DESCRIPTION:

--- DEADMAN TRIBUTARY 7.p01 (plan) ---

Plan Title=Multiple Run
Short Identifier=Multiple
Geom File=g01
Flow File=f01
Subcritical Flow
K Sum by GR= 0
Std Step Tol= 0.01
Critical Tol= 0.01
Num of Std Step Trials= 20
Max Error Tol= 0.3
Flow Tol Ratio= 0.001
Split Flow NTrial= 30
Split Flow Tol= 0.02
Split Flow Ratio= 0.02
Log Output Level= 0
Friction Slope Method= 1
Unsteady Friction Slope Method= 2
Unsteady Bridges Friction Slope Method= 1
Parabolic Critical Depth
Global Vel Dist=  1 , 1 , 1
Global Log Level= 0
CheckData=True
Encroach Param= -1, 0, 0, 0
BEGIN DESCRIPTION:
Multiple Run
END DESCRIPTION:

--- DEADMAN TRIBUTARY 7.f01 (steady flow) ---

Flow Title=Multiple
Number of Profiles=7
Profile Names=10-year,25-year,50-year,1pct_min,100-year,1pct_plu,500-year
River Rch & RM= DEADMAN TRIBUTAR,Reach-1,2328
     511     820    1098     713    1424    2840    2365
Boundary for River Rch & Prof#=DEADMAN TRIBUTAR,Reach-1,1
Up Type=0
Dn Type=3
Dn Slope=0.005
Boundary for River Rch & Prof#=DEADMAN TRIBUTAR,Reach-1,2
Up Type=0
Dn Type=3
Dn Slope=0.005
Boundary for River Rch & Prof#=DEADMAN TRIBUTAR,Reach-1,3
Up Type=0
Dn Type=3
Dn Slope=0.005
Boundary for River Rch & Prof#=DEADMAN TRIBUTAR,Reach-1,4
Up Type=0
Dn Type=3
Dn Slope=0.005
Boundary for River Rch & Prof#=DEADMAN TRIBUTAR,Reach-1,5
Up Type=0
Dn Type=3
Dn Slope=0.005
Boundary for River Rch & Prof#=DEADMAN TRIBUTAR,Reach-1,6
Up Type=0
Dn Type=3
Dn Slope=0.005
Boundary for River Rch & Prof#=DEADMAN TRIBUTAR,Reach-1,7
Up Type=0
Dn Type=3
Dn Slope=0.005

--- DEADMAN TRIBUTARY 7.g01 (geometry) ---

Geom Title=Existing Conditions

River Reach=DEADMAN TRIBUTAR,Reach-1
Reach XY= 30
      2269675.00     13740275.00      2269673.63     13740464.57
      2269632.79     13740525.10      2269667.20     13740574.90
      2269626.36     13740635.44      2269625.51     13740759.78
      2269633.14     13740781.05      2269672.73     13740830.94
      2269678.76     13740973.44      2269718.88     13741022.82
      2269729.16     13741073.28      2269768.92     13741122.80
      2269781.16     13741177.20      2269823.20     13741231.11
      2269821.60     13741273.28      2269780.41     13741322.80
      2269775.08     13741359.61      2269782.77     13741380.94
      2269820.78     13741426.72      2269831.11     13741477.18
      2269872.76     13741530.93      2269874.48     13741709.78
      2269866.86     13741731.06      2269827.36     13741780.98
      2269824.48     13741859.78      2269817.14     13741881.17
      2269535.75     13742165.31      2269519.03     13742227.24
      2269478.60     13742276.49      2269475.00     13742325.00

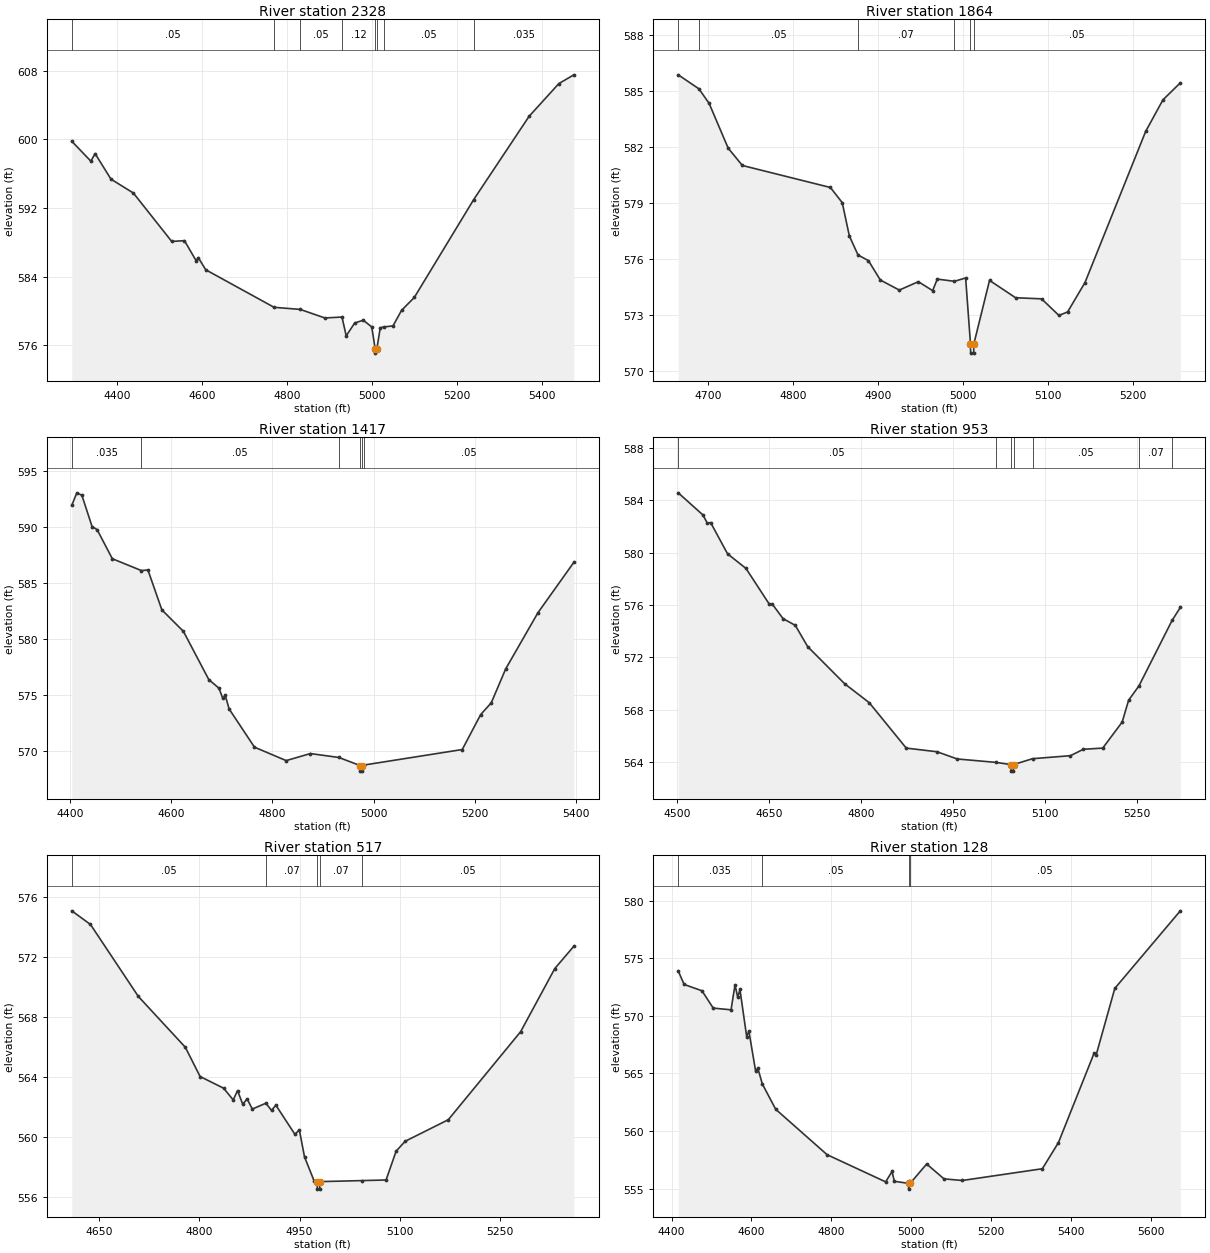
Type RM Length L Ch R = 1,2328,464,464,464
BEGIN DESCRIPTION:
DEADMAN TRIBUTARY 7 5.0
END DESCRIPTION:
XS GIS Cut Line= 3
      2268970.20     13740265.28      2269734.04     13740303.47
      2270150.33     13740306.94
#Sta/Elev= 30
  4294.3  599.77  4339.2  597.45  4349.2  598.33  4386.5  595.36  4439.3  593.74
  4529.4  588.11  4559.4  588.20  4586.8  585.87  4591.8  586.23  4609.5  584.81
  4770.3  580.44  4831.6  580.20  4889.8  579.20  4930.0  579.31  4939.9  577.12
  4959.9  578.62  4980.0  578.94  5000.0  578.16  5008.0  575.61  5008.2  575.11
  5012.0  575.61  5020.0  578.06  5028.7  578.16  5050.0  578.28  5070.1  580.09
  5100.1  581.59  5239.8  592.98  5370.1  602.67  5440.1  606.48  5475.4  607.50
#Mann=8,-1,0
  4294.3    0.05       0  4770.3    0.07       0  4831.6    0.05       0
  4930.0    0.12       0  5008.0    0.05       0  5012.0    0.12       0
  5028.7    0.05       0  5239.8   0.035       0
Bank Sta=5008,5012
Exp/Cntr=0.3,0.1

Type RM Length L Ch R = 1,1864,447,447,447
BEGIN DESCRIPTION:
DEADMAN TRIBUTARY 7 4.0
END DESCRIPTION:
XS GIS Cut Line= 3
      2269325.02     13740874.99      2269625.00     13740725.00
      2269874.96     13740675.01
#Sta/Elev= 30
  4665.1  585.86  4689.4  585.11  4701.4  584.33  4723.8  581.93  4740.5  581.00
  4844.0  579.82  4857.9  579.01  4866.3  577.22  4876.5  576.20  4888.7  575.90
  4902.7  574.86  4925.0  574.32  4947.4  574.77  4964.2  574.29  4969.7  574.91
  4989.8  574.79  5003.0  574.97  5008.7  571.44  5008.9  570.94  5012.4  570.94
  5012.7  571.44  5031.1  574.84  5061.7  573.91  5092.3  573.85  5112.7  572.96
  5122.9  573.15  5143.3  574.72  5214.7  582.83  5235.0  584.52  5255.4  585.43
#Mann=6,-1,0
  4665.1   0.035       0  4689.4    0.05       0  4876.5    0.07       0
  4989.8    0.05       0  5008.7    0.05       0  5012.7    0.05       0
Bank Sta=5008.7,5012.7
Exp/Cntr=0.3,0.1

Type RM Length L Ch R = 1,1417,464,464,464
BEGIN DESCRIPTION:
DEADMAN TRIBUTARY 7 3.0
END DESCRIPTION:
XS GIS Cut Line= 3
      2269175.05     13741075.00      2269775.00     13741125.00
      2270024.97     13740825.03
#Sta/Elev= 30
  4403.2  591.96  4413.2  593.08  4423.2  592.86  4443.3  590.07  4453.3  589.79
  4483.4  587.19  4541.0  586.13  4553.7  586.19  4581.3  582.62  4623.9  580.70
  4674.1  576.39  4694.2  575.62  4701.7  574.71  4706.7  574.97  4714.2  573.77
  4764.4  570.35  4827.1  569.15  4874.8  569.78  4931.2  569.43  4973.1  568.71
  4973.4  568.21  4976.9  568.21  4977.1  568.71  4981.7  568.76  5175.1  570.14
  5211.6  573.27  5232.4  574.31  5261.0  577.35  5324.8  582.37  5395.7  586.87
#Mann=6,-1,0
  4403.2   0.035       0  4541.0    0.05       0  4931.2    0.07       0
  4973.1    0.05       0  4977.1    0.07       0  4981.7    0.05       0
Bank Sta=4973.1,4977.1
Exp/Cntr=0.3,0.1

Type RM Length L Ch R = 1,953,436,436,436
BEGIN DESCRIPTION:
DEADMAN TRIBUTARY 7 2.0
END DESCRIPTION:
XS GIS Cut Line= 3
      2269375.00     13741475.00      2269875.00     13741525.00
      2270174.98     13741425.01
#Sta/Elev= 30
  4502.3  584.57  4542.5  582.88  4550.0  582.23  4555.1  582.30  4582.7  579.91
  4612.8  578.79  4650.5  576.08  4655.6  576.07  4673.1  574.96  4693.2  574.44
  4713.3  572.82  4773.6  569.98  4813.8  568.53  4874.1  565.06  4924.4  564.78
  4957.1  564.23  5019.9  563.97  5045.0  563.80  5045.2  563.30  5048.7  563.30
  5049.0  563.80  5080.0  564.25  5141.8  564.48  5162.9  564.97  5194.5  565.06
  5226.2  567.05  5236.7  568.72  5253.6  569.82  5307.6  574.82  5321.0  575.81
#Mann=7,-1,0
  4502.3    0.05       0  5019.9    0.07       0  5045.0    0.05       0
  5049.0    0.07       0  5080.0    0.05       0  5253.6    0.07       0
  5307.6    0.05       0
Bank Sta=5045,5049
Exp/Cntr=0.3,0.1

Type RM Length L Ch R = 1,517,389,389,389
BEGIN DESCRIPTION:
DEADMAN TRIBUTARY 7 1.0
END DESCRIPTION:
XS GIS Cut Line= 3
      2269474.97     13741674.97      2269775.00     13741925.00
      2270074.99     13742125.00
#Sta/Elev= 30
  4609.2  575.11  4637.2  574.20  4708.8  569.40  4779.1  566.01  4801.2  564.06
  4836.4  563.28  4850.7  562.50  4857.2  563.12  4865.0  562.21  4871.5  562.57
  4879.3  561.89  4899.6  562.28  4908.0  561.80  4914.5  562.15  4943.1  560.20
  4949.6  560.51  4957.4  558.70  4971.8  557.09  4976.3  557.05  4976.5  556.55
  4980.0  556.55  4980.3  557.05  5043.7  557.12  5079.4  557.16  5094.4  559.08
  5107.9  559.74  5172.5  561.18  5280.7  567.05  5331.8  571.26  5360.3  572.75
#Mann=5,-1,0
  4609.2    0.05       0  4899.6    0.07       0  4976.3    0.05       0
  4980.3    0.07       0  5043.7    0.05       0
Bank Sta=4976.3,4980.3
Exp/Cntr=0.3,0.1

Type RM Length L Ch R = 1,128,0,0,0
BEGIN DESCRIPTION:
X18802
END DESCRIPTION:
XS GIS Cut Line= 4
      2269202.80     13741747.93      2269400.71     13742143.75
      2269772.24     13742352.08      2270157.70     13742303.47
#Sta/Elev= 30
  4416.6  573.89  4431.4  572.72  4476.1  572.17  4504.1  570.67  4548.8  570.52
  4558.7  572.68  4565.6  571.60  4571.1  572.29  4587.9  568.20  4593.5  568.67
  4610.3  565.21  4615.9  565.45  4627.2  564.08  4660.6  561.89  4789.2  557.95
  4935.9  555.59  4951.9  556.49  4957.6  555.64  4993.2  555.46  4993.5  554.96
  4997.2  555.46  5038.6  557.14  5082.0  555.85  5127.7  555.71  5328.2  556.73
  5368.5  559.00  5457.9  566.77  5462.9  566.60  5509.6  572.38  5673.6  579.11
#Mann=4,-1,0
  4416.6   0.035       0  4627.2    0.05       0  4993.2    0.05       0
  4997.2    0.05       0
Bank Sta=4993.2,4997.2
Exp/Cntr=0.3,0.1

Chan Stop Cuts=-1