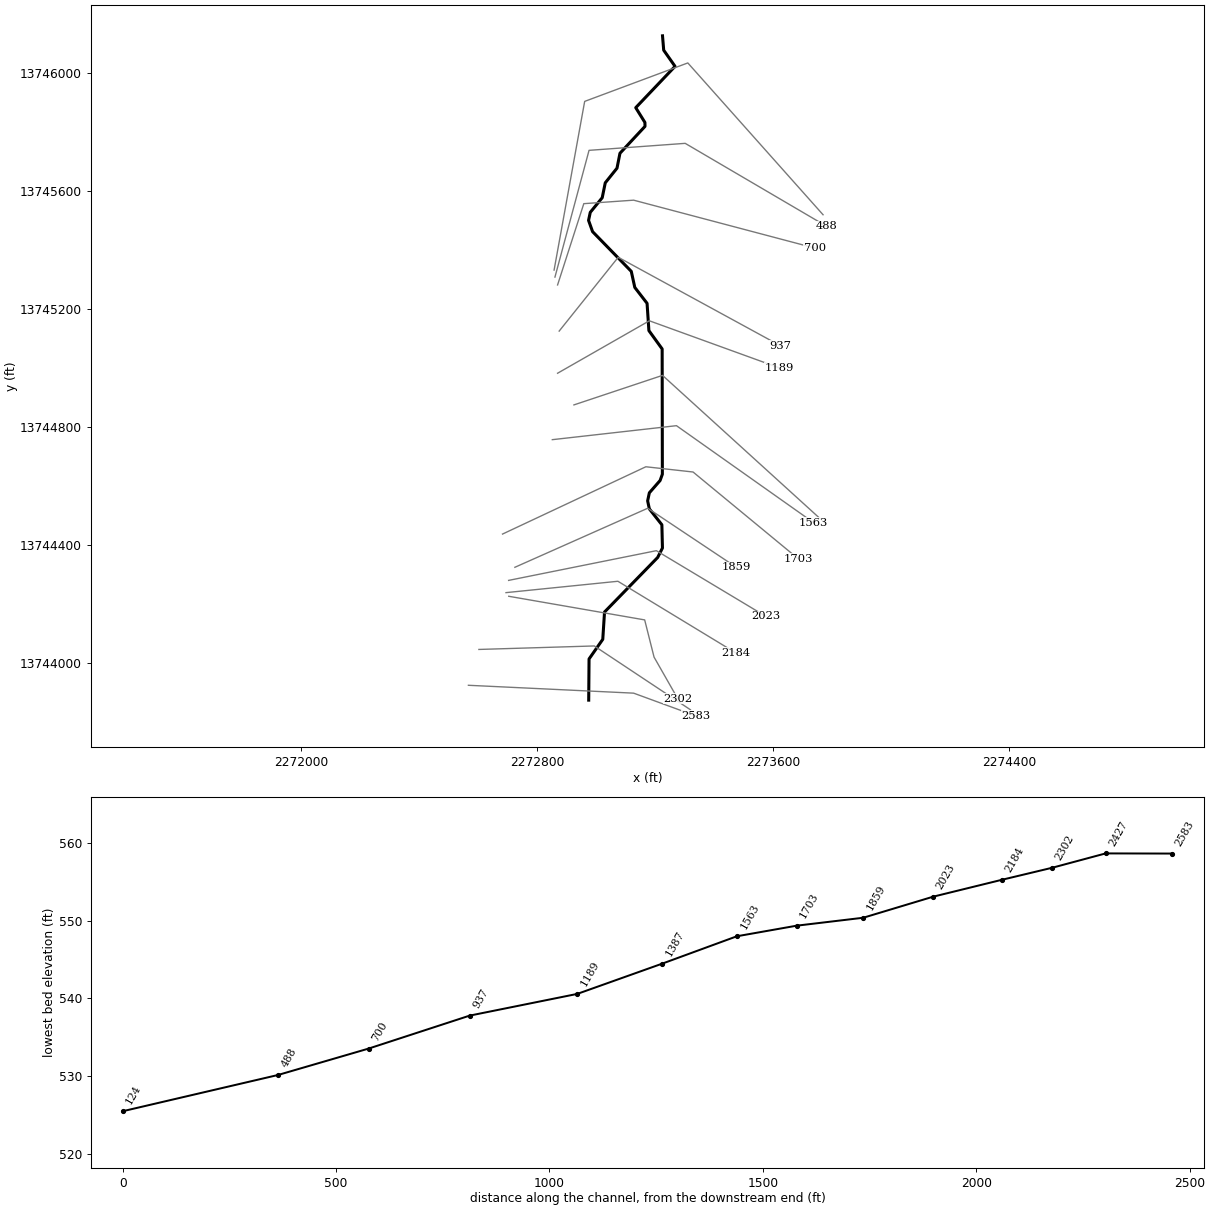
--- DEADMAN TRIBUTARY B.prj (project) ---

Proj Title=DEADMAN TRIBUTARY B Base Level Engineering
Current Plan=p01
Default Exp/Contr=0.3,0.1
English Units
Geom File=g01
Flow File=f01
Plan File=p01
BEGIN DESCRIPTION:
DEADMAN TRIBUTARY B
END DESCRIPTION:

--- DEADMAN TRIBUTARY B.p01 (plan) ---

Plan Title=Multiple Run
Short Identifier=Multiple
Geom File=g01
Flow File=f01
Subcritical Flow
K Sum by GR= 0
Std Step Tol= 0.01
Critical Tol= 0.01
Num of Std Step Trials= 20
Max Error Tol= 0.3
Flow Tol Ratio= 0.001
Split Flow NTrial= 30
Split Flow Tol= 0.02
Split Flow Ratio= 0.02
Log Output Level= 0
Friction Slope Method= 1
Unsteady Friction Slope Method= 2
Unsteady Bridges Friction Slope Method= 1
Parabolic Critical Depth
Global Vel Dist=  1 , 1 , 1
Global Log Level= 0
CheckData=True
Encroach Param= -1, 0, 0, 0
BEGIN DESCRIPTION:
Multiple Run
END DESCRIPTION:

--- DEADMAN TRIBUTARY B.f01 (steady flow) ---

Flow Title=Multiple
Number of Profiles=7
Profile Names=10-year,25-year,50-year,1pct_min,100-year,1pct_plu,500-year
River Rch & RM= DEADMAN TRIBUTAR,Reach-1,2583
     132     192     240     147     293     585     429
Boundary for River Rch & Prof#=DEADMAN TRIBUTAR,Reach-1,1
Up Type=0
Dn Type=3
Dn Slope=0.005
Boundary for River Rch & Prof#=DEADMAN TRIBUTAR,Reach-1,2
Up Type=0
Dn Type=3
Dn Slope=0.005
Boundary for River Rch & Prof#=DEADMAN TRIBUTAR,Reach-1,3
Up Type=0
Dn Type=3
Dn Slope=0.005
Boundary for River Rch & Prof#=DEADMAN TRIBUTAR,Reach-1,4
Up Type=0
Dn Type=3
Dn Slope=0.005
Boundary for River Rch & Prof#=DEADMAN TRIBUTAR,Reach-1,5
Up Type=0
Dn Type=3
Dn Slope=0.005
Boundary for River Rch & Prof#=DEADMAN TRIBUTAR,Reach-1,6
Up Type=0
Dn Type=3
Dn Slope=0.005
Boundary for River Rch & Prof#=DEADMAN TRIBUTAR,Reach-1,7
Up Type=0
Dn Type=3
Dn Slope=0.005

--- DEADMAN TRIBUTARY B.g01 (geometry) ---

Geom Title=Existing Conditions

River Reach=DEADMAN TRIBUTAR,Reach-1
Reach XY= 30
      2272975.00     13743875.00      2272976.17     13744014.52
      2273022.64     13744080.98      2273028.61     13744173.50
      2273208.60     13744358.25      2273224.76     13744390.22
      2273222.81     13744469.03      2273180.38     13744522.82
      2273174.60     13744550.00      2273180.38     13744577.18
      2273216.81     13744618.92      2273224.46     13744640.21
      2273223.78     13745064.50      2273178.86     13745126.60
      2273172.67     13745219.03      2273131.14     13745272.83
      2273119.17     13745327.30      2272988.12     13745461.79
      2272974.49     13745499.96      2272980.31     13745527.19
      2273020.78     13745576.72      2273031.08     13745627.20
      2273070.81     13745676.74      2273080.86     13745727.30
      2273165.68     13745818.34      2273165.38     13745831.67
      2273134.30     13745881.67      2273267.41     13746021.61
      2273229.02     13746076.36      2273225.00     13746125.00

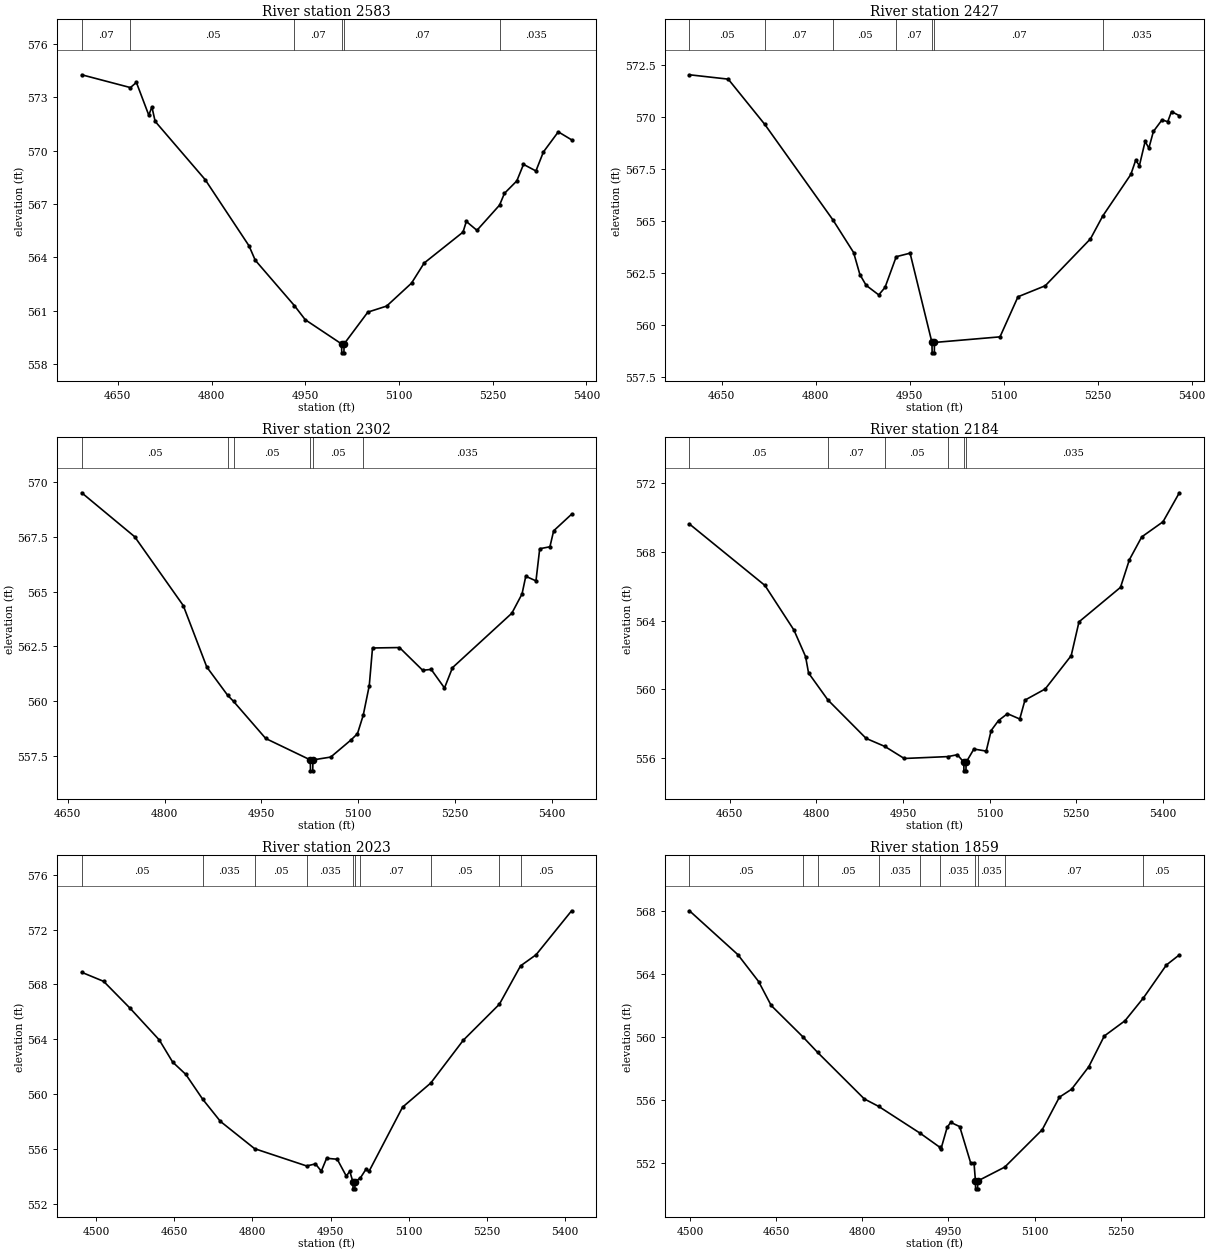
Type RM Length L Ch R = 1,2583,156,156,156
BEGIN DESCRIPTION:
X18811
END DESCRIPTION:
XS GIS Cut Line= 3
      2272567.59     13743925.33      2273127.14     13743898.68
      2273337.31     13743821.72
#Sta/Elev= 30
  4592.2  574.26  4670.1  573.54  4679.7  573.83  4699.5  571.99  4704.5  572.45
  4709.7  571.64  4789.8  568.36  4859.9  564.64  4869.9  563.83  4932.7  561.27
  4950.0  560.48  5008.1  559.12  5008.3  558.62  5011.8  558.62  5012.1  559.12
  5050.1  560.91  5080.2  561.25  5120.0  562.54  5140.2  563.67  5202.4  565.41
  5207.7  566.01  5224.7  565.51  5260.9  566.93  5268.7  567.59  5288.5  568.29
  5299.2  569.22  5319.1  568.85  5331.1  569.92  5354.9  571.05  5376.2  570.60
#Mann=6,-1,0
  4592.2    0.07       0  4670.1    0.05       0  4932.7    0.07       0
  5008.1    0.05       0  5012.1    0.07       0  5260.9   0.035       0
Bank Sta=5008.1,5012.1
Exp/Cntr=0.3,0.1

Type RM Length L Ch R = 1,2427,125,125,125
BEGIN DESCRIPTION:
X18812
END DESCRIPTION:
XS GIS Cut Line= 3
      2272603.09     13744046.71      2272993.91     13744058.55
      2273319.53     13743842.46
#Sta/Elev= 30
  4598.5  572.03  4660.4  571.82  4718.5  569.65  4827.5  565.04  4860.5  563.47
  4870.5  562.41  4880.5  561.89  4900.6  561.43  4910.6  561.79  4928.5  563.27
  4950.6  563.44  4985.5  559.14  4985.8  558.64  4989.3  558.64  4989.5  559.14
  5094.1  559.41  5122.8  561.34  5166.3  561.87  5238.5  564.13  5258.1  565.23
  5302.9  567.23  5310.6  567.91  5316.6  567.66  5325.7  568.82  5331.7  568.50
  5338.9  569.30  5352.7  569.86  5361.8  569.77  5367.8  570.26  5380.3  570.06
#Mann=7,-1,0
  4598.5    0.05       0  4718.5    0.07       0  4827.5    0.05       0
  4928.5    0.07       0  4985.5    0.05       0  4989.5    0.07       0
  5258.1   0.035       0
Bank Sta=4985.5,4989.5
Exp/Cntr=0.3,0.1

Type RM Length L Ch R = 1,2302,118,118,118
BEGIN DESCRIPTION:
DEADMAN TRIBUTARY B 4.0
END DESCRIPTION:
XS GIS Cut Line= 4
      2272704.18     13744226.78      2273164.57     13744146.76
      2273196.36     13744020.70      2273276.37     13743880.41
#Sta/Elev= 30
  4671.7  569.52  4753.7  567.51  4829.0  564.36  4865.4  561.55  4897.9  560.25
  4906.8  559.98  4956.7  558.28  5025.8  557.30  5026.0  556.80  5029.5  556.80
  5029.8  557.30  5057.4  557.43  5088.7  558.21  5098.8  558.50  5107.7  559.34
  5117.1  560.70  5122.1  562.42  5163.9  562.44  5199.8  561.40  5213.0  561.44
  5233.6  560.59  5246.0  561.52  5337.9  564.01  5353.7  564.89  5359.5  565.70
  5375.3  565.49  5381.1  566.96  5396.9  567.05  5402.7  567.78  5430.5  568.54
#Mann=6,-1,0
  4671.7    0.05       0  4897.9    0.07       0  4906.8    0.05       0
  5025.8    0.05       0  5029.8    0.05       0  5107.7   0.035       0
Bank Sta=5025.8,5029.8
Exp/Cntr=0.3,0.1

Type RM Length L Ch R = 1,2184,161,161,161
BEGIN DESCRIPTION:
X18810
END DESCRIPTION:
XS GIS Cut Line= 3
      2272694.90     13744239.14      2273073.85     13744277.63
      2273473.50     13744034.88
#Sta/Elev= 30
  4580.0  569.63  4710.8  566.05  4761.0  563.45  4781.1  561.91  4786.3  560.95
  4819.8  559.38  4886.0  557.14  4918.5  556.67  4952.0  555.97  5027.8  556.08
  5044.1  556.19  5055.2  555.75  5055.4  555.25  5058.9  555.25  5059.2  555.75
  5072.7  556.52  5094.0  556.40  5102.6  557.60  5115.3  558.18  5130.8  558.58
  5152.1  558.27  5161.1  559.37  5196.2  560.02  5241.2  561.96  5254.7  563.93
  5326.6  565.94  5342.0  567.55  5363.4  568.88  5400.2  569.76  5428.5  571.45
#Mann=6,-1,0
  4580.0    0.05       0  4819.8    0.07       0  4918.5    0.05       0
  5027.8   0.035       0  5055.2    0.05       0  5059.2   0.035       0
Bank Sta=5055.2,5059.2
Exp/Cntr=0.3,0.1

Type RM Length L Ch R = 1,2023,164,164,164
BEGIN DESCRIPTION:
X18809
END DESCRIPTION:
XS GIS Cut Line= 3
      2272703.77     13744280.59      2273204.11     13744381.25
      2273573.55     13744159.59
#Sta/Elev= 30
  4471.9  568.88  4514.0  568.22  4565.0  566.25  4621.0  563.94  4646.6  562.33
  4671.9  561.43  4704.3  559.62  4738.4  558.00  4804.1  556.01  4904.0  554.75
  4921.0  554.90  4932.2  554.37  4942.4  555.31  4962.8  555.24  4980.2  554.01
  4986.9  554.36  4993.0  553.58  4993.2  553.08  4996.7  553.08  4997.0  553.58
  5007.5  553.89  5018.0  554.51  5023.8  554.35  5088.3  559.04  5142.5  560.80
  5204.9  563.92  5274.3  566.55  5315.0  569.35  5344.8  570.16  5413.1  573.37
#Mann=10,-1,0
  4471.9    0.05       0  4704.3   0.035       0  4804.1    0.05       0
  4904.0   0.035       0  4993.0   0.035       0  4997.0   0.035       0
  5007.5    0.07       0  5142.5    0.05       0  5274.3    0.07       0
  5315.0    0.05       0
Bank Sta=4993,4997
Exp/Cntr=0.3,0.1

Type RM Length L Ch R = 1,1859,156,156,156
BEGIN DESCRIPTION:
DEADMAN TRIBUTARY B 3.0
END DESCRIPTION:
XS GIS Cut Line= 3
      2272724.96     13744324.98      2273175.00     13744525.00
      2273474.96     13744325.02
#Sta/Elev= 30
  4499.1  568.02  4583.3  565.24  4619.5  563.53  4641.4  562.01  4696.3  560.03
  4722.3  559.03  4803.5  556.08  4828.7  555.60  4901.2  553.89  4935.0  553.01
  4936.9  552.88  4947.8  554.27  4954.0  554.59  4969.7  554.32  4988.9  552.00
  4994.6  552.00  4997.1  550.87  4997.3  550.37  5000.8  550.37  5001.1  550.87
  5048.1  551.75  5113.3  554.12  5143.3  556.19  5164.4  556.69  5194.4  558.12
  5221.4  560.07  5257.5  561.04  5289.6  562.49  5329.6  564.58  5352.1  565.22
#Mann=10,-1,0
  4499.1    0.05       0  4696.3   0.035       0  4722.3    0.05       0
  4828.7   0.035       0  4901.2    0.05       0  4935.0   0.035       0
  4997.1   0.035       0  5001.1   0.035       0  5048.1    0.07       0
  5289.6    0.05       0
Bank Sta=4997.1,5001.1
Exp/Cntr=0.3,0.1

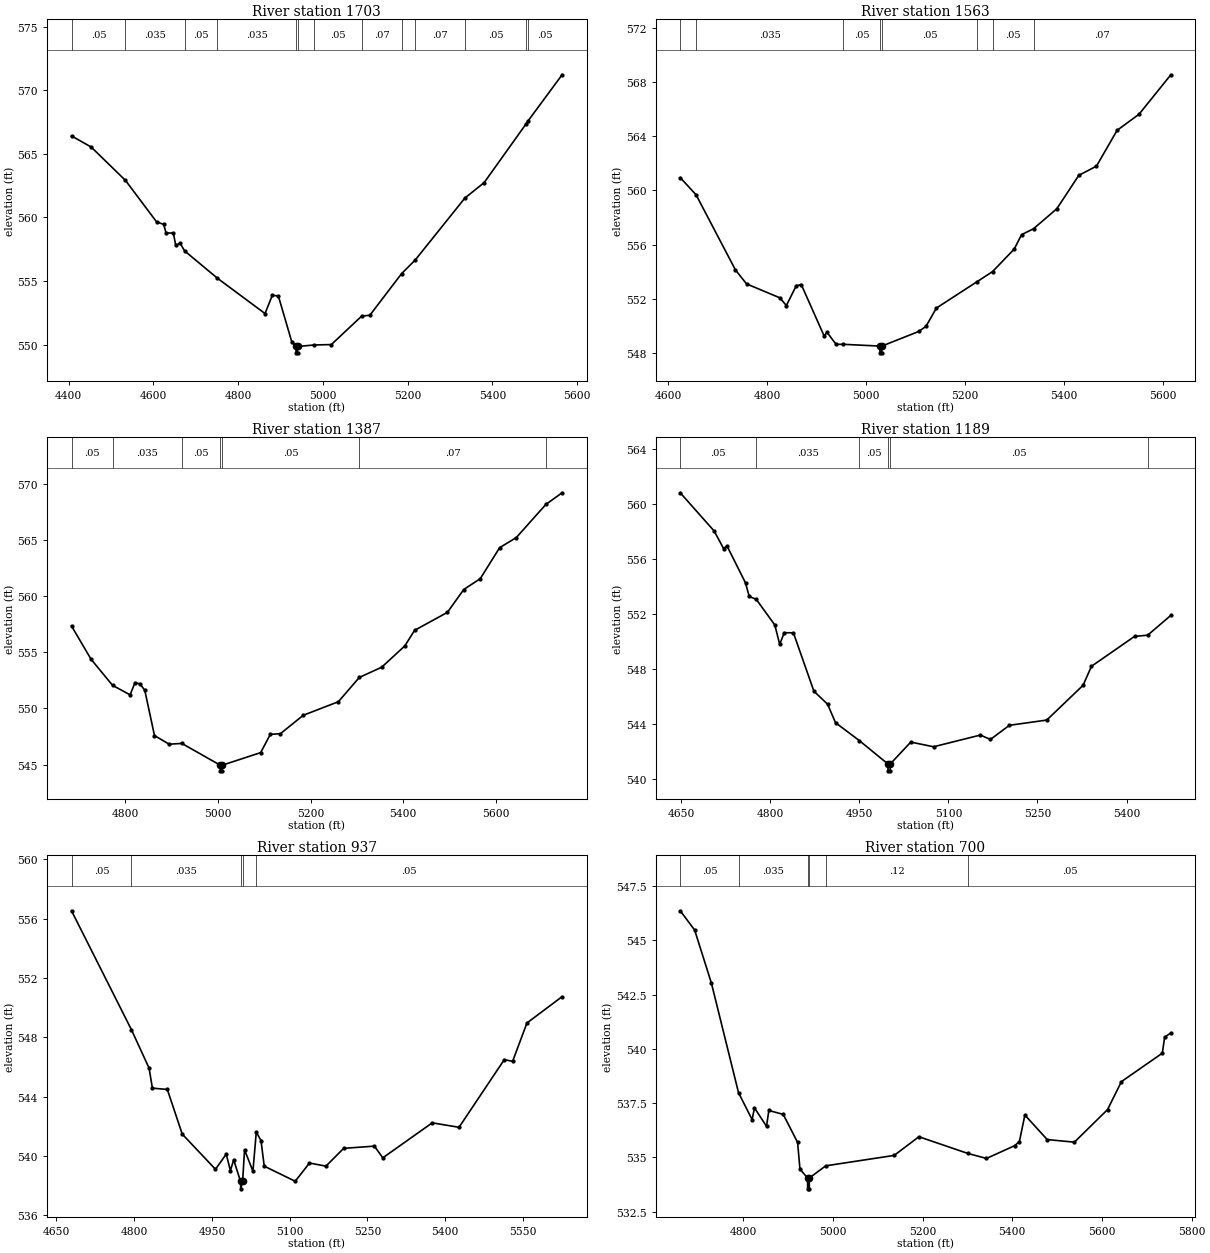
Type RM Length L Ch R = 1,1703,140,140,140
BEGIN DESCRIPTION:
X18808
END DESCRIPTION:
XS GIS Cut Line= 4
      2272683.09     13744437.51      2273168.58     13744665.46
      2273328.45     13744647.70      2273683.75     13744354.58
#Sta/Elev= 30
  4406.5  566.41  4452.8  565.54  4533.9  562.91  4607.5  559.64  4624.1  559.46
  4629.6  558.78  4646.9  558.77  4652.4  557.81  4662.7  557.97  4673.7  557.36
  4750.8  555.22  4863.2  552.44  4880.5  553.88  4894.7  553.82  4926.2  550.23
  4936.1  549.85  4936.4  549.35  4939.9  549.35  4940.1  549.85  4979.8  549.97
  5019.7  550.00  5091.0  552.23  5110.7  552.31  5185.5  555.58  5217.9  556.66
  5334.8  561.52  5380.4  562.74  5479.6  567.37  5484.2  567.60  5564.3  571.22
#Mann=13,-1,0
  4406.5    0.05       0  4533.9   0.035       0  4673.7    0.05       0
  4750.8   0.035       0  4936.1    0.05       0  4940.1   0.035       0
  4979.8    0.05       0  5091.0    0.07       0  5185.5    0.05       0
  5217.9    0.07       0  5334.8    0.05       0  5479.6    0.07       0
  5484.2    0.05       0
Bank Sta=4936.1,4940.1
Exp/Cntr=0.3,0.1

Type RM Length L Ch R = 1,1563,176,176,176
BEGIN DESCRIPTION:
X18807
END DESCRIPTION:
XS GIS Cut Line= 3
      2272851.79     13744757.23      2273272.20     13744804.61
      2273736.99     13744475.99
#Sta/Elev= 30
  4624.4  560.95  4656.4  559.68  4735.9  554.13  4758.5  553.09  4825.8  552.06
  4839.0  551.49  4859.1  552.96  4869.2  553.04  4915.7  549.21  4920.8  549.53
  4939.6  548.62  4954.1  548.62  5028.2  548.49  5028.4  547.99  5031.9  547.99
  5032.2  548.49  5106.7  549.57  5121.5  549.95  5142.4  551.30  5224.6  553.25
  5256.1  554.00  5300.0  555.67  5314.7  556.73  5338.9  557.17  5386.1  558.65
  5430.5  561.12  5466.2  561.80  5508.0  564.45  5552.3  565.64  5616.7  568.56
#Mann=8,-1,0
  4624.4    0.05       0  4656.4   0.035       0  4954.1    0.05       0
  5028.2    0.05       0  5032.2    0.05       0  5224.6    0.07       0
  5256.1    0.05       0  5338.9    0.07       0
Bank Sta=5028.2,5032.2
Exp/Cntr=0.3,0.1

Type RM Length L Ch R = 1,1387,198,198,198
BEGIN DESCRIPTION:
DEADMAN TRIBUTARY B 2.0
END DESCRIPTION:
XS GIS Cut Line= 3
      2272924.95     13744874.98      2273225.00     13744975.00
      2273775.01     13744474.99
#Sta/Elev= 30
  4683.6  557.34  4725.8  554.38  4772.2  552.06  4810.1  551.21  4820.7  552.29
  4831.2  552.19  4841.8  551.63  4862.8  547.59  4894.5  546.82  4921.9  546.89
  5005.0  544.95  5005.2  544.45  5008.7  544.45  5009.0  544.95  5092.1  546.07
  5113.1  547.70  5134.7  547.75  5184.0  549.39  5260.0  550.60  5305.2  552.76
  5353.6  553.67  5403.6  555.57  5424.6  556.95  5495.5  558.55  5530.7  560.58
  5566.5  561.55  5608.4  564.31  5644.2  565.20  5708.1  568.15  5743.2  569.19
#Mann=7,-1,0
  4683.6    0.05       0  4772.2   0.035       0  4921.9    0.05       0
  5005.0    0.05       0  5009.0    0.05       0  5305.2    0.07       0
  5708.1    0.05       0
Bank Sta=5005,5009
Exp/Cntr=0.3,0.1

Type RM Length L Ch R = 1,1189,252,252,252
BEGIN DESCRIPTION:
X18806
END DESCRIPTION:
XS GIS Cut Line= 3
      2272869.54     13744982.22      2273180.43     13745159.87
      2273620.74     13745000.29
#Sta/Elev= 30
  4648.3  560.79  4705.4  558.01  4721.2  556.74  4727.0  556.93  4758.2  554.24
  4764.4  553.26  4776.4  553.04  4807.6  551.18  4815.8  549.77  4823.4  550.62
  4838.9  550.61  4873.4  546.37  4896.5  545.42  4909.8  544.08  4949.9  542.78
  4998.1  541.08  4998.4  540.58  5001.9  540.58  5002.1  541.08  5036.6  542.67
  5075.0  542.33  5153.8  543.18  5170.8  542.86  5202.7  543.89  5265.7  544.27
  5326.9  546.80  5341.0  548.18  5413.5  550.35  5435.7  550.44  5474.7  551.88
#Mann=6,-1,0
  4648.3    0.05       0  4776.4   0.035       0  4949.9    0.05       0
  4998.1    0.05       0  5002.1    0.05       0  5435.7    0.07       0
Bank Sta=4998.1,5002.1
Exp/Cntr=0.3,0.1

Type RM Length L Ch R = 1,937,237,237,237
BEGIN DESCRIPTION:
DEADMAN TRIBUTARY B 1.0
END DESCRIPTION:
XS GIS Cut Line= 3
      2272874.99     13745124.98      2273075.00     13745375.00
      2273625.02     13745074.99
#Sta/Elev= 30
  4679.0  556.54  4794.5  548.53  4828.7  545.93  4835.1  544.58  4863.9  544.49
  4892.7  541.48  4956.8  539.11  4977.6  540.13  4985.6  539.02  4992.0  539.74
  5005.2  538.29  5005.5  537.79  5009.2  538.29  5012.9  540.42  5029.1  538.98
  5035.6  541.62  5044.7  541.04  5050.9  539.32  5110.7  538.30  5138.2  539.53
  5170.0  539.32  5204.2  540.52  5263.5  540.67  5279.7  539.88  5375.1  542.24
  5426.8  541.94  5514.1  546.50  5530.3  546.39  5557.8  548.97  5625.7  550.75
#Mann=5,-1,0
  4679.0    0.05       0  4794.5   0.035       0  5005.2   0.035       0
  5009.2   0.035       0  5035.6    0.05       0
Bank Sta=5005.2,5009.2
Exp/Cntr=0.3,0.1

Type RM Length L Ch R = 1,700,212,212,212
BEGIN DESCRIPTION:
X18805
END DESCRIPTION:
XS GIS Cut Line= 4
      2272869.58     13745281.28      2272958.39     13745556.58
      2273127.14     13745568.42      2273741.49     13745405.97
#Sta/Elev= 30
  4659.7  546.36  4691.8  545.47  4729.1  543.03  4789.6  537.98  4819.9  536.74
  4825.2  537.28  4852.0  536.43  4857.2  537.16  4889.3  536.98  4921.3  535.69
  4926.6  534.46  4943.5  534.05  4943.8  533.55  4947.3  533.55  4947.5  534.05
  4984.1  534.61  5136.6  535.09  5191.8  535.95  5301.1  535.18  5342.5  534.95
  5405.5  535.54  5415.9  535.73  5428.1  536.95  5477.9  535.82  5538.5  535.70
  5612.4  537.20  5643.4  538.49  5734.6  539.80  5739.8  540.54  5753.6  540.73
#Mann=6,-1,0
  4659.7    0.05       0  4789.6   0.035       0  4943.5    0.05       0
  4947.5   0.035       0  4984.1    0.12       0  5301.1    0.05       0
Bank Sta=4943.5,4947.5
Exp/Cntr=0.3,0.1

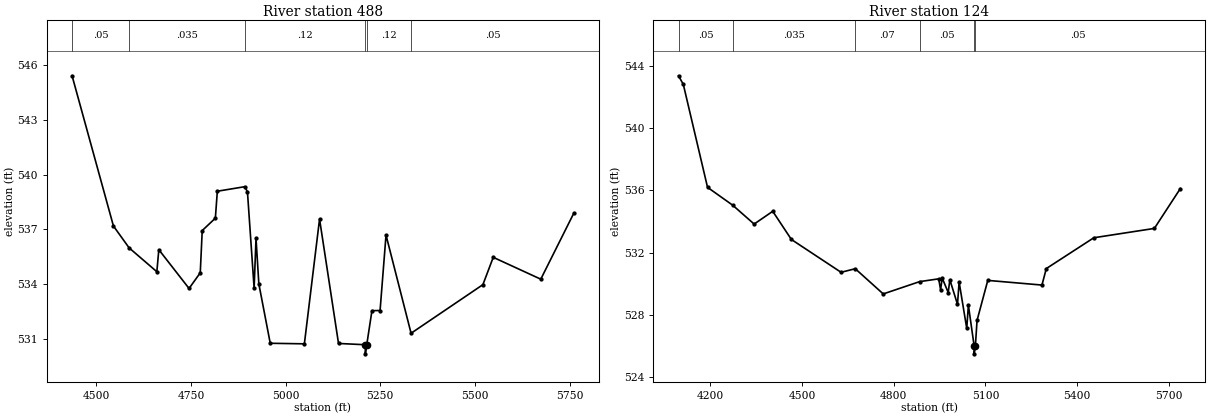
Type RM Length L Ch R = 1,488,364,364,364
BEGIN DESCRIPTION:
X18804
END DESCRIPTION:
XS GIS Cut Line= 4
      2272860.69     13745307.91      2272976.15     13745737.17
      2273301.81     13745760.86      2273780.36     13745480.22
#Sta/Elev= 30
  4435.7  545.43  4545.0  537.18  4586.4  535.98  4659.7  534.67  4664.9  535.88
  4744.8  533.75  4774.4  534.61  4779.6  536.93  4814.3  537.61  4819.5  539.09
  4892.3  539.34  4899.1  539.05  4916.7  533.77  4921.7  536.50  4929.2  534.00
  4959.3  530.74  5049.5  530.71  5089.6  537.56  5139.7  530.73  5210.3  530.66
  5210.6  530.16  5214.3  530.66  5228.0  532.53  5249.5  532.54  5265.2  536.68
  5331.4  531.29  5521.2  533.96  5548.5  535.46  5674.1  534.26  5761.5  537.89
#Mann=6,-1,0
  4435.7    0.05       0  4586.4   0.035       0  4892.3    0.12       0
  5210.3    0.05       0  5214.3    0.12       0  5331.4    0.05       0
Bank Sta=5210.3,5214.3
Exp/Cntr=0.3,0.1

Type RM Length L Ch R = 1,124,0,0,0
BEGIN DESCRIPTION:
X18803
END DESCRIPTION:
XS GIS Cut Line= 4
      2272857.73     13745331.61      2272961.35     13745902.96
      2273310.69     13746033.22      2273768.72     13745519.05
#Sta/Elev= 30
  4095.6  543.37  4111.3  542.81  4190.5  536.20  4273.0  535.05  4343.0  533.84
  4403.9  534.66  4464.9  532.85  4627.5  530.74  4673.9  530.97  4765.5  529.35
  4884.4  530.14  4947.0  530.32  4953.2  529.61  4958.5  530.37  4978.1  529.44
  4983.5  530.26  5008.5  528.68  5013.8  530.12  5038.8  527.13  5044.1  528.63
  5063.0  526.00  5063.2  525.50  5067.0  526.00  5072.5  527.65  5107.6  530.22
  5284.9  529.92  5299.1  530.98  5454.6  532.96  5652.7  533.56  5737.7  536.12
#Mann=6,-1,0
  4095.6    0.05       0  4273.0   0.035       0  4673.9    0.07       0
  4884.4    0.05       0  5063.0    0.05       0  5067.0    0.05       0
Bank Sta=5063,5067
Exp/Cntr=0.3,0.1

Chan Stop Cuts=-1