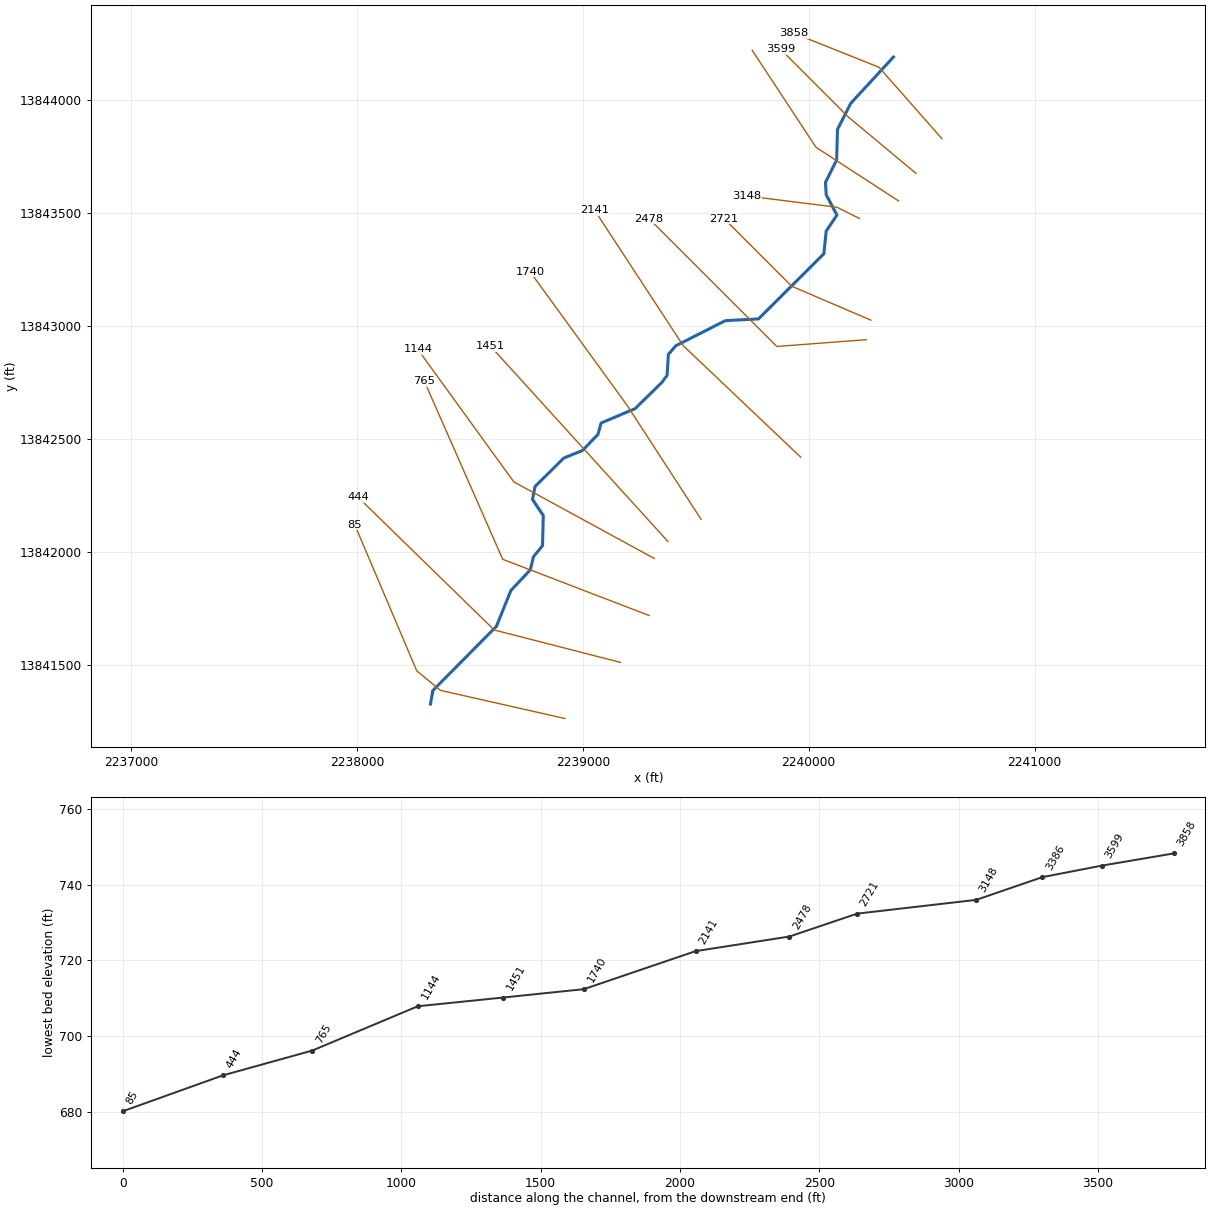
--- Deep Creek.prj (project) ---

Proj Title=Deep Creek Base Level Engineering
Current Plan=p01
Default Exp/Contr=0.3,0.1
English Units
Geom File=g01
Flow File=f01
Plan File=p01
Y Axis Title=Elevation
X Axis Title(PF)=Main Channel Distance
X Axis Title(XS)=Station
BEGIN DESCRIPTION:
Deep Creek
END DESCRIPTION:
DSS Export Rating Curves= 0
DSS Export Rating Curve Sorted= 0
DSS Export Volume Flow Curves= 0
DXF OffsetX= 0
DXF OffsetY= 0
DXF ScaleX= 1
DXF ScaleY= 10

--- Deep Creek.p01 (plan) ---

Plan Title=Multiple Run
Short Identifier=Multiple
Geom File=g01
Flow File=f01
Subcritical Flow
K Sum by GR= 0
Std Step Tol= 0.01
Critical Tol= 0.01
Num of Std Step Trials= 20
Max Error Tol= 0.3
Flow Tol Ratio= 0.001
Split Flow NTrial= 30
Split Flow Tol= 0.02
Split Flow Ratio= 0.02
Log Output Level= 0
Friction Slope Method= 1
Unsteady Friction Slope Method= 2
Unsteady Bridges Friction Slope Method= 1
Parabolic Critical Depth
Global Vel Dist=  1 , 1 , 1
Global Log Level= 0
CheckData=True
Encroach Param= -1, 0, 0, 0
BEGIN DESCRIPTION:
Multiple Run
END DESCRIPTION:

--- Deep Creek.f01 (steady flow) ---

Flow Title=Multiple
Program Version=4.10
Number of Profiles= 7
Profile Names=10-year,25-year,50-year,1pct_min,100-year,1pct_plu,500-year
River Rch & RM=Deep Creek,Reach-1         ,3858
    1482    2580    3654    2509    5007    9990    9297
River Rch & RM=Deep Creek,Reach-1         ,3148
    1905    3342    4757    3278    6541   13051   12235
Boundary for River Rch & Prof#=Deep Creek,Reach-1         , 1
Up Type= 0
Dn Type= 3
Dn Slope=0.05
Boundary for River Rch & Prof#=Deep Creek,Reach-1         , 2
Up Type= 0
Dn Type= 3
Dn Slope=0.05
Boundary for River Rch & Prof#=Deep Creek,Reach-1         , 3
Up Type= 0
Dn Type= 3
Dn Slope=0.05
Boundary for River Rch & Prof#=Deep Creek,Reach-1         , 4
Up Type= 0
Dn Type= 3
Dn Slope=0.05
Boundary for River Rch & Prof#=Deep Creek,Reach-1         , 5
Up Type= 0
Dn Type= 3
Dn Slope=0.05
Boundary for River Rch & Prof#=Deep Creek,Reach-1         , 6
Up Type= 0
Dn Type= 3
Dn Slope=0.05
Boundary for River Rch & Prof#=Deep Creek,Reach-1         , 7
Up Type= 0
Dn Type= 3
Dn Slope=0.05
DSS Import GetInterval= 0
DSS Import GetPeak= 0
DSS Import FillOption= 0

--- Deep Creek.g01 (geometry) ---

Geom Title=Existing Conditions

River Reach=Deep Creek,Reach-1
Reach XY= 30
      2240375.00     13844190.12      2240185.76     13843984.68
      2240127.36     13843869.48      2240123.61     13843734.67
      2240074.23     13843635.05      2240077.31     13843580.56
      2240124.91     13843490.39      2240077.38     13843419.03
      2240067.14     13843318.83      2239777.45     13843030.47
      2239630.93     13843022.75      2239411.37     13842911.55
      2239378.53     13842873.72      2239372.73     13842780.49
      2239348.82     13842748.13      2239231.05     13842633.14
      2239080.61     13842569.41      2239066.72     13842519.23
      2238998.51     13842448.00      2238915.32     13842414.22
      2238788.12     13842288.22      2238776.78     13842231.14
      2238824.48     13842159.78      2238821.26     13842026.56
      2238781.14     13841977.17      2238766.84     13841918.95
      2238680.85     13841827.29      2238616.86     13841668.94
      2238335.51     13841384.79      2238325.00     13841325.00

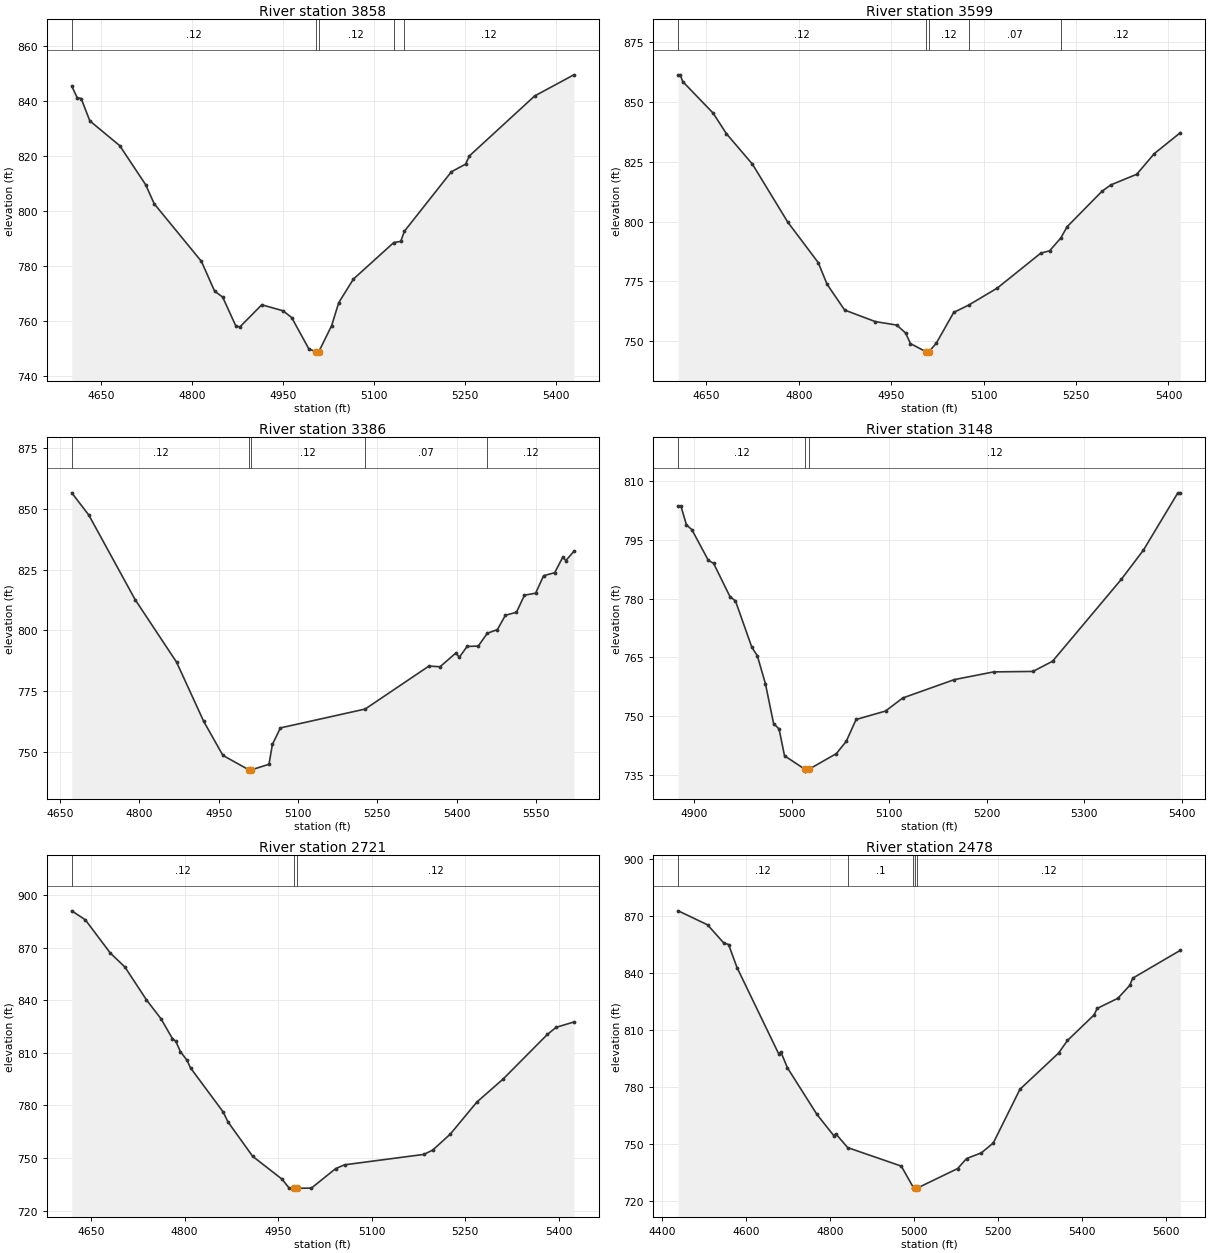
Type RM Length L Ch R = 1,3858,259,259,259
BEGIN DESCRIPTION:
X18822
END DESCRIPTION:
XS GIS Cut Line= 3
      2240590.15     13843828.21      2240311.17     13844144.89
      2239934.14     13844295.70
#Sta/Elev= 30
  4601.9  845.51  4610.8  841.26  4617.4  840.95  4631.7  832.80  4681.0  823.78
  4723.7  809.58  4737.9  802.60  4815.7  781.63  4837.5  770.77  4850.8  768.61
  4872.6  758.03  4879.3  757.76  4915.3  765.80  4950.4  763.61  4964.6  761.15
  4993.1  749.66  5005.3  748.69  5005.6  748.19  5009.3  748.69  5030.6  758.25
  5042.2  766.58  5066.4  775.16  5133.0  788.48  5144.5  788.90  5150.4  792.56
  5228.0  814.26  5251.4  817.04  5257.6  820.02  5365.3  841.87  5430.0  849.58
#Mann=5,-1,0
  4601.9    0.12       0  5005.3    0.05       0  5009.3    0.12       0
  5133.0    0.07       0  5150.4    0.12       0
Bank Sta=5005.3,5009.3
Exp/Cntr=0.3,0.1

Type RM Length L Ch R = 1,3599,213,213,213
BEGIN DESCRIPTION:
Deep Creek 8.0
END DESCRIPTION:
XS GIS Cut Line= 3
      2240475.01     13843674.99      2240175.00     13843925.00
      2239874.99     13844225.01
#Sta/Elev= 30
  4604.4  861.33  4607.7  861.33  4611.6  858.54  4661.0  845.33  4682.5  836.75
  4724.8  823.99  4782.1  799.77  4831.6  782.82  4845.9  773.78  4874.5  762.98
  4924.0  758.17  4959.1  756.69  4973.4  753.39  4981.3  748.95  5007.1  745.47
  5007.3  744.97  5011.1  745.47  5023.2  749.14  5051.5  761.99  5076.3  765.13
  5122.2  772.18  5192.9  786.80  5207.1  787.75  5225.5  793.18  5235.3  797.77
  5291.9  812.59  5306.1  815.27  5348.5  819.75  5376.8  828.35  5419.2  837.13
#Mann=5,-1,0
  4604.4    0.12       0  5007.1    0.05       0  5011.1    0.12       0
  5076.3    0.07       0  5225.5    0.12       0
Bank Sta=5007.1,5011.1
Exp/Cntr=0.3,0.1

Type RM Length L Ch R = 1,3386,238,238,238
BEGIN DESCRIPTION:
X18821
END DESCRIPTION:
XS GIS Cut Line= 3
      2240397.86     13843553.02      2240032.20     13843790.52
      2239749.82     13844219.74
#Sta/Elev= 30
  4672.1  856.61  4704.3  847.46  4791.9  812.63  4870.4  786.82  4921.8  762.40
  4958.0  748.43  5007.4  742.44  5007.6  741.94  5011.4  742.44  5045.2  744.77
  5051.6  752.93  5066.8  759.75  5227.1  767.52  5347.8  785.23  5368.8  784.95
  5399.0  790.66  5405.0  788.81  5420.1  793.33  5441.1  793.47  5458.1  798.73
  5477.3  800.27  5492.4  806.16  5513.4  807.41  5528.5  814.44  5549.6  815.26
  5564.7  822.47  5585.7  823.70  5600.8  830.05  5606.8  828.72  5621.9  832.48
#Mann=5,-1,0
  4672.1    0.12       0  5007.4    0.05       0  5011.4    0.12       0
  5227.1    0.07       0  5458.1    0.12       0
Bank Sta=5007.4,5011.4
Exp/Cntr=0.3,0.1

Type RM Length L Ch R = 1,3148,427,427,427
BEGIN DESCRIPTION:
Deep Creek 7.0
END DESCRIPTION:
XS GIS Cut Line= 3
      2240225.01     13843475.00      2240125.00     13843525.00
      2239725.02     13843575.00
#Sta/Elev= 30
  4883.6  803.59  4886.4  803.59  4892.0  798.83  4897.6  797.58  4914.4  789.78
  4919.9  788.98  4936.7  780.47  4942.3  779.40  4959.1  767.56  4964.7  765.40
  4973.0  758.28  4981.4  748.09  4987.0  746.72  4992.6  739.87  5013.4  736.45
  5013.7  735.95  5017.8  736.45  5045.8  740.43  5055.9  743.56  5066.0  749.13
  5096.2  751.29  5113.8  754.62  5166.7  759.31  5207.0  761.28  5247.4  761.40
  5267.5  764.01  5338.1  784.94  5360.7  792.38  5396.0  806.99  5398.5  806.99
#Mann=3,-1,0
  4883.6    0.12       0  5013.4    0.05       0  5017.8    0.12       0
Bank Sta=5013.4,5017.8
Exp/Cntr=0.3,0.1

Type RM Length L Ch R = 1,2721,243,243,243
BEGIN DESCRIPTION:
Deep Creek 6.0
END DESCRIPTION:
XS GIS Cut Line= 3
      2240275.02     13843024.99      2239925.00     13843175.00
      2239624.98     13843475.02
#Sta/Elev= 30
  4619.2  890.95  4641.0  885.81  4680.9  866.92  4704.4  858.94  4738.9  840.23
  4762.5  829.33  4780.6  818.12  4786.0  816.62  4793.3  810.77  4804.2  805.65
  4809.6  801.44  4862.2  776.21  4869.5  770.73  4909.3  751.03  4956.5  737.97
  4967.4  733.08  4976.1  732.83  4976.4  732.33  4980.5  732.83  5003.5  732.92
  5042.4  744.04  5056.6  746.19  5183.9  752.13  5198.0  754.59  5226.3  763.74
  5268.7  781.93  5311.1  795.15  5381.8  820.49  5396.0  824.56  5424.3  827.59
#Mann=3,-1,0
  4619.2    0.12       0  4976.1    0.05       0  4980.5    0.12       0
Bank Sta=4976.1,4980.5
Exp/Cntr=0.3,0.1

Type RM Length L Ch R = 1,2478,337,337,337
BEGIN DESCRIPTION:
X18820
END DESCRIPTION:
XS GIS Cut Line= 3
      2240254.67     13842938.52      2239858.78     13842908.36
      2239293.33     13843473.81
#Sta/Elev= 30
  4438.6  872.65  4508.5  865.29  4547.2  855.74  4558.6  854.93  4578.7  842.83
  4678.2  797.37  4683.2  798.41  4699.0  790.06  4769.2  765.59  4809.2  754.47
  4814.2  755.37  4842.5  748.14  4970.3  738.40  4999.2  727.08  5003.4  726.80
  5003.7  726.30  5007.9  726.80  5104.6  737.12  5125.8  742.38  5161.2  745.39
  5189.5  750.57  5253.1  778.82  5345.0  797.81  5366.3  804.47  5429.9  817.94
  5437.0  821.32  5486.5  826.66  5514.8  833.45  5521.8  837.22  5635.3  851.88
#Mann=5,-1,0
  4438.6    0.12       0  4842.5     0.1       0  4999.2    0.12       0
  5003.4    0.05       0  5007.9    0.12       0
Bank Sta=5003.4,5007.9
Exp/Cntr=0.3,0.1

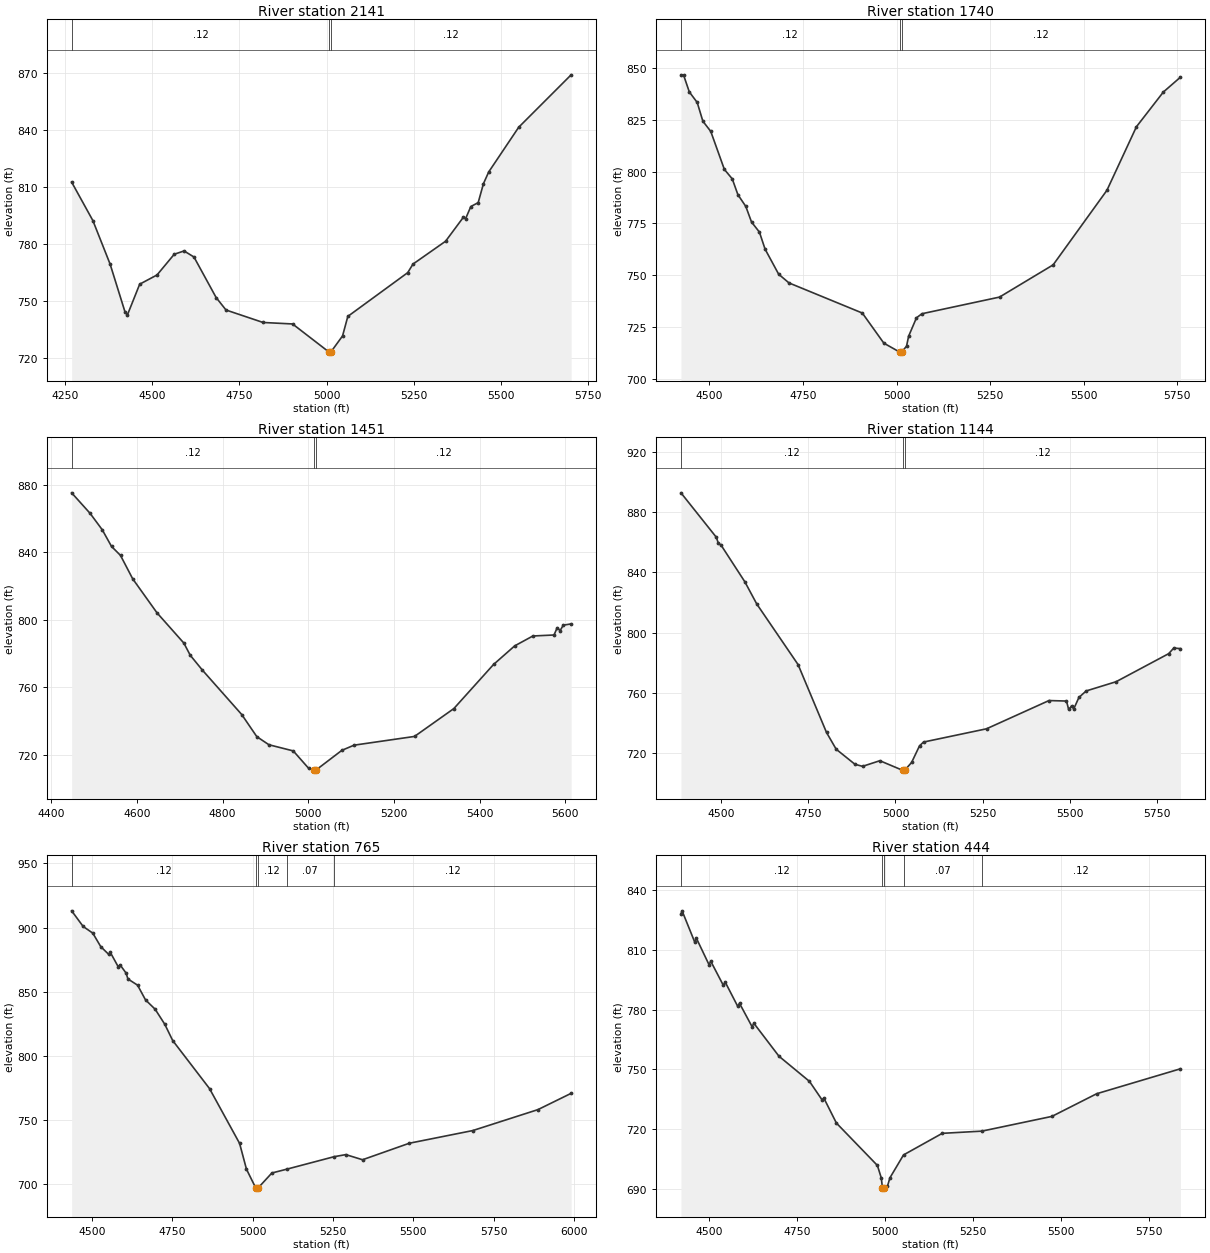
Type RM Length L Ch R = 1,2141,401,401,401
BEGIN DESCRIPTION:
X18819
END DESCRIPTION:
XS GIS Cut Line= 3
      2239964.37     13842418.25      2239444.10     13842912.13
      2239052.52     13843510.78
#Sta/Elev= 30
  4268.8  812.45  4329.7  792.20  4379.1  769.32  4421.5  744.35  4428.8  742.57
  4464.0  758.73  4513.7  763.58  4563.1  774.49  4591.4  776.22  4619.7  773.02
  4683.3  751.69  4711.6  745.14  4817.9  738.58  4902.5  737.80  5007.5  722.95
  5007.8  722.45  5012.0  722.95  5045.9  731.51  5061.0  741.78  5232.8  764.80
  5247.9  769.31  5341.4  781.33  5392.7  794.01  5398.7  793.14  5413.8  799.59
  5434.9  801.64  5450.0  811.62  5465.1  817.79  5551.2  841.33  5701.5  868.90
#Mann=3,-1,0
  4268.8    0.12       0  5007.5    0.05       0  5012.0    0.12       0
Bank Sta=5007.5,5012
Exp/Cntr=0.3,0.1

Type RM Length L Ch R = 1,1740,289,289,289
BEGIN DESCRIPTION:
X18818
END DESCRIPTION:
XS GIS Cut Line= 3
      2239523.26     13842143.07      2239195.28     13842648.24
      2238765.54     13843240.07
#Sta/Elev= 30
  4424.4  846.68  4431.5  846.50  4446.7  838.44  4467.8  833.35  4482.9  824.32
  4504.0  819.38  4540.3  801.06  4561.4  796.49  4576.5  788.84  4597.6  783.19
  4612.8  775.69  4633.9  770.82  4649.0  762.61  4685.3  750.51  4712.8  746.31
  4908.7  731.77  4966.1  717.26  5008.5  712.94  5008.8  712.44  5013.4  712.94
  5026.7  715.76  5032.3  720.60  5053.2  729.46  5067.8  731.44  5275.0  739.47
  5418.2  755.02  5561.8  790.98  5640.6  821.64  5712.5  838.39  5758.1  845.54
#Mann=3,-1,0
  4424.4    0.12       0  5008.5    0.05       0  5013.4    0.12       0
Bank Sta=5008.5,5013.4
Exp/Cntr=0.3,0.1

Type RM Length L Ch R = 1,1451,307,307,307
BEGIN DESCRIPTION:
X18817
END DESCRIPTION:
XS GIS Cut Line= 2
      2239376.24     13842045.05      2238592.07     13842908.38
#Sta/Elev= 30
  4447.4  875.19  4490.5  863.02  4518.9  853.28  4540.5  843.43  4561.5  838.09
  4589.9  824.25  4646.6  804.10  4709.5  786.11  4724.3  778.93  4752.7  770.11
  4844.6  743.77  4879.8  730.67  4908.1  725.87  4964.9  722.22  5000.7  711.93
  5012.2  710.74  5012.6  710.24  5017.2  710.74  5078.4  722.57  5106.8  725.62
  5248.0  730.80  5339.9  747.32  5432.5  773.44  5481.9  784.47  5524.4  790.34
  5573.8  790.93  5581.2  795.27  5588.0  793.54  5595.4  796.75  5613.7  797.50
#Mann=3,-1,0
  4447.4    0.12       0  5012.2    0.05       0  5017.2    0.12       0
Bank Sta=5012.2,5017.2
Exp/Cntr=0.3,0.1

Type RM Length L Ch R = 1,1144,379,379,379
BEGIN DESCRIPTION:
X18816
END DESCRIPTION:
XS GIS Cut Line= 3
      2239315.94     13841969.64      2238693.88     13842308.94
      2238268.92     13842895.62
#Sta/Elev= 30
  4384.5  892.92  4486.0  863.37  4491.7  859.43  4499.5  858.18  4567.7  833.82
  4602.0  819.03  4720.5  778.76  4802.1  733.64  4829.8  722.51  4883.8  712.47
  4905.6  711.13  4955.1  714.86  5021.0  708.44  5021.4  707.94  5026.0  708.44
  5046.2  713.68  5068.9  724.74  5080.4  727.26  5261.1  736.07  5440.4  754.85
  5490.6  754.52  5496.8  748.91  5505.3  751.26  5511.5  749.34  5526.2  756.91
  5547.1  761.24  5632.9  767.37  5783.7  786.01  5798.4  789.75  5817.5  789.36
#Mann=3,-1,0
  4384.5    0.12       0  5021.0    0.05       0  5026.0    0.12       0
Bank Sta=5021,5026
Exp/Cntr=0.3,0.1

Type RM Length L Ch R = 1,765,321,321,321
BEGIN DESCRIPTION:
X18815
END DESCRIPTION:
XS GIS Cut Line= 3
      2239293.29     13841717.07      2238644.88     13841965.88
      2238298.04     13842753.81
#Sta/Elev= 30
  4436.2  912.99  4472.1  900.80  4502.1  895.62  4526.8  885.13  4551.4  879.13
  4556.8  880.56  4581.4  869.35  4586.8  870.98  4605.7  864.53  4611.5  859.92
  4641.5  855.10  4666.2  843.65  4696.2  836.37  4726.2  824.68  4750.9  811.98
  4865.6  774.55  4959.2  731.89  4980.6  711.81  5010.3  696.77  5010.7  696.27
  5015.3  696.77  5059.7  708.83  5105.3  711.75  5253.1  721.50  5290.0  723.15
  5342.1  719.15  5487.6  732.00  5685.2  741.87  5888.3  758.19  5991.6  770.86
#Mann=5,-1,0
  4436.2    0.12       0  5010.3    0.05       0  5015.3    0.12       0
  5105.3    0.07       0  5253.1    0.12       0
Bank Sta=5010.3,5015.3
Exp/Cntr=0.3,0.1

Type RM Length L Ch R = 1,444,359,359,359
BEGIN DESCRIPTION:
X18814
END DESCRIPTION:
XS GIS Cut Line= 3
      2239165.13     13841509.72      2238607.18     13841652.98
      2238004.56     13842240.54
#Sta/Elev= 30
  4421.2  827.96  4424.4  829.70  4460.0  814.11  4465.2  815.85  4500.8  802.63
  4505.9  804.31  4541.5  792.22  4546.7  793.89  4582.3  781.67  4587.4  783.19
  4623.0  771.44  4628.2  773.13  4699.4  756.57  4786.0  743.91  4821.6  734.65
  4826.8  735.52  4862.4  722.96  4978.8  701.63  4989.8  695.35  4993.2  690.23
  4993.6  689.73  4998.4  690.23  5007.3  691.20  5014.3  695.41  5052.9  706.93
  5162.9  717.79  5275.5  718.90  5474.1  726.31  5601.2  737.71  5838.9  750.25
#Mann=5,-1,0
  4421.2    0.12       0  4993.2    0.05       0  4998.4    0.12       0
  5052.9    0.07       0  5275.5    0.12       0
Bank Sta=4993.2,4998.4
Exp/Cntr=0.3,0.1

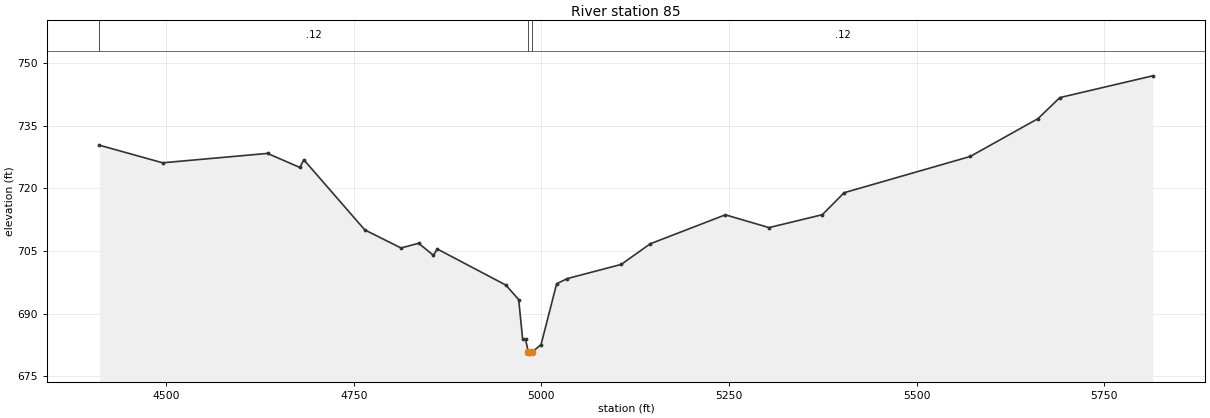
Type RM Length L Ch R = 1,85,0,0,0
BEGIN DESCRIPTION:
X18813
END DESCRIPTION:
XS GIS Cut Line= 4
      2238920.07     13841260.91      2238369.67     13841385.32
      2238264.12     13841472.03      2237989.54     13842118.98
#Sta/Elev= 30
  4411.0  730.31  4495.3  726.09  4635.1  728.34  4678.3  724.97  4683.4  726.83
  4764.7  710.03  4813.0  705.70  4836.5  706.83  4856.2  703.94  4861.3  705.46
  4952.8  696.81  4969.8  693.34  4975.1  683.81  4979.0  683.81  4982.6  680.79
  4983.0  680.29  4987.8  680.79  4999.6  682.57  5020.4  697.14  5034.7  698.38
  5106.5  701.77  5145.1  706.70  5245.2  713.64  5303.4  710.58  5374.4  713.67
  5403.5  718.93  5571.4  727.60  5661.8  736.66  5690.9  741.70  5814.7  746.91
#Mann=3,-1,0
  4411.0    0.12       0  4982.6    0.05       0  4987.8    0.12       0
Bank Sta=4982.6,4987.8
Exp/Cntr=0.3,0.1

Chan Stop Cuts=-1