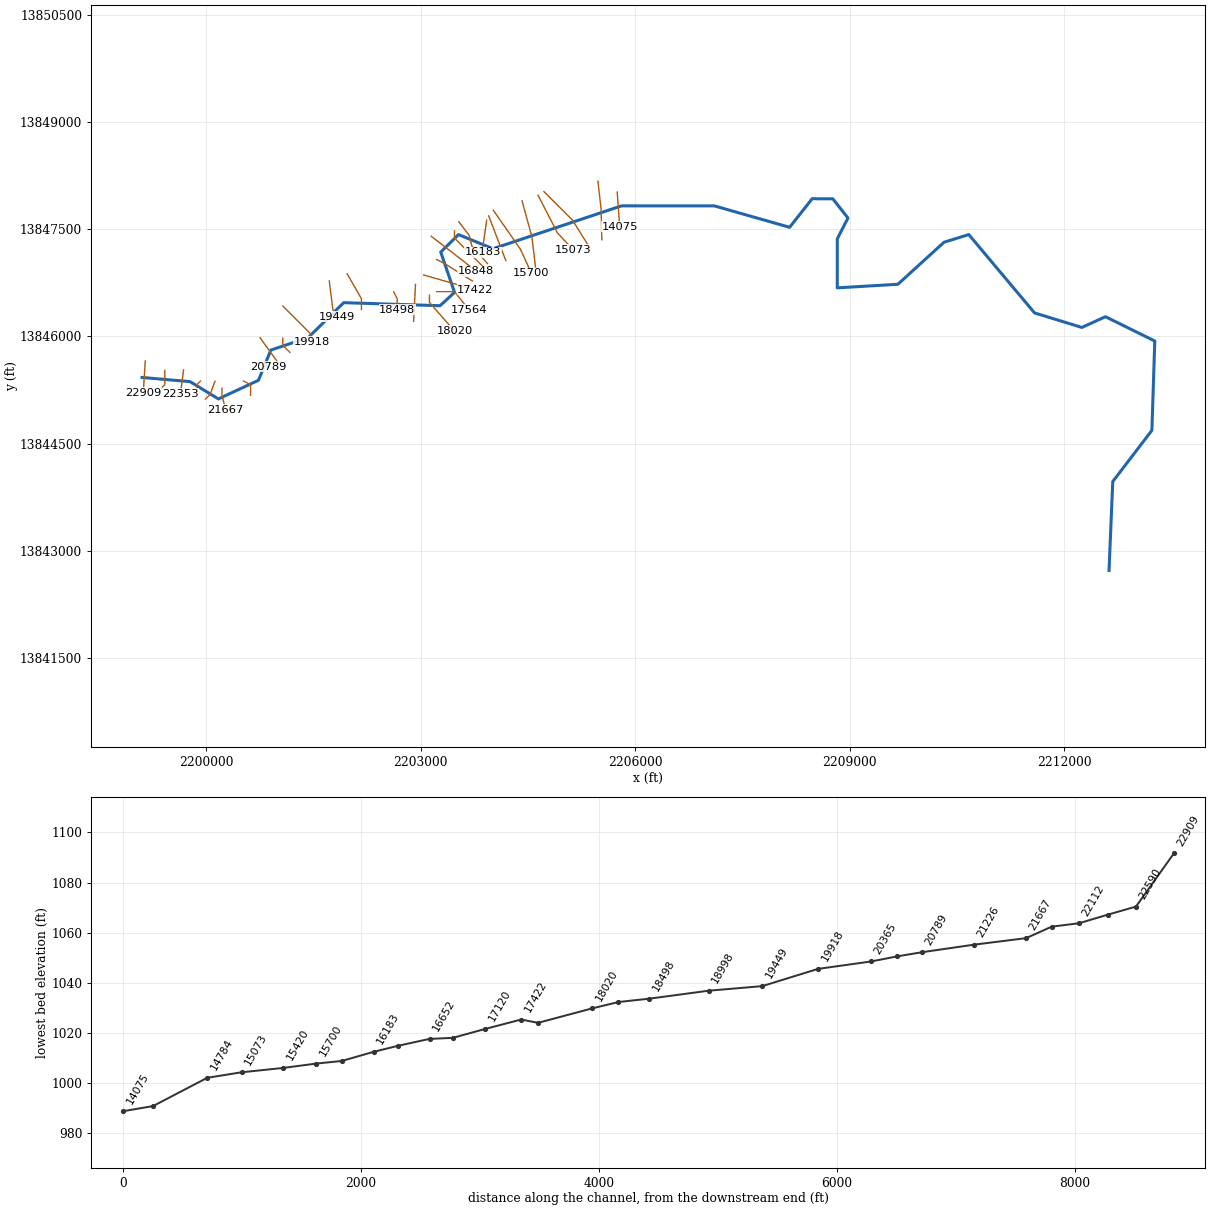
--- Dry Bear Creek.prj (project) ---

Proj Title=Dry Bear Creek Base Level Engineering
Current Plan=p01
Default Exp/Contr=0.3,0.1
English Units
Geom File=g01
Flow File=f01
Plan File=p01
Y Axis Title=Elevation
X Axis Title(PF)=Main Channel Distance
X Axis Title(XS)=Station
BEGIN DESCRIPTION:
Dry Bear Creek
END DESCRIPTION:
DSS Export Rating Curves= 0
DSS Export Rating Curve Sorted= 0
DSS Export Volume Flow Curves= 0
DXF OffsetX= 0
DXF OffsetY= 0
DXF ScaleX= 1
DXF ScaleY= 10

--- Dry Bear Creek.p01 (plan) ---

Plan Title=Multiple Run
Short Identifier=Multiple
Geom File=g01
Flow File=f01
Subcritical Flow
K Sum by GR= 0
Std Step Tol= 0.01
Critical Tol= 0.01
Num of Std Step Trials= 20
Max Error Tol= 0.3
Flow Tol Ratio= 0.001
Split Flow NTrial= 30
Split Flow Tol= 0.02
Split Flow Ratio= 0.02
Log Output Level= 0
Friction Slope Method= 1
Unsteady Friction Slope Method= 2
Unsteady Bridges Friction Slope Method= 1
Parabolic Critical Depth
Global Vel Dist=  1 , 1 , 1
Global Log Level= 0
CheckData=True
Encroach Param= -1, 0, 0, 0
BEGIN DESCRIPTION:
Multiple Run
END DESCRIPTION:

--- Dry Bear Creek.f01 (steady flow) ---

Flow Title=Multiple
Number of Profiles=7
Profile Names=10-year,25-year,50-year,1pct_min,100-year,1pct_plu,500-year
River Rch & RM= Dry Bear Creek,Reach-1,22909
    1063    1793    2485    1669    3329    6643    5911
River Rch & RM= Dry Bear Creek,Reach-1,21667
    1886    3282    4642    3174    6332   12635   11671
River Rch & RM= Dry Bear Creek,Reach-1,16183
    2312    4050    5755    3951    7884   15730   14649
River Rch & RM= Dry Bear Creek,Reach-1,15420
    2536    4447    6322    4340    8660   17279   16090
River Rch & RM= Dry Bear Creek,Reach-1,10999
    2955    5211    7435    5120   10215   20382   19096
River Rch & RM= Dry Bear Creek,Reach-1,6863
    3042    5364    7652    5267   10509   20969   19631
River Rch & RM= Dry Bear Creek,Reach-1,4224
    3251    5745    8208    5657   11287   22520   21135
River Rch & RM= Dry Bear Creek,Reach-1,2312
    3429    6066    8674    5982   11935   23813   22375
Boundary for River Rch & Prof#=Dry Bear Creek,Reach-1,1
Up Type=0
Dn Type=3
Dn Slope=0.005
Boundary for River Rch & Prof#=Dry Bear Creek,Reach-1,2
Up Type=0
Dn Type=3
Dn Slope=0.005
Boundary for River Rch & Prof#=Dry Bear Creek,Reach-1,3
Up Type=0
Dn Type=3
Dn Slope=0.005
Boundary for River Rch & Prof#=Dry Bear Creek,Reach-1,4
Up Type=0
Dn Type=3
Dn Slope=0.005
Boundary for River Rch & Prof#=Dry Bear Creek,Reach-1,5
Up Type=0
Dn Type=3
Dn Slope=0.005
Boundary for River Rch & Prof#=Dry Bear Creek,Reach-1,6
Up Type=0
Dn Type=3
Dn Slope=0.005
Boundary for River Rch & Prof#=Dry Bear Creek,Reach-1,7
Up Type=0
Dn Type=3
Dn Slope=0.005

--- Dry Bear Creek.g01 (geometry) ---

Geom Title=Existing Conditions
Program Version=4.10

River Reach=Dry Bear Creek  ,Reach-1
Reach XY= 30
      2199107.57       13845425.       2199778.3     13845366.92
        2200175.       13845125.      2200734.73     13845385.76
      2200908.21     13845808.56      2201431.06     13845983.14
      2201926.47     13846471.45      2203273.42     13846428.67
      2203475.82     13846614.93      2203283.04     13847178.32
      2203531.04     13847423.38      2204014.31     13847225.77
      2205809.82     13847825.43      2207109.78     13847824.48
      2208159.84     13847525.36        2208475.       13847925.
       2208764.5      13847923.8      2208975.29     13847654.82
       2208826.2      13847364.5      2208826.22     13846678.43
      2209673.45     13846728.75      2210318.68     13847316.92
       2210664.5      13847423.8      2211583.34     13846328.17
      2212245.18     13846124.72        2212575.       13846275.
      2213264.52      13845934.8      2213224.23     13844685.69
      2212677.07     13843969.14        2212625.       13842725.

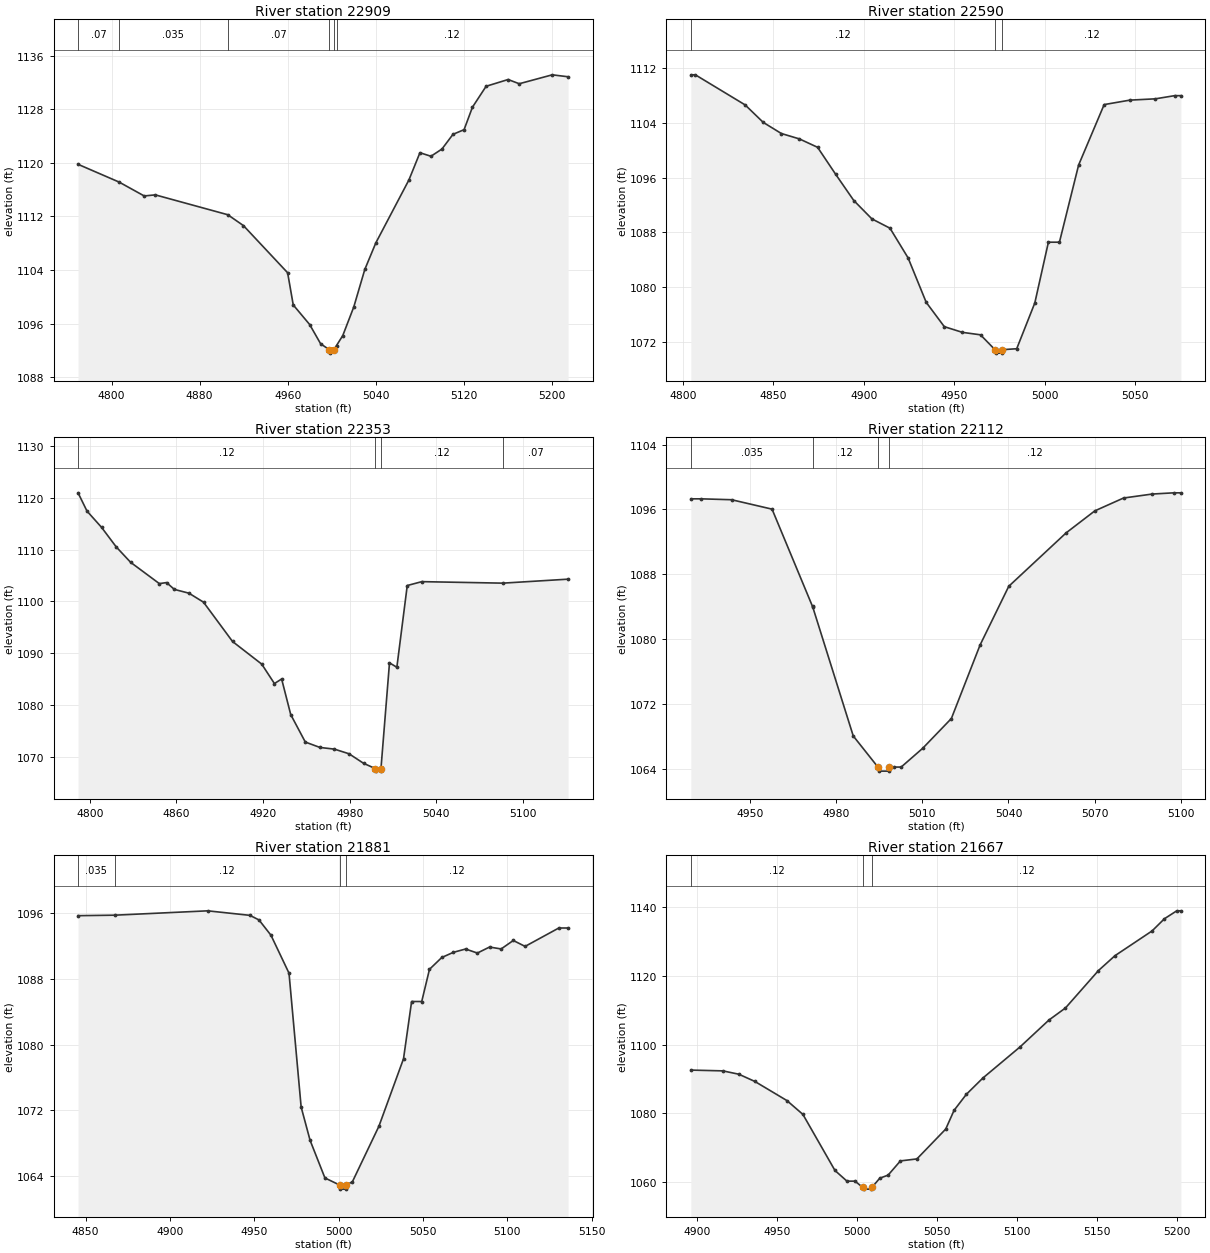
Type RM Length L Ch R = 1 ,22909   ,319,319,319
BEGIN DESCRIPTION:
X18889
END DESCRIPTION:
XS GIS Cut Line= 2
      2199151.84     13845655.02       2199124.9     13845210.64
#Sta/Elev= 30
  4769.6 1119.77  4806.9 1117.12  4829.7 1115.05  4839.8 1115.21  4905.6 1112.25
  4919.9 1110.62    4960 1103.59  4965.1 1098.79    4980 1095.87    4990 1092.99
    4998  1092.1  4998.3  1091.6    5002  1092.1  5004.4 1092.73  5010.1 1094.22
  5020.1 1098.49  5030.1 1104.08  5040.1 1108.04  5070.2 1117.44  5080.2  1121.5
  5090.2 1120.97  5100.2 1122.05  5110.2 1124.24  5120.3 1124.94  5127.9 1128.29
  5140.3 1131.41  5160.3 1132.42  5170.4 1131.79  5200.4 1133.12  5214.8 1132.83
#Mann= 6 ,-1 , 0
  4769.6     .07       0  4806.9    .035       0  4905.6     .07       0
    4998     .05       0    5002     .07       0  5004.4     .12       0
Bank Sta=4998,5002
XS Rating Curve= 0 ,0
Exp/Cntr=0.3,0.1

Type RM Length L Ch R = 1 ,22590   ,237,237,237
BEGIN DESCRIPTION:
Dry Bear Creek 49.0
END DESCRIPTION:
XS GIS Cut Line= 3
        2199425.     13845525.03        2199425.       13845325.
      2199375.03     13845275.03
#Sta/Elev= 30
  4804.5 1110.99    4807 1110.99  4834.5  1106.6  4844.5 1104.05  4854.5 1102.43
  4864.5 1101.64  4874.5 1100.42  4884.5 1096.48  4894.5 1092.66  4904.5 1089.98
  4914.5 1088.62  4924.5 1084.29  4934.5 1077.81  4944.5 1074.26  4954.5 1073.43
  4964.5 1073.07  4972.5  1070.9  4972.8  1070.4  4976.3  1070.4  4976.5  1070.9
  4984.5 1071.04  4994.5 1077.72    5002 1086.58  5008.1 1086.58  5018.7 1097.84
  5032.8 1106.65    5047  1107.3  5061.1 1107.49  5071.7 1107.95  5075.2 1107.95
#Mann= 3 ,-1 , 0
  4804.5     .12       0  4972.5     .05       0  4976.5     .12       0
Bank Sta=4972.5,4976.5
XS Rating Curve= 0 ,0
Exp/Cntr=0.3,0.1

Type RM Length L Ch R = 1 ,22353   ,241,241,241
BEGIN DESCRIPTION:
X18888
END DESCRIPTION:
XS GIS Cut Line= 2
      2199687.75     13845531.15      2199644.66      13845194.5
#Sta/Elev= 30
  4791.9 1120.98  4798.1 1117.45  4808.2  1114.3  4818.3 1110.54  4828.3 1107.55
  4848.2 1103.43  4853.2 1103.63  4858.6 1102.31  4868.7 1101.58  4878.8 1099.84
  4898.9 1092.24  4919.1 1087.87  4927.9 1084.11  4932.9 1084.99  4939.2 1078.11
  4949.3  1072.8  4959.4 1071.76  4969.5 1071.43  4979.6 1070.53  4989.6  1068.7
  4997.7 1067.68    4998 1067.18  5001.5 1067.18  5001.7 1067.68  5007.6 1088.11
  5012.7 1087.26  5019.9 1103.06    5030 1103.81  5086.1 1103.52  5131.3 1104.29
#Mann= 4 ,-1 , 0
  4791.9     .12       0  4997.7     .05       0  5001.7     .12       0
  5086.1     .07       0
Bank Sta=4997.7,5001.7
XS Rating Curve= 0 ,0
Exp/Cntr=0.3,0.1

Type RM Length L Ch R = 1 ,22112   ,231,231,231
BEGIN DESCRIPTION:
Dry Bear Creek 48.0
END DESCRIPTION:
XS GIS Cut Line= 3
      2199925.03     13845375.03        2199875.       13845325.
        2199875.     13845224.96
#Sta/Elev= 23
  4929.3 1097.31  4932.9 1097.31  4943.5  1097.2  4957.6 1096.04  4971.7 1084.06
  4971.8 1083.97  4985.9 1068.11  4994.5 1064.28  4994.8 1063.78  4998.3 1063.78
  4998.5 1064.28  5000.1 1064.28  5002.6 1064.28  5010.1 1066.59  5020.1 1070.26
  5030.1 1079.31  5040.1 1086.54  5060.1 1093.12  5070.1 1095.83  5080.1 1097.41
  5090.1  1097.9  5097.6 1098.05  5100.1 1098.05
#Mann= 4 ,-1 , 0
  4929.3    .035       0  4971.7     .12       0  4994.5     .05       0
  4998.5     .12       0
Bank Sta=4994.5,4998.5
XS Rating Curve= 0 ,0
Exp/Cntr=0.3,0.1

Type RM Length L Ch R = 1 ,21881   ,214,214,214
BEGIN DESCRIPTION:
X18887
END DESCRIPTION:
XS GIS Cut Line= 3
      2200126.71     13845372.27      2200056.69     13845183.75
      2199992.08     13845121.83
#Sta/Elev= 30
  4845.5 1095.69  4867.3 1095.75  4922.4 1096.28  4947.4 1095.73  4952.8 1095.17
  4959.9 1093.31  4970.6 1088.69  4977.8 1072.39  4983.1 1068.34  4991.9 1063.76
  5000.6  1062.9  5000.9  1062.4  5004.4  1062.4  5004.6  1062.9  5008.2  1063.3
  5023.9 1070.05  5038.5 1078.27  5043.3 1085.24  5049.3 1085.24  5053.9 1089.16
  5061.2  1090.6  5068.1 1091.23  5075.3 1091.63  5082.3 1091.14  5089.5 1091.87
  5096.4 1091.64  5103.6 1092.67  5110.6 1091.95  5130.6 1094.19  5136.1 1094.19
#Mann= 4 ,-1 , 0
  4845.5    .035       0  4867.3     .12       0  5000.6     .05       0
  5004.6     .12       0
Bank Sta=5000.6,5004.6
XS Rating Curve= 0 ,0
Exp/Cntr=0.3,0.1

Type RM Length L Ch R = 1 ,21667   ,441,441,441
BEGIN DESCRIPTION:
Dry Bear Creek 47.0
END DESCRIPTION:
XS GIS Cut Line= 3
        2200225.     13845274.97        2200225.       13845175.
      2200274.99     13844975.02
#Sta/Elev= 30
  4896.3 1092.56  4916.3 1092.33  4926.3 1091.35  4936.3 1089.24  4956.3 1083.67
  4966.3 1079.63  4986.3 1063.29  4993.8 1060.17  4998.8 1060.17  5003.7 1058.34
  5004.2 1057.84    5009 1057.84  5009.4 1058.34  5014.3 1061.03  5019.5 1061.92
  5027.2 1066.07  5037.5 1066.65  5055.5 1075.36  5060.7 1080.81  5068.4  1085.5
  5078.7 1090.24  5101.9 1099.31    5120 1107.17  5130.3 1110.68  5150.9 1121.59
  5161.2 1125.92  5184.4 1133.15  5192.1  1136.7  5199.8 1139.01  5202.4 1139.01
#Mann= 3 ,-1 , 0
  4896.3     .12       0  5003.7     .05       0  5009.4     .12       0
Bank Sta=5003.7,5009.4
XS Rating Curve= 0 ,0
Exp/Cntr=0.3,0.1

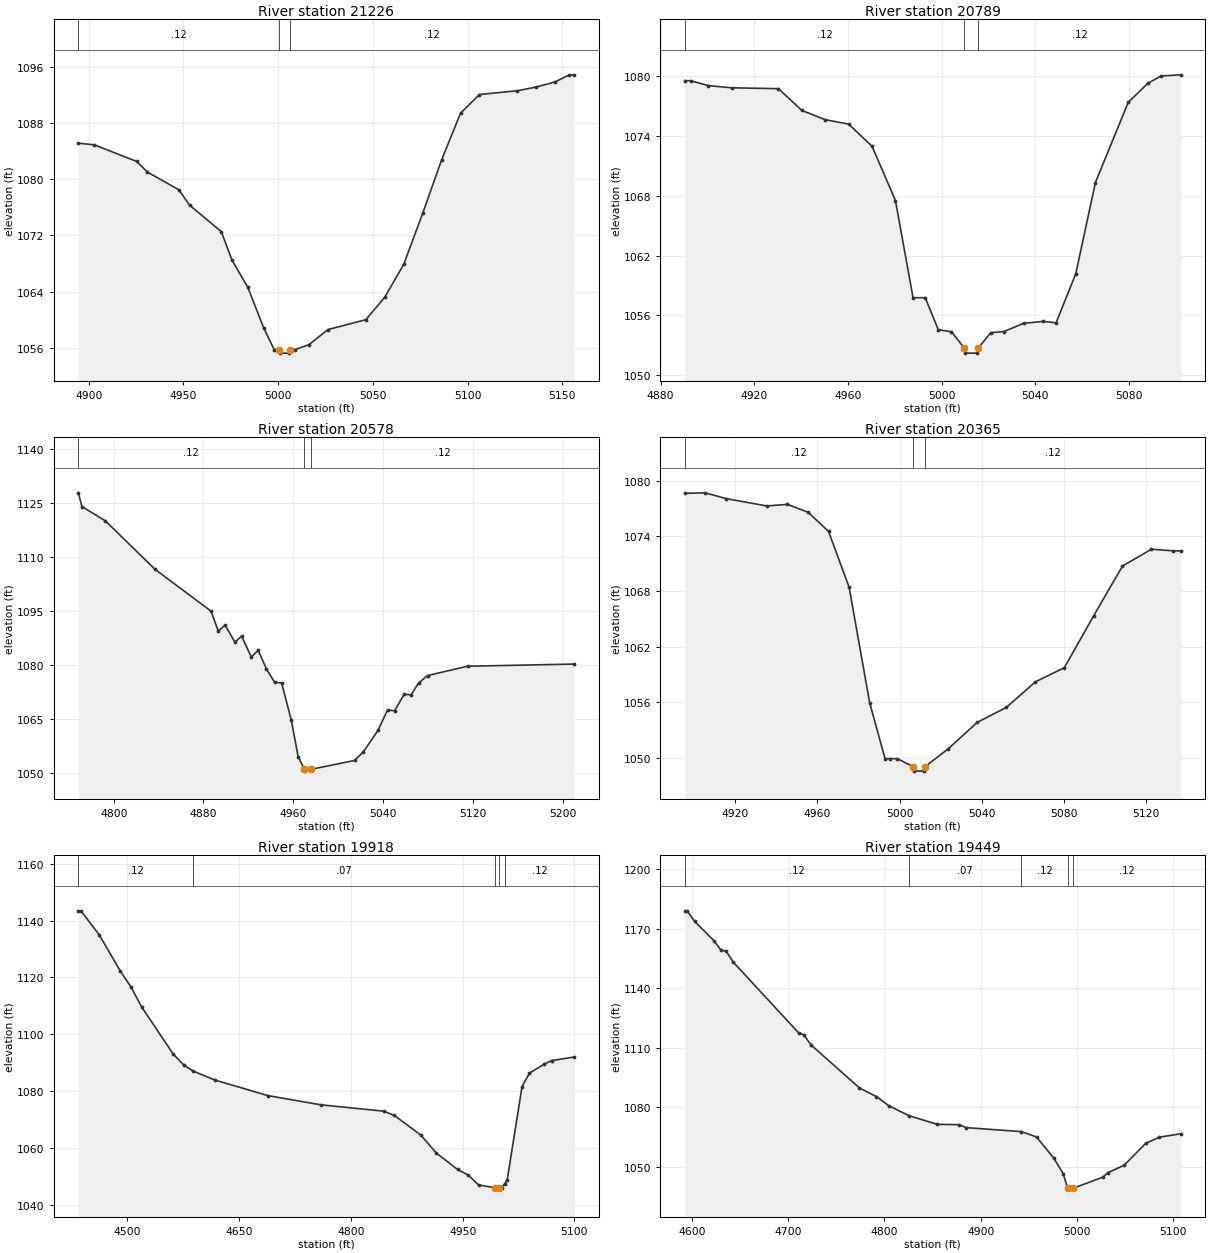
Type RM Length L Ch R = 1 ,21226   ,437,437,437
BEGIN DESCRIPTION:
Dry Bear Creek 46.0
END DESCRIPTION:
XS GIS Cut Line= 3
      2200524.98     13845375.01        2200625.       13845325.
        2200625.     13845175.03
#Sta/Elev= 30
  4894.5 1085.16  4902.9 1084.93  4925.3 1082.56  4930.9 1081.06  4947.6 1078.51
  4953.2 1076.33    4970 1072.54  4975.6  1068.5    4984  1064.6  4992.4  1058.8
  4997.9 1055.73  5000.7 1055.72  5001.1 1055.22  5005.9 1055.22  5006.4 1055.72
  5008.8 1055.72  5016.3 1056.43  5026.3 1058.58  5046.3 1059.99  5056.3  1063.2
  5066.3 1067.87  5076.3 1075.14  5086.3 1082.77  5096.3 1089.43  5106.3  1092.1
  5126.3 1092.64  5136.3 1093.17  5146.3 1093.91  5153.8 1094.91  5156.3 1094.91
#Mann= 3 ,-1 , 0
  4894.5     .12       0  5000.7     .05       0  5006.4     .12       0
Bank Sta=5000.7,5006.4
XS Rating Curve= 0 ,0
Exp/Cntr=0.3,0.1

Type RM Length L Ch R = 1 ,20789   ,211,211,211
BEGIN DESCRIPTION:
Dry Bear Creek 45.0
END DESCRIPTION:
XS GIS Cut Line= 3
      2200675.05       13845625.        2200775.       13845625.
      2200875.04     13845574.98
#Sta/Elev= 29
  4890.3 1079.53  4892.8 1079.53  4900.3 1079.04  4910.3 1078.82  4930.3 1078.73
  4940.3 1076.55  4950.3 1075.62  4960.3 1075.18  4970.3 1072.95  4980.3  1067.5
  4987.8 1057.77    4993 1057.77  4998.6 1054.55  5004.2 1054.36  5009.7 1052.71
  5010.2 1052.21  5015.1 1052.21  5015.6 1052.71    5021 1054.26  5026.6 1054.37
    5035  1055.2  5043.4 1055.39  5048.9 1055.25  5057.3 1060.16  5065.7 1069.32
  5079.7 1077.35  5088.1 1079.27  5093.7    1080  5102.1 1080.12
#Mann= 3 ,-1 , 0
  4890.3     .12       0  5009.7     .05       0  5015.6     .12       0
Bank Sta=5009.7,5015.6
XS Rating Curve= 0 ,0
Exp/Cntr=0.3,0.1

Type RM Length L Ch R = 1 ,20578   ,213,213,213
BEGIN DESCRIPTION:
X18886
END DESCRIPTION:
XS GIS Cut Line= 2
       2200756.9     13845980.86      2201015.41     13845622.72
#Sta/Elev= 30
  4768.5 1127.73  4771.7 1123.93  4792.6 1119.95  4836.7 1106.55  4886.7 1094.91
  4893.2 1089.37  4899.3 1091.05  4907.9 1086.32    4914 1087.96  4922.6 1082.17
  4928.7 1084.06  4936.1 1078.85  4943.4 1075.15  4949.6 1074.99  4958.2  1064.7
  4964.3 1054.58  4969.9 1051.03  4970.4 1050.53  4975.8 1051.03  5014.6 1053.49
  5022.4 1055.88  5035.5 1061.85    5044 1067.54  5050.2 1067.24  5058.7 1071.84
  5064.9 1071.69  5071.7    1075  5079.6 1077.04  5115.2 1079.63  5210.2 1080.23
#Mann= 3 ,-1 , 0
  4768.5     .12       0  4969.9     .05       0  4975.8     .12       0
Bank Sta=4969.9,4975.8
XS Rating Curve= 0 ,0
Exp/Cntr=0.3,0.1

Type RM Length L Ch R = 1 ,20365   ,447,447,447
BEGIN DESCRIPTION:
Dry Bear Creek 44.0
END DESCRIPTION:
XS GIS Cut Line= 3
        2201075.     13845974.96        2201075.       13845875.
      2201175.01     13845774.99
#Sta/Elev= 26
  4895.4 1078.62  4905.4 1078.67  4915.4 1078.05  4935.4 1077.25  4945.4 1077.42
  4955.4 1076.57  4965.4 1074.49  4975.4 1068.45  4985.4 1055.95  4992.9  1049.9
  4995.4  1049.9  4998.9  1049.9  5006.5 1049.05    5007 1048.55    5012 1048.55
  5012.5 1049.05  5023.6 1050.96  5037.8 1053.83  5051.9 1055.44  5066.1 1058.21
  5080.2 1059.75  5094.4 1065.34  5108.5 1070.74  5122.6 1072.57  5133.3 1072.39
  5136.8 1072.39
#Mann= 3 ,-1 , 0
  4895.4     .12       0  5006.5     .05       0  5012.5     .12       0
Bank Sta=5006.5,5012.5
XS Rating Curve= 0 ,0
Exp/Cntr=0.3,0.1

Type RM Length L Ch R = 1 ,19918   ,469,469,469
BEGIN DESCRIPTION:
Dry Bear Creek 43.0
END DESCRIPTION:
XS GIS Cut Line= 3
        2201075.       13846425.        2201475.       13846025.
        2201475.     13845924.98
#Sta/Elev= 30
    4434 1143.41  4437.5 1143.41  4462.3 1134.88  4490.6 1122.12  4504.7 1116.65
  4518.9 1109.67  4561.3  1093.1  4575.4 1089.25  4588.6 1087.04  4617.8 1083.89
  4688.6 1078.46  4759.3 1075.24  4844.1 1072.98  4858.3  1071.5  4893.6 1064.64
  4914.8 1058.26  4943.1 1052.49  4957.3 1050.59  4971.4 1047.03  4993.1 1046.09
  4993.6 1045.59  4999.1 1046.09  5002.2 1046.09  5006.3 1047.48  5009.7 1048.64
  5029.7  1081.6  5039.7 1086.36  5059.7 1089.57  5069.7 1090.79  5099.7 1092.02
#Mann= 5 ,-1 , 0
    4434     .12       0  4588.6     .07       0  4993.1     .05       0
  4999.1     .07       0  5006.3     .12       0
Bank Sta=4993.1,4999.1
XS Rating Curve= 0 ,0
Exp/Cntr=0.3,0.1

Type RM Length L Ch R = 1 ,19449   ,451,451,451
BEGIN DESCRIPTION:
Dry Bear Creek 42.0
END DESCRIPTION:
XS GIS Cut Line= 3
        2201725.       13846775.        2201775.       13846375.
      2201824.99     13846275.01
#Sta/Elev= 30
  4592.7 1178.96  4595.2 1178.96  4602.8 1173.71  4622.9 1163.95  4630.5 1159.04
  4635.5 1158.75  4643.1 1153.08  4711.1 1117.34  4716.2 1116.52  4723.7 1111.43
  4774.1 1089.69  4791.7 1085.37  4804.3 1080.81  4825.3 1075.77  4854.7 1071.38
  4877.4 1071.18    4885 1069.71  4942.2 1067.71    4958    1065  4975.7 1054.44
  4985.7 1046.51  4990.2 1039.22  4990.7 1038.72  4996.3 1039.22  5026.6 1044.71
  5032.1 1047.01  5048.9 1050.74  5071.3 1061.77  5085.3 1064.87  5107.6 1066.61
#Mann= 5 ,-1 , 0
  4592.7     .12       0  4825.3     .07       0  4942.2     .12       0
  4990.2     .05       0  4996.3     .12       0
Bank Sta=4990.2,4996.3
XS Rating Curve= 0 ,0
Exp/Cntr=0.3,0.1

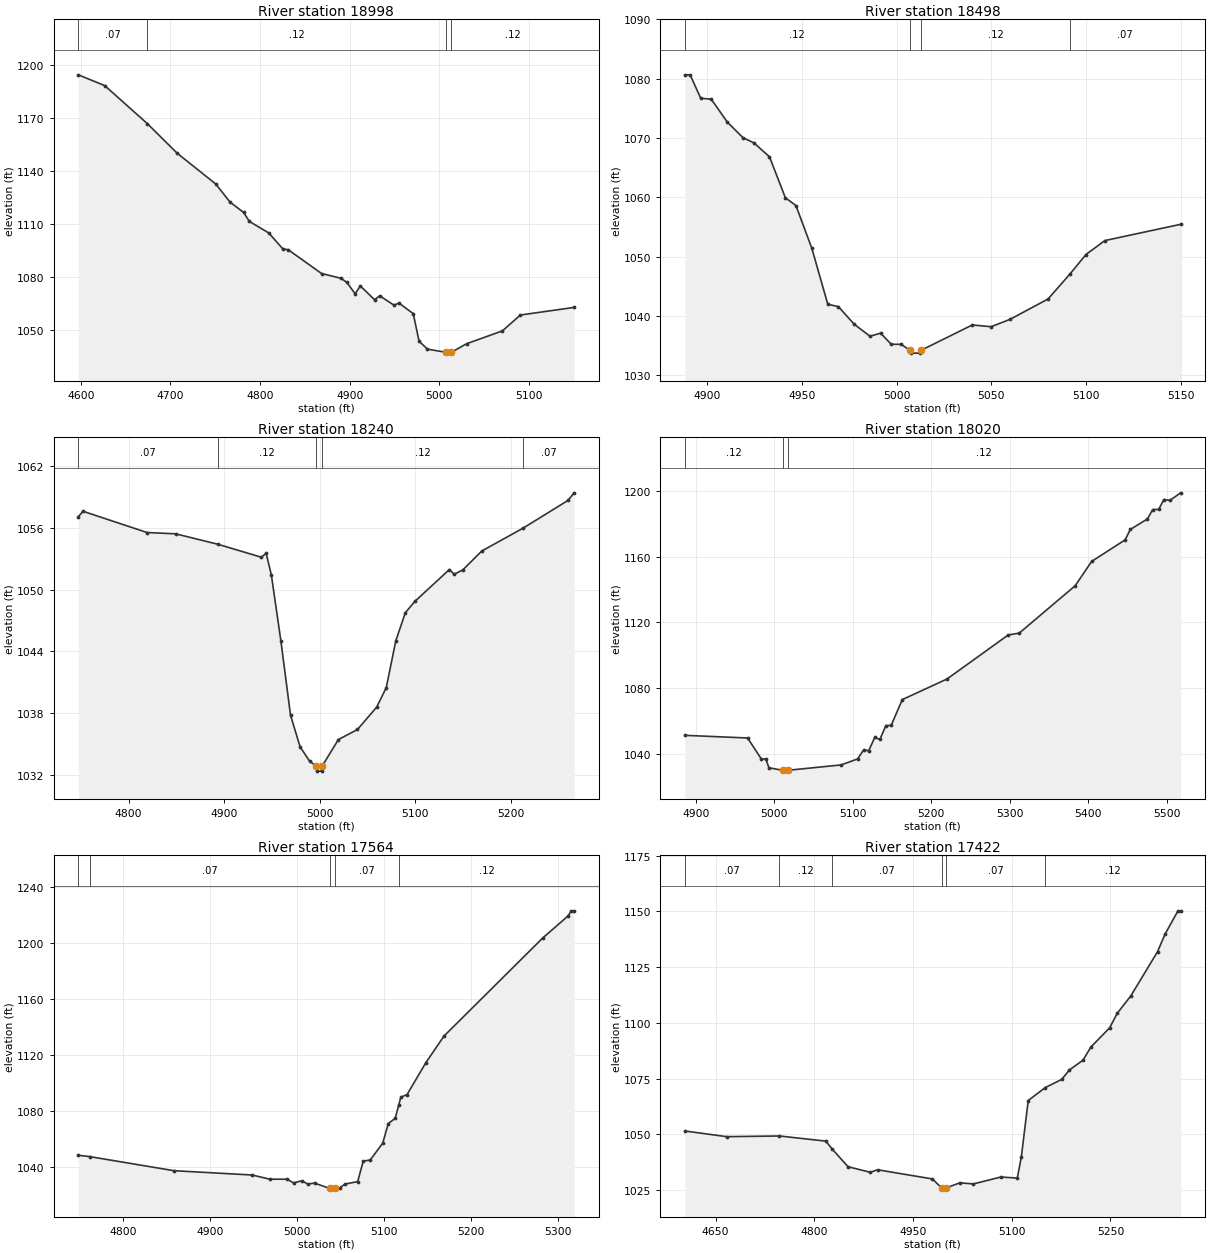
Type RM Length L Ch R = 1 ,18998   ,500,500,500
BEGIN DESCRIPTION:
Dry Bear Creek 41.0
END DESCRIPTION:
XS GIS Cut Line= 3
      2201974.98     13846875.03        2202175.       13846525.
        2202175.     13846375.04
#Sta/Elev= 30
  4597.3 1194.23  4626.8 1188.11  4674.3 1166.63  4707.5 1149.93  4750.7 1132.46
  4766.5 1122.27  4781.6 1116.48  4788.1 1111.34  4809.7 1104.84  4825.5 1095.77
  4831.3 1095.39  4868.7 1081.88  4890.3 1079.21  4896.8 1076.87  4906.1 1070.44
  4911.9 1074.86  4927.7 1067.09  4933.5 1069.32  4949.3 1064.03  4955.1 1065.15
  4970.9  1059.2  4977.4 1043.61  4986.8 1039.12  5007.3 1037.39  5007.8 1036.89
  5013.5 1037.39  5030.4  1042.2  5070.4 1049.48  5090.4 1058.43  5150.4 1062.75
#Mann= 4 ,-1 , 0
  4597.3     .07       0  4674.3     .12       0  5007.3     .05       0
  5013.5     .12       0
Bank Sta=5007.3,5013.5
XS Rating Curve= 0 ,0
Exp/Cntr=0.3,0.1

Type RM Length L Ch R = 1 ,18498   ,258,258,258
BEGIN DESCRIPTION:
Dry Bear Creek 40.0
END DESCRIPTION:
XS GIS Cut Line= 3
      2202624.99     13846625.02        2202675.       13846525.
        2202675.     13846375.02
#Sta/Elev= 30
  4888.2 1080.66    4891 1080.66  4896.6 1076.72  4902.2 1076.54  4910.6  1072.7
    4919 1070.03  4924.6  1069.2  4932.9 1066.84  4941.3 1059.92  4946.9  1058.6
  4955.3 1051.37  4963.7 1041.96  4969.3 1041.55  4977.7 1038.57    4986 1036.56
  4991.6 1037.08  4997.2  1035.2  5002.5  1035.2  5006.9 1034.21  5007.4 1033.71
  5012.6 1033.71  5013.1 1034.21    5040 1038.46    5050 1038.17    5060 1039.42
    5080 1042.84  5091.5 1047.03    5100 1050.34    5110  1052.7    5150 1055.44
#Mann= 4 ,-1 , 0
  4888.2     .12       0  5006.9     .05       0  5013.1     .12       0
  5091.5     .07       0
Bank Sta=5006.9,5013.1
XS Rating Curve= 0 ,0
Exp/Cntr=0.3,0.1

Type RM Length L Ch R = 1 ,18240   ,220,220,220
BEGIN DESCRIPTION:
X18885
END DESCRIPTION:
XS GIS Cut Line= 2
      2202930.15     13846726.84      2202903.29     13846208.53
#Sta/Elev= 30
  4747.4 1057.07  4752.3  1057.6  4819.3 1055.54  4849.4 1055.41  4893.5  1054.4
    4939 1053.14    4944 1053.53  4949.5 1051.39  4959.5 1044.97  4969.5 1037.82
  4979.5 1034.75  4989.6 1033.34  4996.4 1032.89  4996.9 1032.39  5002.2 1032.39
  5002.7 1032.89  5019.6 1035.45  5039.6 1036.43  5059.7  1038.6  5069.7 1040.48
  5079.7 1045.03  5089.7 1047.76  5099.7 1048.86  5135.8 1051.95  5140.8 1051.49
  5149.8 1051.91  5169.8 1053.75  5212.7 1055.95  5259.9 1058.65  5266.4 1059.39
#Mann= 5 ,-1 , 0
  4747.4     .07       0  4893.5     .12       0  4996.4     .05       0
  5002.7     .12       0  5212.7     .07       0
Bank Sta=4996.4,5002.7
XS Rating Curve= 0 ,0
Exp/Cntr=0.3,0.1

Type RM Length L Ch R = 1 ,18020   ,456,456,456
BEGIN DESCRIPTION:
Dry Bear Creek 39.0
END DESCRIPTION:
XS GIS Cut Line= 3
        2203125.     13846575.01        2203125.       13846475.
      2203474.99     13846075.01
#Sta/Elev= 30
    4886 1051.57    4966 1049.95  4983.5 1037.21  4989.3 1037.21  4993.1 1031.89
  5010.8 1030.36  5011.3 1029.86  5017.2 1030.36  5085.2 1033.63  5106.1 1037.26
  5113.7  1042.7  5120.3 1042.27  5127.9 1050.27  5134.5 1049.08  5142.1 1057.49
  5148.8 1057.55    5163 1073.23    5220 1085.73  5297.8 1112.39    5312 1113.56
  5383.2 1142.26  5404.1 1156.98  5446.8 1170.09  5453.4 1176.38  5475.3 1182.81
  5481.9 1188.43  5489.5 1188.53  5496.2 1194.56  5503.8    1194  5517.5 1198.61
#Mann= 3 ,-1 , 0
    4886     .12       0  5010.8     .05       0  5017.2     .12       0
Bank Sta=5010.8,5017.2
XS Rating Curve= 0 ,0
Exp/Cntr=0.3,0.1

Type RM Length L Ch R = 1 ,17564   ,142,142,142
BEGIN DESCRIPTION:
Dry Bear Creek 38.0
END DESCRIPTION:
XS GIS Cut Line= 3
      2203225.03       13846625.        2203475.       13846625.
      2203674.98     13846375.02
#Sta/Elev= 30
  4748.7 1048.33  4761.8 1047.35  4858.7 1037.27  4948.7 1034.18  4968.7 1031.21
  4988.7 1031.18  4996.2 1028.54  5005.9 1030.08  5012.3 1027.76  5020.3 1028.36
  5037.9 1024.59  5038.4 1024.09  5044.3 1024.59  5049.1 1024.94  5055.5 1027.73
  5069.9 1029.46  5076.3 1044.18  5084.3 1044.88  5098.7 1056.99  5105.1 1071.01
  5113.1 1074.79    5117 1083.99  5119.5 1089.88  5126.7 1091.76  5148.3 1114.58
  5169.2 1133.64  5282.8 1203.82  5311.6 1219.41  5315.6 1223.18  5318.8 1223.18
#Mann= 5 ,-1 , 0
  4748.7     .12       0  4761.8     .07       0  5037.9     .05       0
  5044.3     .07       0    5117     .12       0
Bank Sta=5037.9,5044.3
XS Rating Curve= 0 ,0
Exp/Cntr=0.3,0.1

Type RM Length L Ch R = 1 ,17422   ,302,302,302
BEGIN DESCRIPTION:
X18884
END DESCRIPTION:
XS GIS Cut Line= 2
      2203043.27     13846858.81      2203767.67     13846651.45
#Sta/Elev= 30
  4603.1 1051.51  4666.8 1048.95  4746.9 1049.26  4817.5 1046.95  4826.8 1043.48
  4851.2 1035.46    4885 1032.97  4896.1  1034.1  4979.4 1029.98  4993.5 1025.91
    4994 1025.41  4999.9 1025.91    5021 1028.23  5041.8 1027.75  5083.4 1030.84
  5108.4 1030.37  5114.6 1039.99    5125 1065.18  5151.1 1071.01    5176 1074.66
  5187.4 1078.85  5208.2 1083.26  5220.2 1089.17  5248.7 1097.78  5260.2 1104.29
    5281 1112.16  5321.5 1131.96    5333  1139.9  5352.6  1150.3  5356.6  1150.3
#Mann= 6 ,-1 , 0
  4603.1     .07       0  4746.9     .12       0  4826.8     .07       0
  4993.5     .05       0  4999.9     .07       0  5151.1     .12       0
Bank Sta=4993.5,4999.9
XS Rating Curve= 0 ,0
Exp/Cntr=0.3,0.1

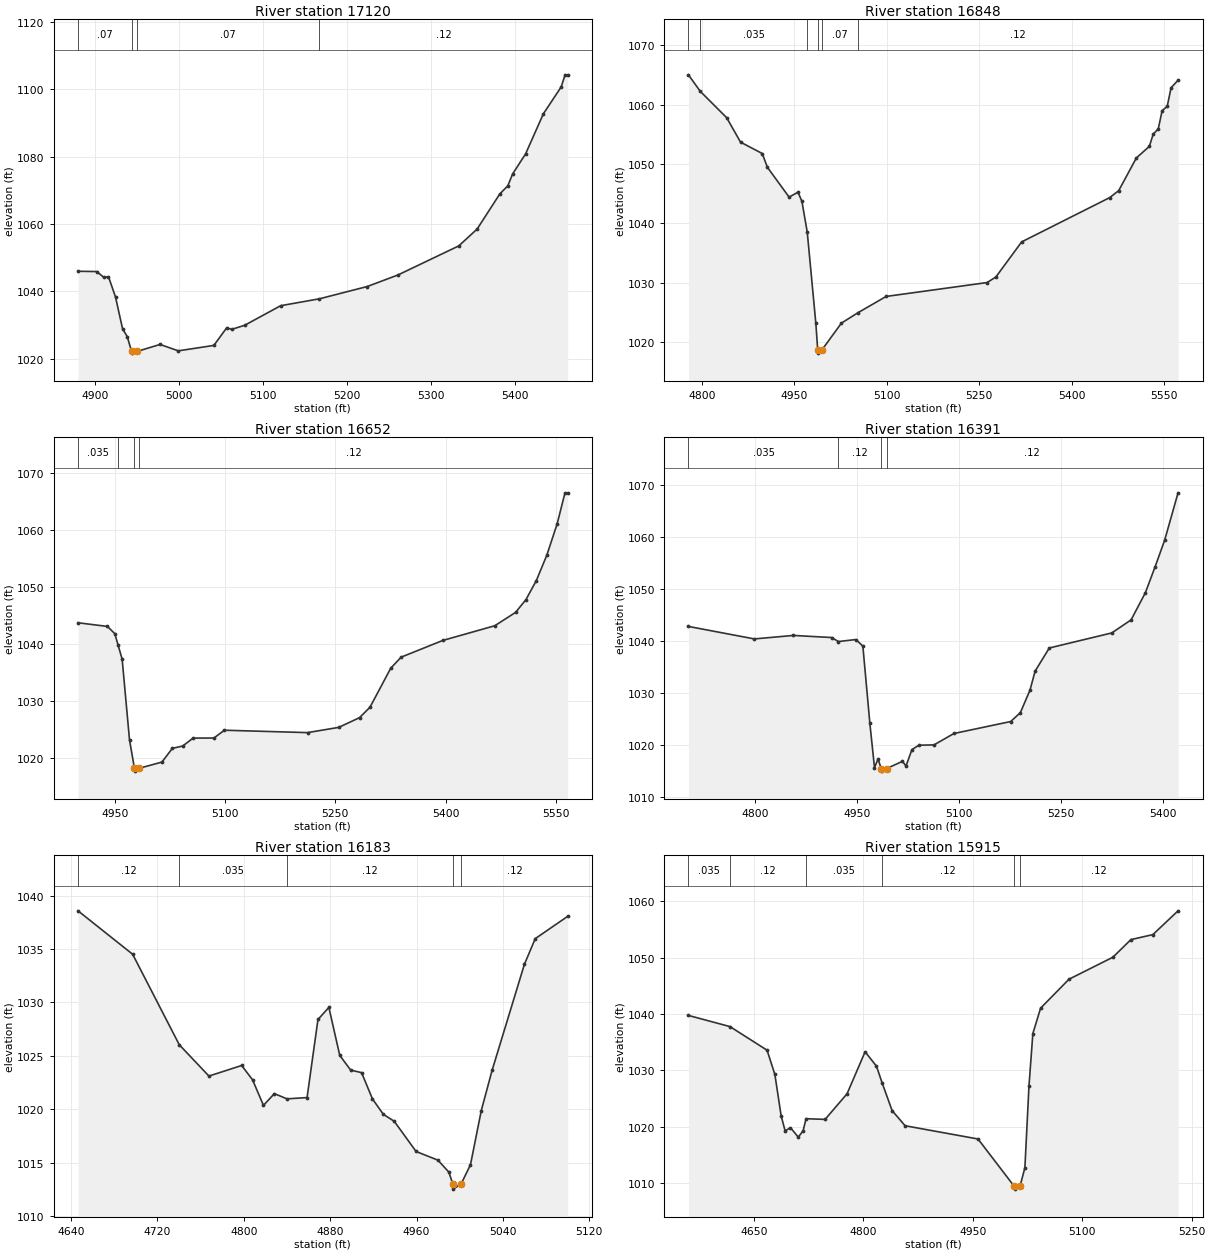
Type RM Length L Ch R = 1 ,17120   ,272,272,272
BEGIN DESCRIPTION:
Dry Bear Creek 37.0
END DESCRIPTION:
XS GIS Cut Line= 3
        2203225.       13847075.        2203325.       13847025.
        2203725.       13846775.
#Sta/Elev= 30
  4879.8 1045.98  4902.2 1045.89  4910.5 1044.17  4916.1 1044.37  4924.5 1038.32
  4932.9 1028.87  4938.5 1026.56  4943.6 1022.16  4944.1 1021.66  4950.1 1022.16
  4977.6 1024.24  4999.3 1022.34  5041.7 1023.95    5057 1029.19  5062.9 1028.72
  5078.3 1029.92  5121.3 1035.75  5167.5  1037.8  5224.5 1041.45  5261.1 1044.88
  5333.6 1053.52  5355.4 1058.51  5382.5 1068.96    5392 1071.36  5397.8 1074.92
  5413.2 1080.85  5434.4 1092.76  5455.6 1100.74  5460.3 1104.34  5463.3 1104.34
#Mann= 4 ,-1 , 0
  4879.8     .07       0  4943.6     .05       0  4950.1     .07       0
  5167.5     .12       0
Bank Sta=4943.6,4950.1
XS Rating Curve= 0 ,0
Exp/Cntr=0.3,0.1

Type RM Length L Ch R = 1 ,16848   ,196,196,196
BEGIN DESCRIPTION:
X18882
END DESCRIPTION:
XS GIS Cut Line= 2
      2203150.98     13847400.11      2203778.41      13846912.7
#Sta/Elev= 30
    4778    1065  4797.1 1062.23  4840.1 1057.77  4862.5 1053.66  4897.8 1051.74
    4906 1049.44  4941.3  1044.4  4955.8 1045.22  4962.1 1043.69  4970.8 1038.49
  4984.7 1023.17  4987.8 1018.61  4988.3 1018.11  4994.3 1018.61  5026.3 1023.17
  5052.6 1024.89  5098.8 1027.66  5262.6    1030  5276.9 1030.94  5318.7 1036.85
  5461.7 1044.32  5476.2 1045.49  5504.9    1051  5525.9 1052.94  5532.3 1055.02
  5540.4 1055.89  5546.7 1058.98  5554.9 1059.68  5561.2 1062.82  5572.5 1064.09
#Mann= 6 ,-1 , 0
    4778     .12       0  4797.1    .035       0  4970.8     .07       0
  4987.8     .05       0  4994.3     .07       0  5052.6     .12       0
Bank Sta=4987.8,4994.3
XS Rating Curve= 0 ,0
Exp/Cntr=0.3,0.1

Type RM Length L Ch R = 1 ,16652   ,261,261,261
BEGIN DESCRIPTION:
Dry Bear Creek 36.0
END DESCRIPTION:
XS GIS Cut Line= 3
        2203475.     13847474.97        2203475.       13847375.
      2203875.03     13846974.97
#Sta/Elev= 30
  4900.1 1043.73  4940.1 1043.09  4950.1 1041.82  4954.4 1039.89  4960.1 1037.34
  4970.1 1023.18  4976.8 1018.19  4977.3 1017.69  4983.3 1018.19  5014.2 1019.28
  5028.4 1021.69  5042.5  1022.1  5056.6 1023.49  5084.9  1023.5  5099.1 1024.87
  5212.2 1024.45  5254.6 1025.37  5282.9 1027.08  5297.1 1028.91  5325.3 1035.76
  5339.5  1037.7  5396.1 1040.63  5466.8 1043.21    5495 1045.55  5509.2 1047.81
  5523.3 1051.15  5537.5 1055.59  5551.6 1061.11  5562.2 1066.54  5565.8 1066.54
#Mann= 4 ,-1 , 0
  4900.1    .035       0  4954.4     .12       0  4976.8     .05       0
  4983.3     .12       0
Bank Sta=4976.8,4983.3
XS Rating Curve= 0 ,0
Exp/Cntr=0.3,0.1

Type RM Length L Ch R = 1 ,16391   ,208,208,208
BEGIN DESCRIPTION:
X18883
END DESCRIPTION:
XS GIS Cut Line= 4
      2203536.05     13847602.12       2203681.5     13847410.88
       2203719.2     13847260.07      2203936.34     13847018.82
#Sta/Elev= 30
  4702.5 1042.79  4799.4 1040.39  4856.8 1041.06    4913 1040.66  4923.2 1039.89
  4948.8 1040.27  4959.1 1039.02  4969.4 1024.17  4976.2 1015.68  4981.4  1017.3
  4986.2 1015.49  4986.7 1014.99    4994 1015.49  5017.4 1016.87  5022.6 1015.97
  5031.3 1019.13  5041.6 1019.97  5063.8 1020.03  5093.1 1022.22  5176.6 1024.52
  5190.8 1026.22    5205 1030.56  5212.5  1034.2  5233.4 1038.65  5325.3 1041.54
  5353.7 1044.05  5374.7 1049.26  5388.9  1054.2  5403.1 1059.36  5422.8 1068.46
#Mann= 4 ,-1 , 0
  4702.5    .035       0  4923.2     .12       0  4986.2     .05       0
    4994     .12       0
Bank Sta=4986.2,4994
XS Rating Curve= 0 ,0
Exp/Cntr=0.3,0.1

Type RM Length L Ch R = 1 ,16183   ,268,268,268
BEGIN DESCRIPTION:
Dry Bear Creek 35.0
END DESCRIPTION:
XS GIS Cut Line= 3
      2203925.01     13847625.04        2203875.       13847275.
        2203875.       13847175.
#Sta/Elev= 30
  4646.4 1038.57    4697 1034.51  4740.2 1026.05  4767.7 1023.12    4798 1024.11
  4808.1 1022.77  4818.2 1020.38  4828.3 1021.48    4840 1020.99  4858.6 1021.11
  4868.7 1028.41  4878.8 1029.54  4888.9 1025.05    4899 1023.68  4909.1 1023.44
  4919.2 1020.98  4929.3 1019.54  4939.4 1018.89  4959.6 1016.07  4979.8 1015.26
  4989.9 1014.15  4993.6 1013.05  4994.1 1012.55  5001.4 1013.05    5010 1014.83
    5020 1019.89    5030 1023.65    5060 1033.58    5070 1035.97    5100 1038.05
#Mann= 5 ,-1 , 0
  4646.4     .12       0  4740.2    .035       0    4840     .12       0
  4993.6     .05       0  5001.4     .12       0
Bank Sta=4993.6,5001.4
XS Rating Curve= 0 ,0
Exp/Cntr=0.3,0.1

Type RM Length L Ch R = 1 ,15915   ,215,215,215
BEGIN DESCRIPTION:
X18881
END DESCRIPTION:
XS GIS Cut Line= 2
      2203953.49      13847685.6      2204192.81     13847059.05
#Sta/Elev= 30
  4560.6 1039.73  4617.5 1037.75  4668.3 1033.56    4679 1029.25  4687.6  1021.9
    4693 1019.25  4700.4  1019.8  4711.1 1018.13  4717.7 1019.27  4721.7  1021.4
  4747.8 1021.28  4777.9 1025.83  4802.6 1033.28  4818.2 1030.72  4825.8  1027.8
  4839.6 1022.84  4857.4 1020.15  4957.3  1017.8  5006.9  1009.4  5007.4  1008.9
  5014.8  1009.4  5021.5  1012.7  5027.1 1027.22  5032.4 1036.52    5043 1041.02
  5081.9 1046.16    5142 1050.06  5166.7 1053.19  5196.8 1054.08  5231.3  1058.3
#Mann= 6 ,-1 , 0
  4560.6    .035       0  4617.5     .12       0  4721.7    .035       0
  4825.8     .12       0  5006.9     .05       0  5014.8     .12       0
Bank Sta=5006.9,5014.8
XS Rating Curve= 0 ,0
Exp/Cntr=0.3,0.1

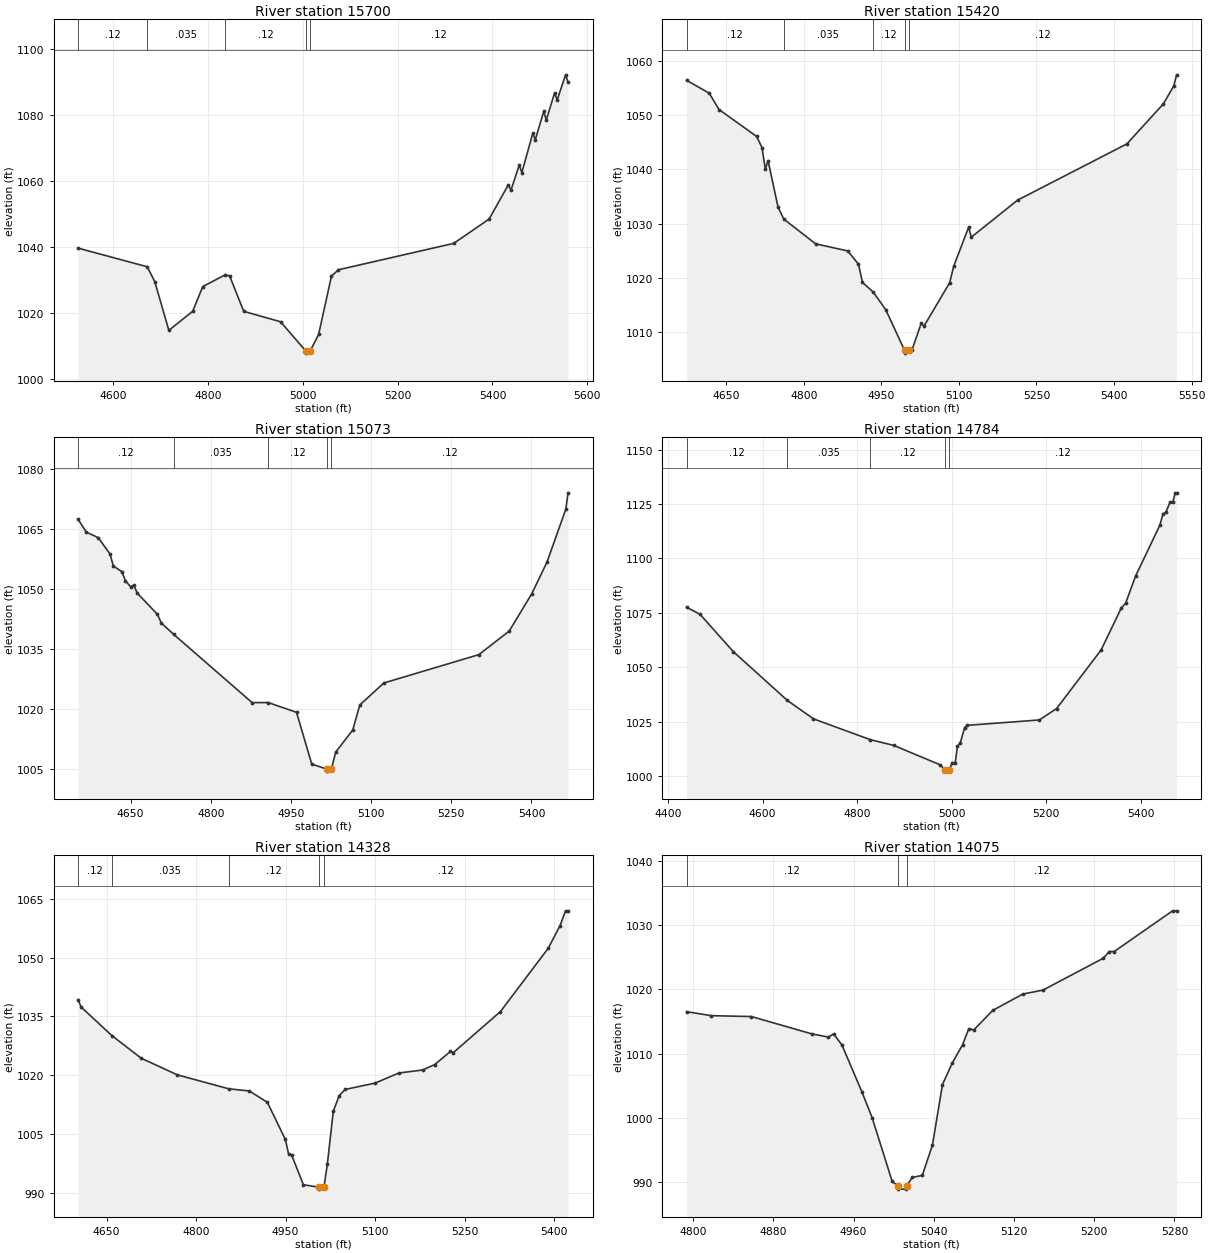
Type RM Length L Ch R = 1 ,15700   ,280,280,280
BEGIN DESCRIPTION:
X18880
END DESCRIPTION:
XS GIS Cut Line= 3
      2204018.13     13847763.67      2204397.85     13847216.99
      2204550.69     13846881.81
#Sta/Elev= 30
  4525.5 1039.68  4671.5 1034.03  4687.4 1029.54  4717.1 1014.77  4767.4 1020.53
  4788.7 1028.03  4835.7 1031.57  4845.4 1031.26  4875.1 1020.52  4952.8 1017.37
    5007 1008.36  5007.5 1007.86  5014.9 1008.36  5033.2 1013.54  5060.2 1031.17
    5075 1033.12  5318.3 1041.12  5392.9 1048.48  5433.5 1058.87    5439 1057.22
  5456.5 1064.84    5462 1062.59    5485 1074.43  5490.5 1072.57  5508.1 1081.08
  5513.6 1078.53  5531.1  1086.7  5536.6 1084.55  5554.2 1092.19  5559.5 1089.91
#Mann= 5 ,-1 , 0
  4525.5     .12       0  4671.5    .035       0  4835.7     .12       0
    5007     .05       0  5014.9     .12       0
Bank Sta=5007,5014.9
XS Rating Curve= 0 ,0
Exp/Cntr=0.3,0.1

Type RM Length L Ch R = 1 ,15420   ,347,347,347
BEGIN DESCRIPTION:
X18879
END DESCRIPTION:
XS GIS Cut Line= 3
       2204419.4     13847895.61      2204556.74     13847394.72
      2204607.85     13846969.66
#Sta/Elev= 30
  4573.4 1056.46  4617.1 1054.09  4636.2 1051.06  4708.8  1046.1  4719.2 1044.05
  4725.7 1040.05  4730.9 1041.65  4750.3 1033.05  4761.4 1030.84  4822.9 1026.28
  4885.1 1024.97  4905.8 1022.52  4913.5 1019.15  4933.9 1017.42  4958.4 1014.15
    4995 1006.61  4995.5 1006.11  5003.3 1006.61  5009.5 1006.75  5027.3 1011.68
  5032.5  1011.1  5082.1  1019.1    5090 1022.16  5118.9 1029.37  5123.9  1027.5
  5213.4 1034.34  5424.9 1044.73  5495.4 1052.12  5515.5 1055.43  5520.9 1057.47
#Mann= 5 ,-1 , 0
  4573.4     .12       0  4761.4    .035       0  4933.9     .12       0
    4995     .05       0  5003.3     .12       0
Bank Sta=4995,5003.3
XS Rating Curve= 0 ,0
Exp/Cntr=0.3,0.1

Type RM Length L Ch R = 1 ,15073   ,289,289,289
BEGIN DESCRIPTION:
X18878
END DESCRIPTION:
XS GIS Cut Line= 3
      2204642.89     13847973.77      2204914.91     13847445.89
      2205135.21     13847209.47
#Sta/Elev= 30
  4551.5 1067.47    4567 1064.23  4589.2 1062.87  4611.3 1058.77  4617.6 1055.74
  4633.5 1054.35  4640.1  1052.1    4650 1050.54  4655.7 1050.94  4662.6 1048.93
    4700 1043.65  4707.6 1041.44  4730.4 1038.65  4877.3 1021.55  4907.4 1021.57
  4960.4 1019.12  4988.8 1006.17    5017  1004.9  5017.5  1004.4  5025.5  1004.9
  5033.8 1009.19  5065.6 1014.69  5078.8 1020.97  5123.8 1026.47  5301.6 1033.57
  5358.3 1039.46  5400.8 1048.86  5429.1 1056.74  5464.3 1069.98  5468.5 1074.08
#Mann= 5 ,-1 , 0
  4551.5     .12       0  4730.4    .035       0  4907.4     .12       0
    5017     .05       0  5025.5     .12       0
Bank Sta=5017,5025.5
XS Rating Curve= 0 ,0
Exp/Cntr=0.3,0.1

Type RM Length L Ch R = 1 ,14784   ,456,456,456
BEGIN DESCRIPTION:
Dry Bear Creek 32.0
END DESCRIPTION:
XS GIS Cut Line= 3
      2204724.99     13848025.01        2205125.       13847625.
        2205375.       13847225.
#Sta/Elev= 30
  4438.9 1077.54  4467.2 1074.35  4537.9 1057.13  4652.4 1034.68  4707.6 1026.24
  4828.2 1016.64  4877.3 1014.05  4976.3 1005.04  4986.2  1002.7  4986.7  1002.2
  4994.7  1002.7  5001.1 1005.94  5007.6 1005.94  5012.3 1013.66  5018.2 1015.11
  5027.6 1022.25  5033.5 1023.27  5185.6 1025.72  5222.2 1030.95  5316.5 1057.91
    5359  1077.1  5368.4 1079.42  5389.6 1091.95  5440.9 1115.29  5447.4 1120.42
  5453.3 1121.15  5462.7 1125.92  5468.6 1126.02  5473.4 1130.16  5476.3 1130.16
#Mann= 5 ,-1 , 0
  4438.9     .12       0  4652.4    .035       0  4828.2     .12       0
  4986.2     .05       0  4994.7     .12       0
Bank Sta=4986.2,4994.7
XS Rating Curve= 0 ,0
Exp/Cntr=0.3,0.1

Type RM Length L Ch R = 1 ,14328   ,253,253,253
BEGIN DESCRIPTION:
Dry Bear Creek 31.0
END DESCRIPTION:
XS GIS Cut Line= 3
      2205480.44      13848170.3        2205525.       13847775.
       2205534.3     13847351.61
#Sta/Elev= 30
  4602.2 1039.28  4607.5 1037.37  4658.9 1030.11  4708.2 1024.32  4768.5  1020.1
  4854.8 1016.53  4889.3 1015.98  4919.5 1013.08  4949.7  1003.6    4955  999.97
  4960.1  999.66  4979.9  992.05  5005.7  991.43  5006.2  990.93  5014.3  991.43
    5020  997.22    5030 1010.77    5040  1014.8    5050 1016.37    5100 1017.99
    5140 1020.56    5180 1021.34  5200.1 1022.72  5226.3 1026.06  5231.3 1025.78
  5310.1 1036.23  5390.1 1052.36  5410.1 1058.17  5419.3 1061.95  5423.5 1061.95
#Mann= 5 ,-1 , 0
  4602.2     .12       0  4658.9    .035       0  4854.8     .12       0
  5005.7     .05       0  5014.3     .12       0
Bank Sta=5005.7,5014.3
XS Rating Curve= 0 ,0
Exp/Cntr=0.3,0.1

Type RM Length L Ch R = 1 ,14075   ,213,213,213
BEGIN DESCRIPTION:
X18877
END DESCRIPTION:
XS GIS Cut Line= 2
      2205749.74     13848019.53      2205784.75     13847532.09
#Sta/Elev= 30
  4793.4 1016.53    4818 1015.91  4858.1 1015.77  4918.3 1013.07  4934.9 1012.57
    4940 1013.07  4948.3 1011.35  4968.4 1003.98  4978.4 1000.03  4998.5  990.06
  5004.2  989.37  5004.7  988.87  5012.3  988.87  5012.8  989.37  5018.5  990.69
  5028.5  991.02  5038.6  995.72  5048.6 1005.17  5058.6  1008.6  5068.6 1011.35
  5074.9 1013.89  5079.9 1013.69  5098.7 1016.73  5128.8 1019.28  5148.8 1019.89
    5209 1024.86  5214.9  1025.9  5219.9 1025.91  5278.1 1032.25  5282.1 1032.25
#Mann= 3 ,-1 , 0
  4793.4     .12       0  5004.2     .05       0  5012.8     .12       0
Bank Sta=5004.2,5012.8
XS Rating Curve= 0 ,0
Exp/Cntr=0.3,0.1