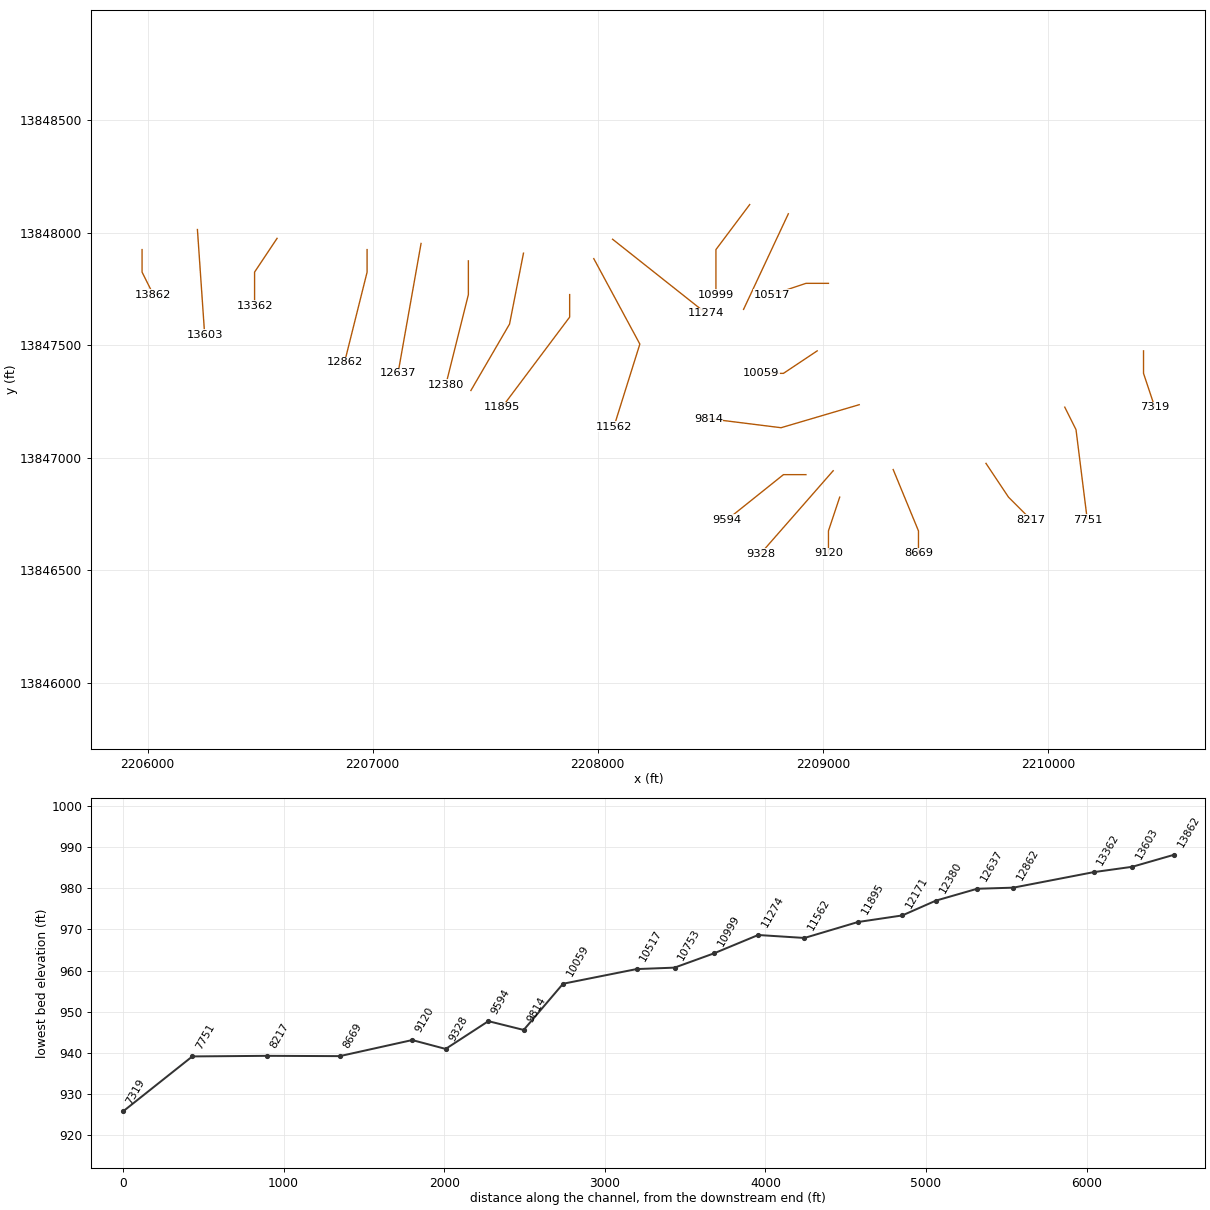
HEC-RAS study Dry Bear Creek.prj: Dry Bear Creek Base Level Engineering

--- Dry Bear Creek.g01 (geometry) --- (continued)

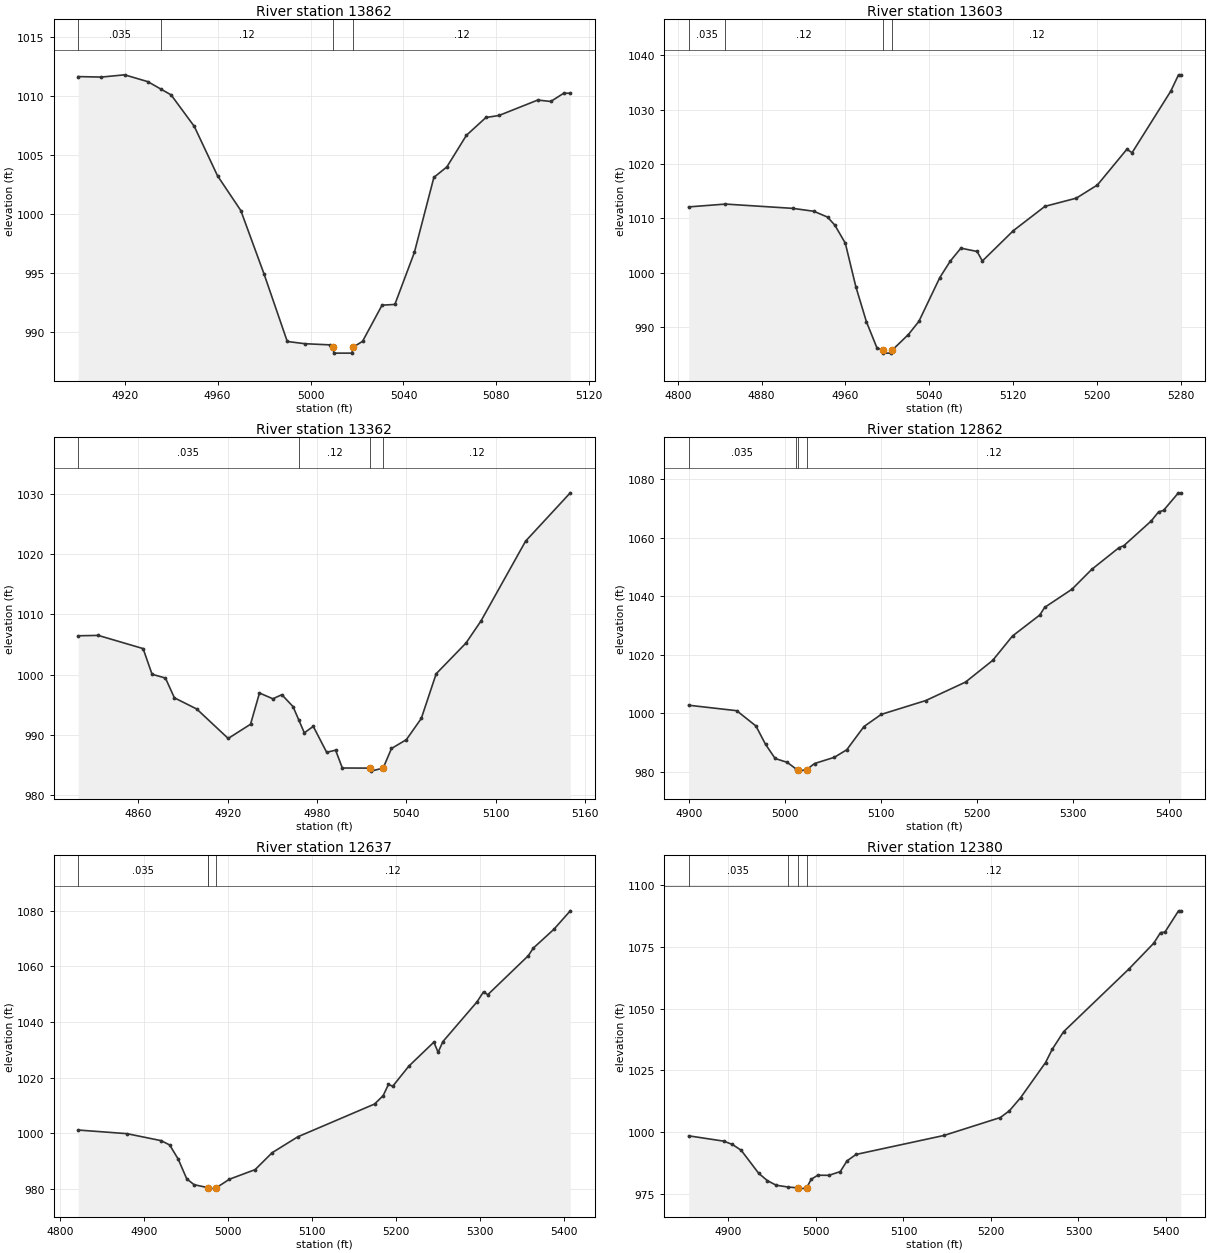
Type RM Length L Ch R = 1 ,13862   ,259,259,259
BEGIN DESCRIPTION:
Dry Bear Creek 30.0
END DESCRIPTION:
XS GIS Cut Line= 3
        2205975.     13847925.01        2205975.       13847825.
        2206025.     13847725.01
#Sta/Elev= 30
    4900 1011.63    4910 1011.59    4920 1011.78    4930  1011.2  4935.6 1010.57
    4940 1010.08    4950  1007.4    4960 1003.21    4970 1000.27    4980  994.89
    4990  989.16  4997.5  988.97  5008.4  988.87  5009.6  988.67  5010.1  988.17
  5017.8  988.17  5018.3  988.67  5022.4  989.17  5030.8  992.24  5036.3   992.3
  5044.7  996.71  5053.1 1003.08  5058.7 1003.97  5067.1 1006.65  5075.5 1008.16
  5081.1 1008.33  5097.8 1009.64  5103.4 1009.52    5109 1010.22  5111.8 1010.22
#Mann= 4 ,-1 , 0
    4900    .035       0  4935.6     .12       0  5009.6     .05       0
  5018.3     .12       0
Bank Sta=5009.6,5018.3
XS Rating Curve= 0 ,0
Exp/Cntr=0.3,0.1

Type RM Length L Ch R = 1 ,13603   ,241,241,241
BEGIN DESCRIPTION:
X18876
END DESCRIPTION:
XS GIS Cut Line= 2
      2206221.02     13848014.16      2206253.34     13847545.57
#Sta/Elev= 30
  4810.4 1012.13  4845.5 1012.65  4909.8 1011.86  4929.8 1011.33  4942.9 1010.26
  4949.9 1008.78  4959.9 1005.46  4969.9   997.5    4980  991.05    4990  986.26
  4995.7  985.76  4996.2  985.26  5003.9  985.26  5004.4  985.76  5020.1  988.68
  5030.1  991.09  5050.1  999.15  5060.1 1002.18  5070.2 1004.55  5085.7 1003.94
  5090.7 1002.19  5120.3 1007.77  5150.4 1012.23  5180.4 1013.74  5200.5 1016.16
  5228.6 1022.72  5233.6 1022.09  5270.6 1033.43  5277.9  1036.4  5280.1  1036.4
#Mann= 4 ,-1 , 0
  4810.4    .035       0  4845.5     .12       0  4995.7     .05       0
  5004.4     .12       0
Bank Sta=4995.7,5004.4
XS Rating Curve= 0 ,0
Exp/Cntr=0.3,0.1

Type RM Length L Ch R = 1 ,13362   ,500,500,500
BEGIN DESCRIPTION:
Dry Bear Creek 29.0
END DESCRIPTION:
XS GIS Cut Line= 3
      2206575.01     13847975.02        2206475.       13847825.
        2206475.       13847675.
#Sta/Elev= 30
  4819.7 1006.44  4833.2  1006.5  4863.3 1004.31  4869.3 1000.05  4878.3  999.41
  4884.3  996.13  4899.3  994.27  4920.4  989.38  4935.4  991.74  4941.4  996.93
  4950.4  995.97  4956.4  996.65  4963.9  994.68  4967.7   992.5  4971.5  990.31
  4977.5  991.39  4986.5  987.08  4992.5  987.43    4997  984.47  5015.7  984.45
  5016.2  983.95  5024.4  984.45    5030  987.71    5040  989.18    5050   992.7
    5060 1000.13    5080 1005.23    5090 1008.87    5120 1022.16    5150 1030.19
#Mann= 4 ,-1 , 0
  4819.7    .035       0  4967.7     .12       0  5015.7     .05       0
  5024.4     .12       0
Bank Sta=5015.7,5024.4
XS Rating Curve= 0 ,0
Exp/Cntr=0.3,0.1

Type RM Length L Ch R = 1 ,12862   ,225,225,225
BEGIN DESCRIPTION:
Dry Bear Creek 28.0
END DESCRIPTION:
XS GIS Cut Line= 3
        2206975.     13847925.04        2206975.       13847825.
      2206875.01     13847425.05
#Sta/Elev= 30
    4900  1002.7    4950 1000.83    4970  995.61    4980  989.34    4990   984.5
  5002.6  983.17  5011.5  980.99  5013.4  980.68  5013.9  980.18  5022.7  980.68
    5031  982.78  5051.6   984.9  5064.5  987.46  5082.5  995.43  5100.5  999.57
  5146.9 1004.31  5188.2 1010.61  5216.5 1018.03  5237.1 1026.36  5265.5 1033.53
  5270.6 1036.14    5299 1042.34  5319.6 1049.13  5347.9 1056.53  5353.1 1057.25
  5381.4 1065.63  5389.2 1068.77  5394.3 1069.26  5409.8 1075.28  5412.3 1075.28
#Mann= 4 ,-1 , 0
    4900    .035       0  5011.5     .12       0  5013.4    .035       0
  5022.7     .12       0
Bank Sta=5013.4,5022.7
XS Rating Curve= 0 ,0
Exp/Cntr=0.3,0.1

Type RM Length L Ch R = 1 ,12637   ,257,257,257
BEGIN DESCRIPTION:
X18875
END DESCRIPTION:
XS GIS Cut Line= 2
      2207214.75     13847952.21      2207112.41     13847375.83
#Sta/Elev= 30
  4821.7 1001.16  4879.8  999.85  4920.4  997.34  4930.6  995.78  4940.7  990.71
  4950.9   983.6  4959.6  981.51  4976.5  980.41  4976.7  980.41  4977.2  979.91
  4986.1  980.41  5001.7  983.48  5032.2  986.92  5052.5  993.01  5082.9  998.71
  5174.3 1010.51  5184.5 1013.52  5190.8 1017.53  5195.9  1016.9    5215 1024.11
  5244.8 1032.75  5249.9 1029.13  5255.6 1032.96  5296.2 1047.25  5303.9 1050.84
    5309 1049.83  5357.2 1063.84    5363 1066.53  5387.6 1073.33  5407.1 1079.97
#Mann= 4 ,-1 , 0
  4821.7    .035       0  4976.5     .12       0  4976.7     .05       0
  4986.1     .12       0
Bank Sta=4976.7,4986.1
XS Rating Curve= 0 ,0
Exp/Cntr=0.3,0.1

Type RM Length L Ch R = 1 ,12380   ,209,209,209
BEGIN DESCRIPTION:
Dry Bear Creek 27.0
END DESCRIPTION:
XS GIS Cut Line= 3
        2207425.     13847874.97        2207425.       13847725.
        2207325.     13847324.98
#Sta/Elev= 30
  4854.6  998.57  4894.6  996.42  4904.6  995.07  4914.6  992.73  4934.6  983.41
  4944.6  980.43  4954.6   978.6  4968.2  977.87  4979.9  977.52  4980.4  977.02
  4989.3  977.52  4994.6     981  5002.1  982.65  5014.9   982.6  5027.8  984.12
  5035.5  988.44  5045.8  991.04  5146.3  998.72  5210.7 1005.97    5221 1008.68
  5233.9 1014.01  5262.3 1028.17    5270 1033.56  5282.9 1040.64  5357.6 1066.02
    5386 1076.45  5393.7 1080.72  5398.8 1080.96  5414.3 1089.53  5416.9 1089.53
#Mann= 4 ,-1 , 0
  4854.6    .035       0  4968.2     .12       0  4979.9     .05       0
  4989.3     .12       0
Bank Sta=4979.9,4989.3
XS Rating Curve= 0 ,0
Exp/Cntr=0.3,0.1

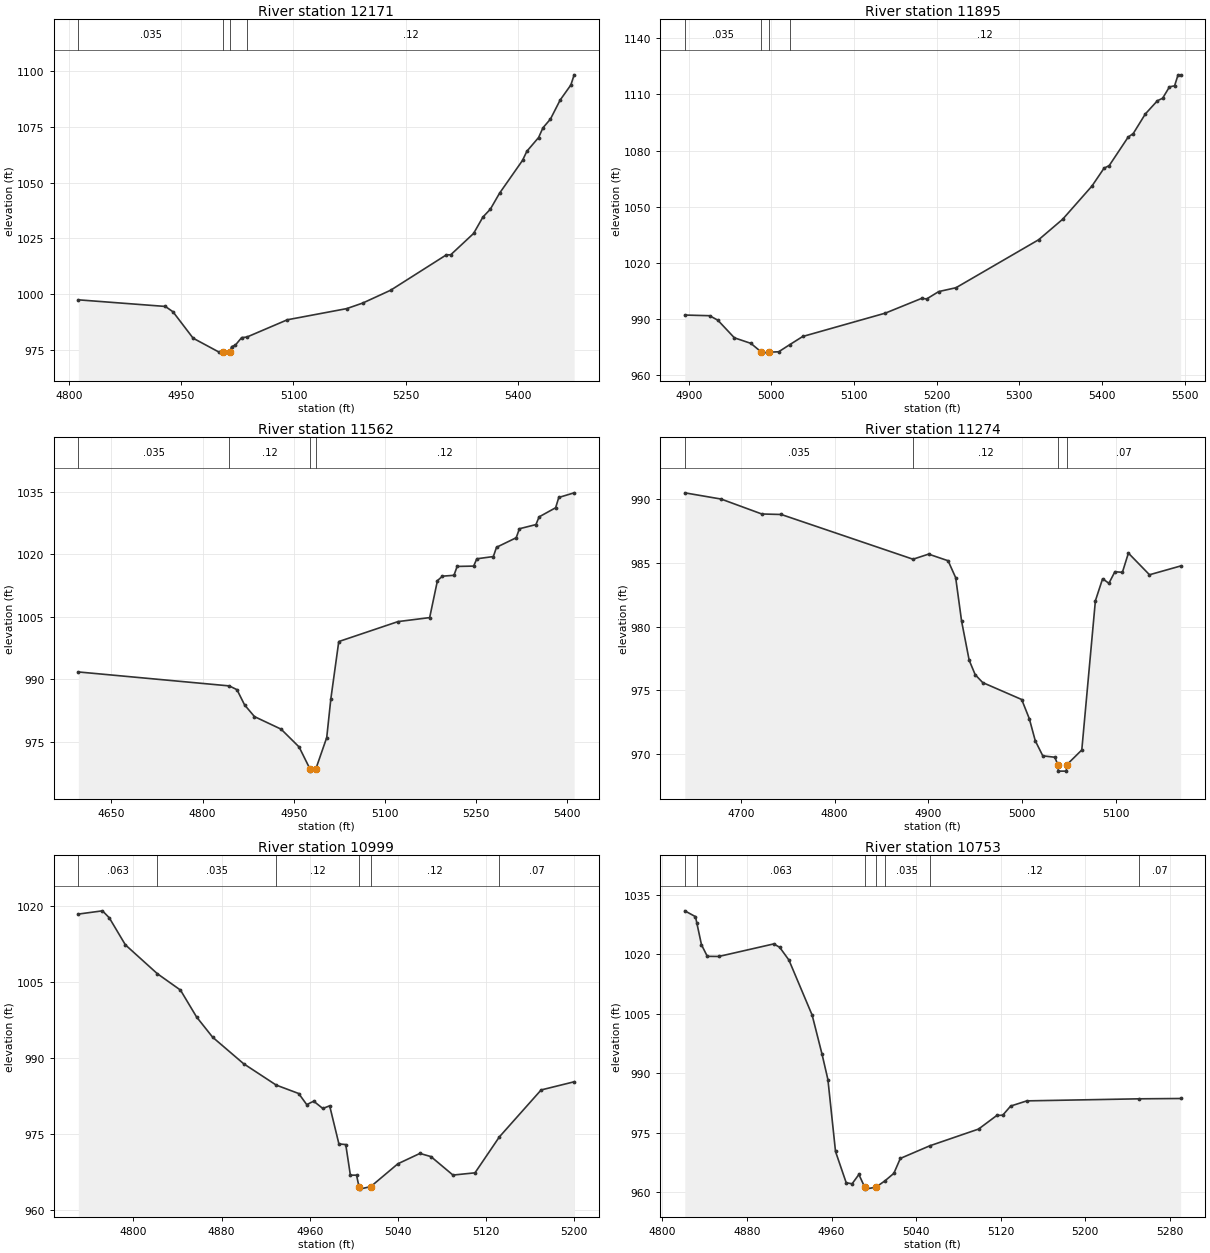
Type RM Length L Ch R = 1 ,12171   ,276,276,276
BEGIN DESCRIPTION:
X18874
END DESCRIPTION:
XS GIS Cut Line= 3
      2207669.87      13847909.1      2207607.93     13847594.01
      2207436.21     13847298.86
#Sta/Elev= 30
  4812.5  997.35  4928.8  994.38    4939  991.98  4965.9  980.13  5000.1  973.95
  5005.6  973.92  5006.1  973.42  5015.1  973.92  5017.3  976.32  5022.4  977.02
  5030.7  980.38  5037.7  980.63  5091.8  988.39  5171.1   993.4  5192.6  995.91
  5229.9 1001.67  5304.4 1017.56  5310.1 1017.56  5340.7 1027.15  5353.2 1034.53
  5363.1 1038.05  5375.4 1045.22  5406.1 1059.96  5411.9 1064.06  5427.6 1070.23
  5433.4 1074.59  5443.4  1078.5  5456.4 1087.06  5470.7 1093.82  5475.1 1098.37
#Mann= 4 ,-1 , 0
  4812.5    .035       0  5005.6    .035       0  5015.1    .035       0
  5037.7     .12       0
Bank Sta=5005.6,5015.1
XS Rating Curve= 0 ,0
Exp/Cntr=0.3,0.1

Type RM Length L Ch R = 1 ,11895   ,333,333,333
BEGIN DESCRIPTION:
Dry Bear Creek 26.0
END DESCRIPTION:
XS GIS Cut Line= 3
        2207875.     13847725.04        2207875.       13847625.
      2207575.02     13847225.03
#Sta/Elev= 30
  4895.2  992.16  4925.2  991.81  4935.2   989.4  4955.2     980  4975.2  977.03
    4988  972.32  4988.5  971.82  4997.5  972.32  5008.8  972.54    5022  976.29
  5037.9  980.71  5137.9  993.19  5181.7 1001.05  5187.9 1000.77  5202.5  1004.7
  5223.4 1006.76  5323.4 1032.39  5352.5 1043.35  5387.9 1061.07  5402.5 1070.58
  5408.8    1072  5431.7  1087.2  5437.9 1089.13  5452.5 1099.57  5467.1 1106.63
  5473.4 1107.95  5481.7 1114.06  5487.9 1114.59  5492.1 1120.47  5495.2 1120.47
#Mann= 4 ,-1 , 0
  4895.2    .035       0    4988    .035       0  4997.5    .035       0
    5022     .12       0
Bank Sta=4988,4997.5
XS Rating Curve= 0 ,0
Exp/Cntr=0.3,0.1

Type RM Length L Ch R = 1 ,11562   ,288,288,288
BEGIN DESCRIPTION:
Dry Bear Creek 25.0
END DESCRIPTION:
XS GIS Cut Line= 3
      2207982.28     13847884.82      2208186.93     13847505.14
      2208071.73     13847138.11
#Sta/Elev= 30
  4595.6  991.74    4844  988.39  4856.7  987.48  4869.2  983.83  4885.5  981.02
  4929.3  978.01  4958.9  973.74  4976.9  968.44  4977.4  967.94  4986.4  968.44
  5004.4     976  5011.2  985.32  5024.2  999.03  5121.7 1003.82  5173.8 1004.78
  5186.6 1013.65  5194.8 1014.72  5213.8 1014.93    5219 1017.06  5246.2 1017.14
  5251.4 1018.89  5278.6 1019.43  5283.8 1021.65  5316.2 1023.94  5321.5  1026.1
  5348.7  1027.1  5353.9 1028.95  5381.1 1031.14  5386.3 1033.61  5411.6 1034.72
#Mann= 4 ,-1 , 0
  4595.6    .035       0    4844     .12       0  4976.9     .05       0
  4986.4     .12       0
Bank Sta=4976.9,4986.4
XS Rating Curve= 0 ,0
Exp/Cntr=0.3,0.1

Type RM Length L Ch R = 1 ,11274   ,275,275,275
BEGIN DESCRIPTION:
X18873
END DESCRIPTION:
XS GIS Cut Line= 2
      2208065.71     13847971.06       2208480.2     13847642.69
#Sta/Elev= 30
  4640.2   990.5    4679  990.01  4722.3  988.84  4743.1   988.8  4883.6  985.29
  4900.2  985.69    4921  985.17  4929.1  983.84  4935.4  980.43  4943.5  977.36
  4949.9  976.23  4957.9  975.61  4999.5  974.28  5007.6  972.78    5014  971.04
    5022  969.86  5034.8  969.75  5038.1  969.16  5038.6  968.66  5047.1  968.66
  5047.6  969.16  5063.6  970.32  5078.1  982.03  5085.8  983.76  5092.5   983.4
  5098.9  984.31  5106.9  984.26  5113.3  985.77  5135.8  984.07    5169  984.76
#Mann= 4 ,-1 , 0
  4640.2    .035       0  4883.6     .12       0  5038.1     .05       0
  5047.6     .07       0
Bank Sta=5038.1,5047.6
XS Rating Curve= 0 ,0
Exp/Cntr=0.3,0.1

Type RM Length L Ch R = 1 ,10999   ,246,246,246
BEGIN DESCRIPTION:
Dry Bear Creek 24.0
END DESCRIPTION:
XS GIS Cut Line= 3
      2208675.01     13848125.01        2208525.       13847925.
        2208525.     13847725.01
#Sta/Elev= 30
    4750 1018.37  4771.9 1019.01  4778.1 1017.63  4792.7 1012.31  4821.7 1006.63
  4842.7  1003.4  4857.3  998.11  4871.9  994.12    4900   988.9  4929.6  984.69
    4950  983.03  4957.3  980.84  4963.6  981.52  4971.9  980.08  4978.1  980.61
  4986.5   973.1  4992.7  972.98  4996.9  966.95  5002.5  966.95  5004.7   964.7
  5005.2   964.2  5015.4   964.7    5040  969.19    5060  971.23    5070  970.61
    5090  966.97    5110  967.41  5132.1  974.48    5170  983.73    5200  985.34
#Mann= 6 ,-1 , 0
    4750    .063       0  4821.7    .035       0  4929.6     .12       0
  5004.7     .05       0  5015.4     .12       0  5132.1     .07       0
Bank Sta=5004.7,5015.4
XS Rating Curve= 0 ,0
Exp/Cntr=0.3,0.1

Type RM Length L Ch R = 1 ,10753   ,236,236,236
BEGIN DESCRIPTION:
X18872
END DESCRIPTION:
XS GIS Cut Line= 2
      2208846.73     13848084.16      2208647.77     13847659.34
#Sta/Elev= 30
  4821.1 1030.98  4831.2 1029.51  4832.4 1028.01  4836.9  1022.4  4842.4 1019.49
  4853.3 1019.46  4905.3 1022.63  4910.9 1021.76  4919.6 1018.56  4941.6 1004.64
    4951  994.72  4956.5  988.38  4963.7  970.22  4973.8  962.33  4979.4  962.07
  4985.8  964.42  4991.3  961.22  4991.8  960.72    5002  961.22  5010.5  962.82
  5018.9  964.71    5025  968.47  5052.8  971.65    5099  975.88  5116.3  979.32
  5121.9  979.39  5129.4  981.69  5144.7     983    5251  983.52  5290.2   983.6
#Mann= 7 ,-1 , 0
  4821.1    .035       0  4832.4    .063       0  4991.3    .063       0
    5002    .063       0  5010.5    .035       0  5052.8     .12       0
    5251     .07       0
Bank Sta=4991.3,5002
XS Rating Curve= 0 ,0
Exp/Cntr=0.3,0.1

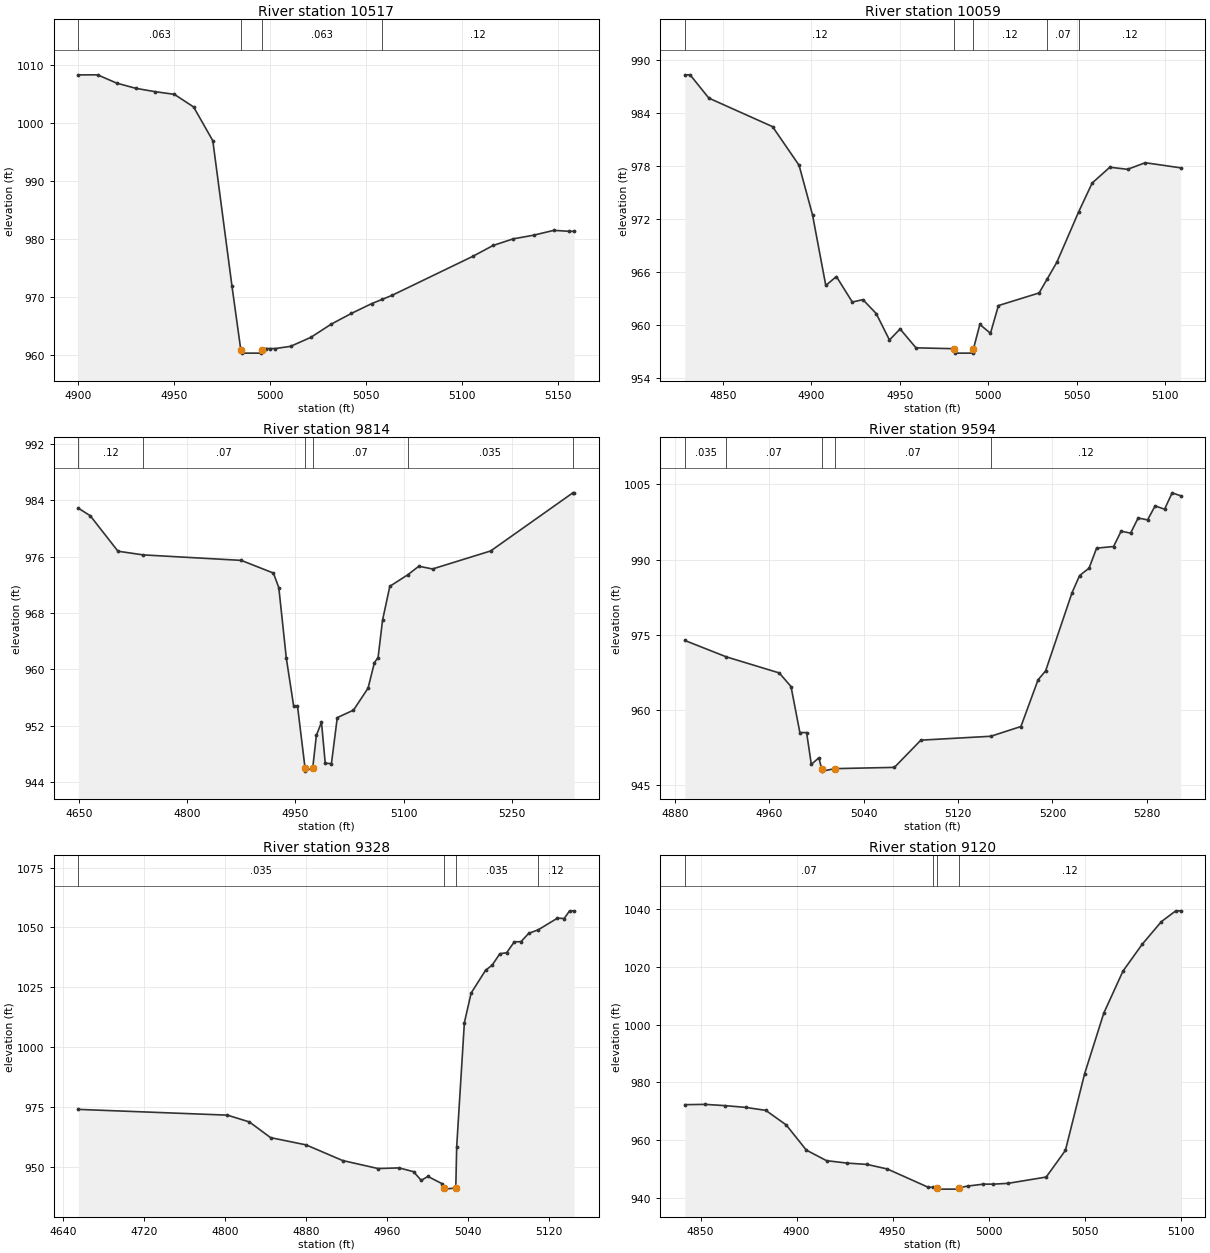
Type RM Length L Ch R = 1 ,10517   ,458,458,458
BEGIN DESCRIPTION:
Dry Bear Creek 23.0
END DESCRIPTION:
XS GIS Cut Line= 3
      2209024.96       13847775.        2208925.       13847775.
      2208774.97     13847724.99
#Sta/Elev= 30
  4900.1 1008.26  4910.1 1008.27  4920.1 1006.84  4930.1 1005.94  4940.1 1005.37
  4950.1 1004.91  4960.1 1002.74  4970.1  996.93  4980.1  971.84  4984.7  960.87
  4985.2  960.37    4995  960.37  4995.5  960.87  4997.6  961.16  5000.1  961.16
  5002.7  961.16  5010.6  961.54  5021.1  963.08  5031.7  965.35  5042.2   967.2
  5052.8  968.89  5058.4  969.64  5063.3   970.3  5105.5  977.04    5116   978.9
  5126.5  980.04  5137.1  980.67  5147.6   981.5  5155.5  981.34  5158.2  981.34
#Mann= 4 ,-1 , 0
  4900.1    .063       0  4984.7    .063       0  4995.5    .063       0
  5058.4     .12       0
Bank Sta=4984.7,4995.5
XS Rating Curve= 0 ,0
Exp/Cntr=0.3,0.1

Type RM Length L Ch R = 1 ,10059   ,245,245,245
BEGIN DESCRIPTION:
Dry Bear Creek 22.0
END DESCRIPTION:
XS GIS Cut Line= 3
      2208975.03     13847475.02        2208825.       13847375.
      2208725.02       13847375.
#Sta/Elev= 30
  4828.5  988.34  4831.5  988.34  4842.1   985.7  4878.1  982.47  4893.1  978.09
  4900.7  972.47  4908.2  964.47  4914.2  965.48  4923.2  962.59  4929.2  962.86
  4936.7  961.29  4944.2  958.29  4950.2  959.54  4959.2   957.4  4980.9   957.3
  4981.4   956.8  4991.2   956.8  4991.7   957.3  4995.3  960.05  5001.3  959.05
  5005.8  962.19  5028.8  963.62  5033.3  965.18  5038.8  967.09  5051.2  972.83
  5058.8  976.08  5068.8  977.87  5078.8  977.63  5088.8  978.38  5108.8   977.8
#Mann= 5 ,-1 , 0
  4828.5     .12       0  4980.9     .05       0  4991.7     .12       0
  5033.3     .07       0  5051.2     .12       0
Bank Sta=4980.9,4991.7
XS Rating Curve= 0 ,0
Exp/Cntr=0.3,0.1

Type RM Length L Ch R = 1 ,9814    ,220,220,220
BEGIN DESCRIPTION:
X18870
END DESCRIPTION:
XS GIS Cut Line= 3
      2209161.79     13847235.83       2208814.4      13847133.5
      2208491.26     13847173.89
#Sta/Elev= 30
  4648.9  982.89  4665.4  981.82  4703.9  976.78  4738.8  976.26  4874.9  975.48
  4919.5  973.68    4927  971.61  4937.4   961.6  4947.7  954.74  4952.9  954.85
  4963.3  946.06  4963.8  945.56  4974.1  946.06  4979.1  950.63  4986.2  952.51
  4991.4  946.68    5000  946.63  5008.1  953.16  5030.6  954.22  5050.8  957.34
  5059.6  960.96  5064.7  961.69  5070.9  966.99    5081   971.8  5105.7  973.42
  5121.3  974.65  5140.2  974.26  5220.9  976.82  5334.9  985.07  5336.7  985.07
#Mann= 6 ,-1 , 0
  4648.9     .12       0  4738.8     .07       0  4963.3     .05       0
  4974.1     .07       0  5105.7    .035       0  5334.9     .07       0
Bank Sta=4963.3,4974.1
XS Rating Curve= 0 ,0
Exp/Cntr=0.3,0.1

Type RM Length L Ch R = 1 ,9594    ,266,266,266
BEGIN DESCRIPTION:
Dry Bear Creek 21.0
END DESCRIPTION:
XS GIS Cut Line= 3
      2208924.95       13846925.        2208825.       13846925.
      2208575.01     13846725.01
#Sta/Elev= 30
  4888.5  973.82  4923.7  970.54  4968.5  967.33  4978.5  964.61    4986  955.41
  4991.7  955.41  4995.7  949.05  5002.1  950.37  5004.4   948.2  5004.9   947.7
  5015.8   948.2  5066.1  948.45  5088.5  953.89  5147.8  954.67  5173.3  956.62
  5187.8  965.95  5194.2  967.73  5216.6  983.37    5223   986.8    5231  988.26
  5237.4  992.27  5251.8   992.6  5258.2  995.67  5266.2  995.27  5272.6   998.3
  5280.6  997.92    5287 1000.72    5295 1000.05  5301.4 1003.33  5308.6 1002.74
#Mann= 5 ,-1 , 0
  4888.5    .035       0  4923.7     .07       0  5004.4     .05       0
  5015.8     .07       0  5147.8     .12       0
Bank Sta=5004.4,5015.8
XS Rating Curve= 0 ,0
Exp/Cntr=0.3,0.1

Type RM Length L Ch R = 1 ,9328    ,208,208,208
BEGIN DESCRIPTION:
X18871
END DESCRIPTION:
XS GIS Cut Line= 2
        2209046.      13846942.3      2208722.82     13846573.32
#Sta/Elev= 30
  4654.8  974.18  4802.3  971.78    4824  968.95    4845  962.41  4880.1  959.38
  4916.2  952.87  4951.3  949.52  4972.2  949.79  4986.4  948.21    4994  944.59
  5000.6  946.23  5014.9  943.15  5016.8  941.44  5017.3  940.94  5028.2  941.44
  5029.1  958.66  5036.7 1010.35  5043.4 1022.68  5057.6 1032.13  5064.2 1034.32
  5071.8 1039.07  5078.5 1039.48  5086.1 1044.02  5092.7  1044.1  5100.3 1047.55
  5109.8 1049.05  5128.8 1053.91  5135.4 1053.74  5140.8 1056.95  5145.3 1056.95
#Mann= 4 ,-1 , 0
  4654.8    .035       0  5016.8    .035       0  5028.2    .035       0
  5109.8     .12       0
Bank Sta=5016.8,5028.2
XS Rating Curve= 0 ,0
Exp/Cntr=0.3,0.1

Type RM Length L Ch R = 1 ,9120    ,451,451,451
BEGIN DESCRIPTION:
Dry Bear Creek 20.0
END DESCRIPTION:
XS GIS Cut Line= 3
      2209075.02     13846825.05        2209025.       13846675.
        2209025.     13846574.96
#Sta/Elev= 30
  4841.8  972.32  4852.4  972.42  4862.9  971.98  4873.5  971.38    4884  970.34
  4894.6  965.32  4905.1   956.6  4915.6  952.95  4926.2  952.11  4936.7  951.65
  4947.3  950.06  4968.3  943.82  4971.2  943.69  4973.2   943.6  4973.7   943.1
  4984.1   943.1  4984.6   943.6  4989.4  944.18  4997.3  944.83  5002.5  944.83
    5010  945.09    5030  947.28    5040   956.5    5050  983.01    5060 1004.01
    5070 1018.55    5080 1027.82    5090 1035.66  5097.5 1039.38    5100 1039.38
#Mann= 4 ,-1 , 0
  4841.8     .07       0  4971.2     .12       0  4973.2     .05       0
  4984.6     .12       0
Bank Sta=4973.2,4984.6
XS Rating Curve= 0 ,0
Exp/Cntr=0.3,0.1

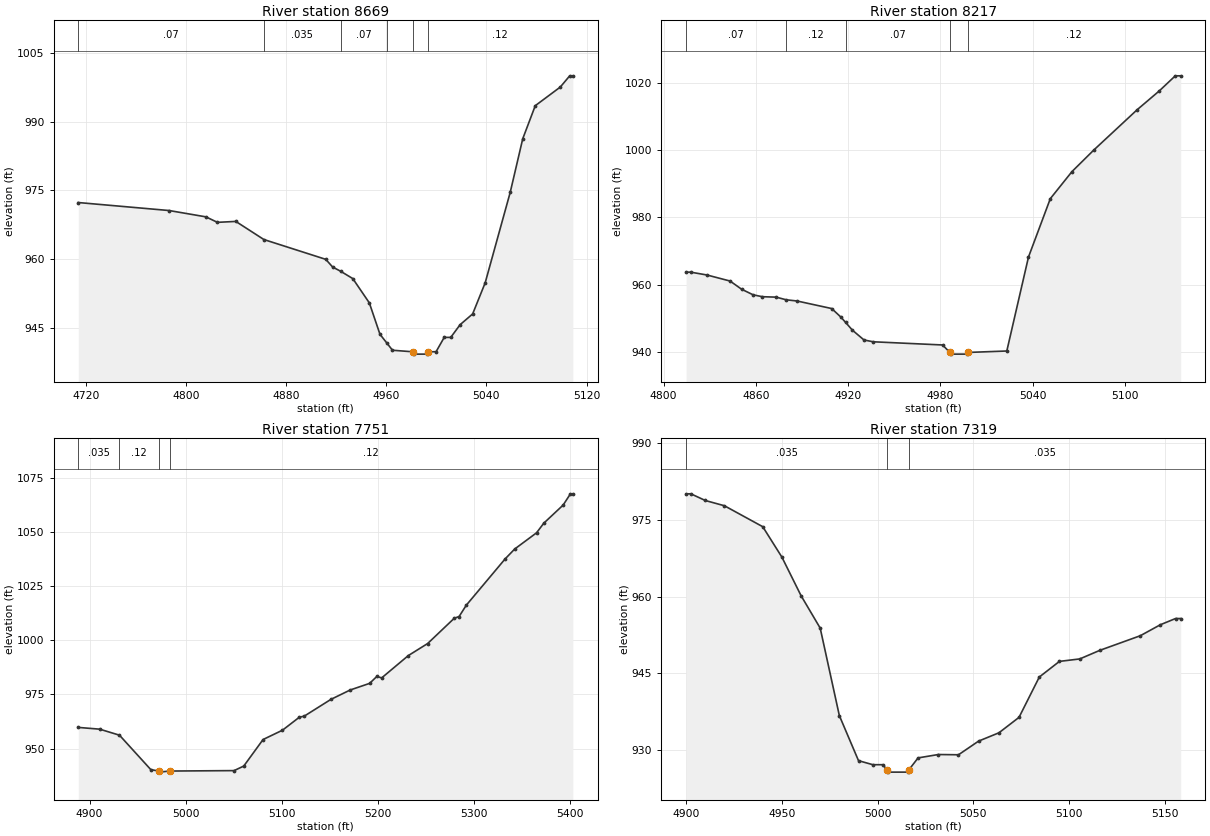
Type RM Length L Ch R = 1 ,8669    ,452,452,452
BEGIN DESCRIPTION:
Dry Bear Creek 19.0
END DESCRIPTION:
XS GIS Cut Line= 3
      2209312.61      13846947.7        2209425.       13846675.
        2209425.     13846575.05
#Sta/Elev= 30
  4714.1  972.34  4786.7  970.59    4816  969.21  4825.2  968.01  4839.9  968.21
  4862.3  964.25  4911.7  959.92  4917.2  958.24  4923.6  957.31  4933.3  955.71
  4946.5   950.4    4955  943.53  4960.5  941.61    4965  940.04  4981.7  939.69
  4982.2  939.19  4992.7  939.19  4993.2  939.69  4999.8  939.72  5006.3  942.85
  5011.5  942.85    5019  945.63    5029  947.98    5039  954.78    5059  974.57
    5069  986.29    5079  993.52    5099   997.6  5106.5 1000.05    5109 1000.05
#Mann= 6 ,-1 , 0
  4714.1     .07       0  4862.3    .035       0  4923.6     .07       0
  4960.5     .12       0  4981.7     .05       0  4993.2     .12       0
Bank Sta=4981.7,4993.2
XS Rating Curve= 0 ,0
Exp/Cntr=0.3,0.1

Type RM Length L Ch R = 1 ,8217    ,466,466,466
BEGIN DESCRIPTION:
Dry Bear Creek 18.0
END DESCRIPTION:
XS GIS Cut Line= 3
      2209724.98     13846975.04        2209825.       13846825.
      2209924.97     13846725.03
#Sta/Elev= 30
  4814.6   963.7  4817.6   963.7  4828.2  962.85  4843.2  961.05  4850.7  958.61
  4858.2  956.94  4864.2  956.38  4873.2  956.25  4879.7  955.46  4886.8   955.1
  4909.3  952.85  4915.3  950.29  4918.3  948.73  4922.8  946.39  4930.3  943.48
  4936.3  942.94  4981.4  941.99  4986.2  939.76  4986.7  939.26  4997.2  939.26
  4997.7  939.76  5023.2  940.19  5037.3  968.21  5051.5  985.62  5065.6  993.69
  5079.8 1000.12  5108.1 1012.18  5122.2 1017.67  5132.8 1022.24  5136.3 1022.24
#Mann= 5 ,-1 , 0
  4814.6     .07       0  4879.7     .12       0  4918.3     .07       0
  4986.2     .05       0  4997.7     .12       0
Bank Sta=4986.2,4997.7
XS Rating Curve= 0 ,0
Exp/Cntr=0.3,0.1

Type RM Length L Ch R = 1 ,7751    ,432,432,432
BEGIN DESCRIPTION:
Dry Bear Creek 17.0
END DESCRIPTION:
XS GIS Cut Line= 3
      2210075.01     13847224.99        2210125.       13847125.
        2210175.       13846725.
#Sta/Elev= 30
  4888.2  959.76  4910.5  958.95  4931.1  956.17  4963.7  940.29  4971.8  939.62
  4972.3  939.12  4983.4  939.62  5050.4  939.82  5060.5  941.92  5080.6  954.17
  5100.8  958.47  5118.4  964.48  5123.4  964.94  5151.2  972.69  5171.3  977.03
  5191.5  980.08    5199  983.26  5204.1  982.62  5231.8  992.91  5251.9  998.46
  5279.6 1010.12  5284.7 1010.95  5292.2 1016.18  5332.6 1037.53  5342.6 1042.11
  5365.3 1049.57  5372.9 1054.04    5393 1062.38  5400.6 1067.57  5403.1 1067.57
#Mann= 4 ,-1 , 0
  4888.2    .035       0  4931.1     .12       0  4971.8     .05       0
  4983.4     .12       0
Bank Sta=4971.8,4983.4
XS Rating Curve= 0 ,0
Exp/Cntr=0.3,0.1

Type RM Length L Ch R = 1 ,7319    ,232,232,232
BEGIN DESCRIPTION:
Dry Bear Creek 16.0
END DESCRIPTION:
XS GIS Cut Line= 3
        2210425.     13847475.05        2210425.       13847375.
      2210475.01     13847224.96
#Sta/Elev= 30
    4900  980.08  4902.5  980.08    4910  978.78    4920  977.75    4940  973.66
    4950  967.72    4960  960.19    4970  953.85    4980  936.76    4990  927.96
  4997.5  927.17  5002.7  927.17  5004.8  926.22  5005.3  925.72  5015.9  925.72
  5016.4  926.22  5021.1   928.5  5031.7  929.16  5042.2  929.11  5052.7  931.78
  5063.3   933.4  5073.8  936.42  5084.4   944.3  5094.9  947.35  5105.5  947.83
    5116  949.51  5137.1  952.36  5147.6  954.51  5155.5  955.72  5158.2  955.72
#Mann= 3 ,-1 , 0
    4900    .035       0  5004.8    .035       0  5016.4    .035       0
Bank Sta=5004.8,5016.4
XS Rating Curve= 0 ,0
Exp/Cntr=0.3,0.1