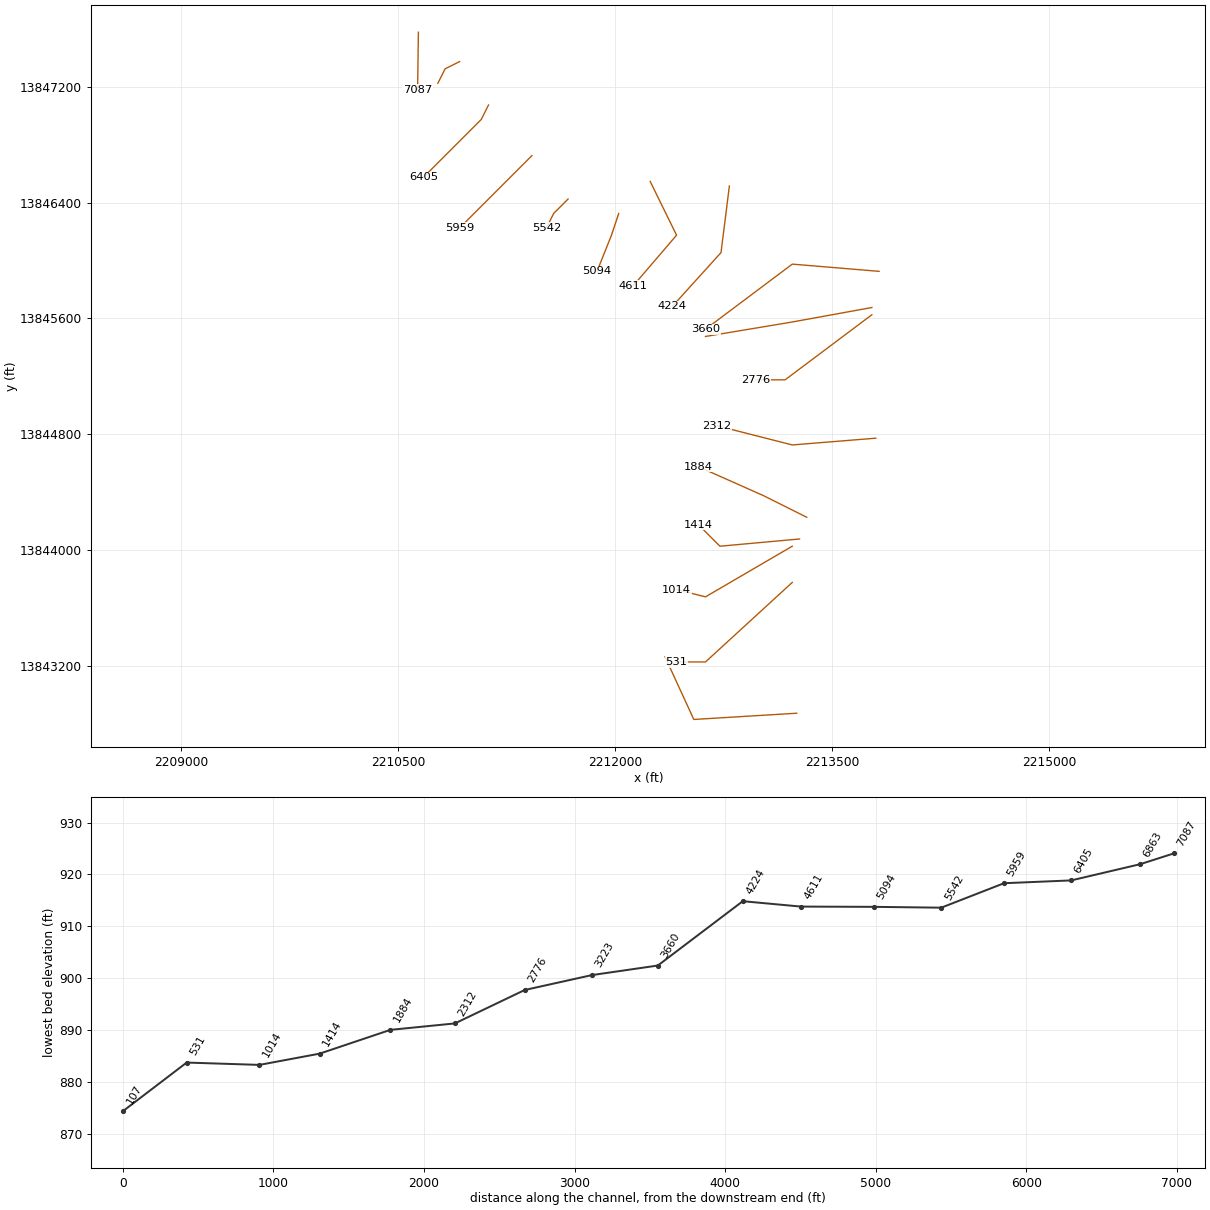
HEC-RAS study Dry Bear Creek.prj: Dry Bear Creek Base Level Engineering

--- Dry Bear Creek.g01 (geometry) --- (continued)

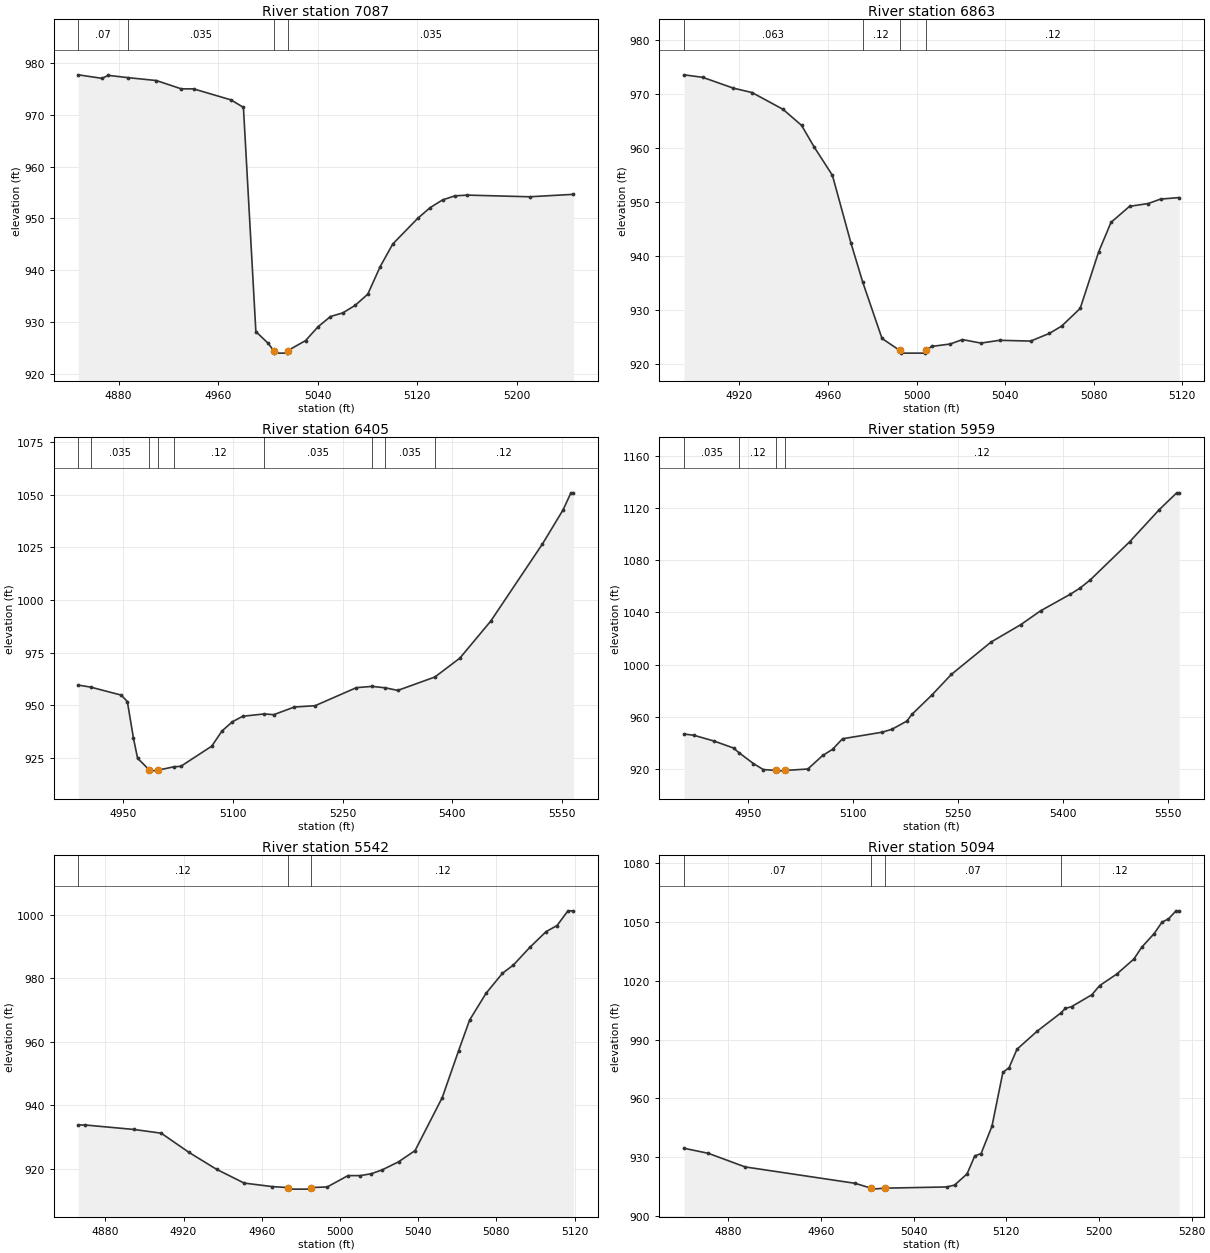
Type RM Length L Ch R = 1 ,7087    ,224,224,224
BEGIN DESCRIPTION:
X18869
END DESCRIPTION:
XS GIS Cut Line= 2
      2210640.27     13847577.83      2210634.89     13847179.66
#Sta/Elev= 30
  4847.6  977.66  4866.7  976.98  4871.7  977.56  4887.8  977.11  4910.4  976.56
  4930.4  974.96  4940.4  974.95  4970.4  972.83  4980.4  971.39  4990.4   928.2
  5000.4  925.92  5004.6  924.55  5005.1  924.05  5015.7  924.05  5016.2  924.55
  5030.4  926.47  5040.4  929.13  5050.4   931.1  5060.4  931.81  5070.4  933.28
  5080.4  935.41  5090.4  940.73  5100.5  945.08  5120.5     950  5130.5  952.07
  5140.5  953.56  5150.5  954.35  5160.5  954.49  5210.5  954.17  5245.8  954.64
#Mann= 4 ,-1 , 0
  4847.6     .07       0  4887.8    .035       0  5004.6    .035       0
  5016.2    .035       0
Bank Sta=5004.6,5016.2
XS Rating Curve= 0 ,0
Exp/Cntr=0.3,0.1

Type RM Length L Ch R = 1 ,6863    ,458,458,458
BEGIN DESCRIPTION:
Dry Bear Creek 15.0
END DESCRIPTION:
XS GIS Cut Line= 3
      2210924.97     13847374.98        2210825.       13847325.
      2210774.99     13847224.98
#Sta/Elev= 30
    4895  973.53  4903.4  973.07  4917.3  971.06  4925.7  970.25  4939.7  967.14
  4948.1  964.16  4953.7   960.2    4962  954.92  4970.4  942.33  4975.7  935.12
  4984.4  924.69  4992.4  922.47  4992.9  921.97  5003.9  921.97  5004.4  922.47
  5006.8  923.21  5015.2  923.66  5020.7  924.48  5029.1  923.83  5037.5  924.35
  5051.5   924.2  5059.9  925.61  5065.5  926.97  5073.9  930.26  5082.2  940.69
  5087.8  946.19  5096.2  949.17  5104.6  949.68  5110.2  950.51  5118.6  950.79
#Mann= 4 ,-1 , 0
    4895    .063       0  4975.7     .12       0  4992.4     .05       0
  5004.4     .12       0
Bank Sta=4992.4,5004.4
XS Rating Curve= 0 ,0
Exp/Cntr=0.3,0.1

Type RM Length L Ch R = 1 ,6405    ,446,446,446
BEGIN DESCRIPTION:
Dry Bear Creek 14.0
END DESCRIPTION:
XS GIS Cut Line= 3
      2211125.02     13847075.03        2211075.       13846975.
      2210675.02     13846575.02
#Sta/Elev= 30
  4888.2  959.66    4905   958.7  4946.9  954.91  4955.3  951.86  4963.7  934.43
  4969.3  924.96  4985.6  919.34  4986.1  918.84  4997.7  919.34  5019.6  920.94
  5028.3  921.09  5070.7  930.66  5084.9  937.91    5099  942.26  5113.2  944.86
  5142.4  945.97  5155.6  945.62  5183.9  949.26  5212.2  949.87  5268.7  958.44
  5290.1  959.04  5308.3  958.36  5325.3  957.13  5376.1  963.49  5410.2  972.43
  5452.6  990.04  5523.3 1026.62  5551.6 1042.84  5562.2 1050.86  5565.7 1050.86
#Mann= 9 ,-1 , 0
  4888.2    .063       0    4905    .035       0  4985.6    .035       0
  4997.7    .035       0  5019.6     .12       0  5142.4    .035       0
  5290.1     .07       0  5308.3    .035       0  5376.1     .12       0
Bank Sta=4985.6,4997.7
XS Rating Curve= 0 ,0
Exp/Cntr=0.3,0.1

Type RM Length L Ch R = 1 ,5959    ,417,417,417
BEGIN DESCRIPTION:
Dry Bear Creek 13.0
END DESCRIPTION:
XS GIS Cut Line= 3
        2211425.       13846725.        2211325.       13846625.
        2210925.       13846225.
#Sta/Elev= 30
  4858.8  946.75  4872.9  945.77  4901.2  941.43  4929.5  936.01  4937.1   932.5
  4957.8  924.14  4971.9  919.53  4990.6   918.8  4991.1   918.3  5002.7   918.8
  5035.6  919.94  5056.8  930.29  5070.9  935.01  5085.1   943.1  5141.6  948.11
  5155.8  950.39    5177  956.66  5184.1  961.73  5212.4  976.43  5240.6  992.44
  5297.2 1017.19  5339.6 1030.52  5367.9 1041.13  5410.3 1053.81  5424.5 1058.65
  5438.6 1064.69  5495.2 1094.06  5537.6 1118.77  5562.4 1131.56  5565.9 1131.56
#Mann= 4 ,-1 , 0
  4858.8    .035       0  4937.1     .12       0  4990.6     .05       0
  5002.7     .12       0
Bank Sta=4990.6,5002.7
XS Rating Curve= 0 ,0
Exp/Cntr=0.3,0.1

Type RM Length L Ch R = 1 ,5542    ,448,448,448
BEGIN DESCRIPTION:
Dry Bear Creek 12.0
END DESCRIPTION:
XS GIS Cut Line= 3
        2211675.       13846425.        2211575.       13846325.
      2211525.01     13846225.02
#Sta/Elev= 30
  4866.2  933.79  4869.7  933.79  4894.5  932.39  4908.6  931.21  4922.8  925.16
  4936.9  919.83    4951  915.49  4965.2  914.39  4973.2  914.08  4973.7  913.58
  4984.9  913.58  4985.4  914.08  4993.5  914.27  5004.1  917.84  5010.4  917.84
    5016  918.43  5021.6  919.65    5030   922.2  5038.4  925.72  5052.3  942.43
  5060.7  957.26  5066.3  966.87  5074.7  975.29  5083.1  981.61  5088.7  984.21
  5097.1  989.78  5105.4  994.72    5111  996.65  5116.6 1001.28  5119.4 1001.28
#Mann= 3 ,-1 , 0
  4866.2     .12       0  4973.2     .05       0  4985.4     .12       0
Bank Sta=4973.2,4985.4
XS Rating Curve= 0 ,0
Exp/Cntr=0.3,0.1

Type RM Length L Ch R = 1 ,5094    ,483,483,483
BEGIN DESCRIPTION:
Dry Bear Creek 11.0
END DESCRIPTION:
XS GIS Cut Line= 3
        2212025.       13846325.        2211975.       13846175.
      2211874.99     13845924.98
#Sta/Elev= 30
  4841.8  934.58  4862.9  931.98  4894.5  925.07  4989.4  916.71  5003.2  914.24
  5003.7  913.74  5015.4  914.24  5068.6  914.85  5075.3   915.8  5086.1  921.52
  5092.8  930.72  5098.2  931.85  5107.6  945.84    5117  973.23  5122.4  975.73
  5129.2  985.08  5146.7  994.34  5166.9 1003.51  5170.9 1005.88  5176.3  1006.8
  5193.8 1012.84  5200.5 1017.52  5215.3  1023.4  5230.1 1031.07  5236.9 1037.14
  5247.6 1044.05  5254.4 1049.92  5259.8 1051.46  5266.5 1055.66  5269.2 1055.66
#Mann= 4 ,-1 , 0
  4841.8     .07       0  5003.2     .05       0  5015.4     .07       0
  5166.9     .12       0
Bank Sta=5003.2,5015.4
XS Rating Curve= 0 ,0
Exp/Cntr=0.3,0.1

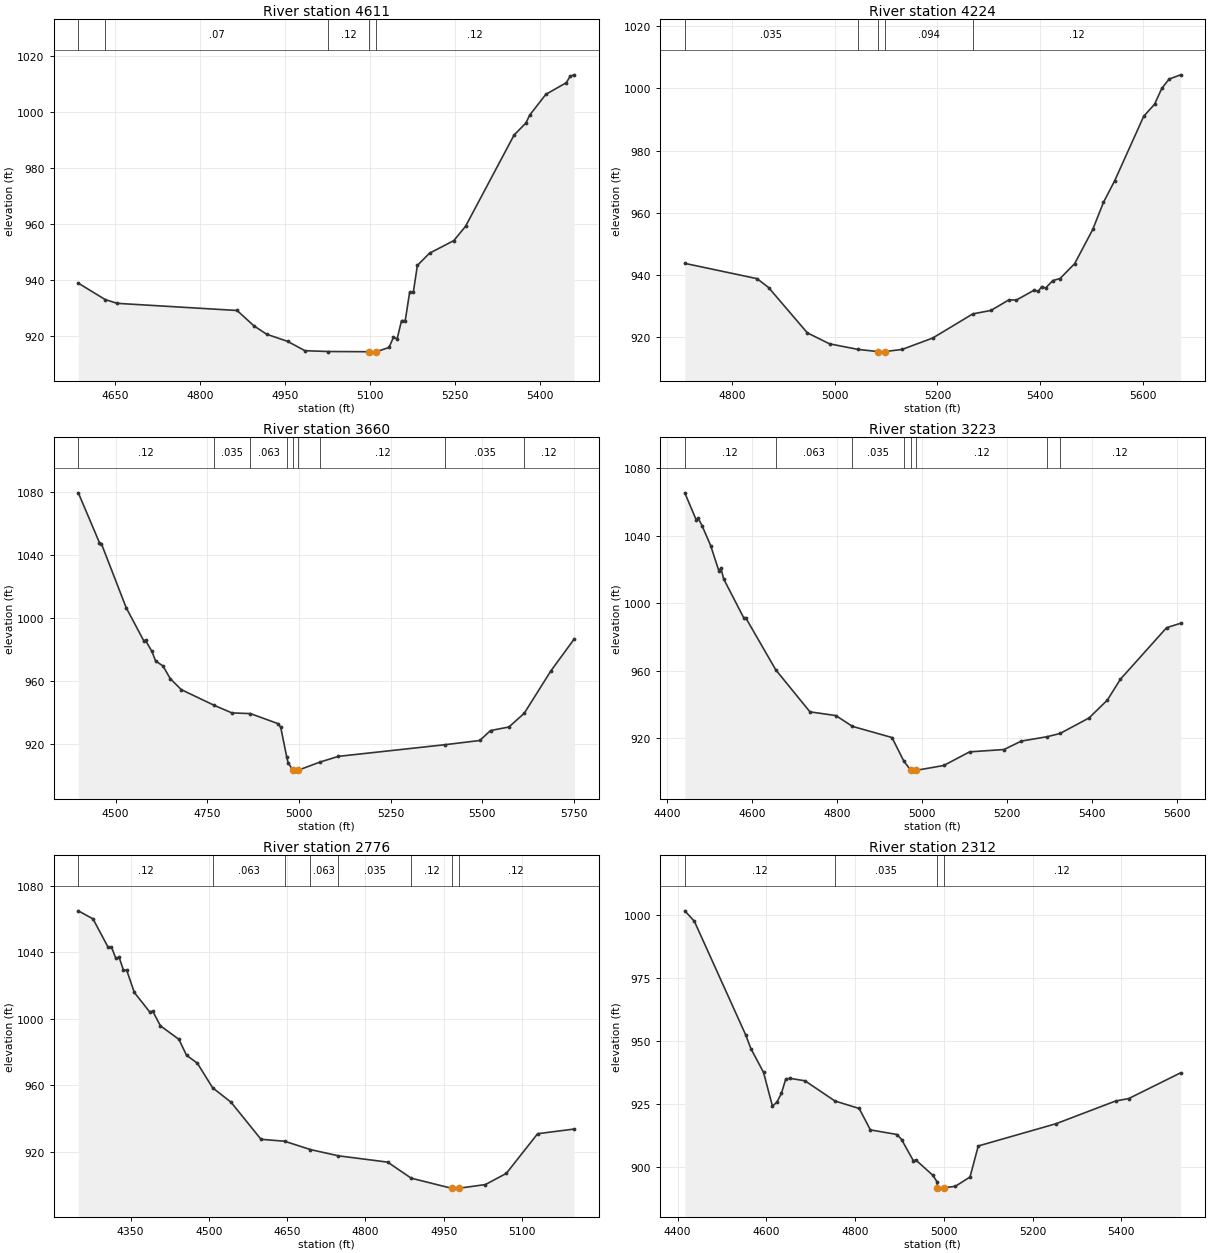
Type RM Length L Ch R = 1 ,4611    ,387,387,387
BEGIN DESCRIPTION:
Dry Bear Creek 10.0
END DESCRIPTION:
XS GIS Cut Line= 3
      2212242.62     13846546.43        2212425.       13846175.
      2212124.98     13845824.97
#Sta/Elev= 30
  4585.8  938.76    4633  932.93  4654.2  931.56  4865.9  929.01  4895.6  923.53
  4918.1  920.53    4955  917.99  4985.6  914.66  5026.2  914.37  5099.4  914.29
  5099.9  913.79  5111.6  914.29    5134  915.82  5141.7  919.43  5148.3  918.89
    5156  925.38  5162.6  925.42  5170.3  935.47  5176.8  935.51    5184   945.1
  5205.4  949.46  5248.2  953.94    5269  959.06  5354.6  991.63  5375.5  995.94
  5382.1  998.73  5410.6 1006.14  5446.8 1010.32  5453.4 1012.58  5460.6 1013.12
#Mann= 5 ,-1 , 0
  4585.8     .12       0    4633     .07       0  5026.2     .12       0
  5099.4     .05       0  5111.6     .12       0
Bank Sta=5099.4,5111.6
XS Rating Curve= 0 ,0
Exp/Cntr=0.3,0.1

Type RM Length L Ch R = 1 ,4224    ,564,564,564
BEGIN DESCRIPTION:
Dry Bear Creek 9.0
END DESCRIPTION:
XS GIS Cut Line= 3
      2212789.93     13846514.62      2212732.27     13846054.66
      2212395.54      13845682.7
#Sta/Elev= 30
  4708.1   943.7  4848.8  938.78  4871.2  935.93  4946.6  921.36  4989.9  917.82
  5045.3  916.03  5084.2  915.33  5084.7  914.83  5097.1  915.33    5131  916.01
  5190.7  919.68  5268.8  927.45  5304.2  928.57  5339.4  931.99  5353.6  931.89
  5388.7  935.12  5396.2  934.68  5402.9  936.23  5410.4  935.76  5424.6  938.17
  5438.7  938.83  5467.1  943.61  5502.3   954.6  5523.2  963.33  5544.9  970.23
  5601.6  991.03  5622.6  994.87  5636.8    1000    5651 1002.97  5673.4 1004.34
#Mann= 5 ,-1 , 0
  4708.1    .035       0  5045.3    .094       0  5084.2    .035       0
  5097.1    .094       0  5268.8     .12       0
Bank Sta=5084.2,5097.1
XS Rating Curve= 0 ,0
Exp/Cntr=0.3,0.1

Type RM Length L Ch R = 1 ,3660    ,437,437,437
BEGIN DESCRIPTION:
Dry Bear Creek 8.0
END DESCRIPTION:
XS GIS Cut Line= 3
      2213825.03       13845925.        2213225.       13845975.
      2212625.01     13845525.01
#Sta/Elev= 30
  4398.3 1079.64    4456 1047.82    4461 1047.36  4528.8 1006.49  4576.4  985.58
  4581.5  985.66    4599  978.63  4609.1  972.51  4629.1  969.41  4649.2  961.22
  4679.3  954.29  4768.5  944.35  4817.3  939.49  4867.6  939.06  4942.7  932.67
  4950.2  930.36  4966.7  911.31  4970.3  907.84  4983.8  902.92  4984.3  902.42
  4996.9  902.92  5056.7  908.15  5107.7  911.83  5398.3  919.25  5493.1  921.93
  5522.3  928.26  5572.3  930.51  5614.2  939.24  5686.9  966.25  5750.4  986.53
#Mann= 9 ,-1 , 0
  4398.3     .12       0  4768.5    .035       0  4867.6    .063       0
  4966.7    .035       0  4983.8    .035       0  4996.9    .035       0
  5056.7     .12       0  5398.3    .035       0  5614.2     .12       0
Bank Sta=4983.8,4996.9
XS Rating Curve= 0 ,0
Exp/Cntr=0.3,0.1

Type RM Length L Ch R = 1 ,3223    ,447,447,447
BEGIN DESCRIPTION:
Dry Bear Creek 7.0
END DESCRIPTION:
XS GIS Cut Line= 3
      2213774.96     13845674.99        2213225.       13845575.
      2212624.95     13845474.99
#Sta/Elev= 30
    4441 1065.43  4467.6 1049.57  4472.7 1050.39  4481.6 1045.97  4501.9 1034.18
    4521 1019.35  4526.1 1020.79  4532.4 1014.48  4579.4  991.57  4584.5  991.38
  4655.2  960.56  4735.7  935.69  4796.7  933.49  4835.7  927.09  4928.8  920.48
  4956.6  906.54  4973.1  901.08  4973.6  900.58  4986.2  901.08  5050.7  903.92
  5111.5     912  5192.6  913.38  5233.1  918.36  5293.8  920.96  5324.5  922.89
  5392.8  932.09  5435.9  942.69  5466.3  954.95  5575.3  985.55  5608.3  988.16
#Mann= 8 ,-1 , 0
    4441     .12       0  4655.2    .063       0  4835.7    .035       0
  4956.6     .12       0  4973.1     .05       0  4986.2     .12       0
  5293.8    .035       0  5324.5     .12       0
Bank Sta=4973.1,4986.2
XS Rating Curve= 0 ,0
Exp/Cntr=0.3,0.1

Type RM Length L Ch R = 1 ,2776    ,464,464,464
BEGIN DESCRIPTION:
Dry Bear Creek 6.0
END DESCRIPTION:
XS GIS Cut Line= 3
      2213774.98     13845624.99        2213175.       13845175.
      2212974.98       13845175.
#Sta/Elev= 30
    4250 1064.95  4278.1  1060.1  4307.3 1042.94  4313.5 1043.21  4321.9 1036.34
  4328.1 1037.03  4336.4 1029.34  4342.7 1029.25  4357.3 1015.87  4386.4 1004.34
  4392.7 1004.53  4407.3  995.85  4442.7  987.71  4457.3  978.15  4478.1  973.37
  4507.2  958.65  4542.7  949.89    4600  927.65  4645.1  926.49  4694.8  921.47
  4748.1  917.73  4842.7  913.92  4887.8  904.28  4965.3   898.2  4965.8   897.7
  4978.4   898.2    5030  900.45    5070  907.15    5130     931    5200  933.81
#Mann= 8 ,-1 , 0
    4250     .12       0  4507.2    .063       0  4645.1    .035       0
  4694.8    .063       0  4748.1    .035       0  4887.8     .12       0
  4965.3     .05       0  4978.4     .12       0
Bank Sta=4965.3,4978.4
XS Rating Curve= 0 ,0
Exp/Cntr=0.3,0.1

Type RM Length L Ch R = 1 ,2312    ,428,428,428
BEGIN DESCRIPTION:
Dry Bear Creek 5.0
END DESCRIPTION:
XS GIS Cut Line= 3
      2213801.86     13844771.72        2213225.       13844725.
       2212703.1      13844857.9
#Sta/Elev= 30
  4416.2  1001.7  4437.8  997.54  4553.5  952.43    4565  947.05  4593.6  937.61
  4613.7  924.19  4623.7  925.77  4633.8  929.21  4643.8  935.02  4653.8   935.2
  4687.1  934.24  4754.6  926.22  4809.2  923.25  4834.4  914.76  4894.6  912.93
  4904.7  910.93  4931.4  902.47  4936.4  902.88  4974.9  896.79  4984.9   894.1
  4985.6  891.75  4986.1  891.25  4999.3  891.75  5025.9  892.37  5058.9  896.07
  5077.5  908.38  5252.9  917.22  5387.1  926.23  5416.6   927.2  5533.5  937.41
#Mann= 4 ,-1 , 0
  4416.2     .12       0  4754.6    .035       0  4985.6     .05       0
  4999.3     .12       0
Bank Sta=4985.6,4999.3
XS Rating Curve= 0 ,0
Exp/Cntr=0.3,0.1

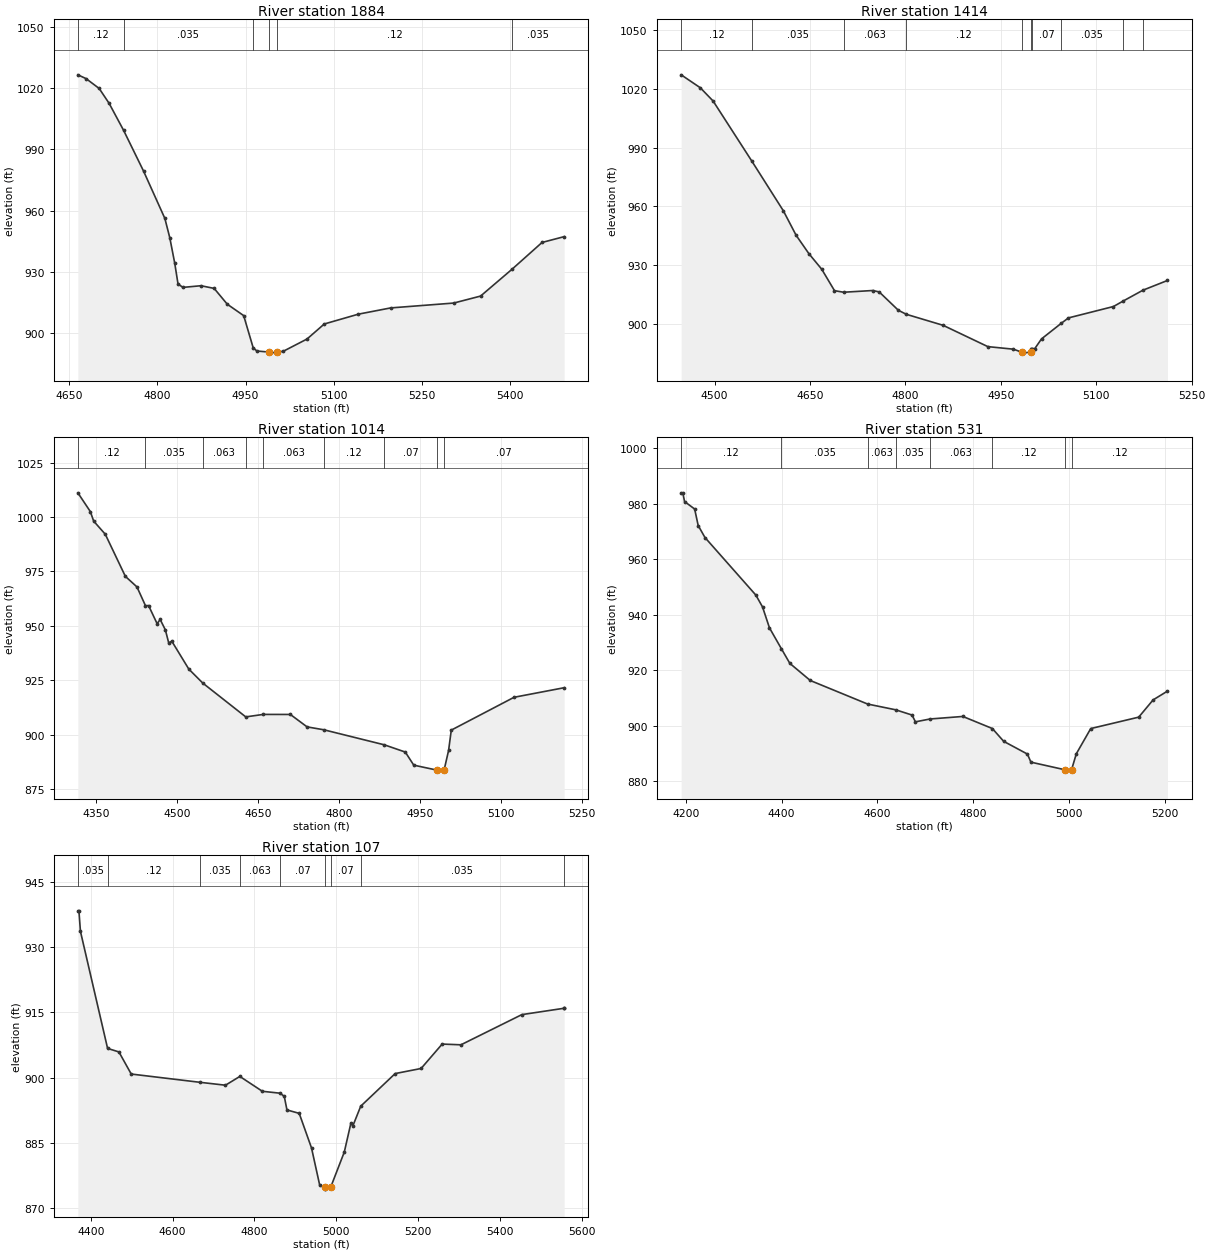
Type RM Length L Ch R = 1 ,1884    ,470,470,470
BEGIN DESCRIPTION:
Dry Bear Creek 4.0
END DESCRIPTION:
XS GIS Cut Line= 3
      2213325.01       13844225.        2213025.       13844375.
      2212574.96     13844575.02
#Sta/Elev= 30
  4664.6 1026.64  4678.6 1024.78  4700.9 1019.94  4717.7  1012.7  4742.5  999.37
  4776.4   979.4  4812.7  956.15  4821.1  946.67  4829.5   934.2  4835.1  923.97
  4843.5  922.28  4874.2   923.1  4896.6  921.79    4919  914.02  4946.9  908.42
  4963.1  892.61  4969.3  891.06  4990.4  890.51  4990.9  890.01  5004.1  890.51
  5014.4  890.93  5054.7  896.93  5084.1  904.32  5142.3  909.15    5197   912.2
  5304.4  914.59  5350.2  918.02  5403.4  931.11  5454.8  944.34  5492.5   947.2
#Mann= 6 ,-1 , 0
  4664.6     .12       0  4742.5    .035       0  4963.1     .12       0
  4990.4     .05       0  5004.1     .12       0  5403.4    .035       0
Bank Sta=4990.4,5004.1
XS Rating Curve= 0 ,0
Exp/Cntr=0.3,0.1

Type RM Length L Ch R = 1 ,1414    ,400,400,400
BEGIN DESCRIPTION:
Dry Bear Creek 3.0
END DESCRIPTION:
XS GIS Cut Line= 3
      2213274.99       13844075.        2212725.       13844025.
      2212574.99     13844175.01
#Sta/Elev= 30
  4447.5 1026.97  4477.6 1020.38  4497.7 1013.65  4558.2  983.27  4608.1  957.82
  4628.2  945.35  4648.3  935.99  4668.4  928.11  4688.5  917.19  4702.8  916.39
  4748.7  917.27  4758.8  916.54  4788.9  907.21  4801.4  905.17  4859.2  899.57
  4929.5  888.73  4969.6  887.43  4982.8  885.92  4983.3  885.42  4996.6  885.92
  4997.2  887.71  4998.8  887.71  5003.3  887.71  5013.9  892.66  5045.3  900.68
  5056.3  903.34    5127  909.13    5142  911.87  5173.4  917.44  5211.9  922.38
#Mann= 10 ,-1 , 0
  4447.5     .12       0  4558.2    .035       0  4702.8    .063       0
  4801.4     .12       0  4982.8     .05       0  4996.6     .12       0
  4998.8     .07       0  5045.3    .035       0    5142     .07       0
  5173.4    .035       0
Bank Sta=4982.8,4996.6
XS Rating Curve= 0 ,0
Exp/Cntr=0.3,0.1

Type RM Length L Ch R = 1 ,1014    ,483,483,483
BEGIN DESCRIPTION:
Dry Bear Creek 2.0
END DESCRIPTION:
XS GIS Cut Line= 3
      2213224.98     13844024.99        2212625.       13843675.
      2212424.96     13843725.01
#Sta/Elev= 30
    4316 1011.08  4339.1 1002.48  4345.3  998.08  4366.8  992.06    4404  972.71
  4425.5  967.85  4441.2  959.26    4447  959.29  4462.8  950.98  4468.5   952.9
  4478.1  948.12  4484.3  942.13    4490  942.93  4521.5  930.12  4547.4  923.69
    4627  908.16  4659.5   909.3  4709.6  909.28  4740.6  903.57  4771.6  902.24
  4883.7  895.33  4922.5  892.01  4938.2  885.99  4980.4  883.75  4980.9  883.25
  4994.4  883.75  5002.7  892.75  5007.7  902.09    5124  917.17  5216.8  921.56
#Mann= 9 ,-1 , 0
    4316     .12       0  4441.2    .035       0  4547.4    .063       0
    4627    .035       0  4659.5    .063       0  4771.6     .12       0
  4883.7     .07       0  4980.4     .05       0  4994.4     .07       0
Bank Sta=4980.4,4994.4
XS Rating Curve= 0 ,0
Exp/Cntr=0.3,0.1

Type RM Length L Ch R = 1 ,531     ,424,424,424
BEGIN DESCRIPTION:
Dry Bear Creek 1.0
END DESCRIPTION:
XS GIS Cut Line= 3
        2213225.       13843775.        2212625.       13843225.
      2212425.04       13843225.
#Sta/Elev= 30
  4190.7  983.93  4194.1  983.93  4197.8  980.78  4218.8   978.1  4226.2  972.14
  4240.3  967.84  4346.4   947.1  4360.3  942.84  4374.8  935.29  4399.7  927.76
  4417.3   922.5  4459.9  916.34  4579.4  907.86  4637.8  905.79    4672   903.9
  4679.1  901.45  4709.5  902.48    4778  903.39  4839.5  899.04  4863.1  894.43
  4912.5  889.85  4919.9  886.93  4990.5   884.2    4991   883.7  5004.6   884.2
  5014.6  889.98  5044.6  899.03  5144.6  903.14  5174.6  909.35  5204.6  912.52
#Mann= 8 ,-1 , 0
  4190.7     .12       0  4399.7    .035       0  4579.4    .063       0
  4637.8    .035       0  4709.5    .063       0  4839.5     .12       0
  4990.5     .05       0  5004.6     .12       0
Bank Sta=4990.5,5004.6
XS Rating Curve= 0 ,0
Exp/Cntr=0.3,0.1

Type RM Length L Ch R = 1 ,107     ,0,0,0
BEGIN DESCRIPTION:
X18868
END DESCRIPTION:
XS GIS Cut Line= 3
      2213255.23     13842870.45      2212544.24     13842827.36
      2212345.16      13843260.5
#Sta/Elev= 30
  4368.6  938.37  4371.2  938.37  4374.9  933.65  4441.3   906.7    4469  905.89
  4499.1   900.8  4666.1  898.91  4729.5  898.23  4764.6  900.25  4819.7  896.83
  4863.1  896.39  4873.3  895.65  4879.8  892.54  4909.8  891.75  4939.9  883.78
  4959.9  875.22  4972.9  874.81  4973.4  874.31    4987  874.81    5020  882.84
  5036.1  889.47  5041.1   888.9  5060.2   893.4  5144.4  900.91  5207.8  902.08
  5259.3   907.7  5305.2  907.53  5454.1  914.48  5556.6  915.93  5557.6  915.92
#Mann= 9 ,-1 , 0
  4368.6    .035       0  4441.3     .12       0  4666.1    .035       0
  4764.6    .063       0  4863.1     .07       0  4972.9     .05       0
    4987     .07       0  5060.2    .035       0  5556.6     .12       0
Bank Sta=4972.9,4987
XS Rating Curve= 0 ,0
Exp/Cntr=0.3,0.1

Chan Stop Cuts=-1
Use User Specified Reach Order=0
Composite Channel Slope=5