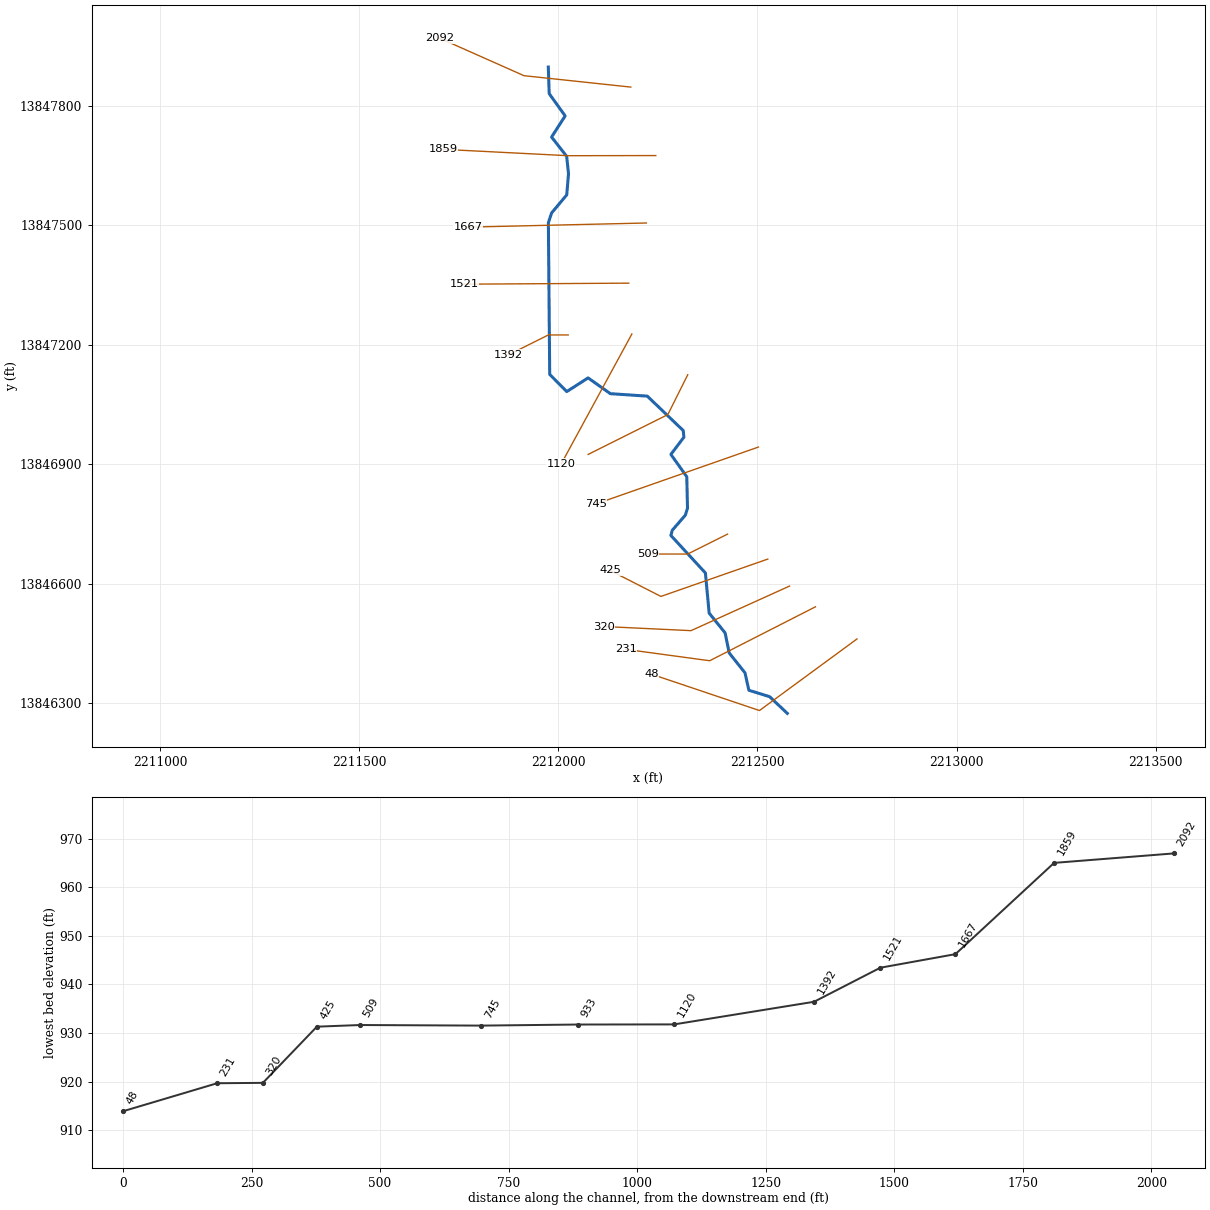
--- Dry Bear Tributary 2.prj (project) ---

Proj Title=Dry Bear Tributary 2 Base Level Engineering
Current Plan=p01
Default Exp/Contr=0.3,0.1
English Units
Geom File=g01
Flow File=f01
Plan File=p01
BEGIN DESCRIPTION:
Dry Bear Tributary 2
END DESCRIPTION:

--- Dry Bear Tributary 2.p01 (plan) ---

Plan Title=Multiple Run
Short Identifier=Multiple
Geom File=g01
Flow File=f01
Subcritical Flow
K Sum by GR= 0
Std Step Tol= 0.01
Critical Tol= 0.01
Num of Std Step Trials= 20
Max Error Tol= 0.3
Flow Tol Ratio= 0.001
Split Flow NTrial= 30
Split Flow Tol= 0.02
Split Flow Ratio= 0.02
Log Output Level= 0
Friction Slope Method= 1
Unsteady Friction Slope Method= 2
Unsteady Bridges Friction Slope Method= 1
Parabolic Critical Depth
Global Vel Dist=  1 , 1 , 1
Global Log Level= 0
CheckData=True
Encroach Param= -1, 0, 0, 0
BEGIN DESCRIPTION:
Multiple Run
END DESCRIPTION:

--- Dry Bear Tributary 2.f01 (steady flow) ---

Flow Title=Multiple
Number of Profiles=7
Profile Names=10-year,25-year,50-year,1pct_min,100-year,1pct_plu,500-year
River Rch & RM= Dry Bear Tributa,Reach-1,2092
     582     947    1282     844    1683    3359    2864
Boundary for River Rch & Prof#=Dry Bear Tributa,Reach-1,1
Up Type=0
Dn Type=3
Dn Slope=0.005
Boundary for River Rch & Prof#=Dry Bear Tributa,Reach-1,2
Up Type=0
Dn Type=3
Dn Slope=0.005
Boundary for River Rch & Prof#=Dry Bear Tributa,Reach-1,3
Up Type=0
Dn Type=3
Dn Slope=0.005
Boundary for River Rch & Prof#=Dry Bear Tributa,Reach-1,4
Up Type=0
Dn Type=3
Dn Slope=0.005
Boundary for River Rch & Prof#=Dry Bear Tributa,Reach-1,5
Up Type=0
Dn Type=3
Dn Slope=0.005
Boundary for River Rch & Prof#=Dry Bear Tributa,Reach-1,6
Up Type=0
Dn Type=3
Dn Slope=0.005
Boundary for River Rch & Prof#=Dry Bear Tributa,Reach-1,7
Up Type=0
Dn Type=3
Dn Slope=0.005

--- Dry Bear Tributary 2.g01 (geometry) ---

Geom Title=Existing Conditions

River Reach=Dry Bear Tributa,Reach-1
Reach XY= 30
      2211975.00     13847897.61      2211977.28     13847830.72
      2212017.32     13847774.92      2211983.28     13847721.78
      2212021.07     13847673.50      2212025.77     13847630.05
      2212021.29     13847576.60      2211983.15     13847531.06
      2211975.21     13847506.73      2211978.54     13847126.00
      2212021.38     13847082.87      2212074.89     13847117.19
      2212130.89     13847077.55      2212223.53     13847071.39
      2212313.77     13846985.03      2212315.41     13846968.35
      2212282.81     13846925.10      2212322.64     13846869.11
      2212324.47     13846790.22      2212319.03     13846772.57
      2212286.34     13846734.85      2212282.81     13846721.59
      2212369.45     13846627.43      2212378.83     13846526.59
      2212418.88     13846477.18      2212429.14     13846426.69
      2212468.78     13846376.86      2212478.59     13846333.05
      2212530.70     13846316.88      2212575.00     13846275.00

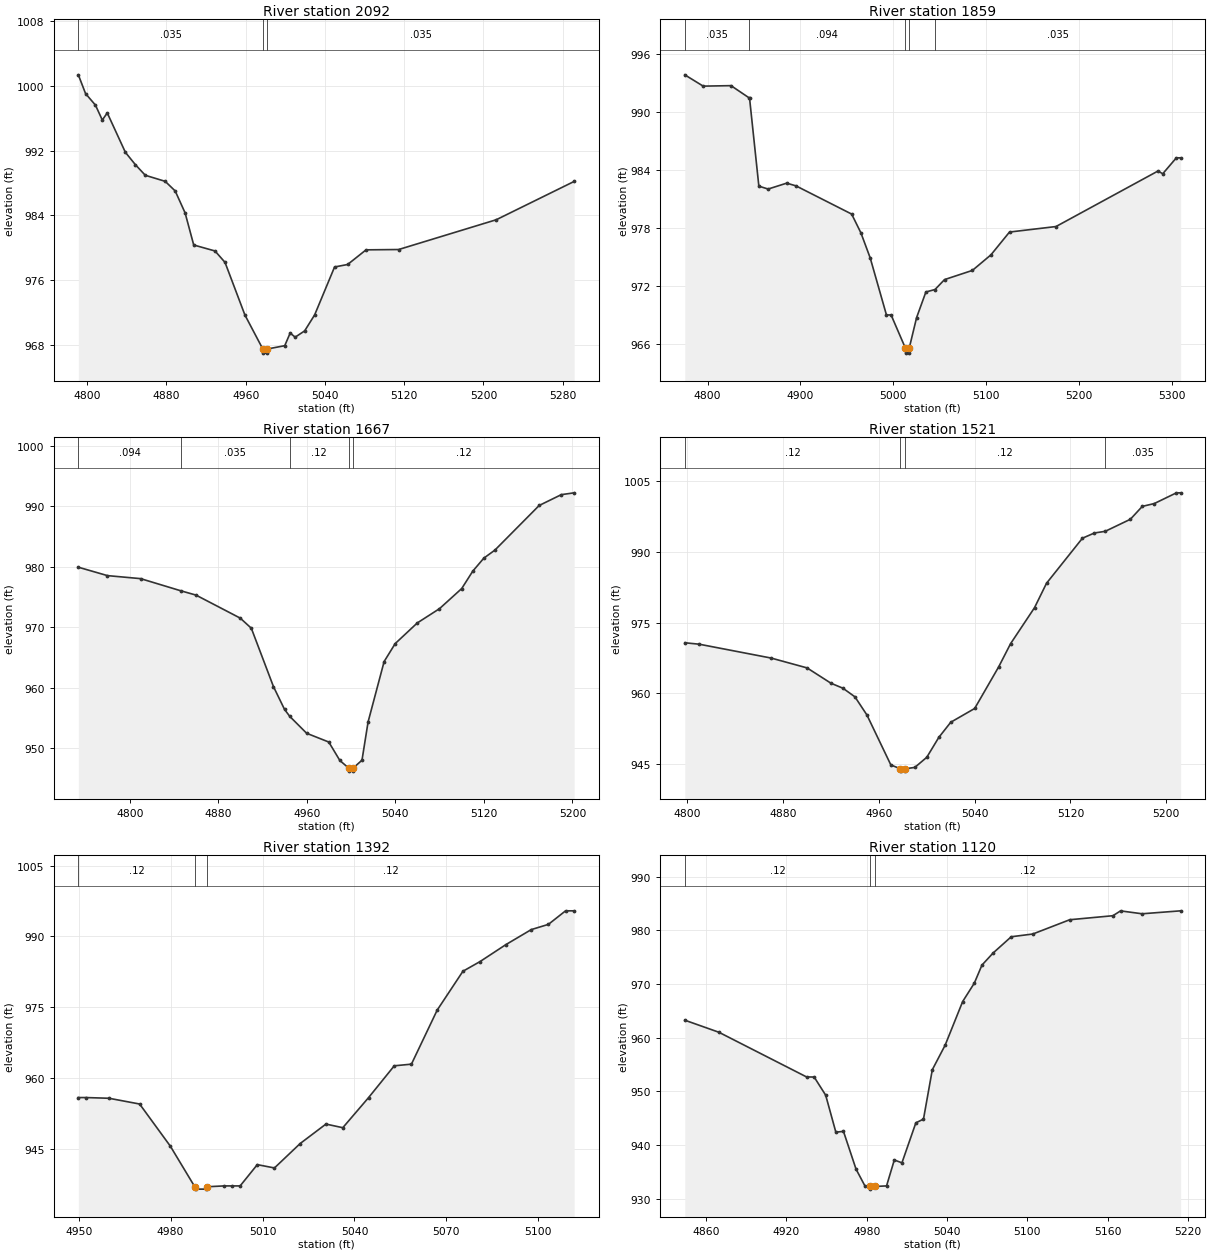
Type RM Length L Ch R = 1,2092,233,233,233
BEGIN DESCRIPTION:
X18898
END DESCRIPTION:
XS GIS Cut Line= 3
      2212182.23     13847847.24      2211914.01     13847875.89
      2211703.05     13847969.65
#Sta/Elev= 30
  4791.0 1001.38  4798.3  999.06  4808.3  997.63  4815.2  995.79  4820.2  996.67
  4838.5  991.80  4848.6  990.27  4858.6  988.96  4878.7  988.21  4888.8  987.02
  4898.8  984.31  4907.5  980.34  4929.0  979.60  4939.1  978.19  4959.2  971.68
  4977.3  967.47  4977.5  966.97  4981.0  966.97  4981.3  967.47  4999.4  967.89
  5004.9  969.46  5009.9  968.94  5019.5  969.72  5029.6  971.70  5049.7  977.62
  5062.9  977.93  5081.5  979.74  5114.4  979.78  5212.9  983.46  5291.6  988.20
#Mann=3,-1,0
  4791.0   0.035       0  4977.3   0.035       0  4981.3   0.035       0
Bank Sta=4977.3,4981.3
Exp/Cntr=0.3,0.1

Type RM Length L Ch R = 1,1859,192,192,192
BEGIN DESCRIPTION:
Dry Bear Tributary 2 4.0
END DESCRIPTION:
XS GIS Cut Line= 3
      2212244.77     13847675.37      2212025.00     13847675.00
      2211710.88     13847690.99
#Sta/Elev= 30
  4775.4  993.82  4795.2  992.65  4825.2  992.70  4844.5  991.45  4845.2  991.39
  4855.2  982.30  4865.2  982.00  4885.2  982.61  4895.2  982.33  4955.2  979.41
  4965.2  977.46  4975.2  974.87  4992.7  968.97  4997.7  968.97  5013.2  965.52
  5013.4  965.02  5016.9  965.02  5017.2  965.52  5025.2  968.70  5035.2  971.35
  5045.0  971.60  5055.3  972.63  5085.3  973.58  5105.3  975.19  5125.3  977.55
  5175.4  978.12  5285.4  983.87  5290.4  983.58  5305.1  985.23  5309.7  985.23
#Mann=5,-1,0
  4775.4   0.035       0  4844.5   0.094       0  5013.2    0.05       0
  5017.2   0.094       0  5045.0   0.035       0
Bank Sta=5013.2,5017.2
Exp/Cntr=0.3,0.1

Type RM Length L Ch R = 1,1667,146,146,146
BEGIN DESCRIPTION:
X18897
END DESCRIPTION:
XS GIS Cut Line= 2
      2212221.26     13847506.10      2211773.38     13847495.68
#Sta/Elev= 30
  4753.5  979.96  4779.8  978.57  4809.8  978.07  4846.1  976.06  4859.8  975.35
  4899.8  971.54  4909.8  969.87  4929.8  960.22  4939.8  956.45  4944.6  955.28
  4959.8  952.50  4979.8  951.05  4989.8  948.00  4997.8  946.74  4998.1  946.24
  5001.6  946.24  5001.8  946.74  5009.8  948.05  5015.3  954.37  5029.8  964.36
  5039.8  967.33  5059.8  970.75  5079.8  973.10  5099.9  976.43  5109.9  979.31
  5119.9  981.46  5129.9  982.79  5169.9  990.17  5189.9  991.96  5201.5  992.26
#Mann=5,-1,0
  4753.5   0.094       0  4846.1   0.035       0  4944.6    0.12       0
  4997.8    0.05       0  5001.8    0.12       0
Bank Sta=4997.8,5001.8
Exp/Cntr=0.3,0.1

Type RM Length L Ch R = 1,1521,129,129,129
BEGIN DESCRIPTION:
X18896
END DESCRIPTION:
XS GIS Cut Line= 2
      2212177.07     13847355.06      2211762.97     13847352.45
#Sta/Elev= 30
  4797.9  970.72  4810.0  970.41  4870.0  967.47  4900.0  965.38  4920.0  962.12
  4930.0  961.06  4940.0  959.23  4950.0  955.38  4970.0  944.76  4978.0  943.95
  4978.2  943.45  4981.7  943.45  4982.0  943.95  4990.0  944.24  5000.0  946.39
  5010.0  950.60  5020.0  953.83  5040.0  956.76  5060.0  965.58  5070.0  970.53
  5090.0  978.18  5100.0  983.36  5130.0  992.93  5140.0  994.04  5149.0  994.39
  5170.0  996.95  5180.0  999.69  5190.0 1000.29  5208.5 1002.57  5212.0 1002.57
#Mann=4,-1,0
  4797.9    0.12       0  4978.0    0.05       0  4982.0    0.12       0
  5149.0   0.035       0
Bank Sta=4978,4982
Exp/Cntr=0.3,0.1

Type RM Length L Ch R = 1,1392,272,272,272
BEGIN DESCRIPTION:
Dry Bear Tributary 2 3.0
END DESCRIPTION:
XS GIS Cut Line= 3
      2212025.01     13847225.00      2211975.00     13847225.00
      2211875.01     13847175.01
#Sta/Elev= 28
  4949.9  955.85  4952.4  955.85  4959.9  955.70  4969.9  954.48  4979.9  945.57
  4987.9  936.94  4988.2  936.44  4991.7  936.44  4991.9  936.94  4997.4  937.12
  4999.9  937.12  5002.7  937.12  5008.3  941.63  5013.9  940.93  5022.3  946.11
  5030.7  950.23  5036.2  949.46  5044.6  955.83  5053.0  962.58  5058.6  962.93
  5067.0  974.38  5075.4  982.62  5081.0  984.68  5089.4  988.26  5097.7  991.45
  5103.3  992.56  5108.9  995.43  5111.7  995.43
#Mann=3,-1,0
  4949.9    0.12       0  4987.9    0.05       0  4991.9    0.12       0
Bank Sta=4987.9,4991.9
Exp/Cntr=0.3,0.1

Type RM Length L Ch R = 1,1120,187,187,187
BEGIN DESCRIPTION:
X18895
END DESCRIPTION:
XS GIS Cut Line= 2
      2212184.86     13847227.48      2212007.76     13846901.93
#Sta/Elev= 30
  4844.0  963.26  4869.5  961.01  4935.0  952.69  4940.7  952.67  4949.3  949.29
  4956.9  942.40  4962.6  942.55  4972.0  935.51  4978.7  932.36  4982.4  932.29
  4982.7  931.79  4986.4  932.29  4994.8  932.39  5000.6  937.22  5006.3  936.69
  5016.7  944.14  5022.4  944.83  5029.0  954.03  5038.6  958.61  5051.7  966.74
  5060.4  970.16  5066.1  973.52  5074.5  975.79  5088.0  978.80  5104.1  979.31
  5131.7  981.97  5164.0  982.72  5169.7  983.62  5185.8  983.08  5214.6  983.63
#Mann=3,-1,0
  4844.0    0.12       0  4982.4    0.05       0  4986.4    0.12       0
Bank Sta=4982.4,4986.4
Exp/Cntr=0.3,0.1

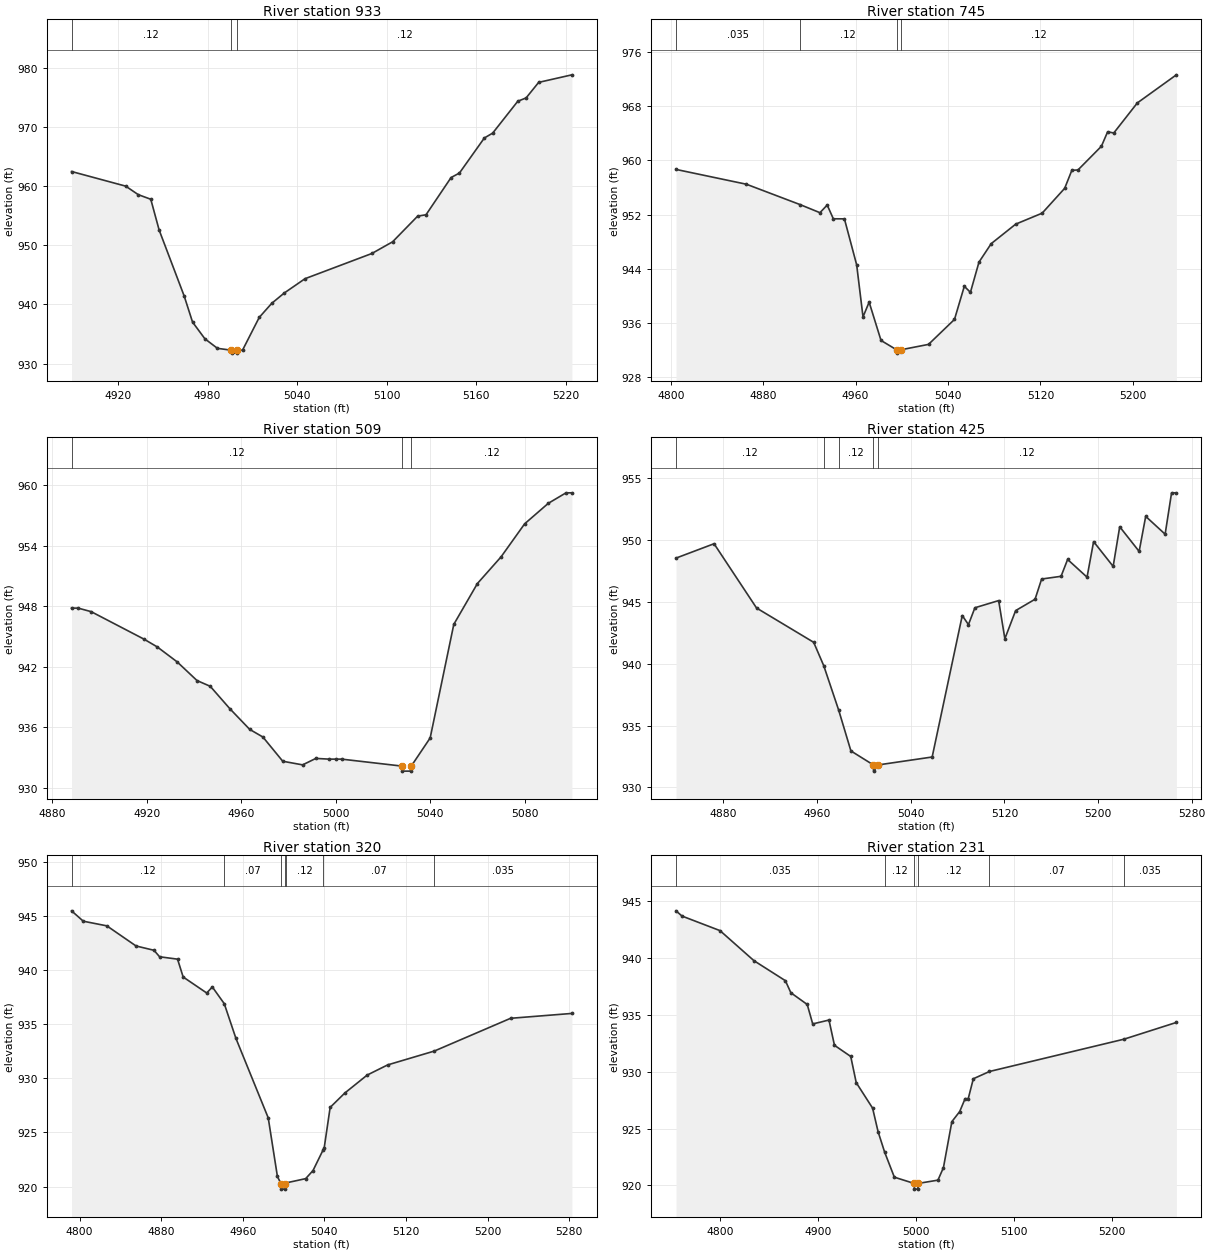
Type RM Length L Ch R = 1,933,188,188,188
BEGIN DESCRIPTION:
Dry Bear Tributary 2 2.0
END DESCRIPTION:
XS GIS Cut Line= 3
      2212325.00     13847125.01      2212275.00     13847025.00
      2212075.02     13846925.01
#Sta/Elev= 30
  4888.8  962.53  4925.1  960.05  4933.5  958.61  4941.9  957.83  4947.5  952.62
  4964.3  941.43  4969.9  937.02  4978.2  934.18  4986.6  932.57  4995.8  932.26
  4996.1  931.76  4999.6  931.76  4999.8  932.26  5003.4  932.26  5014.6  937.81
  5023.0  940.20  5031.4  941.95  5045.3  944.37  5090.1  948.64  5104.0  950.62
  5120.8  954.97  5126.4  955.20  5143.2  961.51  5148.8  962.27  5165.5  968.21
  5171.1  969.04  5187.9  974.43  5193.5  975.00  5201.9  977.63  5224.2  978.91
#Mann=3,-1,0
  4888.8    0.12       0  4995.8    0.05       0  4999.8    0.12       0
Bank Sta=4995.8,4999.8
Exp/Cntr=0.3,0.1

Type RM Length L Ch R = 1,745,236,236,236
BEGIN DESCRIPTION:
X18892
END DESCRIPTION:
XS GIS Cut Line= 2
      2212502.56     13846943.60      2212093.72     13846800.38
#Sta/Elev= 30
  4804.5  958.67  4865.5  956.48  4912.0  953.47  4929.1  952.28  4935.4  953.41
  4940.7  951.38  4950.3  951.37  4960.9  944.58  4966.4  936.89  4971.7  939.07
  4982.0  933.41  4995.4  932.04  4995.7  931.54  4999.4  932.04  5023.1  932.83
  5045.6  936.52  5054.1  941.41  5059.4  940.52  5066.8  944.98  5077.4  947.71
  5098.6  950.59  5121.5  952.21  5141.0  955.88  5147.2  958.54  5152.5  958.59
  5172.8  962.09  5178.2  964.23  5183.5  964.05  5203.9  968.49  5237.7  972.64
#Mann=4,-1,0
  4804.5   0.035       0  4912.0    0.12       0  4995.4    0.05       0
  4999.4    0.12       0
Bank Sta=4995.4,4999.4
Exp/Cntr=0.3,0.1

Type RM Length L Ch R = 1,509,84,84,84
BEGIN DESCRIPTION:
Dry Bear Tributary 2 1.0
END DESCRIPTION:
XS GIS Cut Line= 3
      2212424.96     13846724.98      2212325.00     13846675.00
      2212224.96     13846675.00
#Sta/Elev= 29
  4888.1  947.82  4890.9  947.82  4896.4  947.47  4918.8  944.74  4924.4  943.97
  4932.8  942.49  4941.2  940.64  4946.8  940.07  4955.1  937.85  4963.5  935.80
  4969.1  935.04  4977.5  932.64  4985.9  932.28  4991.5  932.92  4997.1  932.85
  4999.9  932.85  5002.4  932.85  5027.9  932.16  5028.1  931.66  5031.6  931.66
  5031.9  932.16  5039.9  934.95  5049.9  946.21  5059.9  950.26  5069.9  952.90
  5079.9  956.18  5089.9  958.21  5097.4  959.25  5099.9  959.25
#Mann=3,-1,0
  4888.1    0.12       0  5027.9    0.05       0  5031.9    0.12       0
Bank Sta=5027.9,5031.9
Exp/Cntr=0.3,0.1

Type RM Length L Ch R = 1,425,105,105,105
BEGIN DESCRIPTION:
X18893
END DESCRIPTION:
XS GIS Cut Line= 3
      2212526.01     13846662.35      2212257.76     13846568.60
      2212130.17     13846633.69
#Sta/Elev= 30
  4839.5  948.52  4872.0  949.68  4908.3  944.49  4957.1  941.72  4965.7  939.83
  4978.5  936.23  4988.9  932.95  5008.1  931.82  5008.3  931.32  5012.1  931.82
  5058.3  932.46  5084.0  943.88  5089.3  943.15  5094.8  944.51  5115.1  945.09
  5120.4  942.01  5129.6  944.28  5146.2  945.20  5151.8  946.83  5168.4  947.05
  5174.0  948.41  5190.6  946.98  5196.2  949.85  5212.9  947.85  5218.5  951.05
  5235.1  949.06  5240.7  951.89  5257.3  950.45  5262.8  953.79  5266.9  953.79
#Mann=5,-1,0
  4839.5    0.12       0  4965.7    0.07       0  4978.5    0.12       0
  5008.1    0.05       0  5012.1    0.12       0
Bank Sta=5008.1,5012.1
Exp/Cntr=0.3,0.1

Type RM Length L Ch R = 1,320,89,89,89
BEGIN DESCRIPTION:
X18894
END DESCRIPTION:
XS GIS Cut Line= 3
      2212580.66     13846594.63      2212333.28     13846482.66
      2212114.57     13846493.07
#Sta/Elev= 30
  4792.2  945.50  4803.7  944.54  4826.8  944.11  4855.4  942.25  4873.0  941.85
  4878.5  941.25  4896.1  941.03  4901.6  939.38  4924.7  937.90  4930.2  938.46
  4941.9  936.91  4953.3  933.71  4985.0  926.35  4994.0  920.93  4997.5  920.26
  4997.7  919.76  5001.2  919.76  5001.5  920.26  5002.7  920.34  5021.7  920.73
  5028.9  921.48  5038.6  923.35  5039.9  923.60  5045.7  927.32  5060.1  928.65
  5082.0  930.31  5102.1  931.25  5147.8  932.53  5222.6  935.56  5282.7  936.01
#Mann=7,-1,0
  4792.2    0.12       0  4941.9    0.07       0  4997.5    0.05       0
  5001.5    0.07       0  5002.7    0.12       0  5038.6    0.07       0
  5147.8   0.035       0
Bank Sta=4997.5,5001.5
Exp/Cntr=0.3,0.1

Type RM Length L Ch R = 1,231,183,183,183
BEGIN DESCRIPTION:
X18891
END DESCRIPTION:
XS GIS Cut Line= 3
      2212645.79     13846542.56      2212380.16     13846407.14
      2212169.65     13846435.73
#Sta/Elev= 30
  4755.1  944.14  4761.2  943.68  4800.0  942.40  4834.6  939.76  4866.7  938.00
  4872.3  936.94  4889.0  935.91  4894.6  934.20  4911.2  934.54  4916.8  932.32
  4933.4  931.34  4939.0  929.04  4955.7  926.80  4961.3  924.73  4968.0  922.93
  4977.9  920.73  4998.1  920.18  4998.4  919.68  5001.9  919.68  5002.1  920.18
  5022.4  920.47  5028.0  921.57  5036.6  925.61  5044.6  926.50  5050.1  927.63
  5053.3  927.63  5058.5  929.38  5075.0  930.02  5212.3  932.86  5265.7  934.33
#Mann=6,-1,0
  4755.1   0.035       0  4968.0    0.12       0  4998.1    0.05       0
  5002.1    0.12       0  5075.0    0.07       0  5212.3   0.035       0
Bank Sta=4998.1,5002.1
Exp/Cntr=0.3,0.1

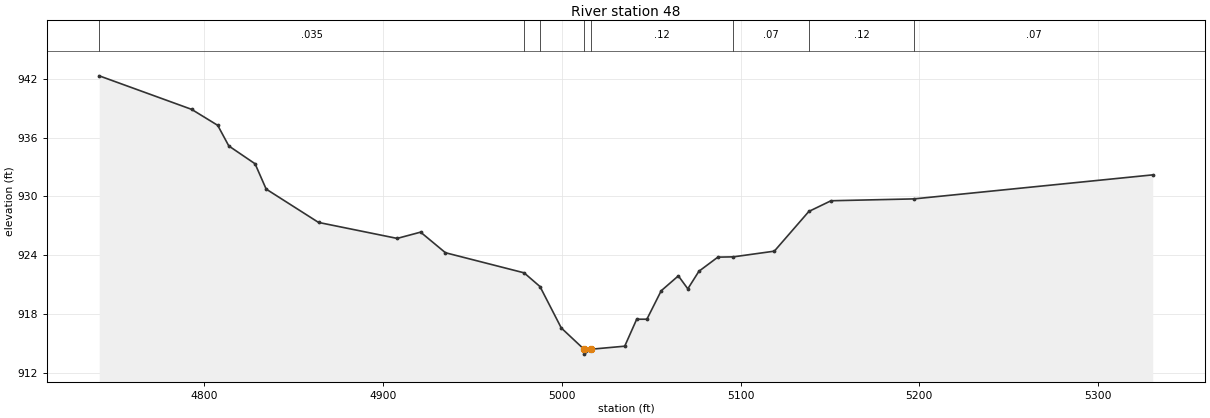
Type RM Length L Ch R = 1,48,0,0,0
BEGIN DESCRIPTION:
X18890
END DESCRIPTION:
XS GIS Cut Line= 3
      2212749.96     13846461.84      2212505.16     13846282.14
      2212234.36     13846373.27
#Sta/Elev= 30
  4741.2  942.30  4792.9  938.88  4807.5  937.25  4813.7  935.15  4828.4  933.33
  4834.6  930.75  4863.9  927.35  4907.9  925.72  4921.0  926.36  4934.9  924.26
  4978.9  922.21  4987.8  920.81  4999.7  916.59  5012.4  914.42  5012.6  913.92
  5016.4  914.42  5035.2  914.73  5041.9  917.48  5047.6  917.48  5055.6  920.38
  5065.2  921.90  5070.5  920.58  5076.7  922.37  5087.3  923.81  5096.0  923.84
  5118.9  924.42  5138.2  928.47  5150.6  929.56  5197.0  929.75  5330.6  932.20
#Mann=8,-1,0
  4741.2   0.035       0  4978.9   0.094       0  4987.8    0.12       0
  5012.4    0.05       0  5016.4    0.12       0  5096.0    0.07       0
  5138.2    0.12       0  5197.0    0.07       0
Bank Sta=5012.4,5016.4
Exp/Cntr=0.3,0.1

Chan Stop Cuts=-1