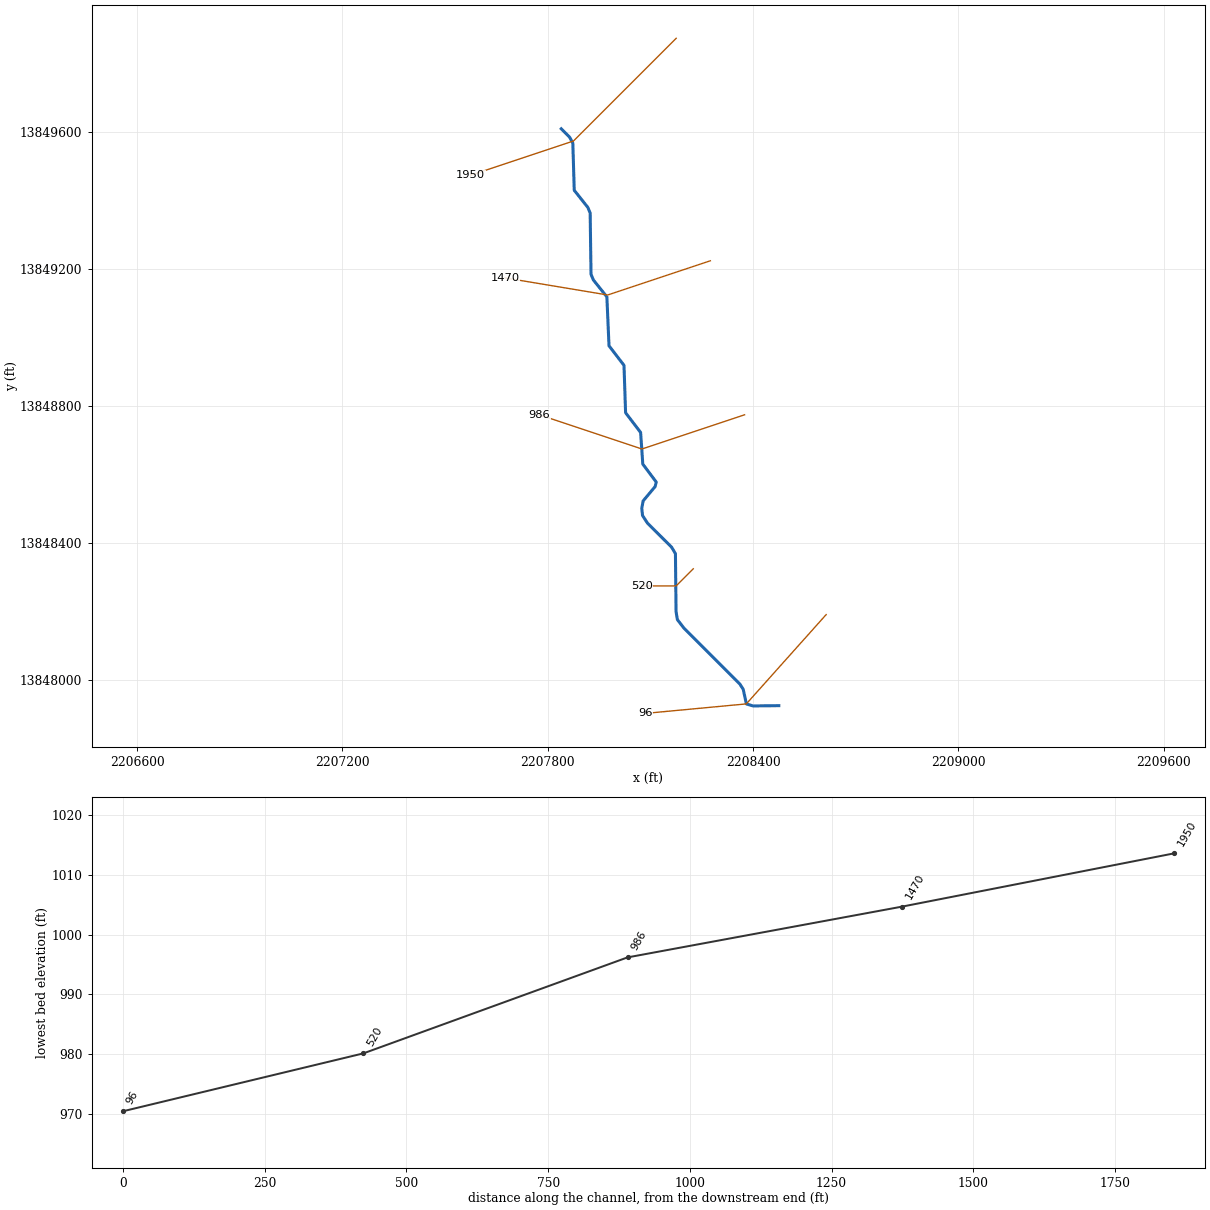
--- Dry Bear Tributary 5.prj (project) ---

Proj Title=Dry Bear Tributary 5 Base Level Engineering
Current Plan=p01
Default Exp/Contr=0.3,0.1
English Units
Geom File=g01
Flow File=f01
Plan File=p01
BEGIN DESCRIPTION:
Dry Bear Tributary 5
END DESCRIPTION:

--- Dry Bear Tributary 5.p01 (plan) ---

Plan Title=Multiple Run
Short Identifier=Multiple
Geom File=g01
Flow File=f01
Subcritical Flow
K Sum by GR= 0
Std Step Tol= 0.01
Critical Tol= 0.01
Num of Std Step Trials= 20
Max Error Tol= 0.3
Flow Tol Ratio= 0.001
Split Flow NTrial= 30
Split Flow Tol= 0.02
Split Flow Ratio= 0.02
Log Output Level= 0
Friction Slope Method= 1
Unsteady Friction Slope Method= 2
Unsteady Bridges Friction Slope Method= 1
Parabolic Critical Depth
Global Vel Dist=  1 , 1 , 1
Global Log Level= 0
CheckData=True
Encroach Param= -1, 0, 0, 0
BEGIN DESCRIPTION:
Multiple Run
END DESCRIPTION:

--- Dry Bear Tributary 5.f01 (steady flow) ---

Flow Title=Multiple
Number of Profiles=7
Profile Names=10-year,25-year,50-year,1pct_min,100-year,1pct_plu,500-year
River Rch & RM= Dry Bear Tributa,Reach-1,1950
     680    1116    1519    1004    2002    3995    3438
Boundary for River Rch & Prof#=Dry Bear Tributa,Reach-1,1
Up Type=0
Dn Type=3
Dn Slope=0.005
Boundary for River Rch & Prof#=Dry Bear Tributa,Reach-1,2
Up Type=0
Dn Type=3
Dn Slope=0.005
Boundary for River Rch & Prof#=Dry Bear Tributa,Reach-1,3
Up Type=0
Dn Type=3
Dn Slope=0.005
Boundary for River Rch & Prof#=Dry Bear Tributa,Reach-1,4
Up Type=0
Dn Type=3
Dn Slope=0.005
Boundary for River Rch & Prof#=Dry Bear Tributa,Reach-1,5
Up Type=0
Dn Type=3
Dn Slope=0.005
Boundary for River Rch & Prof#=Dry Bear Tributa,Reach-1,6
Up Type=0
Dn Type=3
Dn Slope=0.005
Boundary for River Rch & Prof#=Dry Bear Tributa,Reach-1,7
Up Type=0
Dn Type=3
Dn Slope=0.005

--- Dry Bear Tributary 5.g01 (geometry) ---

Geom Title=Existing Conditions

River Reach=Dry Bear Tributa,Reach-1
Reach XY= 30
      2207839.35     13849610.65      2207863.37     13849586.54
      2207873.08     13849569.20      2207877.26     13849430.94
      2207916.86     13849381.06      2207923.78     13849364.49
      2207926.22     13849185.51      2207933.14     13849168.94
      2207972.61     13849119.47      2207978.79     13848976.57
      2208022.61     13848919.47      2208027.27     13848780.94
      2208071.15     13848723.40      2208077.55     13848630.89
      2208116.90     13848578.29      2208113.47     13848565.07
      2208078.58     13848523.35      2208074.64     13848502.20
      2208076.78     13848480.64      2208091.26     13848458.34
      2208161.60     13848388.31      2208172.93     13848369.14
      2208174.71     13848199.88      2208178.54     13848176.46
      2208197.86     13848151.47      2208361.29     13847987.97
      2208370.91     13847972.96      2208380.31     13847930.00
      2208399.44     13847924.27      2208475.00     13847925.00

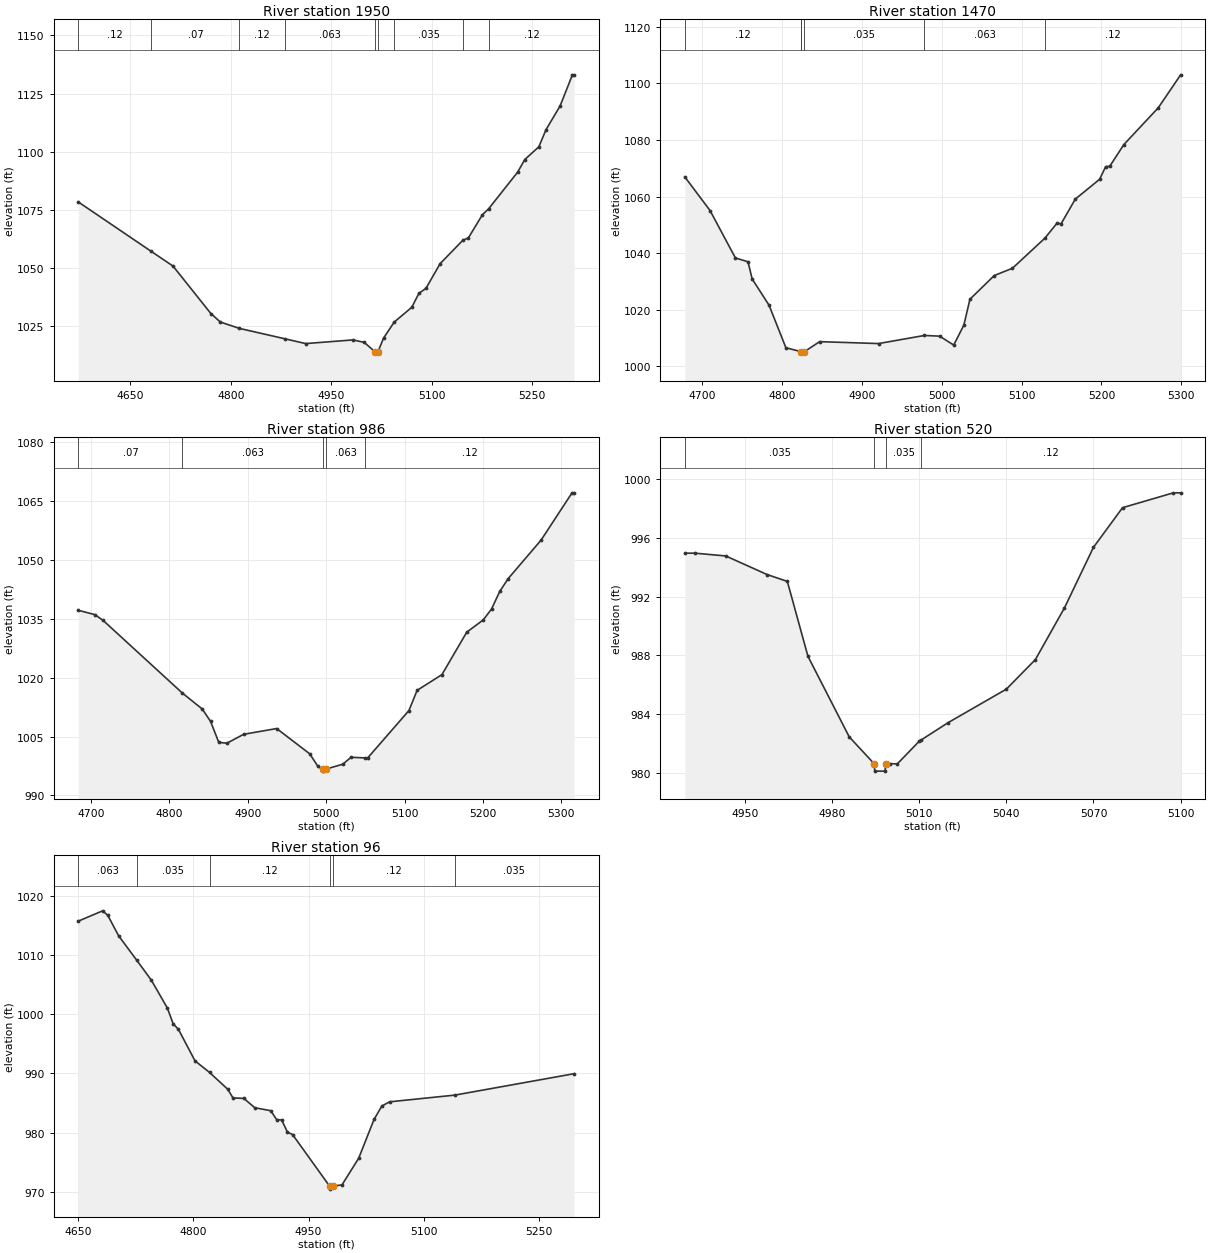
Type RM Length L Ch R = 1,1950,480,480,480
BEGIN DESCRIPTION:
Dry Bear Tributary 5 4.0
END DESCRIPTION:
XS GIS Cut Line= 3
      2208174.97     13849874.97      2207875.00     13849575.00
      2207575.05     13849475.02
#Sta/Elev= 30
  4572.2 1078.45  4681.3 1057.19  4713.6 1050.93  4770.1 1030.56  4784.3 1026.90
  4812.7 1024.18  4880.3 1019.74  4911.6 1017.66  4982.3 1019.23  4999.1 1018.18
  5015.5 1014.06  5015.8 1013.56  5019.5 1014.06  5028.0 1020.02  5043.9 1026.88
  5070.2 1033.27  5080.7 1039.20  5091.3 1041.37  5112.4 1051.95  5146.7 1062.11
  5154.5 1062.96  5175.6 1072.97  5185.0 1075.56  5228.3 1091.29  5238.9 1096.68
  5259.9 1102.14  5270.5 1109.44  5291.6 1119.67  5310.0 1133.03  5312.6 1133.03
#Mann=9,-1,0
  4572.2    0.12       0  4681.3    0.07       0  4812.7    0.12       0
  4880.3   0.063       0  5015.5    0.05       0  5019.5   0.063       0
  5043.9   0.035       0  5146.7    0.07       0  5185.0    0.12       0
Bank Sta=5015.5,5019.5
Exp/Cntr=0.3,0.1

Type RM Length L Ch R = 1,1470,484,484,484
BEGIN DESCRIPTION:
Dry Bear Tributary 5 3.0
END DESCRIPTION:
XS GIS Cut Line= 3
      2208275.00     13849225.00      2207975.00     13849125.00
      2207674.97     13849175.00
#Sta/Elev= 30
  4678.7 1066.97  4710.3 1055.06  4742.0 1038.32  4757.8 1036.95  4763.0 1030.87
  4784.1 1021.61  4805.2 1006.56  4824.1 1005.18  4824.3 1005.16  4824.5 1004.66
  4828.3 1005.16  4847.4 1008.72  4921.1 1008.04  4978.6 1010.91  4997.5 1010.66
  5015.2 1007.51  5027.9 1014.58  5035.5 1023.73  5065.9 1032.08  5088.7 1034.67
  5129.3 1045.31  5144.5 1050.63  5149.5 1050.36  5167.3 1059.11  5197.7 1066.12
  5205.3 1070.59  5210.4 1070.71  5228.1 1078.41  5271.2 1091.42  5299.1 1103.05
#Mann=6,-1,0
  4678.7    0.12       0  4824.1   0.035       0  4824.3    0.05       0
  4828.3   0.035       0  4978.6   0.063       0  5129.3    0.12       0
Bank Sta=4824.3,4828.3
Exp/Cntr=0.3,0.1

Type RM Length L Ch R = 1,986,466,466,466
BEGIN DESCRIPTION:
Dry Bear Tributary 5 2.0
END DESCRIPTION:
XS GIS Cut Line= 3
      2208375.03     13848775.01      2208075.00     13848675.00
      2207774.98     13848775.01
#Sta/Elev= 30
  4683.8 1037.19  4704.9 1036.09  4715.5 1034.60  4816.6 1016.07  4841.9 1012.02
  4852.5 1008.86  4863.0 1003.49  4873.6 1003.32  4894.6 1005.57  4936.8 1007.04
  4979.0 1000.59  4989.5  997.37  4995.4  996.68  4995.7  996.18  4999.4  996.68
  5021.1  997.94  5031.7  999.71  5049.7  999.55  5052.8  999.52  5105.5 1011.62
  5116.0 1016.79  5147.6 1020.78  5179.3 1031.62  5200.3 1034.74  5210.9 1037.52
  5221.4 1042.01  5232.0 1045.24  5274.1 1055.09  5313.6 1067.15  5316.3 1067.15
#Mann=5,-1,0
  4683.8    0.07       0  4816.6   0.063       0  4995.4    0.05       0
  4999.4   0.063       0  5049.7    0.12       0
Bank Sta=4995.4,4999.4
Exp/Cntr=0.3,0.1

Type RM Length L Ch R = 1,520,424,424,424
BEGIN DESCRIPTION:
Dry Bear Tributary 5 1.0
END DESCRIPTION:
XS GIS Cut Line= 3
      2208224.99     13848324.99      2208175.00     13848275.00
      2208075.00     13848275.00
#Sta/Elev= 23
  4929.3  994.95  4932.8  994.95  4943.4  994.76  4957.6  993.50  4964.6  993.03
  4971.7  987.94  4985.9  982.47  4994.5  980.64  4994.7  980.14  4998.2  980.14
  4998.5  980.64  5000.0  980.64  5002.5  980.64  5010.0  982.17  5010.7  982.26
  5020.0  983.44  5040.0  985.71  5050.0  987.72  5060.0  991.23  5070.0  995.35
  5080.0  998.04  5097.5  999.05  5100.0  999.05
#Mann=4,-1,0
  4929.3   0.035       0  4994.5   0.035       0  4998.5   0.035       0
  5010.7    0.12       0
Bank Sta=4994.5,4998.5
Exp/Cntr=0.3,0.1

Type RM Length L Ch R = 1,96,0,0,0
BEGIN DESCRIPTION:
Dry Bear Tributary 5 0.5
END DESCRIPTION:
XS GIS Cut Line= 3
      2208613.26     13848191.04      2208380.07     13847930.17
      2208085.68     13847902.48
#Sta/Elev= 30
  4650.2 1015.69  4681.8 1017.43  4688.5 1016.68  4702.7 1013.21  4726.1 1009.12
  4745.3 1005.72  4766.2 1001.01  4773.7  998.35  4780.4  997.47  4802.1  992.12
  4821.1  990.15  4844.8  987.32  4851.5  985.86  4865.7  985.78  4879.9  984.21
  4900.8  983.70  4908.3  982.21  4915.0  982.13  4922.5  980.09  4929.2  979.67
  4977.4  970.97  4977.6  970.47  4981.4  970.97  4993.5  971.19  5015.2  975.67
  5035.3  982.25  5045.4  984.49  5055.4  985.20  5140.2  986.33  5295.8  989.95
#Mann=6,-1,0
  4650.2   0.063       0  4726.1   0.035       0  4821.1    0.12       0
  4977.4    0.05       0  4981.4    0.12       0  5140.2   0.035       0
Bank Sta=4977.4,4981.4
Exp/Cntr=0.3,0.1

Chan Stop Cuts=-1