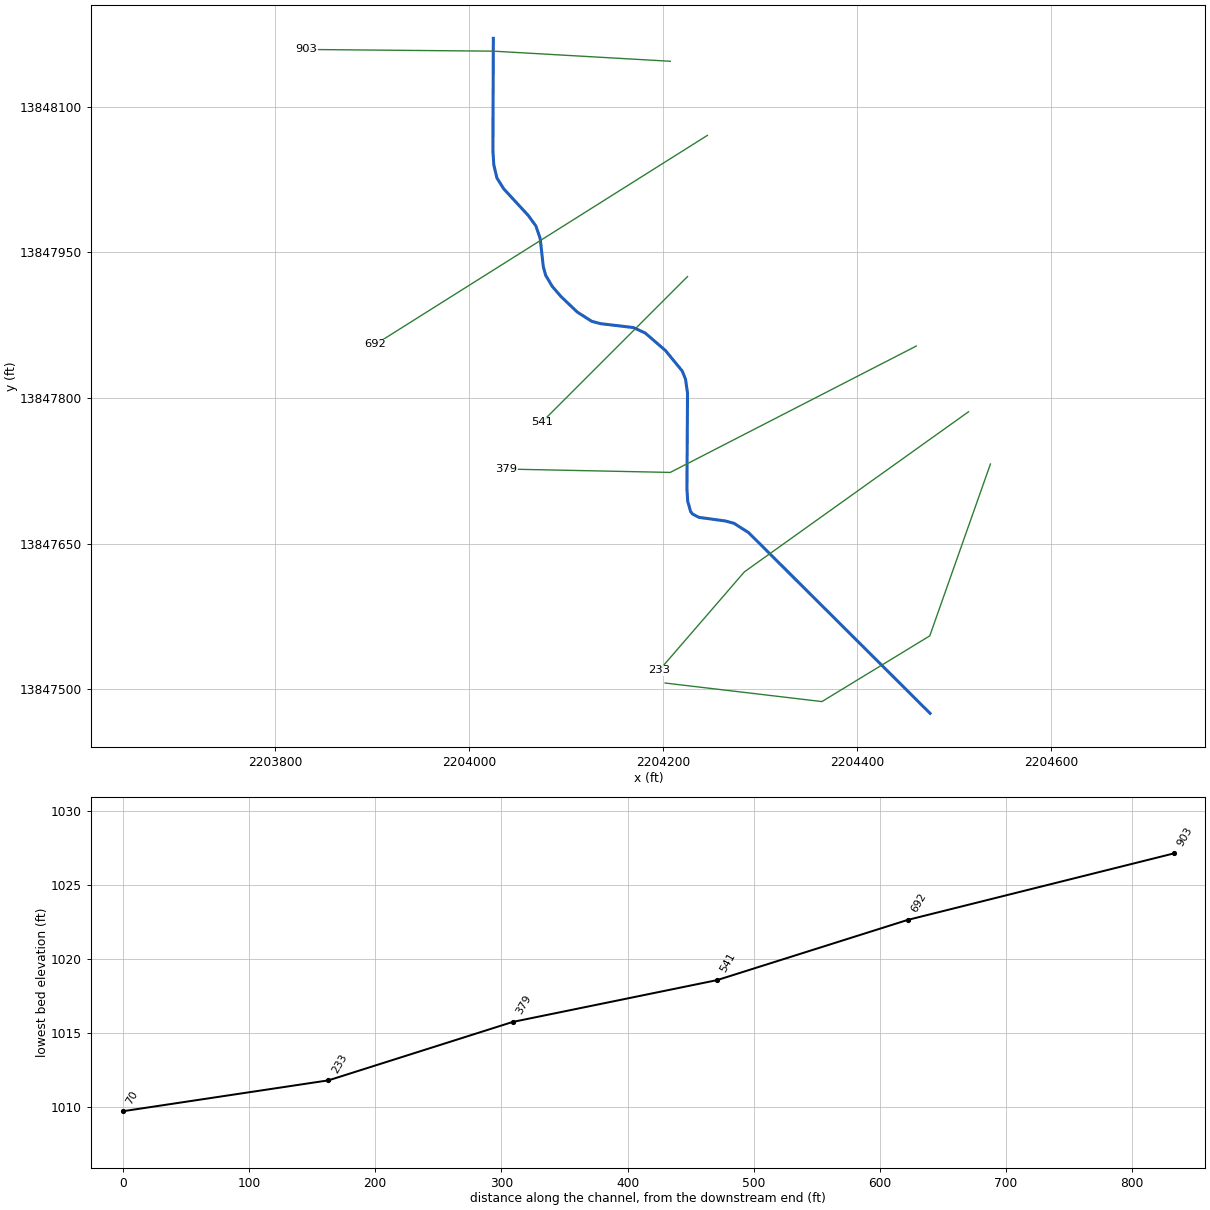
--- Dry Bear Tributary 7.prj (project) ---

Proj Title=Dry Bear Tributary 7 Base Level Engineering
Current Plan=p01
Default Exp/Contr=0.3,0.1
English Units
Geom File=g01
Flow File=f01
Plan File=p01
Y Axis Title=Elevation
X Axis Title(PF)=Main Channel Distance
X Axis Title(XS)=Station
BEGIN DESCRIPTION:
Dry Bear Tributary 7
END DESCRIPTION:
DSS Export Rating Curves= 0
DSS Export Rating Curve Sorted= 0
DSS Export Volume Flow Curves= 0
DXF OffsetX= 0
DXF OffsetY= 0
DXF ScaleX= 1
DXF ScaleY= 10

--- Dry Bear Tributary 7.p01 (plan) ---

Plan Title=Multiple Run
Short Identifier=Multiple
Geom File=g01
Flow File=f01
Subcritical Flow
K Sum by GR= 0
Std Step Tol= 0.01
Critical Tol= 0.01
Num of Std Step Trials= 20
Max Error Tol= 0.3
Flow Tol Ratio= 0.001
Split Flow NTrial= 30
Split Flow Tol= 0.02
Split Flow Ratio= 0.02
Log Output Level= 0
Friction Slope Method= 1
Unsteady Friction Slope Method= 2
Unsteady Bridges Friction Slope Method= 1
Parabolic Critical Depth
Global Vel Dist=  1 , 1 , 1
Global Log Level= 0
CheckData=True
Encroach Param= -1, 0, 0, 0
BEGIN DESCRIPTION:
Multiple Run
END DESCRIPTION:

--- Dry Bear Tributary 7.f01 (steady flow) ---

Flow Title=Multiple
Number of Profiles=7
Profile Names=10-year,25-year,50-year,1pct_min,100-year,1pct_plu,500-year
River Rch & RM= Dry Bear Tributa,Reach-1,903
     294     454     595     380     757    1511    1209
Boundary for River Rch & Prof#=Dry Bear Tributa,Reach-1,1
Up Type=0
Dn Type=3
Dn Slope=0.005
Boundary for River Rch & Prof#=Dry Bear Tributa,Reach-1,2
Up Type=0
Dn Type=3
Dn Slope=0.005
Boundary for River Rch & Prof#=Dry Bear Tributa,Reach-1,3
Up Type=0
Dn Type=3
Dn Slope=0.005
Boundary for River Rch & Prof#=Dry Bear Tributa,Reach-1,4
Up Type=0
Dn Type=3
Dn Slope=0.005
Boundary for River Rch & Prof#=Dry Bear Tributa,Reach-1,5
Up Type=0
Dn Type=3
Dn Slope=0.005
Boundary for River Rch & Prof#=Dry Bear Tributa,Reach-1,6
Up Type=0
Dn Type=3
Dn Slope=0.005
Boundary for River Rch & Prof#=Dry Bear Tributa,Reach-1,7
Up Type=0
Dn Type=3
Dn Slope=0.005

--- Dry Bear Tributary 7.g01 (geometry) ---

Geom Title=Existing Conditions
Program Version=4.10

River Reach=Dry Bear Tributa,Reach-1
Reach XY= 30
        2204025.      13848170.5      2204024.55     13848054.81
      2204025.44     13848040.18      2204028.71     13848026.54
      2204035.79     13848015.32      2204060.95     13847988.03
      2204068.85     13847977.15      2204073.26     13847964.24
      2204076.44     13847935.47      2204078.86     13847926.42
      2204085.63       13847915.      2204094.63     13847904.53
      2204111.45     13847888.49      2204126.46      13847878.9
      2204135.54     13847876.51      2204169.12     13847872.54
      2204181.36     13847866.97      2204202.29      13847848.9
      2204219.63     13847827.69        2204223.     13847819.31
      2204225.06     13847805.09      2204224.45     13847706.35
      2204225.25     13847693.58      2204228.24     13847683.01
      2204230.19     13847680.44      2204236.69     13847676.98
      2204263.86     13847673.25      2204272.91     13847670.84
      2204287.95     13847661.26        2204475.       13847475.

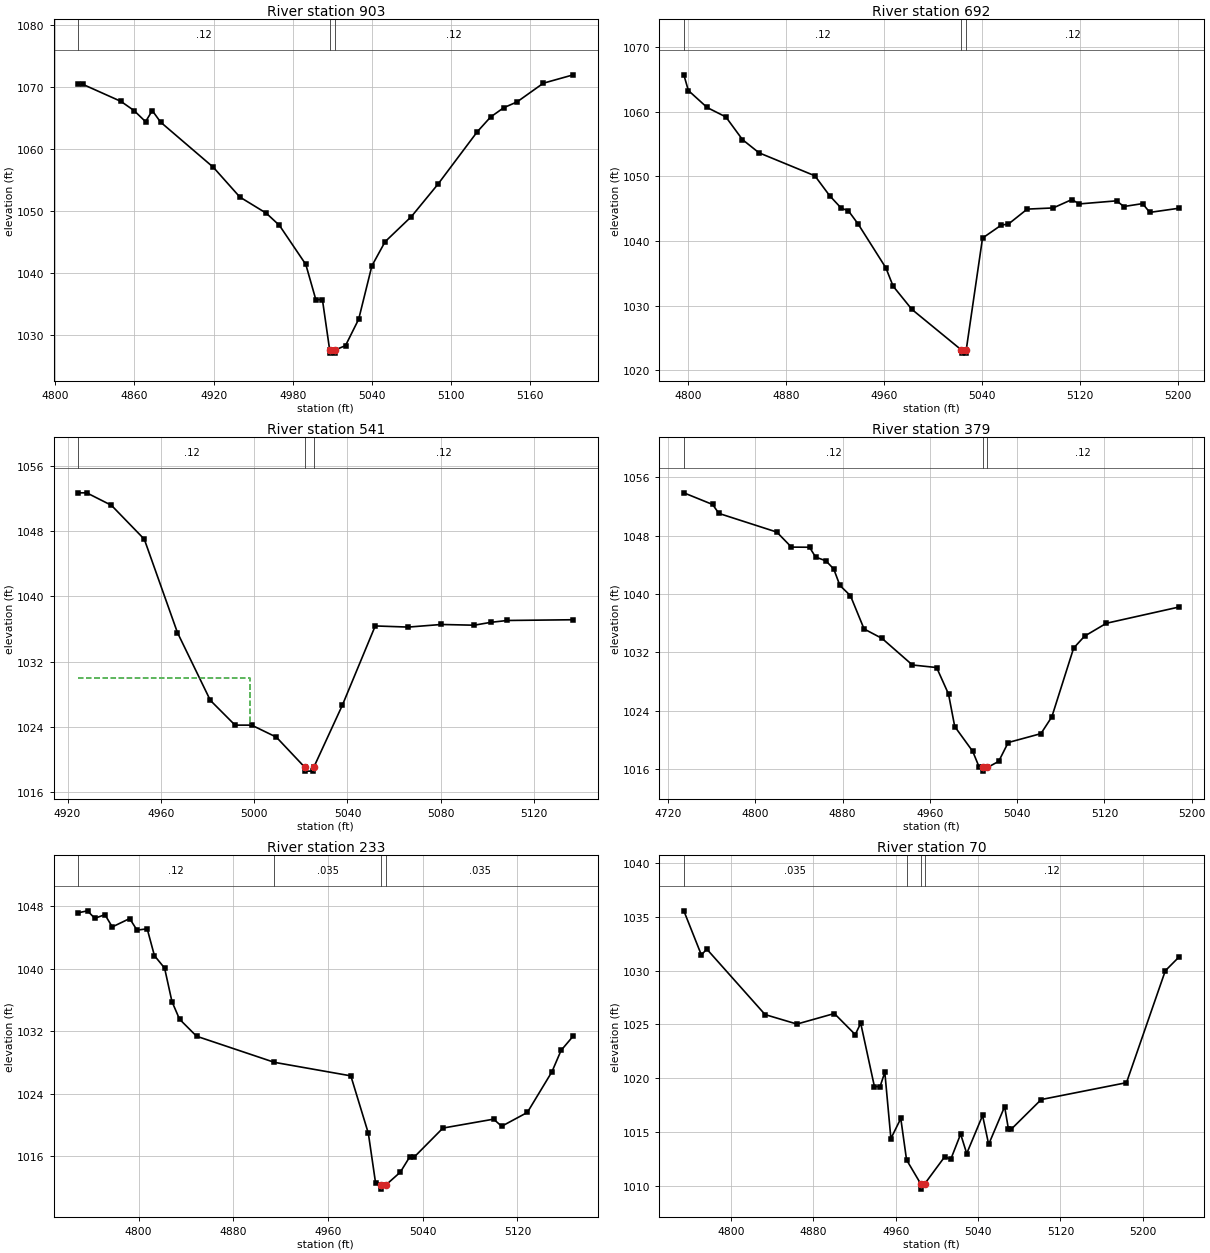
Type RM Length L Ch R = 1 ,903     ,211,211,211
BEGIN DESCRIPTION:
Dry Bear Tributary 710512
END DESCRIPTION:
XS GIS Cut Line= 3
      2204207.27     13848146.88        2204025.     13848157.29
      2203832.27     13848159.03
#Sta/Elev= 30
  4817.4 1070.48    4821 1070.48  4849.7 1067.75  4859.7 1066.26  4868.4 1064.47
  4873.5 1066.26  4879.8  1064.4  4919.8 1057.11  4939.9 1052.31  4959.9 1049.71
  4969.9 1047.74  4989.9 1041.44  4997.5 1035.76  5002.5 1035.76    5008 1027.63
  5008.2 1027.13  5011.7 1027.13    5012 1027.63    5020 1028.34    5030 1032.61
    5040 1041.21    5050  1045.1    5070 1049.17    5090 1054.36    5120 1062.87
    5130 1065.22    5140 1066.73    5150 1067.65    5170 1070.68  5192.7 1072.03
#Mann= 3 ,-1 , 0
  4817.4     .12       0    5008     .05       0    5012     .12       0
Bank Sta=5008,5012
XS Rating Curve= 0 ,0
Exp/Cntr=0.3,0.1

Type RM Length L Ch R = 1 ,692     ,151,151,151
BEGIN DESCRIPTION:
Dry Bear Tributary 710511
END DESCRIPTION:
XS GIS Cut Line= 2
      2204245.53     13848070.51      2203903.45     13847855.19
#Sta/Elev= 30
  4796.8 1065.74  4800.5 1063.31  4815.8 1060.68  4831.1 1059.22  4844.7  1055.7
  4858.2 1053.66  4903.8  1050.1  4915.9 1047.01  4925.3 1045.09  4931.2 1044.67
  4939.2 1042.61  4961.8 1035.83  4967.7    1033    4983 1029.41  5023.4 1023.13
  5023.7 1022.63  5027.2 1022.63  5027.4 1023.13  5040.7 1040.45    5056 1042.46
  5061.9 1042.63  5077.2 1044.94  5098.4 1045.12  5113.7 1046.42  5119.6 1045.74
  5150.2 1046.22  5156.1 1045.34  5171.4 1045.79  5177.3 1044.43    5201 1045.07
#Mann= 3 ,-1 , 0
  4796.8     .12       0  5023.4     .05       0  5027.4     .12       0
Bank Sta=5023.4,5027.4
XS Rating Curve= 0 ,0
Exp/Cntr=0.3,0.1

Type RM Length L Ch R = 1 ,541     ,162,162,162
BEGIN DESCRIPTION:
Dry Bear Tributary 73441
END DESCRIPTION:
XS GIS Cut Line= 3
      2204225.02     13847925.02        2204175.       13847875.
      2204074.98     13847774.98
#Sta/Elev= 21
  4924.6 1052.68  4928.2 1052.68  4938.8 1051.15  4952.9 1046.99  4967.1 1035.55
  4981.2 1027.24  4991.8  1024.2  4998.9  1024.2  5009.5 1022.73  5021.6 1019.06
  5021.9 1018.56  5025.4 1018.56  5025.6 1019.06  5037.8 1026.64  5051.9 1036.36
  5066.1 1036.22  5080.2 1036.54  5094.3 1036.45  5101.4  1036.8  5108.5 1037.03
  5136.8 1037.12
#Mann= 3 ,-1 , 0
  4924.6     .12       0  5021.6     .05       0  5025.6     .12       0
#XS Ineff= 2 , 0
       0    4998    1030               0
Permanent Ineff=
       F       F
Bank Sta=5021.6,5025.6
XS Rating Curve= 0 ,0
Exp/Cntr=0.3,0.1

Type RM Length L Ch R = 1 ,379     ,146,146,146
BEGIN DESCRIPTION:
Dry Bear Tributary 710510
END DESCRIPTION:
XS GIS Cut Line= 3
      2204460.78     13847853.48      2204207.29     13847723.26
      2204038.61     13847726.71
#Sta/Elev= 30
  4734.5 1053.88  4760.9 1052.28  4766.6 1051.06  4819.7  1048.5  4833.1 1046.44
  4849.7 1046.42  4855.3 1045.07  4864.7 1044.56  4871.9 1043.44  4877.5 1041.19
  4887.2 1039.78  4899.7 1035.22  4916.2 1033.92    4944 1030.28  4966.2 1029.93
  4977.1  1026.3  4982.8 1021.84  4999.3 1018.44    5005 1016.35  5008.8 1016.23
  5009.1 1015.73  5012.8 1016.23  5023.1 1017.07  5031.8 1019.65  5061.8 1020.87
  5071.8 1023.17  5091.8  1032.6  5101.8 1034.23  5121.8    1036  5188.2 1038.22
#Mann= 3 ,-1 , 0
  4734.5     .12       0  5008.8     .05       0  5012.8     .12       0
Bank Sta=5008.8,5012.8
XS Rating Curve= 0 ,0
Exp/Cntr=0.3,0.1

Type RM Length L Ch R = 1 ,233     ,163,163,163
BEGIN DESCRIPTION:
Dry Bear Tributary 710509
END DESCRIPTION:
XS GIS Cut Line= 3
      2204514.59     13847785.77      2204283.68     13847620.83
      2204195.83      13847519.2
#Sta/Elev= 30
  4749.1 1047.13  4756.9 1047.38    4763 1046.42  4771.6 1046.89  4777.8 1045.32
  4792.5 1046.39  4798.7 1044.91  4807.3 1045.08  4813.4 1041.65    4822 1040.05
  4828.2 1035.78  4834.6 1033.52    4849 1031.34  4914.7    1028  4979.3 1026.27
  4994.1 1018.92  5000.2 1012.57  5004.7 1012.28  5004.9 1011.78  5008.7 1012.28
  5021.1 1013.95    5029 1015.89  5032.9 1015.89  5057.1 1019.59  5099.9 1020.73
  5106.7 1019.82  5128.4 1021.59  5149.2  1026.8  5156.9 1029.53  5167.2 1031.37
#Mann= 4 ,-1 , 0
  4749.1     .12       0  4914.7    .035       0  5004.7    .035       0
  5008.7    .035       0
Bank Sta=5004.7,5008.7
XS Rating Curve= 0 ,0
Exp/Cntr=0.3,0.1

Type RM Length L Ch R = 1 ,70      ,0,0,0
BEGIN DESCRIPTION:
Dry Bear Tributary 710508
END DESCRIPTION:
XS GIS Cut Line= 4
      2204537.14     13847731.91      2204474.65     13847554.86
      2204363.54     13847487.15      2204202.04     13847506.26
#Sta/Elev= 30
  4754.4 1035.57  4771.4 1031.47  4776.7 1032.01  4833.3 1025.92  4864.2 1025.04
  4900.5 1026.02  4920.8 1024.06  4926.1 1025.12  4939.4 1019.23  4944.9 1019.23
  4949.5 1020.56  4955.4 1014.39    4965 1016.26  4970.6 1012.41  4984.3 1010.19
  4984.6 1009.69  4988.3 1010.19  5007.7 1012.71  5013.5 1012.46  5023.1 1014.81
    5029    1013  5044.4 1016.54  5050.3 1013.85  5065.8 1017.36  5069.5 1015.27
  5072.3 1015.27  5101.3 1018.02  5184.1 1019.59  5221.8    1030  5234.9 1031.26
#Mann= 4 ,-1 , 0
  4754.4    .035       0  4970.6     .12       0  4984.3     .05       0
  4988.3     .12       0
Bank Sta=4984.3,4988.3
XS Rating Curve= 0 ,0
Exp/Cntr=0.3,0.1

Chan Stop Cuts=-1
Use User Specified Reach Order=0
Composite Channel Slope=5