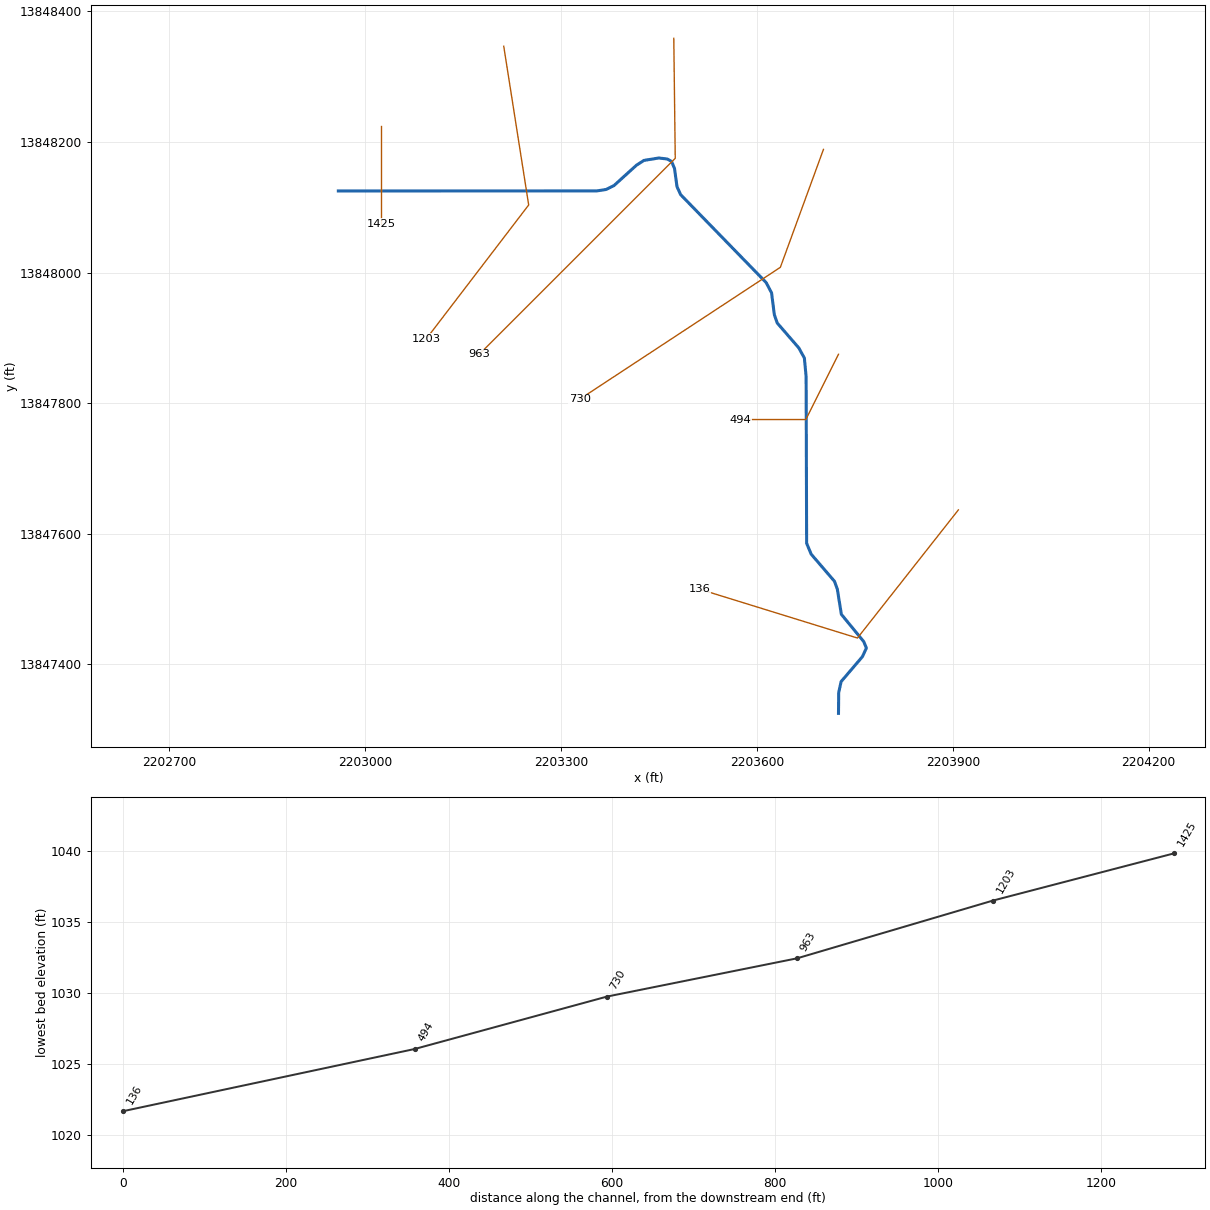
--- Dry Bear Tributary 8.prj (project) ---

Proj Title=Dry Bear Tributary 8 Base Level Engineering
Current Plan=p01
Default Exp/Contr=0.3,0.1
English Units
Geom File=g01
Flow File=f01
Plan File=p01
BEGIN DESCRIPTION:
Dry Bear Tributary 8
END DESCRIPTION:

--- Dry Bear Tributary 8.p01 (plan) ---

Plan Title=Multiple Run
Short Identifier=Multiple
Geom File=g01
Flow File=f01
Subcritical Flow
K Sum by GR= 0
Std Step Tol= 0.01
Critical Tol= 0.01
Num of Std Step Trials= 20
Max Error Tol= 0.3
Flow Tol Ratio= 0.001
Split Flow NTrial= 30
Split Flow Tol= 0.02
Split Flow Ratio= 0.02
Log Output Level= 0
Friction Slope Method= 1
Unsteady Friction Slope Method= 2
Unsteady Bridges Friction Slope Method= 1
Parabolic Critical Depth
Global Vel Dist=  1 , 1 , 1
Global Log Level= 0
CheckData=True
Encroach Param= -1, 0, 0, 0
BEGIN DESCRIPTION:
Multiple Run
END DESCRIPTION:

--- Dry Bear Tributary 8.f01 (steady flow) ---

Flow Title=Multiple
Number of Profiles=7
Profile Names=10-year,25-year,50-year,1pct_min,100-year,1pct_plu,500-year
River Rch & RM= Dry Bear Tributa,Reach-1,1425
     771    1280    1755    1169    2332    4653    4067
Boundary for River Rch & Prof#=Dry Bear Tributa,Reach-1,1
Up Type=0
Dn Type=3
Dn Slope=0.005
Boundary for River Rch & Prof#=Dry Bear Tributa,Reach-1,2
Up Type=0
Dn Type=3
Dn Slope=0.005
Boundary for River Rch & Prof#=Dry Bear Tributa,Reach-1,3
Up Type=0
Dn Type=3
Dn Slope=0.005
Boundary for River Rch & Prof#=Dry Bear Tributa,Reach-1,4
Up Type=0
Dn Type=3
Dn Slope=0.005
Boundary for River Rch & Prof#=Dry Bear Tributa,Reach-1,5
Up Type=0
Dn Type=3
Dn Slope=0.005
Boundary for River Rch & Prof#=Dry Bear Tributa,Reach-1,6
Up Type=0
Dn Type=3
Dn Slope=0.005
Boundary for River Rch & Prof#=Dry Bear Tributa,Reach-1,7
Up Type=0
Dn Type=3
Dn Slope=0.005

--- Dry Bear Tributary 8.g01 (geometry) ---

Geom Title=Existing Conditions

River Reach=Dry Bear Tributa,Reach-1
Reach XY= 30
      2202959.09     13848125.00      2203354.99     13848125.09
      2203369.10     13848127.30      2203381.12     13848133.21
      2203415.74     13848164.56      2203427.11     13848171.81
      2203450.12     13848175.53      2203462.99     13848173.83
      2203469.39     13848170.23      2203473.85     13848159.54
      2203477.69     13848131.62      2203483.28     13848119.35
      2203614.24     13847984.68      2203622.50     13847968.97
      2203626.72     13847935.71      2203631.14     13847922.83
      2203664.21     13847884.67      2203672.76     13847869.07
      2203675.44     13847840.18      2203676.20     13847585.50
      2203683.10     13847568.92      2203718.91     13847527.17
      2203723.22     13847515.13      2203729.41     13847476.63
      2203763.67     13847434.90      2203767.72     13847424.97
      2203761.53     13847411.73      2203729.00     13847373.64
      2203725.31     13847356.88      2203725.00     13847325.00

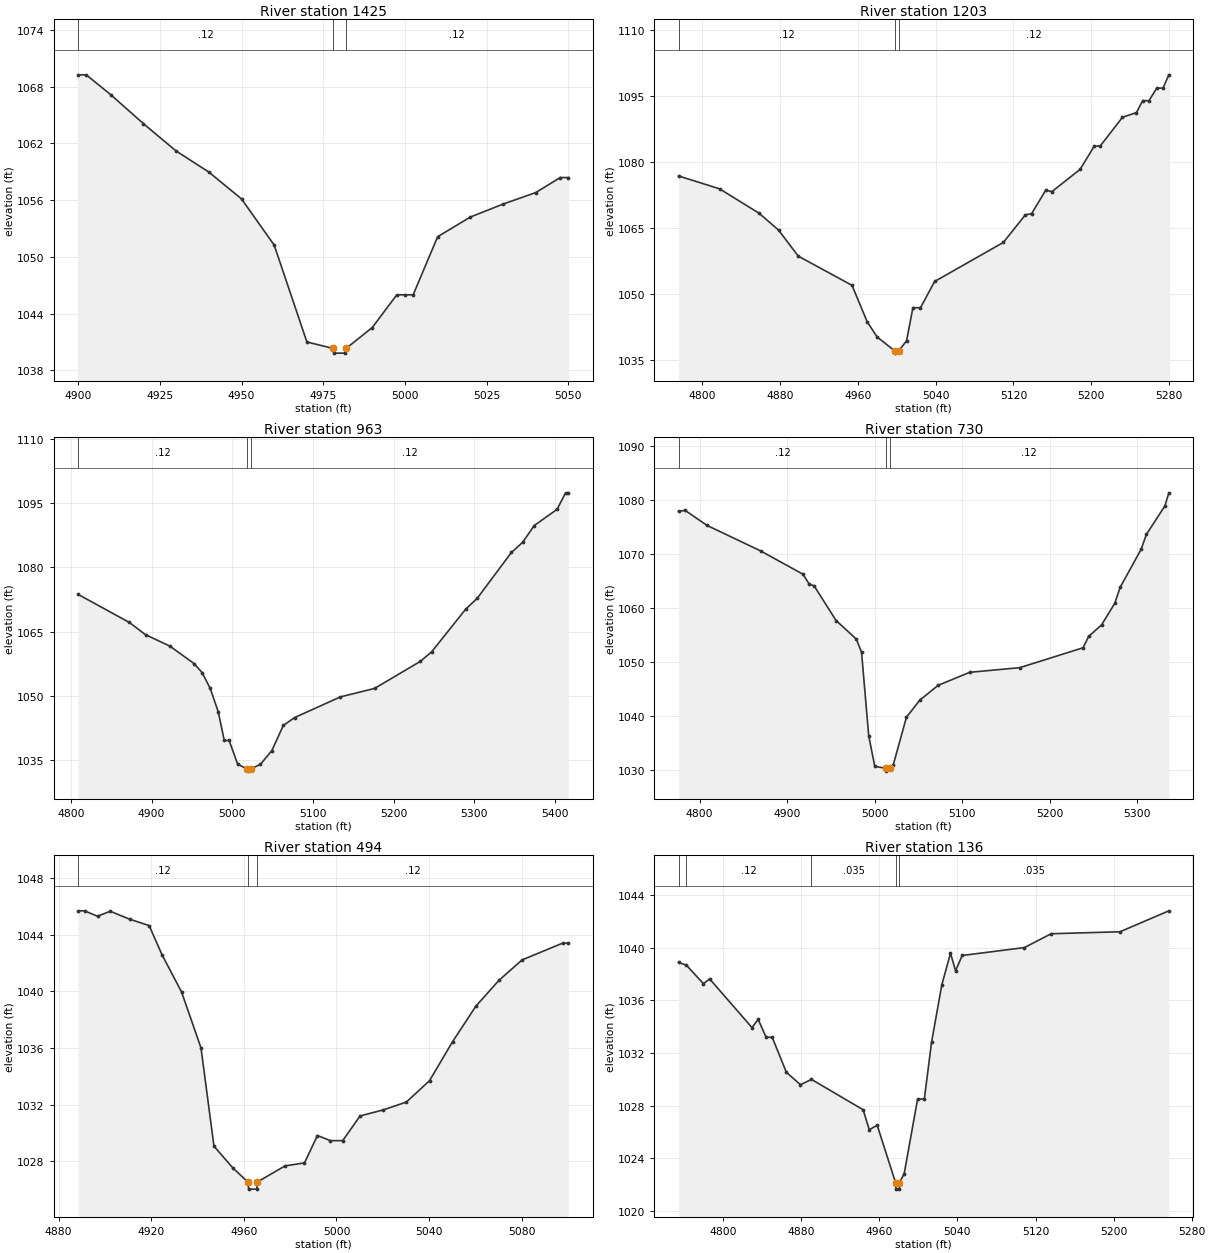
Type RM Length L Ch R = 1,1425,222,222,222
BEGIN DESCRIPTION:
Dry Bear Tributary 8 3.0
END DESCRIPTION:
XS GIS Cut Line= 3
      2203025.00     13848224.99      2203025.00     13848125.00
      2203025.00     13848074.99
#Sta/Elev= 23
  4900.0 1069.26  4902.5 1069.26  4910.0 1067.16  4920.0 1064.09  4930.0 1061.20
  4940.0 1058.97  4950.0 1056.13  4960.0 1051.24  4970.0 1040.99  4978.0 1040.31
  4978.2 1039.81  4981.7 1039.81  4982.0 1040.31  4990.0 1042.52  4997.5 1045.98
  5000.0 1045.98  5002.5 1045.98  5010.0 1052.13  5020.0 1054.21  5030.0 1055.58
  5040.0 1056.80  5047.5 1058.39  5050.0 1058.39
#Mann=3,-1,0
  4900.0    0.12       0  4978.0    0.05       0  4982.0    0.12       0
Bank Sta=4978,4982
Exp/Cntr=0.3,0.1

Type RM Length L Ch R = 1,1203,240,240,240
BEGIN DESCRIPTION:
Dry Bear Tributary 8 2.5
END DESCRIPTION:
XS GIS Cut Line= 3
      2203212.36     13848346.65      2203250.56     13848103.56
      2203093.76     13847898.52
#Sta/Elev= 30
  4775.6 1076.78  4817.8 1073.85  4858.3 1068.32  4878.5 1064.46  4898.7 1058.55
  4954.0 1051.90  4969.6 1043.62  4979.7 1040.19  4998.0 1036.99  4998.2 1036.49
  5002.0 1036.99  5010.1 1039.31  5016.6 1046.82  5024.4 1046.82  5038.9 1052.78
  5109.6 1061.66  5132.3 1067.95  5138.6 1068.19  5153.2 1073.54  5159.5 1073.21
  5188.5 1078.27  5203.0 1083.53  5209.3 1083.61  5232.1 1090.12  5246.5 1091.19
  5252.9 1093.93  5259.2 1093.85  5267.4 1096.78  5273.7 1096.73  5279.8 1099.77
#Mann=3,-1,0
  4775.6    0.12       0  4998.0    0.05       0  5002.0    0.12       0
Bank Sta=4998,5002
Exp/Cntr=0.3,0.1

Type RM Length L Ch R = 1,963,233,233,233
BEGIN DESCRIPTION:
Dry Bear Tributary 8 2.0
END DESCRIPTION:
XS GIS Cut Line= 3
      2203472.78     13848358.74      2203475.00     13848175.00
      2203175.01     13847875.01
#Sta/Elev= 30
  4808.8 1073.71  4872.5 1067.14  4892.5 1064.28  4922.5 1061.64  4952.6 1057.56
  4962.6 1055.44  4972.6 1051.78  4982.6 1046.29  4990.1 1039.60  4996.1 1039.60
  5006.7 1034.04  5018.8 1032.93  5019.1 1032.43  5022.8 1032.93  5035.0 1034.03
  5049.1 1037.24  5063.3 1043.10  5077.4 1044.95  5134.0 1049.76  5176.4 1051.74
  5233.0 1058.04  5247.1 1060.26  5289.5 1070.27  5303.7 1072.79  5346.1 1083.49
  5360.2 1085.90  5374.4 1089.78  5402.7 1093.56  5413.3 1097.42  5416.8 1097.42
#Mann=3,-1,0
  4808.8    0.12       0  5018.8    0.05       0  5022.8    0.12       0
Bank Sta=5018.8,5022.8
Exp/Cntr=0.3,0.1

Type RM Length L Ch R = 1,730,236,236,236
BEGIN DESCRIPTION:
Dry Bear Tributary 8 1.5
END DESCRIPTION:
XS GIS Cut Line= 3
      2203701.94     13848188.62      2203635.97     13848008.08
      2203328.47     13847805.95
#Sta/Elev= 30
  4775.9 1077.87  4783.3 1078.09  4808.5 1075.29  4869.6 1070.57  4918.2 1066.23
  4925.4 1064.35  4930.7 1064.11  4955.9 1057.66  4979.0 1054.22  4985.0 1051.78
  4993.2 1036.27  5000.1 1030.64  5013.2 1030.24  5013.4 1029.74  5017.2 1030.24
  5021.2 1030.90  5036.3 1039.74  5051.4 1042.87  5072.4 1045.64  5108.6 1048.06
  5165.8 1048.92  5238.1 1052.61  5244.5 1054.73  5259.2 1056.85  5274.3 1060.85
  5280.4 1063.81  5304.4 1070.86  5310.4 1073.62  5331.5 1078.89  5336.1 1081.33
#Mann=3,-1,0
  4775.9    0.12       0  5013.2    0.05       0  5017.2    0.12       0
Bank Sta=5013.2,5017.2
Exp/Cntr=0.3,0.1

Type RM Length L Ch R = 1,494,358,358,358
BEGIN DESCRIPTION:
Dry Bear Tributary 8 1.0
END DESCRIPTION:
XS GIS Cut Line= 3
      2203724.99     13847874.97      2203675.00     13847775.00
      2203574.97     13847775.00
#Sta/Elev= 30
  4888.4 1045.68  4891.2 1045.68  4896.8 1045.30  4902.3 1045.65  4910.7 1045.09
  4919.1 1044.64  4924.7 1042.57  4933.1 1039.96  4941.5 1036.01  4947.1 1029.08
  4955.4 1027.52  4961.8 1026.55  4962.1 1026.05  4965.6 1026.05  4965.8 1026.55
  4977.8 1027.69  4986.2 1027.90  4991.8 1029.83  4997.4 1029.47  5002.7 1029.47
  5010.2 1031.21  5020.2 1031.64  5030.2 1032.19  5040.2 1033.70  5050.2 1036.46
  5060.2 1038.95  5070.2 1040.78  5080.2 1042.22  5097.7 1043.40  5100.2 1043.40
#Mann=3,-1,0
  4888.4    0.12       0  4961.8    0.05       0  4965.8    0.12       0
Bank Sta=4961.8,4965.8
Exp/Cntr=0.3,0.1

Type RM Length L Ch R = 1,136,0,0,0
BEGIN DESCRIPTION:
Dry Bear Tributary 8 0.5
END DESCRIPTION:
XS GIS Cut Line= 3
      2203908.55     13847636.56      2203754.03     13847440.37
      2203512.74     13847515.01
#Sta/Elev= 30
  4754.3 1038.88  4762.3 1038.68  4779.8 1037.27  4786.2 1037.63  4829.5 1033.94
  4835.9 1034.55  4844.0 1033.21  4850.3 1033.19  4864.8 1030.54  4879.2 1029.60
  4890.5 1030.00  4943.4 1027.70  4949.7 1026.18  4957.8 1026.52  4976.6 1022.17
  4976.9 1021.67  4980.4 1021.67  4980.6 1022.17  4985.4 1022.82  4999.2 1028.51
  5006.1 1028.51  5013.5 1032.83  5024.0 1037.18  5032.9 1039.58  5038.1 1038.25
  5044.9 1039.41  5108.6 1040.01  5136.0 1041.06  5206.5 1041.21  5256.6 1042.80
#Mann=5,-1,0
  4754.3   0.035       0  4762.3    0.12       0  4890.5   0.035       0
  4976.6   0.035       0  4980.6   0.035       0
Bank Sta=4976.6,4980.6
Exp/Cntr=0.3,0.1

Chan Stop Cuts=-1