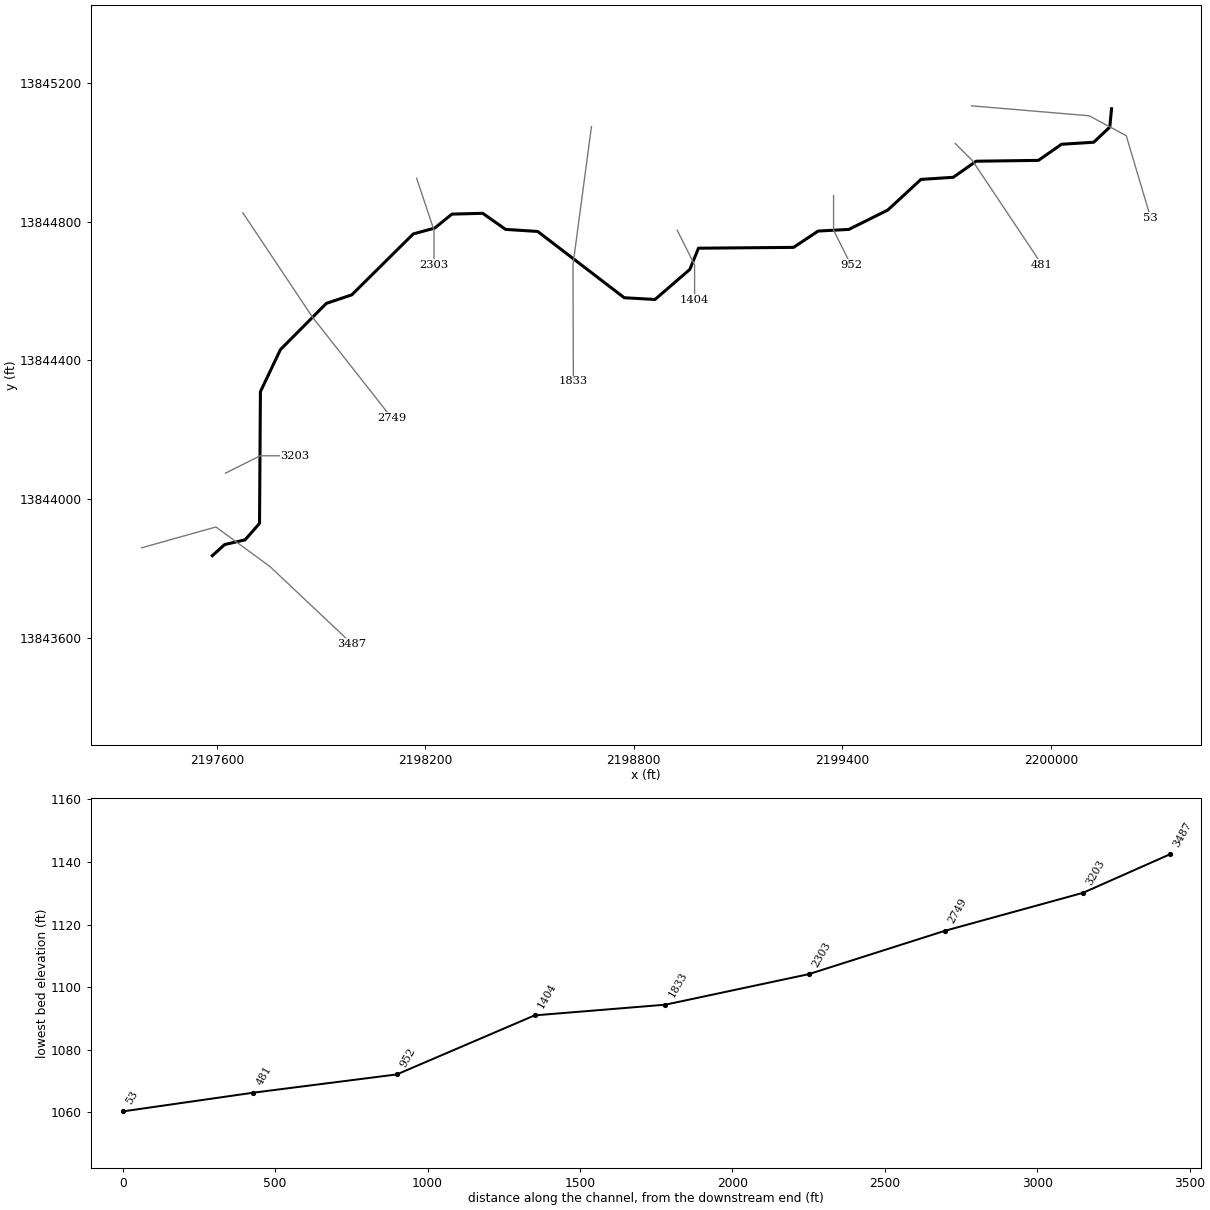
--- Dry Bear Tributary 9.prj (project) ---

Proj Title=Dry Bear Tributary 9 Base Level Engineering
Current Plan=p01
Default Exp/Contr=0.3,0.1
English Units
Geom File=g01
Flow File=f01
Plan File=p01
BEGIN DESCRIPTION:
Dry Bear Tributary 9
END DESCRIPTION:

--- Dry Bear Tributary 9.p01 (plan) ---

Plan Title=Multiple Run
Short Identifier=Multiple
Geom File=g01
Flow File=f01
Subcritical Flow
K Sum by GR= 0
Std Step Tol= 0.01
Critical Tol= 0.01
Num of Std Step Trials= 20
Max Error Tol= 0.3
Flow Tol Ratio= 0.001
Split Flow NTrial= 30
Split Flow Tol= 0.02
Split Flow Ratio= 0.02
Log Output Level= 0
Friction Slope Method= 1
Unsteady Friction Slope Method= 2
Unsteady Bridges Friction Slope Method= 1
Parabolic Critical Depth
Global Vel Dist=  1 , 1 , 1
Global Log Level= 0
CheckData=True
Encroach Param= -1, 0, 0, 0
BEGIN DESCRIPTION:
Multiple Run
END DESCRIPTION:

--- Dry Bear Tributary 9.f01 (steady flow) ---

Flow Title=Multiple
Number of Profiles=7
Profile Names=10-year,25-year,50-year,1pct_min,100-year,1pct_plu,500-year
River Rch & RM= Dry Bear Tributa,Reach-1,3487
    1059    1795    2497    1683    3359    6701    6012
Boundary for River Rch & Prof#=Dry Bear Tributa,Reach-1,1
Up Type=0
Dn Type=3
Dn Slope=0.005
Boundary for River Rch & Prof#=Dry Bear Tributa,Reach-1,2
Up Type=0
Dn Type=3
Dn Slope=0.005
Boundary for River Rch & Prof#=Dry Bear Tributa,Reach-1,3
Up Type=0
Dn Type=3
Dn Slope=0.005
Boundary for River Rch & Prof#=Dry Bear Tributa,Reach-1,4
Up Type=0
Dn Type=3
Dn Slope=0.005
Boundary for River Rch & Prof#=Dry Bear Tributa,Reach-1,5
Up Type=0
Dn Type=3
Dn Slope=0.005
Boundary for River Rch & Prof#=Dry Bear Tributa,Reach-1,6
Up Type=0
Dn Type=3
Dn Slope=0.005
Boundary for River Rch & Prof#=Dry Bear Tributa,Reach-1,7
Up Type=0
Dn Type=3
Dn Slope=0.005

--- Dry Bear Tributary 9.g01 (geometry) ---

Geom Title=Existing Conditions

River Reach=Dry Bear Tributa,Reach-1
Reach XY= 30
      2197587.09     13843837.09      2197622.54     13843869.17
      2197681.49     13843882.83      2197722.92     13843930.26
      2197725.51     13844309.79      2197783.14     13844431.06
      2197915.32     13844564.22      2197988.21     13844588.63
      2198165.32     13844764.24      2198227.17     13844781.15
      2198276.58     13844821.33      2198365.29     13844823.73
      2198430.98     13844777.36      2198523.50     13844771.38
      2198772.58     13844580.41      2198861.09     13844575.40
      2198961.27     13844662.02      2198986.14     13844723.15
      2199259.78     13844725.52      2199330.57     13844772.53
      2199419.03     13844777.33      2199531.05     13844833.16
      2199626.50     13844921.38      2199719.43     13844927.47
      2199785.50     13844973.78      2199964.50     13844976.22
      2200030.98     13845022.64      2200123.70     13845028.46
      2200169.87     13845072.06      2200175.00     13845125.00

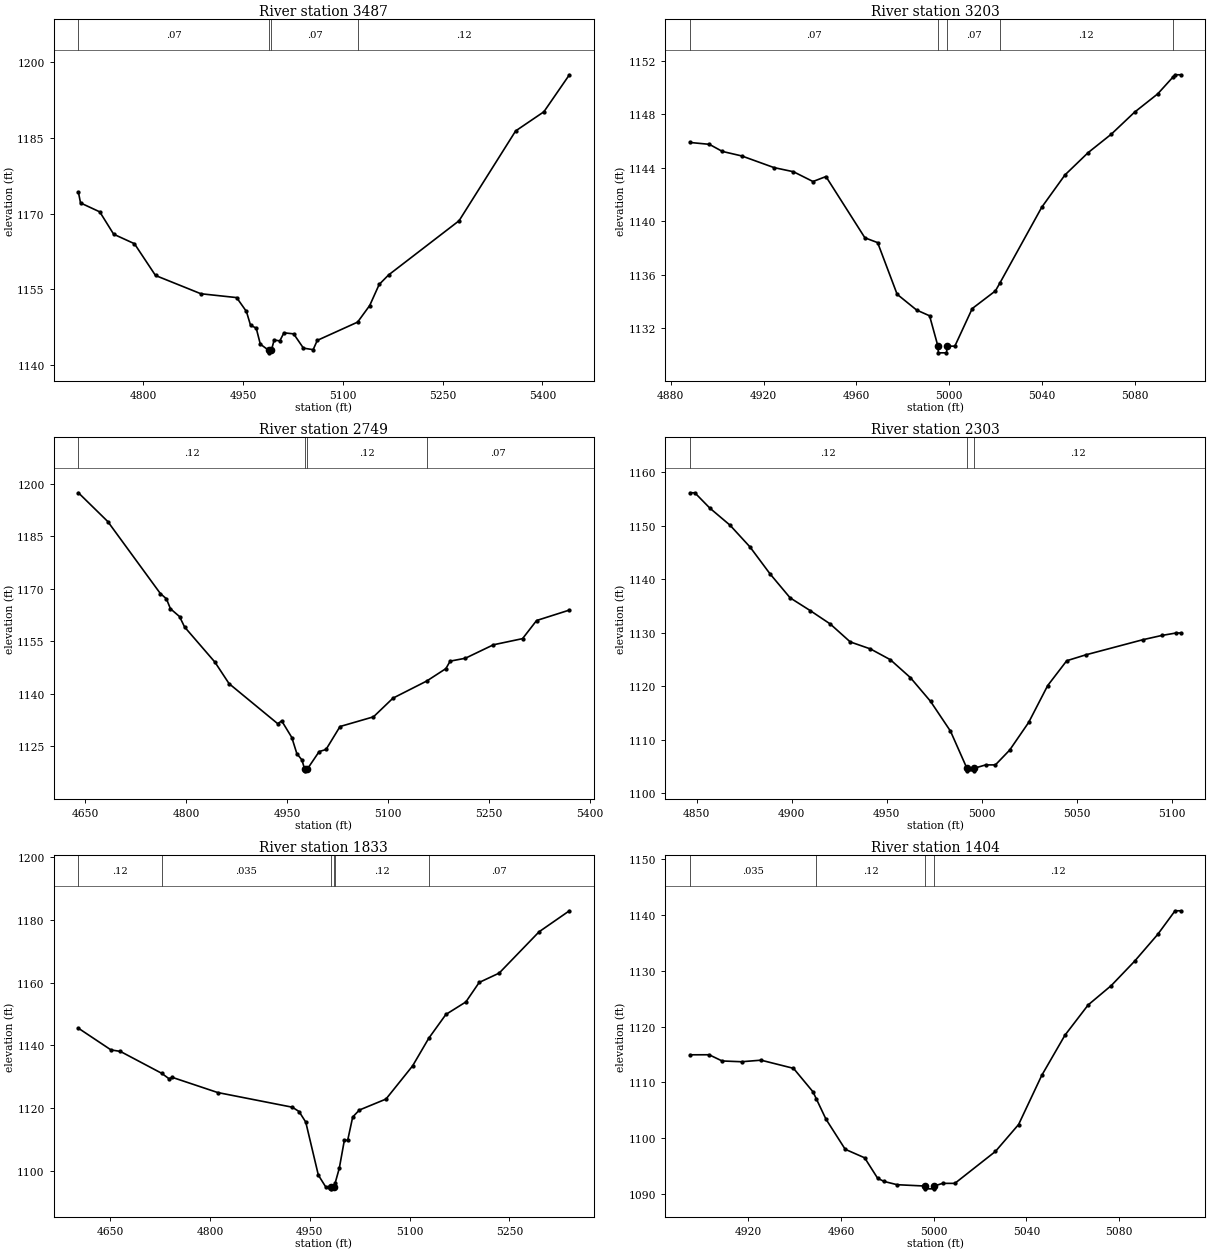
Type RM Length L Ch R = 1,3487,284,284,284
BEGIN DESCRIPTION:
DRY921513
END DESCRIPTION:
XS GIS Cut Line= 4
      2197383.95     13843859.96      2197597.46     13843919.85
      2197753.71     13843805.26      2197988.09     13843583.90
#Sta/Elev= 30
  4702.8 1174.27  4706.0 1172.13  4734.9 1170.36  4755.8 1165.93  4787.0 1164.05
  4818.7 1157.75  4886.9 1154.13  4940.6 1153.37  4955.3 1150.62  4961.5 1147.88
  4970.0 1147.33  4976.2 1144.14  4988.8 1142.92  4989.1 1142.42  4992.8 1142.92
  4997.0 1144.96  5005.5 1144.79  5011.7 1146.39  5026.3 1146.18  5041.0 1143.35
  5055.6 1143.05  5061.8 1144.89  5122.4 1148.51  5140.6 1151.80  5154.8 1155.97
  5168.9 1157.85  5274.9 1168.60  5359.9 1186.40  5402.4 1190.20  5440.7 1197.53
#Mann=4,-1,0
  4702.8    0.07       0  4988.8    0.05       0  4992.8    0.07       0
  5122.4    0.12       0
Bank Sta=4988.8,4992.8
Exp/Cntr=0.3,0.1

Type RM Length L Ch R = 1,3203,454,454,454
BEGIN DESCRIPTION:
Dry Bear Tributary 9 7.0
END DESCRIPTION:
XS GIS Cut Line= 3
      2197625.01     13844075.00      2197725.00     13844125.00
      2197825.01     13844125.00
#Sta/Elev= 30
  4888.2 1145.88  4896.6 1145.74  4902.2 1145.21  4910.6 1144.87  4924.5 1144.00
  4932.9 1143.69  4941.3 1142.96  4946.9 1143.33  4963.7 1138.75  4969.2 1138.39
  4977.6 1134.53  4986.0 1133.35  4991.6 1132.92  4995.2 1130.65  4995.4 1130.15
  4998.9 1130.15  4999.2 1130.65  5002.5 1130.65  5010.0 1133.46  5020.0 1134.78
  5021.9 1135.36  5040.0 1141.04  5050.0 1143.45  5060.0 1145.12  5070.0 1146.50
  5080.0 1148.14  5090.0 1149.51  5096.6 1150.77  5097.5 1150.94  5100.0 1150.94
#Mann=5,-1,0
  4888.2    0.07       0  4995.2    0.05       0  4999.2    0.07       0
  5021.9    0.12       0  5096.6    0.07       0
Bank Sta=4995.2,4999.2
Exp/Cntr=0.3,0.1

Type RM Length L Ch R = 1,2749,446,446,446
BEGIN DESCRIPTION:
Dry Bear Tributary 9 6.0
END DESCRIPTION:
XS GIS Cut Line= 3
      2197675.00     13844825.00      2197875.00     13844525.00
      2198102.68     13844234.94
#Sta/Elev= 30
  4639.7 1197.42  4683.3 1189.21  4761.4 1168.64  4770.4 1167.14  4776.4 1164.29
  4789.9 1162.06  4797.4 1159.08  4842.5 1149.03  4863.5 1142.89  4935.7 1131.46
  4941.7 1132.24  4956.7 1127.50  4964.2 1122.88  4971.7 1121.10  4975.7 1118.48
  4976.0 1117.98  4979.7 1118.48  4997.3 1123.48  5007.5 1124.08  5028.3 1130.64
  5078.0 1133.41  5106.9 1138.74  5157.1 1143.64  5185.5 1147.18  5191.9 1149.32
  5214.5 1150.15  5256.1 1153.99  5299.4 1155.75  5320.3 1160.93  5369.0 1163.91
#Mann=4,-1,0
  4639.7    0.12       0  4975.7    0.05       0  4979.7    0.12       0
  5157.1    0.07       0
Bank Sta=4975.7,4979.7
Exp/Cntr=0.3,0.1

Type RM Length L Ch R = 1,2303,470,470,470
BEGIN DESCRIPTION:
Dry Bear Tributary 9 5.0
END DESCRIPTION:
XS GIS Cut Line= 3
      2198175.00     13844924.99      2198225.00     13844775.00
      2198225.00     13844675.00
#Sta/Elev= 30
  4846.5 1156.14  4849.1 1156.14  4857.0 1153.27  4867.6 1150.08  4878.1 1146.01
  4888.7 1140.95  4899.2 1136.49  4909.7 1134.12  4920.3 1131.60  4930.8 1128.25
  4941.4 1126.94  4951.9 1124.92  4962.4 1121.58  4973.0 1117.14  4983.5 1111.56
  4992.1 1104.64  4992.3 1104.14  4995.8 1104.14  4996.1 1104.64  5002.0 1105.25
  5007.1 1105.25  5014.6 1108.02  5024.6 1113.20  5034.6 1120.09  5044.6 1124.73
  5054.6 1125.83  5084.6 1128.66  5094.6 1129.46  5102.1 1129.92  5104.6 1129.92
#Mann=3,-1,0
  4846.5    0.12       0  4992.1    0.05       0  4996.1    0.12       0
Bank Sta=4992.1,4996.1
Exp/Cntr=0.3,0.1

Type RM Length L Ch R = 1,1833,429,429,429
BEGIN DESCRIPTION:
Dry Bear Tributary 9 4.0
END DESCRIPTION:
XS GIS Cut Line= 3
      2198678.19     13845073.50      2198625.00     13844675.00
      2198626.10     13844339.53
#Sta/Elev= 30
  4602.5 1145.49  4651.4 1138.59  4665.5 1138.11  4727.4 1131.17  4738.6 1129.42
  4743.6 1129.85  4811.7 1125.03  4923.8 1120.36  4933.9 1118.99  4944.0 1115.62
  4962.9 1098.76  4974.3 1094.90  4982.4 1094.89  4982.6 1094.39  4986.4 1094.89
  4988.2 1096.26  4994.4 1100.97  5002.0 1109.86  5007.0 1109.86  5014.5 1117.23
  5024.5 1119.46  5064.5 1122.95  5104.5 1133.51  5128.7 1142.28  5154.5 1149.87
  5184.5 1153.85  5204.5 1160.05  5234.5 1163.02  5294.5 1176.17  5340.0 1182.85
#Mann=6,-1,0
  4602.5    0.12       0  4727.4   0.035       0  4982.4    0.05       0
  4986.4   0.035       0  4988.2    0.12       0  5128.7    0.07       0
Bank Sta=4982.4,4986.4
Exp/Cntr=0.3,0.1

Type RM Length L Ch R = 1,1404,452,452,452
BEGIN DESCRIPTION:
Dry Bear Tributary 9 3.0
END DESCRIPTION:
XS GIS Cut Line= 3
      2198925.02     13844774.97      2198975.00     13844675.00
      2198975.00     13844574.97
#Sta/Elev= 30
  4894.8 1114.95  4903.1 1114.96  4908.7 1113.85  4917.1 1113.71  4925.5 1113.99
  4939.5 1112.53  4947.9 1108.33  4949.3 1107.11  4953.5 1103.44  4961.8 1098.05
  4970.2 1096.52  4975.8 1092.86  4978.6 1092.29  4984.2 1091.71  4996.2 1091.47
  4996.4 1090.97  4999.9 1090.97  5000.2 1091.47  5003.8 1091.95  5009.1 1091.95
  5026.6 1097.66  5036.6 1102.48  5046.6 1111.28  5056.6 1118.46  5066.6 1123.87
  5076.6 1127.35  5086.6 1131.68  5096.6 1136.49  5104.1 1140.72  5106.6 1140.72
#Mann=4,-1,0
  4894.8   0.035       0  4949.3    0.12       0  4996.2    0.05       0
  5000.2    0.12       0
Bank Sta=4996.2,5000.2
Exp/Cntr=0.3,0.1

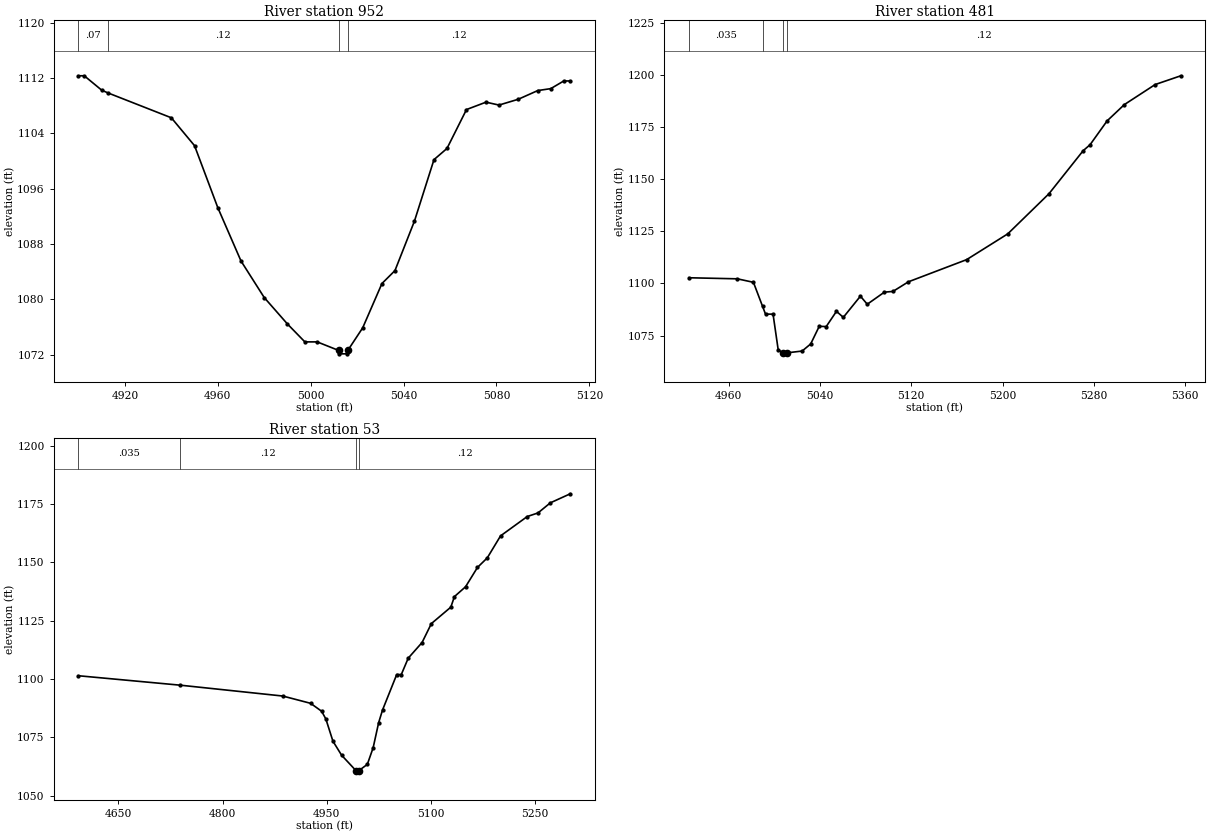
Type RM Length L Ch R = 1,952,471,471,471
BEGIN DESCRIPTION:
Dry Bear Tributary 9 2.0
END DESCRIPTION:
XS GIS Cut Line= 3
      2199375.00     13844875.00      2199375.00     13844775.00
      2199425.00     13844675.01
#Sta/Elev= 30
  4900.0 1112.35  4902.5 1112.35  4910.0 1110.27  4912.7 1109.87  4940.0 1106.27
  4950.0 1102.23  4960.0 1093.27  4970.0 1085.54  4980.0 1080.25  4990.0 1076.42
  4997.5 1073.83  5002.8 1073.83  5012.0 1072.60  5012.2 1072.10  5015.7 1072.10
  5016.0 1072.60  5022.4 1075.86  5030.7 1082.28  5036.3 1084.15  5044.7 1091.32
  5053.1 1100.21  5058.7 1101.83  5067.1 1107.46  5075.5 1108.53  5081.1 1108.11
  5089.4 1108.95  5097.8 1110.21  5103.4 1110.49  5109.0 1111.60  5111.8 1111.60
#Mann=4,-1,0
  4900.0    0.07       0  4912.7    0.12       0  5012.0    0.05       0
  5016.0    0.12       0
Bank Sta=5012,5016
Exp/Cntr=0.3,0.1

Type RM Length L Ch R = 1,481,428,428,428
BEGIN DESCRIPTION:
Dry Bear Tributary 9 1.0
END DESCRIPTION:
XS GIS Cut Line= 3
      2199725.02     13845024.98      2199775.00     13844975.00
      2199974.98     13844675.03
#Sta/Elev= 30
  4925.1 1102.72  4967.5 1102.21  4981.6 1100.54  4989.6 1089.03  4992.2 1085.29
  4998.8 1085.29  5003.3 1068.24  5007.3 1066.76  5007.6 1066.26  5011.3 1066.76
  5024.3 1067.60  5031.8 1071.00  5039.3 1079.46  5045.4 1079.32  5054.4 1086.63
  5060.4 1083.75  5075.4 1093.90  5081.4 1090.03  5096.4 1095.82  5103.9 1096.17
  5117.5 1100.79  5168.5 1111.40  5204.6 1123.77  5240.7 1142.99  5270.7 1163.63
  5276.7 1166.45  5291.7 1177.92  5306.8 1185.71  5333.8 1195.32  5356.3 1199.52
#Mann=4,-1,0
  4925.1   0.035       0  4989.6    0.12       0  5007.3    0.05       0
  5011.3    0.12       0
Bank Sta=5007.3,5011.3
Exp/Cntr=0.3,0.1

Type RM Length L Ch R = 1,53,0,0,0
BEGIN DESCRIPTION:
DRY921512
END DESCRIPTION:
XS GIS Cut Line= 4
      2199771.96     13845133.39      2200110.48     13845104.74
      2200217.25     13845047.45      2200287.57     13844810.46
#Sta/Elev= 30
  4592.5 1101.45  4739.3 1097.40  4886.6 1092.76  4926.7 1089.64  4942.6 1086.24
  4948.7 1082.93  4958.9 1073.40  4971.4 1067.39  4992.1 1060.78  4992.4 1060.28
  4996.1 1060.78  5008.4 1063.48  5016.8 1070.63  5024.7 1081.35  5030.3 1086.78
  5050.7 1101.96  5057.3 1101.96  5067.3 1108.99  5087.2 1115.68  5100.6 1123.79
  5128.6 1130.83  5133.8 1135.36  5149.8 1139.56  5167.0 1147.86  5181.1 1151.95
  5200.2 1161.37  5238.7 1169.67  5254.1 1171.20  5271.9 1175.53  5300.6 1179.41
#Mann=4,-1,0
  4592.5   0.035       0  4739.3    0.12       0  4992.1    0.05       0
  4996.1    0.12       0
Bank Sta=4992.1,4996.1
Exp/Cntr=0.3,0.1

Chan Stop Cuts=-1