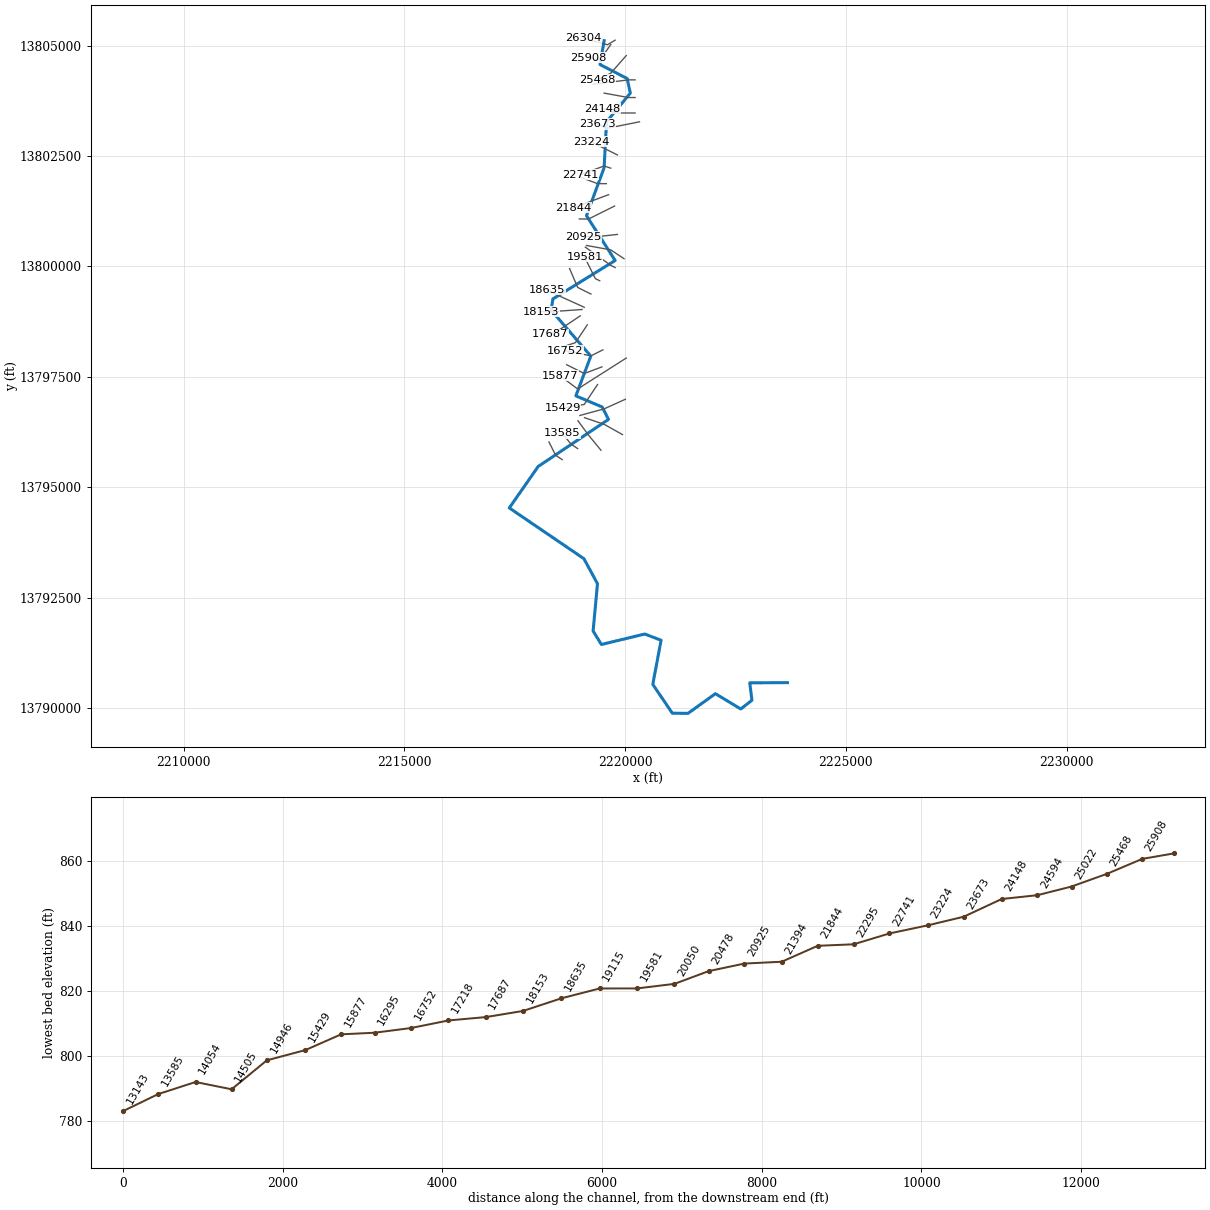
--- Dry Comal Creek Tributary 13.prj (project) ---

Proj Title=Dry Comal Creek Tributary 13 Base Level Engineering
Current Plan=p01
Default Exp/Contr=0.3,0.1
English Units
Geom File=g01
Flow File=f01
Plan File=p01
Y Axis Title=Elevation
X Axis Title(PF)=Main Channel Distance
X Axis Title(XS)=Station
BEGIN DESCRIPTION:
Dry Comal Creek Tributary 13
END DESCRIPTION:
DSS Export Rating Curves= 0
DSS Export Rating Curve Sorted= 0
DSS Export Volume Flow Curves= 0
DXF OffsetX= 0
DXF OffsetY= 0
DXF ScaleX= 1
DXF ScaleY= 10

--- Dry Comal Creek Tributary 13.p01 (plan) ---

Plan Title=Multiple Run
Short Identifier=Multiple
Geom File=g01
Flow File=f01
Subcritical Flow
K Sum by GR= 0
Std Step Tol= 0.01
Critical Tol= 0.01
Num of Std Step Trials= 20
Max Error Tol= 0.3
Flow Tol Ratio= 0.001
Split Flow NTrial= 30
Split Flow Tol= 0.02
Split Flow Ratio= 0.02
Log Output Level= 0
Friction Slope Method= 1
Unsteady Friction Slope Method= 2
Unsteady Bridges Friction Slope Method= 1
Parabolic Critical Depth
Global Vel Dist=  1 , 1 , 1
Global Log Level= 0
CheckData=True
Encroach Param= -1, 0, 0, 0
BEGIN DESCRIPTION:
Multiple Run
END DESCRIPTION:

--- Dry Comal Creek Tributary 13.f01 (steady flow) ---

Flow Title=Multiple
Number of Profiles=7
Profile Names=10-year,25-year,50-year,1pct_min,100-year,1pct_plu,500-year
River Rch & RM= Dry Comal Creek ,Reach-1,26304
     925    1529    2089    1381    2756    5498    4745
River Rch & RM= Dry Comal Creek ,Reach-1,25022
    1262    2122    2930    1956    3903    7787    6854
River Rch & RM= Dry Comal Creek ,Reach-1,22741
    1686    2877    4012    2702    5391   10756    9641
River Rch & RM= Dry Comal Creek ,Reach-1,20478
    1863    3179    4434    2984    5953   11878   10633
River Rch & RM= Dry Comal Creek ,Reach-1,12284
    2432    4230    5975    4070    8121   16204   14871
River Rch & RM= Dry Comal Creek ,Reach-1,8232
    2750    4815    6832    4673    9323   18603   17213
River Rch & RM= Dry Comal Creek ,Reach-1,4166
    2860    5023    7141    4895    9767   19487   18108
Boundary for River Rch & Prof#=Dry Comal Creek ,Reach-1,1
Up Type=0
Dn Type=3
Dn Slope=0.005
Boundary for River Rch & Prof#=Dry Comal Creek ,Reach-1,2
Up Type=0
Dn Type=3
Dn Slope=0.005
Boundary for River Rch & Prof#=Dry Comal Creek ,Reach-1,3
Up Type=0
Dn Type=3
Dn Slope=0.005
Boundary for River Rch & Prof#=Dry Comal Creek ,Reach-1,4
Up Type=0
Dn Type=3
Dn Slope=0.005
Boundary for River Rch & Prof#=Dry Comal Creek ,Reach-1,5
Up Type=0
Dn Type=3
Dn Slope=0.005
Boundary for River Rch & Prof#=Dry Comal Creek ,Reach-1,6
Up Type=0
Dn Type=3
Dn Slope=0.005
Boundary for River Rch & Prof#=Dry Comal Creek ,Reach-1,7
Up Type=0
Dn Type=3
Dn Slope=0.005

--- Dry Comal Creek Tributary 13.g01 (geometry) ---

Geom Title=Existing Conditions
Program Version=4.10

River Reach=Dry Comal Creek ,Reach-1
Reach XY= 30
        2219525.     13805112.71      2219430.69     13804572.61
      2220045.58     13804255.42      2220117.44       13803925.
      2219578.54     13803273.53      2219524.23     13802235.69
      2219124.79     13801149.91      2219773.81     13800134.59
      2218364.94     13799264.39      2218324.56     13799009.82
      2219222.95     13797969.14      2218884.13     13797068.26
      2219481.19     13796817.19      2219623.82     13796535.48
      2218030.59     13795469.39      2217376.96     13794530.89
      2219067.14     13793381.17      2219373.98     13792814.58
       2219274.9      13791745.1      2219461.68     13791438.37
      2220445.05     13791675.21      2220814.49     13791534.81
      2220626.19      13790535.5      2221068.52     13789882.69
      2221423.54     13789878.54      2222045.01     13790325.07
      2222619.07     13789977.24      2222871.54      13790176.5
      2222822.41     13790570.03        2223675.       13790575.

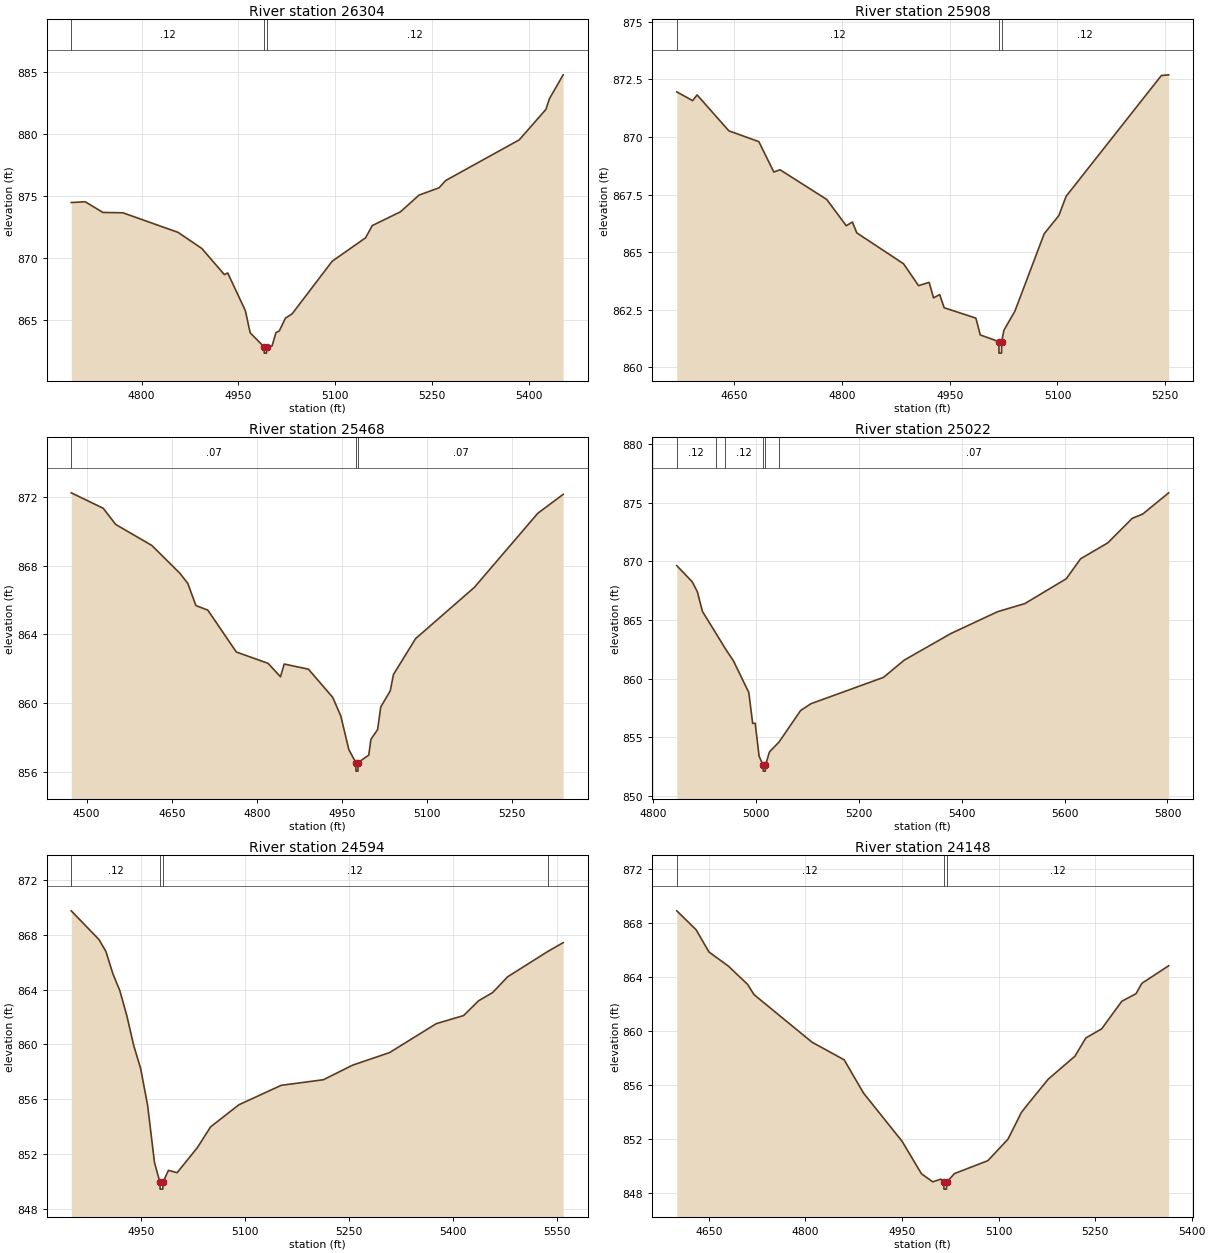
Type RM Length L Ch R = 1 ,26304   ,396,396,396
BEGIN DESCRIPTION:
X18985
END DESCRIPTION:
XS GIS Cut Line= 3
      2219773.74     13805124.13      2219600.11     13805019.95
      2219059.26     13805165.56
#Sta/Elev= 30
    4691  874.47  4712.7  874.53    4740  873.67  4771.1  873.64  4856.6  872.06
  4893.4  870.76  4928.4  868.65  4933.6  868.78  4960.9  865.74  4968.4  863.95
    4990  862.81  4990.2  862.31  4993.7  862.31    4994  862.81  5002.3  862.89
  5008.3  863.96  5013.5   864.1  5023.1  865.14  5033.4  865.48  5095.5  869.73
  5147.3  871.62  5157.7  872.61  5201.4  873.72  5230.2  875.07  5261.2  875.66
  5271.6  876.25  5385.5  879.53  5426.9  881.99  5432.2  882.84  5453.6  884.78
#Mann= 3 ,-1 , 0
    4691     .12       0    4990     .05       0    4994     .12       0
Bank Sta=4990,4994
XS Rating Curve= 0 ,0
Exp/Cntr=0.3,0.1

Type RM Length L Ch R = 1 ,25908   ,440,440,440
BEGIN DESCRIPTION:
Dry Comal Creek Tributary 13 49.0
END DESCRIPTION:
XS GIS Cut Line= 3
        2219675.       13805025.        2219425.       13804675.
      2219174.97     13804725.01
#Sta/Elev= 30
  4569.8  871.96  4591.9  871.58  4598.1  871.83  4642.3  870.27  4684.1   869.8
    4705  868.48  4713.6  868.58  4778.7  867.29  4805.8  866.15  4814.4  866.31
  4820.5  865.84  4885.6   864.5  4906.5  863.55  4921.3  863.69  4927.4  863.02
    4936  863.16  4942.2  862.59  4986.4  862.14  4992.5  861.41  5018.3  861.12
  5018.6  860.62  5022.1  860.62  5022.3  861.12  5025.4  861.61  5040.7  862.44
  5081.5   865.8  5101.9  866.59  5112.1  867.43  5244.7  872.67  5254.9   872.7
#Mann= 3 ,-1 , 0
  4569.8     .12       0  5018.3     .05       0  5022.3     .12       0
Bank Sta=5018.3,5022.3
XS Rating Curve= 0 ,0
Exp/Cntr=0.3,0.1

Type RM Length L Ch R = 1 ,25468   ,446,446,446
BEGIN DESCRIPTION:
Dry Comal Creek Tributary 13 48.0
END DESCRIPTION:
XS GIS Cut Line= 3
      2220024.97     13804774.97        2219675.       13804375.
      2219374.98     13804224.99
#Sta/Elev= 30
    4473  872.23  4529.4  871.33  4551.3  870.39  4614.9  869.17  4664.2  867.56
  4678.4  866.96  4692.7  865.67  4713.6  865.41  4763.9  862.97  4819.9  862.31
  4841.7  861.53  4848.3  862.27    4891  861.97  4933.8  860.33    4948  859.25
  4962.2  857.29  4974.5  856.54  4974.7  856.04  4978.2  856.04  4978.5  856.54
  4997.3  856.97  5001.1  857.89  5012.9  858.46  5018.4  859.77  5035.2  860.71
  5040.8  861.66  5079.9  863.75  5183.4  866.73  5295.2  871.04  5339.9  872.14
#Mann= 3 ,-1 , 0
    4473     .07       0  4974.5     .05       0  4978.5     .07       0
Bank Sta=4974.5,4978.5
XS Rating Curve= 0 ,0
Exp/Cntr=0.3,0.1

Type RM Length L Ch R = 1 ,25022   ,428,428,428
BEGIN DESCRIPTION:
Dry Comal Creek Tributary 13 47.0
END DESCRIPTION:
XS GIS Cut Line= 3
      2220224.95       13804225.        2220075.       13804225.
      2219274.98       13804125.
#Sta/Elev= 30
  4846.2  869.64  4876.2  868.26  4886.2  867.41  4896.2  865.72  4921.6  863.92
  4940.8  862.54  4956.2  861.53  4986.2  858.82  4993.7  856.19  4998.7  856.19
  5006.2  853.38  5014.1  852.61  5014.4  852.11  5018.3  852.11  5018.6  852.61
  5026.4  853.75  5045.1   854.6  5086.9  857.28    5107  857.86  5248.1  860.11
  5288.4  861.58  5379.1  863.85  5469.8  865.71  5522.7   866.4  5603.3  868.52
  5631.1  870.22    5684  871.58  5731.8  873.68    5752  874.04  5802.4  875.85
#Mann= 6 ,-1 , 0
  4846.2     .12       0  4921.6     .07       0  4940.8     .12       0
  5014.1     .05       0  5018.6     .12       0  5045.1     .07       0
Bank Sta=5014.1,5018.6
XS Rating Curve= 0 ,0
Exp/Cntr=0.3,0.1

Type RM Length L Ch R = 1 ,24594   ,446,446,446
BEGIN DESCRIPTION:
Dry Comal Creek Tributary 13 46.0
END DESCRIPTION:
XS GIS Cut Line= 3
      2220225.02       13803825.        2220075.       13803825.
      2219525.04     13803924.99
#Sta/Elev= 30
    4850  869.74    4890  867.64    4900  866.77    4910  865.15    4920  863.92
    4930  862.11    4940  859.92    4950  858.24    4960  855.57    4970  851.37
  4977.8  849.94  4978.1  849.44    4982  849.44  4982.3  849.94    4990  850.81
  5002.6  850.64  5031.8  852.47  5050.8  853.98  5091.5  855.59  5152.5  857.01
  5213.5  857.42  5255.4  858.48  5308.8   859.4  5376.1  861.51  5415.5   862.1
  5437.1  863.18  5457.4  863.78    5479  864.93  5536.7  866.77    5559  867.42
#Mann= 4 ,-1 , 0
    4850     .12       0  4977.8     .05       0  4982.3     .12       0
  5536.7    .035       0
Bank Sta=4977.8,4982.3
XS Rating Curve= 0 ,0
Exp/Cntr=0.3,0.1

Type RM Length L Ch R = 1 ,24148   ,475,475,475
BEGIN DESCRIPTION:
Dry Comal Creek Tributary 13 45.0
END DESCRIPTION:
XS GIS Cut Line= 3
      2220225.03       13803475.        2219825.       13803475.
      2219475.03     13803574.99
#Sta/Elev= 30
  4600.3  868.89  4630.3  867.49  4650.3  865.84  4680.3   864.8  4710.3  863.44
  4720.3  862.68  4810.3  859.16  4860.3  857.85  4890.3  855.39  4950.3  851.81
  4980.3  849.41  4997.8  848.81  5010.7  849.01  5014.9  848.77  5015.3  848.27
  5019.2  848.27  5019.5  848.77  5031.5  849.42  5083.5  850.38  5114.7  851.97
  5135.5  853.95  5145.9  854.58  5177.1  856.41  5218.7  858.12  5235.6  859.47
  5260.3  860.15  5291.5  862.19  5313.6  862.75  5322.7  863.52  5364.3  864.82
#Mann= 3 ,-1 , 0
  4600.3     .12       0  5014.9     .05       0  5019.5     .12       0
Bank Sta=5014.9,5019.5
XS Rating Curve= 0 ,0
Exp/Cntr=0.3,0.1

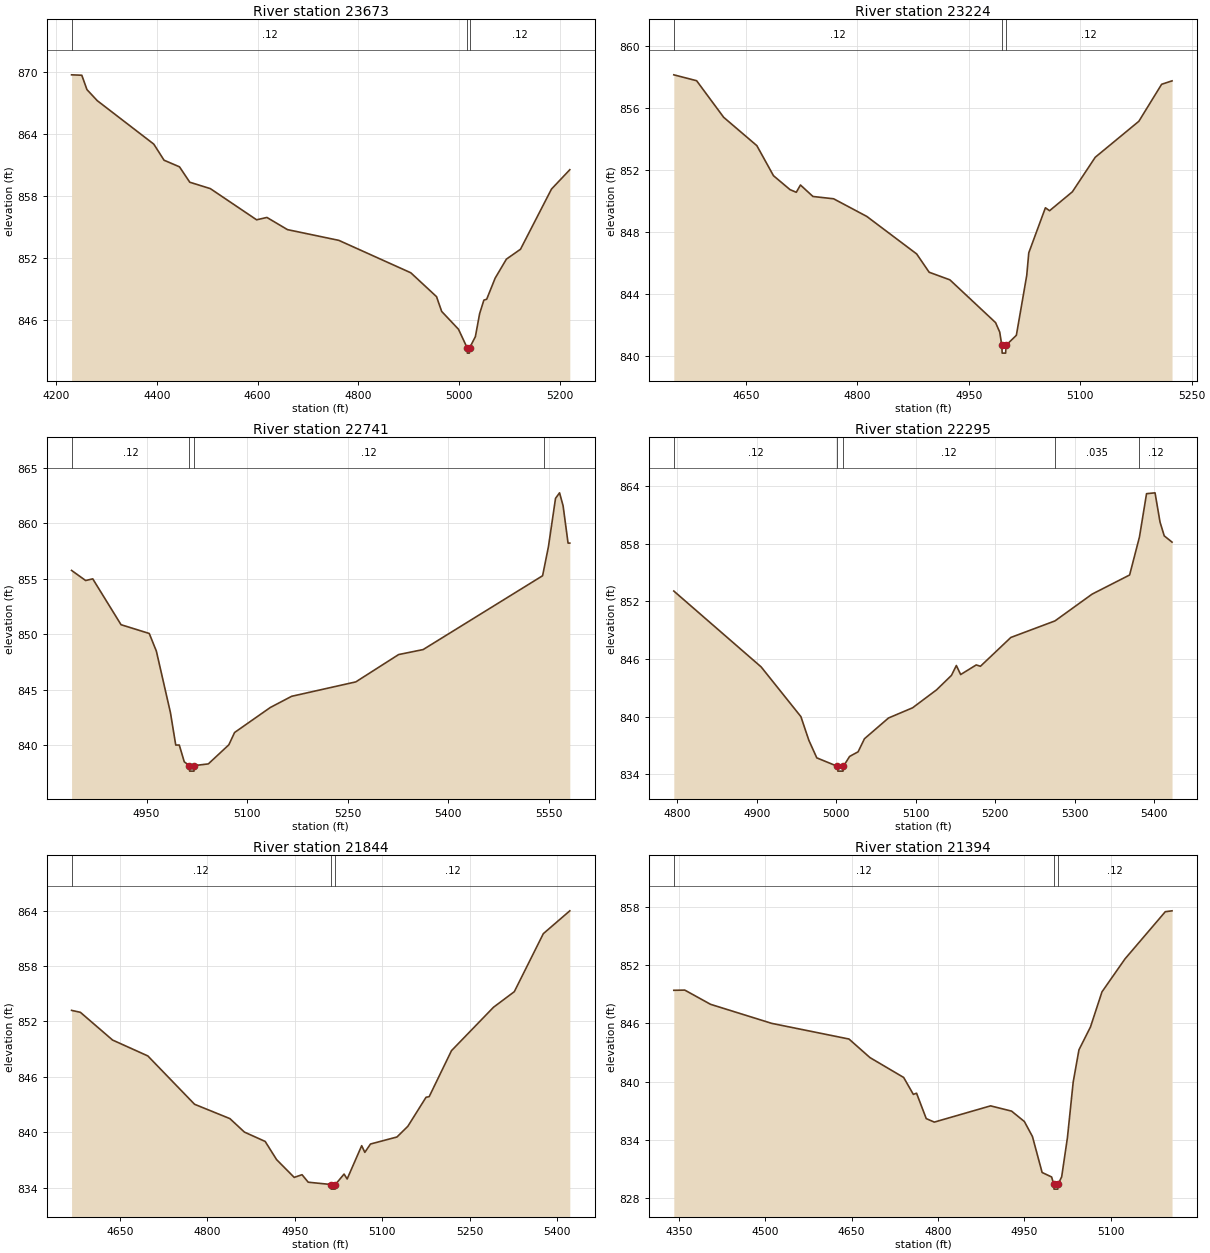
Type RM Length L Ch R = 1 ,23673   ,449,449,449
BEGIN DESCRIPTION:
Dry Comal Creek Tributary 13 44.0
END DESCRIPTION:
XS GIS Cut Line= 3
      2220324.95     13803274.99        2219575.       13803125.
      2219375.01     13803224.99
#Sta/Elev= 30
  4231.1  869.77  4251.4  869.73  4261.6  868.34    4282  867.27  4394.2  863.06
  4414.6   861.5  4445.2  860.86  4465.6  859.37  4506.4  858.75  4598.2  855.73
  4618.6  855.96  4659.4  854.78  4761.3  853.74  4904.1   850.6  4955.1  848.29
  4965.3  846.86  4998.7  845.13    5016  843.32  5016.3  842.82  5020.3  842.82
  5020.6  843.32  5032.2  844.42  5040.6  846.64    5049  847.95  5054.6  848.04
  5071.4  850.08  5093.7  851.92  5121.7  852.88  5183.2  858.71  5219.5  860.58
#Mann= 3 ,-1 , 0
  4231.1     .12       0    5016     .05       0  5020.6     .12       0
Bank Sta=5016,5020.6
XS Rating Curve= 0 ,0
Exp/Cntr=0.3,0.1

Type RM Length L Ch R = 1 ,23224   ,483,483,483
BEGIN DESCRIPTION:
Dry Comal Creek Tributary 13 43.0
END DESCRIPTION:
XS GIS Cut Line= 3
      2219824.99       13802525.        2219425.       13802725.
      2219225.01       13802825.
#Sta/Elev= 30
  4552.7  858.13  4583.4  857.75  4619.8  855.39  4664.5  853.56  4686.9  851.62
  4709.2  850.72  4717.6  850.55  4723.2  851.02    4740  850.28  4767.9  850.13
  4812.6  848.99  4879.7  846.57  4896.5  845.39  4924.4   844.9  4985.9  842.14
  4991.5  841.53  4994.3  840.67  4994.8  840.17  4999.5  840.17  4999.9  840.67
  5013.9  841.32  5027.9  845.19  5030.6  846.64    5053  849.55  5058.6  849.36
  5089.3  850.58  5120.1  852.81  5178.8  855.13  5209.5  857.52  5223.5  857.74
#Mann= 3 ,-1 , 0
  4552.7     .12       0  4994.3     .05       0  4999.9     .12       0
Bank Sta=4994.3,4999.9
XS Rating Curve= 0 ,0
Exp/Cntr=0.3,0.1

Type RM Length L Ch R = 1 ,22741   ,446,446,446
BEGIN DESCRIPTION:
Dry Comal Creek Tributary 13 42.0
END DESCRIPTION:
XS GIS Cut Line= 3
      2219674.97     13802225.01        2219525.       13802275.
      2218975.02     13802075.01
#Sta/Elev= 30
  4838.1  855.74  4859.1  854.83  4869.7  854.98  4911.9  850.85    4954  850.06
  4964.6  848.47  4985.6  842.93  4993.5  840.01  4998.8  840.01  5006.2   838.5
  5013.7  838.16  5014.2  837.66  5020.7  837.66  5021.2  838.16  5042.1  838.31
  5072.7  840.03  5081.3  841.14  5134.5  843.39  5166.4   844.4  5262.2   845.7
    5326  848.16  5362.6  848.61  5540.8  855.26  5543.1  855.95  5549.5  857.87
  5560.1  862.23  5566.1  862.73  5571.4  861.56  5578.8   858.2  5581.4   858.2
#Mann= 4 ,-1 , 0
  4838.1     .12       0  5013.7     .05       0  5021.2     .12       0
  5543.1    .035       0
Bank Sta=5013.7,5021.2
XS Rating Curve= 0 ,0
Exp/Cntr=0.3,0.1

Type RM Length L Ch R = 1 ,22295   ,451,451,451
BEGIN DESCRIPTION:
Dry Comal Creek Tributary 13 41.0
END DESCRIPTION:
XS GIS Cut Line= 3
      2219574.98       13801875.        2219375.       13801875.
      2218974.98     13802025.01
#Sta/Elev= 30
  4795.5  853.07  4905.5  845.17  4955.5     840  4965.5  837.54  4975.5  835.71
  5001.5  834.83    5002  834.33  5008.5  834.33    5009  834.83  5016.8  835.86
  5027.5  836.34  5035.5   837.7  5065.8  839.86  5096.1  840.92  5126.3  842.79
    5145  844.29  5151.2  845.32  5156.6  844.38  5176.2  845.38  5181.5  845.24
  5219.8  848.24  5275.3  849.96  5322.1  852.75  5369.3  854.74  5381.7   858.7
  5390.6   863.2  5401.3  863.29  5407.6  860.24  5412.9  858.81  5422.7  858.16
#Mann= 5 ,-1 , 0
  4795.5     .12       0  5001.5     .05       0    5009     .12       0
  5275.3    .035       0  5381.7     .12       0
Bank Sta=5001.5,5009
XS Rating Curve= 0 ,0
Exp/Cntr=0.3,0.1

Type RM Length L Ch R = 1 ,21844   ,450,450,450
BEGIN DESCRIPTION:
Dry Comal Creek Tributary 13 40.0
END DESCRIPTION:
XS GIS Cut Line= 3
      2219625.01       13801625.        2219225.       13801475.
      2218825.01       13801325.
#Sta/Elev= 30
  4567.1   853.2  4582.2  852.99  4637.4  849.99  4697.9  848.27    4778  843.04
  4838.6  841.49  4863.5  840.03  4899.1  839.02  4918.7  837.05  4948.9  835.13
  4962.3  835.42  4972.9  834.61  5011.9  834.36  5012.4  833.86    5019  833.86
  5019.5  834.36  5034.4  835.49  5039.7  834.96  5064.6  838.56    5070  837.84
  5079.7  838.74  5125.1   839.5  5143.8  840.66    5175   843.8  5180.3  843.86
  5218.6  848.84  5290.7  853.54  5326.3  855.22  5376.1   861.5  5421.5  863.97
#Mann= 3 ,-1 , 0
  4567.1     .12       0  5011.9     .05       0  5019.5     .12       0
Bank Sta=5011.9,5019.5
XS Rating Curve= 0 ,0
Exp/Cntr=0.3,0.1

Type RM Length L Ch R = 1 ,21394   ,469,469,469
BEGIN DESCRIPTION:
Dry Comal Creek Tributary 13 39.0
END DESCRIPTION:
XS GIS Cut Line= 4
      2219759.83     13801367.17        2219175.       13801075.
        2219075.       13801075.      2218963.25       13801075.
#Sta/Elev= 30
  4341.2   849.4  4360.3  849.42    4405  847.96  4511.3     846  4645.5  844.39
    4682  842.48  4740.5  840.44  4757.3   838.7  4762.9  838.82  4779.7  836.21
  4793.7  835.85  4891.5  837.52  4927.9  836.98  4950.2  835.91  4964.2  834.37
    4981  830.67  4997.5  830.21  5001.2  829.46  5001.7  828.96  5008.3  828.96
  5008.8  829.46    5015  830.23    5025  834.26    5035  839.97    5045  843.28
    5065  845.63    5085  849.24    5125  852.63    5195  857.48  5206.7  857.57
#Mann= 3 ,-1 , 0
  4341.2     .12       0  5001.2     .05       0  5008.8     .12       0
Bank Sta=5001.2,5008.8
XS Rating Curve= 0 ,0
Exp/Cntr=0.3,0.1

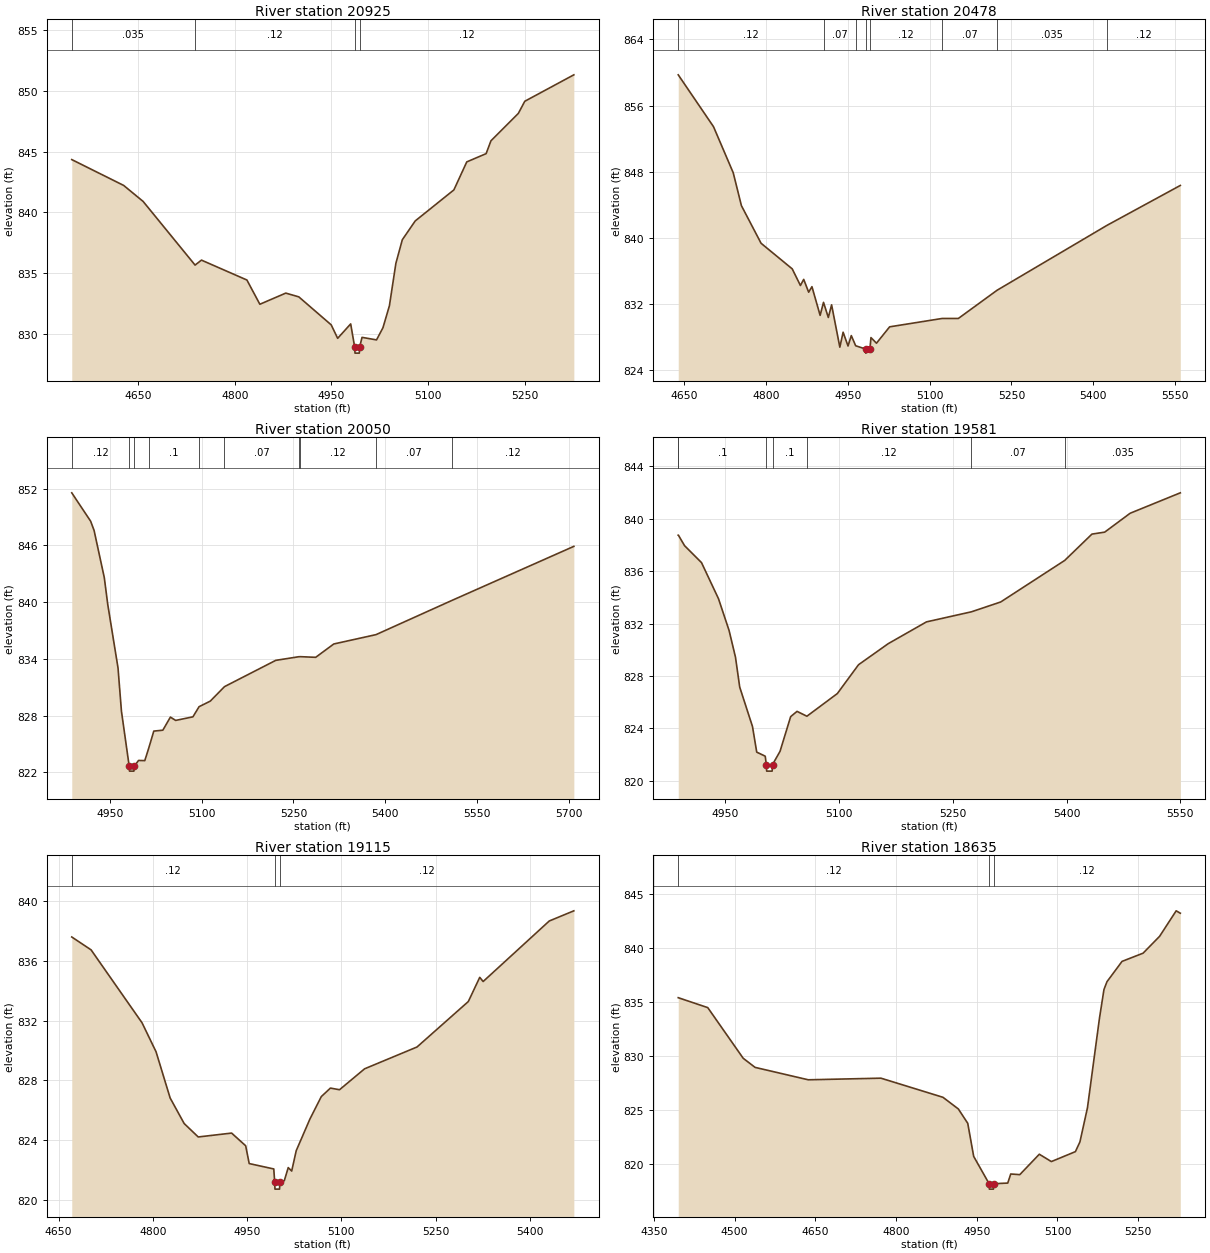
Type RM Length L Ch R = 1 ,20925   ,447,447,447
BEGIN DESCRIPTION:
Dry Comal Creek Tributary 13 38.0
END DESCRIPTION:
XS GIS Cut Line= 4
      2219825.01       13800725.        2219375.       13800675.
        2219175.       13800675.      2219048.88       13800675.
#Sta/Elev= 30
  4547.2  844.35  4627.7  842.22  4657.9   840.9  4738.5  835.65  4748.4  836.06
  4818.9  834.42    4839  832.42  4879.2  833.34  4899.4  833.03  4949.7  830.72
  4959.7  829.61  4979.9   830.8  4986.1  828.89  4986.6  828.39  4993.3  828.39
  4993.8  828.89  4997.5  829.69    5020  829.48    5030  830.49    5040   832.3
    5050  835.79    5060  837.74    5080  839.29    5140  841.85    5160  844.16
    5190  844.84  5197.5   845.9    5240  848.16    5250  849.16  5326.1  851.34
#Mann= 4 ,-1 , 0
  4547.2    .035       0  4738.5     .12       0  4986.1     .05       0
  4993.8     .12       0
Bank Sta=4986.1,4993.8
XS Rating Curve= 0 ,0
Exp/Cntr=0.3,0.1

Type RM Length L Ch R = 1 ,20478   ,428,428,428
BEGIN DESCRIPTION:
Dry Comal Creek Tributary 13 37.0
END DESCRIPTION:
XS GIS Cut Line= 3
        2219975.       13800175.        2219675.       13800375.
      2219124.97     13800475.01
#Sta/Elev= 30
  4639.6  859.72  4704.2  853.45  4740.3  847.88  4755.3   843.9  4791.3  839.35
  4848.4  836.25  4863.4  834.24  4869.4  834.98  4878.5  833.43  4884.5   834.1
  4899.5  830.63  4905.7   832.2  4914.5  830.37  4920.5   831.9  4935.6  826.78
  4941.6  828.59  4950.6  826.92  4956.6  828.18  4964.6  826.95  4982.6  826.56
  4983.1  826.06  4990.7  826.56  4992.6  827.94  5002.7  827.26  5026.8  829.24
  5122.8  830.25  5152.6  830.25  5223.5  833.66  5424.8  841.51  5559.2  846.34
#Mann= 8 ,-1 , 0
  4639.6     .12       0  4905.7     .07       0  4964.6     .12       0
  4982.6     .05       0  4990.7     .12       0  5122.8     .07       0
  5223.5    .035       0  5424.8     .12       0
Bank Sta=4982.6,4990.7
XS Rating Curve= 0 ,0
Exp/Cntr=0.3,0.1

Type RM Length L Ch R = 1 ,20050   ,469,469,469
BEGIN DESCRIPTION:
Dry Comal Creek Tributary 13 36.0
END DESCRIPTION:
XS GIS Cut Line= 4
      2219775.02     13799974.99        2219675.       13800025.
        2219325.       13800275.      2219099.06     13800436.39
#Sta/Elev= 30
  4888.2  851.56    4919  848.56  4924.6  847.59  4941.3   842.6  4946.9  839.78
  4963.7  833.05  4969.3  828.47    4982  822.64  4982.5  822.14  4989.6  822.14
  4990.1  822.64  4997.2  823.27  5007.4  823.25  5013.8  824.56  5022.1  826.37
  5036.9  826.47  5049.2  827.85  5057.8   827.5    5086  827.88    5096  828.95
  5114.3  829.54  5137.5  831.07  5221.2  833.85  5258.5  834.23  5261.2  834.24
  5286.4  834.17  5315.9  835.58  5384.9  836.57  5508.6  840.18  5707.8   845.9
#Mann= 10 ,-1 , 0
  4888.2     .12       0    4982     .05       0  4990.1     .12       0
  5013.8      .1       0    5096    .035       0  5137.5     .07       0
  5258.5    .035       0  5261.2     .12       0  5384.9     .07       0
  5508.6     .12       0
Bank Sta=4982,4990.1
XS Rating Curve= 0 ,0
Exp/Cntr=0.3,0.1

Type RM Length L Ch R = 1 ,19581   ,466,466,466
BEGIN DESCRIPTION:
Dry Comal Creek Tributary 13 35.0
END DESCRIPTION:
XS GIS Cut Line= 4
      2219424.96     13799675.02        2219325.       13799725.
        2219125.       13800125.      2219079.19     13800216.61
#Sta/Elev= 30
  4888.5  838.75  4888.7  838.75  4896.8  837.95  4919.2  836.65  4941.6  833.89
  4955.5  831.47  4963.9  829.44  4969.5  827.15  4986.3  824.15  4991.9  822.19
  5003.1  821.88  5004.5  821.24    5005  820.74  5012.2  820.74  5012.7  821.24
  5022.6  822.25  5036.6   824.9    5045   825.3    5058  824.93  5098.1  826.66
    5126  828.86  5165.2  830.47  5215.5  832.13  5274.8   832.9  5313.3  833.65
  5397.6  836.82  5433.5  838.83  5450.3  838.98  5483.8  840.42  5549.9  841.98
#Mann= 7 ,-1 , 0
  4888.5     .12       0  4888.7      .1       0  5004.5     .05       0
  5012.7      .1       0    5058     .12       0  5274.8     .07       0
  5397.6    .035       0
Bank Sta=5004.5,5012.7
XS Rating Curve= 0 ,0
Exp/Cntr=0.3,0.1

Type RM Length L Ch R = 1 ,19115   ,480,480,480
BEGIN DESCRIPTION:
Dry Comal Creek Tributary 13 34.0
END DESCRIPTION:
XS GIS Cut Line= 4
      2219224.96     13799375.02        2218925.       13799525.
        2218775.       13799875.      2218742.44     13799950.96
#Sta/Elev= 30
    4671   837.6  4701.7  836.74  4782.8  831.86  4805.1  829.92  4827.5  826.83
  4849.8  825.12  4872.2  824.22  4925.3  824.48  4947.7  823.63  4953.3  822.44
  4992.4  822.08  4993.8  821.23  4994.3  820.73  5001.6  820.73  5002.1  821.23
  5009.1  821.29  5015.4  822.17  5020.9  821.94  5028.1   823.3  5049.9  825.42
    5068  826.92  5082.5  827.49    5097  827.38  5136.9  828.78  5220.3  830.24
  5301.9  833.28  5320.1   834.9  5325.5  834.62  5430.7  838.67  5469.8  839.35
#Mann= 3 ,-1 , 0
    4671     .12       0  4993.8     .05       0  5002.1     .12       0
Bank Sta=4993.8,5002.1
XS Rating Curve= 0 ,0
Exp/Cntr=0.3,0.1

Type RM Length L Ch R = 1 ,18635   ,482,482,482
BEGIN DESCRIPTION:
Dry Comal Creek Tributary 13 33.0
END DESCRIPTION:
XS GIS Cut Line= 4
        2219075.       13799075.        2218525.       13799325.
        2218325.       13799425.       2218230.6      13799472.2
#Sta/Elev= 30
  4395.1  835.42    4450   834.5  4515.9  829.81  4537.9  828.97  4636.8  827.82
  4771.9  827.97  4887.2   826.2  4915.8  825.12  4933.3  823.79  4944.3  820.73
    4973   818.2  4973.5   817.7    4981   817.7  4981.5   818.2  5007.6  818.26
  5013.2   819.1    5030  819.04  5066.3  820.93  5088.7  820.25  5133.4  821.17
  5141.8  822.07  5155.8  825.23  5178.1  833.51  5186.5  836.18  5192.1   836.9
  5220.1  838.78  5259.2  839.54  5289.9   841.1  5320.7  843.46  5328.4  843.24
#Mann= 3 ,-1 , 0
  4395.1     .12       0    4973     .05       0  4981.5     .12       0
Bank Sta=4973,4981.5
XS Rating Curve= 0 ,0
Exp/Cntr=0.3,0.1

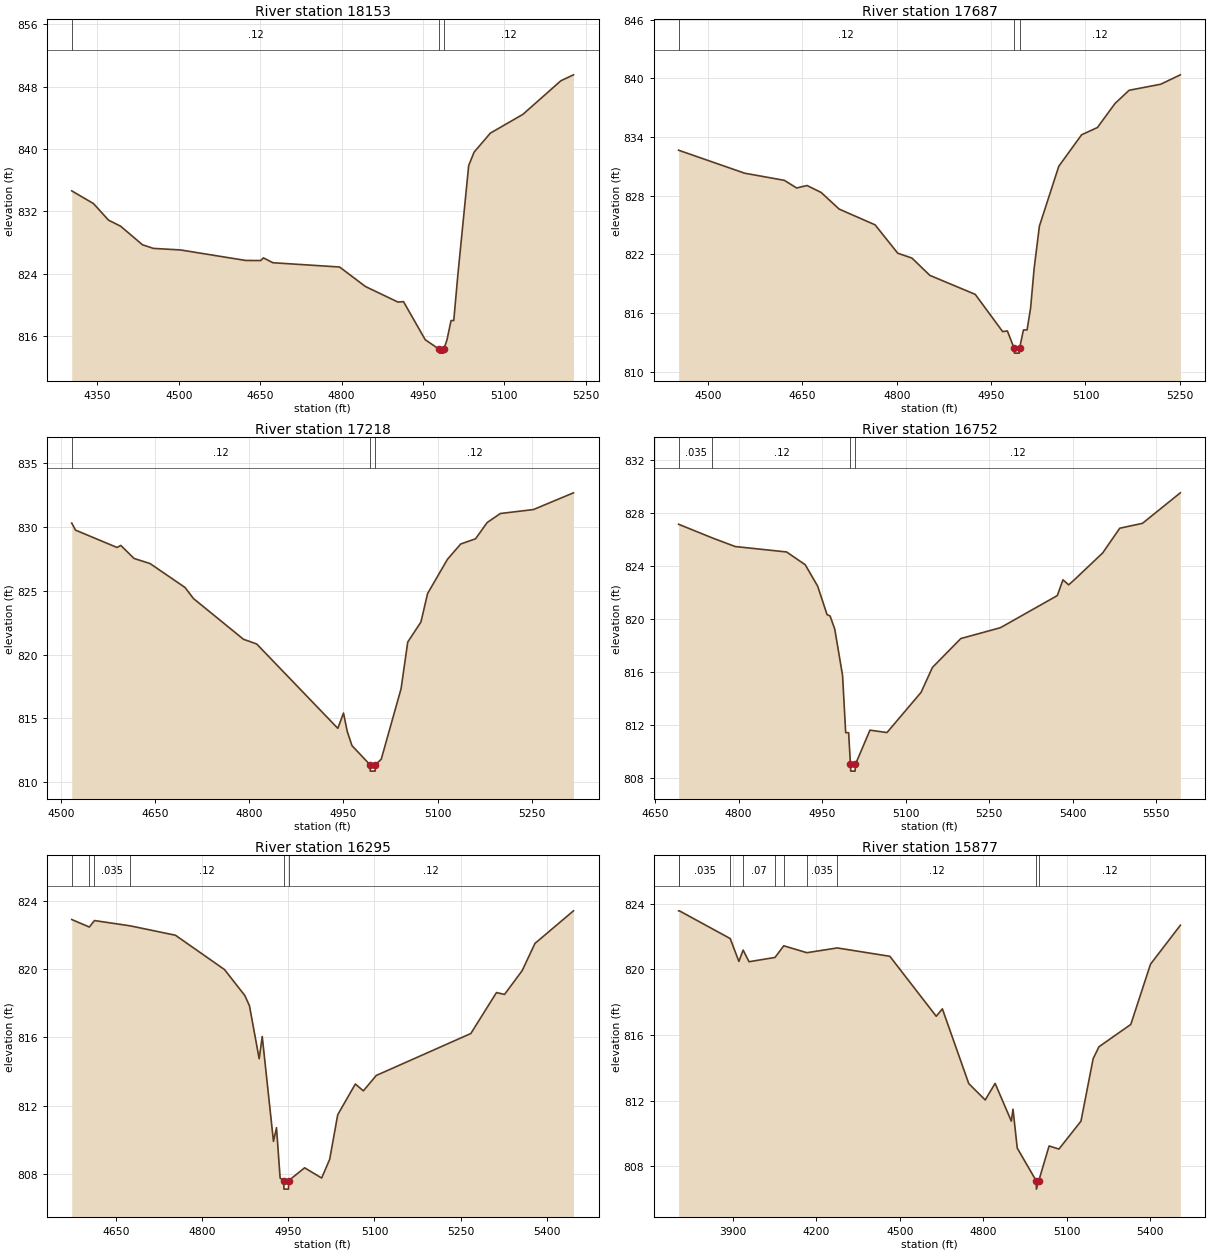
Type RM Length L Ch R = 1 ,18153   ,466,466,466
BEGIN DESCRIPTION:
Dry Comal Creek Tributary 13 32.0
END DESCRIPTION:
XS GIS Cut Line= 4
        2219025.       13799025.        2218325.       13798975.
        2218225.       13798975.      2218101.78       13798975.
#Sta/Elev= 30
  4302.6  834.62  4342.7  832.99  4370.3  830.87  4392.8  830.08  4432.9  827.71
    4453  827.24  4503.1  827.04  4623.4  825.69    4651  825.68    4656  826.02
  4673.5   825.4  4796.4  824.85    4844  822.35  4904.1  820.35  4914.2  820.41
  4954.3  815.52    4980   814.3  4980.5   813.8  4988.1   813.8  4988.6   814.3
  4994.4   815.5  5001.9  817.98  5006.9  817.98  5014.4   823.8  5034.4  837.86
  5044.4  839.59  5074.4  842.03  5134.4  844.44  5204.4  848.75  5227.6  849.51
#Mann= 3 ,-1 , 0
  4302.6     .12       0    4980     .05       0  4988.6     .12       0
Bank Sta=4980,4988.6
XS Rating Curve= 0 ,0
Exp/Cntr=0.3,0.1

Type RM Length L Ch R = 1 ,17687   ,469,469,469
BEGIN DESCRIPTION:
Dry Comal Creek Tributary 13 31.0
END DESCRIPTION:
XS GIS Cut Line= 5
      2218983.58     13798880.72        2218825.       13798775.
        2218525.       13798575.        2218425.       13798525.
      2218304.65     13798464.83
#Sta/Elev= 30
  4453.3  832.66  4558.3  830.31  4621.4  829.58  4640.9   828.8  4657.4  829.05
  4679.9  828.34  4708.5  826.64  4765.6  825.03  4801.6  822.13  4824.2  821.63
  4852.7  819.86  4924.8  817.92  4968.4  814.11  4975.9  814.18  4986.6  812.41
  4987.1  811.91  4994.8  811.91  4995.3  812.41  5001.4  814.28  5007.2  814.28
  5012.8  816.53  5018.4  820.56  5026.8   824.9  5057.6  831.02  5093.9  834.24
    5119  834.98    5147  837.44  5169.4  838.79  5219.7  839.41  5250.8  840.37
#Mann= 3 ,-1 , 0
  4453.3     .12       0  4986.6     .05       0  4995.3     .12       0
Bank Sta=4986.6,4995.3
XS Rating Curve= 0 ,0
Exp/Cntr=0.3,0.1

Type RM Length L Ch R = 1 ,17218   ,466,466,466
BEGIN DESCRIPTION:
Dry Comal Creek Tributary 13 30.0
END DESCRIPTION:
XS GIS Cut Line= 5
      2219142.51     13798676.26        2219075.       13798575.
        2218875.       13798275.        2218725.       13798225.
       2218574.6     13798174.87
#Sta/Elev= 30
  4517.5   830.3  4523.5  829.75  4589.6  828.39  4595.6  828.55  4616.7  827.53
  4642.2  827.13  4697.8  825.26  4711.3  824.39  4790.9   821.2    4812  820.83
  4941.2  814.22  4950.2  815.42  4956.2  813.98  4963.7  812.87  4992.4  811.37
  4992.9  810.87  5000.6  810.87  5001.1  811.37  5010.3   811.8  5041.9  817.33
  5052.5  820.98  5073.5  822.55  5084.1  824.78  5115.7  827.46  5136.8  828.66
  5160.5  829.07  5178.9  830.34    5200  831.05  5252.7  831.36  5316.4  832.67
#Mann= 3 ,-1 , 0
  4517.5     .12       0  4992.4     .05       0  5001.1     .12       0
Bank Sta=4992.4,5001.1
XS Rating Curve= 0 ,0
Exp/Cntr=0.3,0.1

Type RM Length L Ch R = 1 ,16752   ,457,457,457
BEGIN DESCRIPTION:
Dry Comal Creek Tributary 13 29.0
END DESCRIPTION:
XS GIS Cut Line= 5
      2219495.92     13798110.46        2219325.       13798025.
        2219225.       13797975.        2218725.       13798075.
      2218638.31     13798092.34
#Sta/Elev= 30
  4692.3  827.17  4752.8  826.14  4793.9  825.49  4886.2  825.08  4919.7  824.12
  4942.1   822.5  4958.9  820.36  4964.4  820.25  4972.8  819.26  4986.8  815.77
  4992.4  811.45  4997.7  811.45    5001  809.05  5001.5  808.55  5009.3  808.55
  5009.8  809.05    5036  811.64  5066.6  811.46  5127.8  814.49  5148.2  816.37
  5199.2  818.55  5270.5  819.37  5372.5  821.79  5382.7  822.98  5392.9   822.6
  5403.1  822.98  5454.1  825.01  5484.7  826.87  5525.5  827.24  5593.5  829.54
#Mann= 4 ,-1 , 0
  4692.3    .035       0  4752.8     .12       0    5001     .05       0
  5009.8     .12       0
Bank Sta=5001,5009.8
XS Rating Curve= 0 ,0
Exp/Cntr=0.3,0.1

Type RM Length L Ch R = 1 ,16295   ,418,418,418
BEGIN DESCRIPTION:
Dry Comal Creek Tributary 13 28.0
END DESCRIPTION:
XS GIS Cut Line= 3
      2219475.05     13797725.02        2219075.       13797575.
      2218674.97     13797775.02
#Sta/Elev= 30
  4572.4   822.9    4603  822.46    4612  822.84  4674.3  822.53  4753.1  821.98
  4838.6  819.97  4874.2  818.44  4882.2  817.84  4899.1  814.74  4904.4  816.05
    4924   809.9  4929.3   810.7  4935.6  807.75  4941.8   807.6  4942.3   807.1
  4950.1   807.1  4950.6   807.6  4978.3  808.35    5008  807.75    5022  808.85
    5036  811.46  5066.7  813.26  5080.7  812.86  5103.1  813.76    5268  816.22
  5312.7  818.62  5326.7  818.51  5357.4   819.9  5379.8   821.5  5446.9  823.41
#Mann= 6 ,-1 , 0
  4572.4    .035       0    4603     .07       0    4612    .035       0
  4674.3     .12       0  4941.8     .05       0  4950.6     .12       0
Bank Sta=4941.8,4950.6
XS Rating Curve= 0 ,0
Exp/Cntr=0.3,0.1

Type RM Length L Ch R = 1 ,15877   ,448,448,448
BEGIN DESCRIPTION:
Dry Comal Creek Tributary 13 27.0
END DESCRIPTION:
XS GIS Cut Line= 3
      2220025.01       13797925.        2218925.       13797225.
      2218525.04     13797524.97
#Sta/Elev= 30
  3704.7  823.56  3707.5  823.56  3890.3  821.87  3921.4  820.48  3936.7  821.17
  3957.9  820.46  4051.2  820.72  4082.7  821.43  4165.8  821.01  4275.1   821.3
  4464.2  820.79  4630.9  817.14    4653  817.59  4747.8  813.04    4807  812.04
  4842.6  813.05    4901  810.75  4906.9  811.48  4922.2  809.11  4990.6  807.11
  4991.1  806.61  4999.4  807.11  5036.7  809.24  5072.1  809.05  5151.3  810.75
    5195  814.55  5215.8  815.28  5330.4  816.64  5401.3  820.31  5508.5  822.68
#Mann= 10 ,-1 , 0
  3704.7    .063       0  3707.5    .035       0  3890.3     .12       0
  3936.7     .07       0  4051.2    .035       0  4082.7     .12       0
  4165.8    .035       0  4275.1     .12       0  4990.6     .05       0
  4999.4     .12       0
Bank Sta=4990.6,4999.4
XS Rating Curve= 0 ,0
Exp/Cntr=0.3,0.1

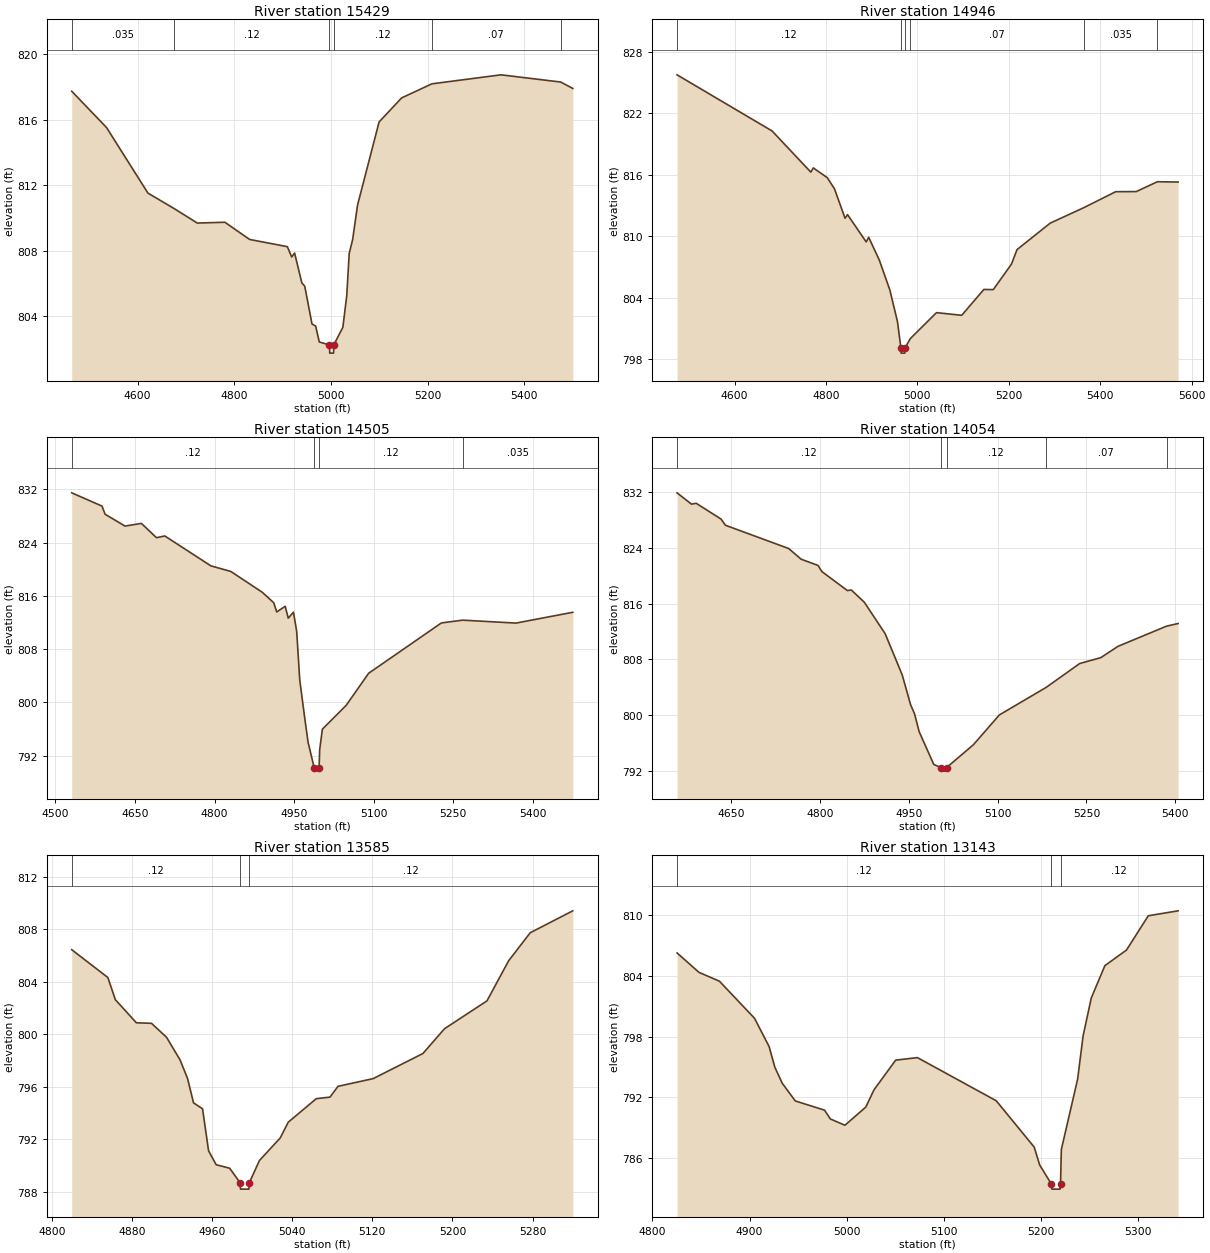
Type RM Length L Ch R = 1 ,15429   ,483,483,483
BEGIN DESCRIPTION:
Dry Comal Creek Tributary 13 26.0
END DESCRIPTION:
XS GIS Cut Line= 3
      2219374.99     13797324.99        2219075.       13796875.
      2218585.35     13796795.99
#Sta/Elev= 30
  4463.6  817.75  4535.7  815.53  4621.3  811.53  4674.7   810.6  4723.5   809.7
  4780.6  809.75  4831.7   808.7  4909.8  808.26  4918.8  807.63  4924.8  807.87
  4939.8  806.05  4945.8  805.85  4960.8  803.54  4968.4  803.41  4975.9  802.44
    4997  802.26  4997.5  801.76  5005.4  801.76  5005.9  802.26  5024.7  803.34
  5032.8   805.3  5037.8  807.85  5044.9  808.69  5055.1   810.8  5099.6  815.87
  5146.2  817.34  5208.9   818.2  5351.8  818.75  5475.4  818.31  5500.4  817.92
#Mann= 6 ,-1 , 0
  4463.6    .035       0  4674.7     .12       0    4997     .05       0
  5005.9     .12       0  5208.9     .07       0  5475.4     .12       0
Bank Sta=4997,5005.9
XS Rating Curve= 0 ,0
Exp/Cntr=0.3,0.1

Type RM Length L Ch R = 1 ,14946   ,441,441,441
BEGIN DESCRIPTION:
Dry Comal Creek Tributary 13 25.0
END DESCRIPTION:
XS GIS Cut Line= 3
      2220004.58     13796991.28        2219525.       13796775.
      2218974.98       13796625.
#Sta/Elev= 30
  4474.2  825.75  4682.2  820.27  4766.8  816.26  4772.3  816.67  4802.8  815.72
  4818.6  814.63  4841.7  811.76  4847.2  812.11    4888  809.45  4893.5   809.9
  4916.6  807.69  4939.7  804.77  4956.4  801.68  4963.9   799.1  4964.4   798.6
  4972.3   798.6  4972.8   799.1  4984.8  800.03  5041.8  802.55    5097  802.29
  5145.4  804.81  5166.1   804.8  5205.9  807.29    5218   808.7  5290.5  811.28
  5364.6   812.8  5433.9  814.35  5478.8  814.36  5525.1  815.32  5570.4  815.29
#Mann= 6 ,-1 , 0
  4474.2     .12       0  4963.9     .05       0  4972.8     .12       0
  4984.8     .07       0  5364.6    .035       0  5525.1     .07       0
Bank Sta=4963.9,4972.8
XS Rating Curve= 0 ,0
Exp/Cntr=0.3,0.1

Type RM Length L Ch R = 1 ,14505   ,451,451,451
BEGIN DESCRIPTION:
Dry Comal Creek Tributary 13 24.0
END DESCRIPTION:
XS GIS Cut Line= 3
       2219939.5     13796191.83        2219525.       13796425.
      2219080.18     13796574.62
#Sta/Elev= 30
  4530.6  831.46  4587.7  829.47  4593.5  828.25  4631.1  826.47    4662  826.87
  4690.4  824.73  4706.3  824.98    4793   820.5  4830.6  819.66  4889.9  816.54
  4911.5  814.97  4917.3  813.58  4933.2  814.43  4938.9  812.65  4948.8  813.54
  4954.9  810.64  4960.6  803.39  4970.8   797.2  4976.5  793.97  4987.9  790.19
  4988.4  789.69  4997.1  790.19  4998.2  792.88  5003.3  795.99  5048.2  799.56
  5090.6  804.38  5227.7  811.93  5267.7  812.35  5368.5  811.91  5475.5  813.53
#Mann= 4 ,-1 , 0
  4530.6     .12       0  4987.9     .05       0  4997.1     .12       0
  5267.7    .035       0
Bank Sta=4987.9,4997.1
XS Rating Curve= 0 ,0
Exp/Cntr=0.3,0.1

Type RM Length L Ch R = 1 ,14054   ,469,469,469
BEGIN DESCRIPTION:
Dry Comal Creek Tributary 13 23.0
END DESCRIPTION:
XS GIS Cut Line= 3
      2219452.56     13795837.63        2219175.       13796175.
      2218931.72     13796504.31
#Sta/Elev= 30
  4558.6  831.94    4583  830.31  4590.8  830.44  4632.9  828.17  4640.3  827.28
  4747.2  823.93  4768.1   822.4  4796.7   821.5  4803.2  820.62  4846.3  817.89
    4853  817.97  4874.9  816.21  4910.1  811.69  4938.8  805.79  4953.1  801.47
  4959.6  800.21  4967.5  797.61  4992.2  792.89  5004.4  792.43  5004.9  791.93
  5013.2  791.93  5013.7  792.43  5059.1  795.72    5103  800.01  5181.9  803.96
  5238.7   807.4  5274.2  808.24  5303.4  809.87  5385.3  812.77  5404.9  813.15
#Mann= 5 ,-1 , 0
  4558.6     .12       0  5004.4     .05       0  5013.7     .12       0
  5181.9     .07       0  5385.3    .035       0
Bank Sta=5004.4,5013.7
XS Rating Curve= 0 ,0
Exp/Cntr=0.3,0.1

Type RM Length L Ch R = 1 ,13585   ,442,442,442
BEGIN DESCRIPTION:
Dry Comal Creek Tributary 13 22.0
END DESCRIPTION:
XS GIS Cut Line= 3
      2218925.03     13795874.98        2218775.       13795975.
      2218574.98     13796225.02
#Sta/Elev= 30
  4819.7  806.44  4855.8  804.32  4863.3  802.63  4884.3  800.87  4899.4  800.83
  4914.4  799.77  4927.9  798.05  4935.4  796.63  4941.4  794.77  4950.4  794.32
  4956.4  791.12    4964  790.06  4977.5  789.79  4987.8   788.7  4988.3   788.2
  4996.7   788.2  4997.2   788.7  5007.2  790.38    5028   792.1    5036   793.3
    5064  795.09  5077.7  795.21  5085.7  796.03  5120.9  796.62  5170.5  798.53
  5192.1  800.42  5234.5  802.54  5256.1  805.59  5277.7  807.73  5320.2   809.4
#Mann= 3 ,-1 , 0
  4819.7     .12       0  4987.8     .05       0  4997.2     .12       0
Bank Sta=4987.8,4997.2
XS Rating Curve= 0 ,0
Exp/Cntr=0.3,0.1

Type RM Length L Ch R = 1 ,13143   ,446,446,446
BEGIN DESCRIPTION:
Dry Comal Creek Tributary 13 21.0
END DESCRIPTION:
XS GIS Cut Line= 3
      2218575.04     13795624.98        2218425.       13795725.
      2218275.01     13796024.97
#Sta/Elev= 30
  4825.4  806.26    4848  804.34    4869  803.47  4905.1  799.81  4920.1  797.02
  4926.1  794.96  4933.6   793.4  4947.1  791.64  4977.2  790.73  4983.2  789.86
  4998.2  789.24  5019.7  791.04  5028.1  792.74  5050.4  795.67  5072.8  795.92
  5153.9  791.66    5193  787.08  5198.6  785.32  5210.7  783.43  5211.2  782.93
  5219.6  782.93  5220.1  783.43  5220.9  786.83  5237.7   793.8  5243.3  798.06
  5251.7   801.8  5265.7     805    5288  806.55  5310.4  809.93  5341.1  810.42
#Mann= 3 ,-1 , 0
  4825.4     .12       0  5210.7     .05       0  5220.1     .12       0
Bank Sta=5210.7,5220.1
XS Rating Curve= 0 ,0
Exp/Cntr=0.3,0.1