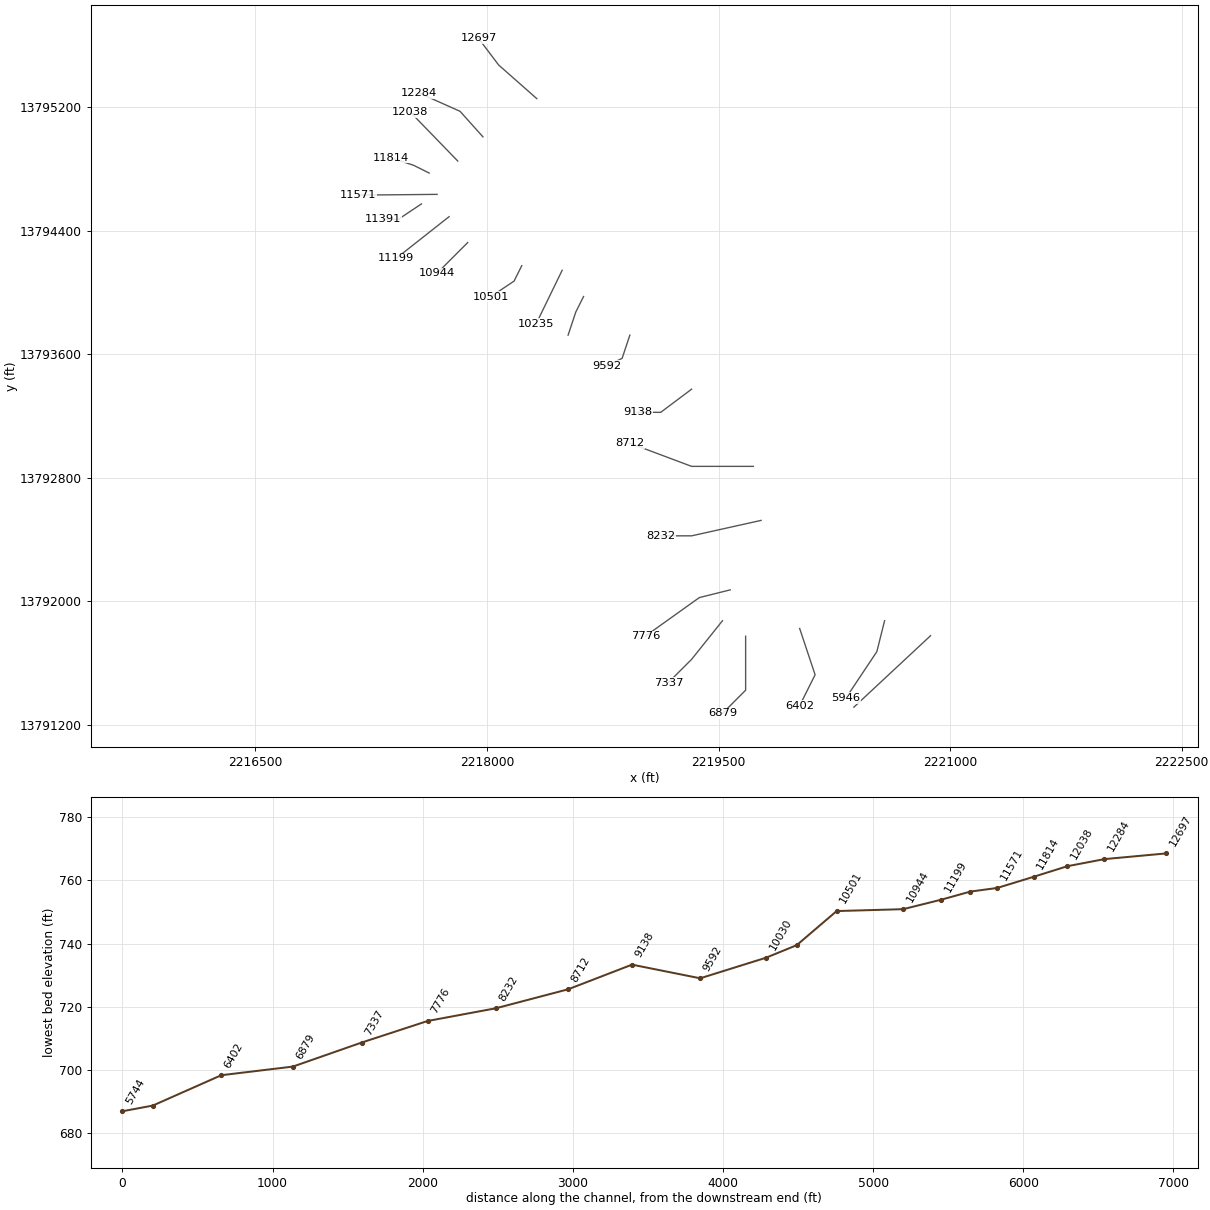
HEC-RAS study Dry Comal Creek Tributary 13.prj: Dry Comal Creek Tributary 13 Base Level Engineering

--- Dry Comal Creek Tributary 13.g01 (geometry) --- (continued)

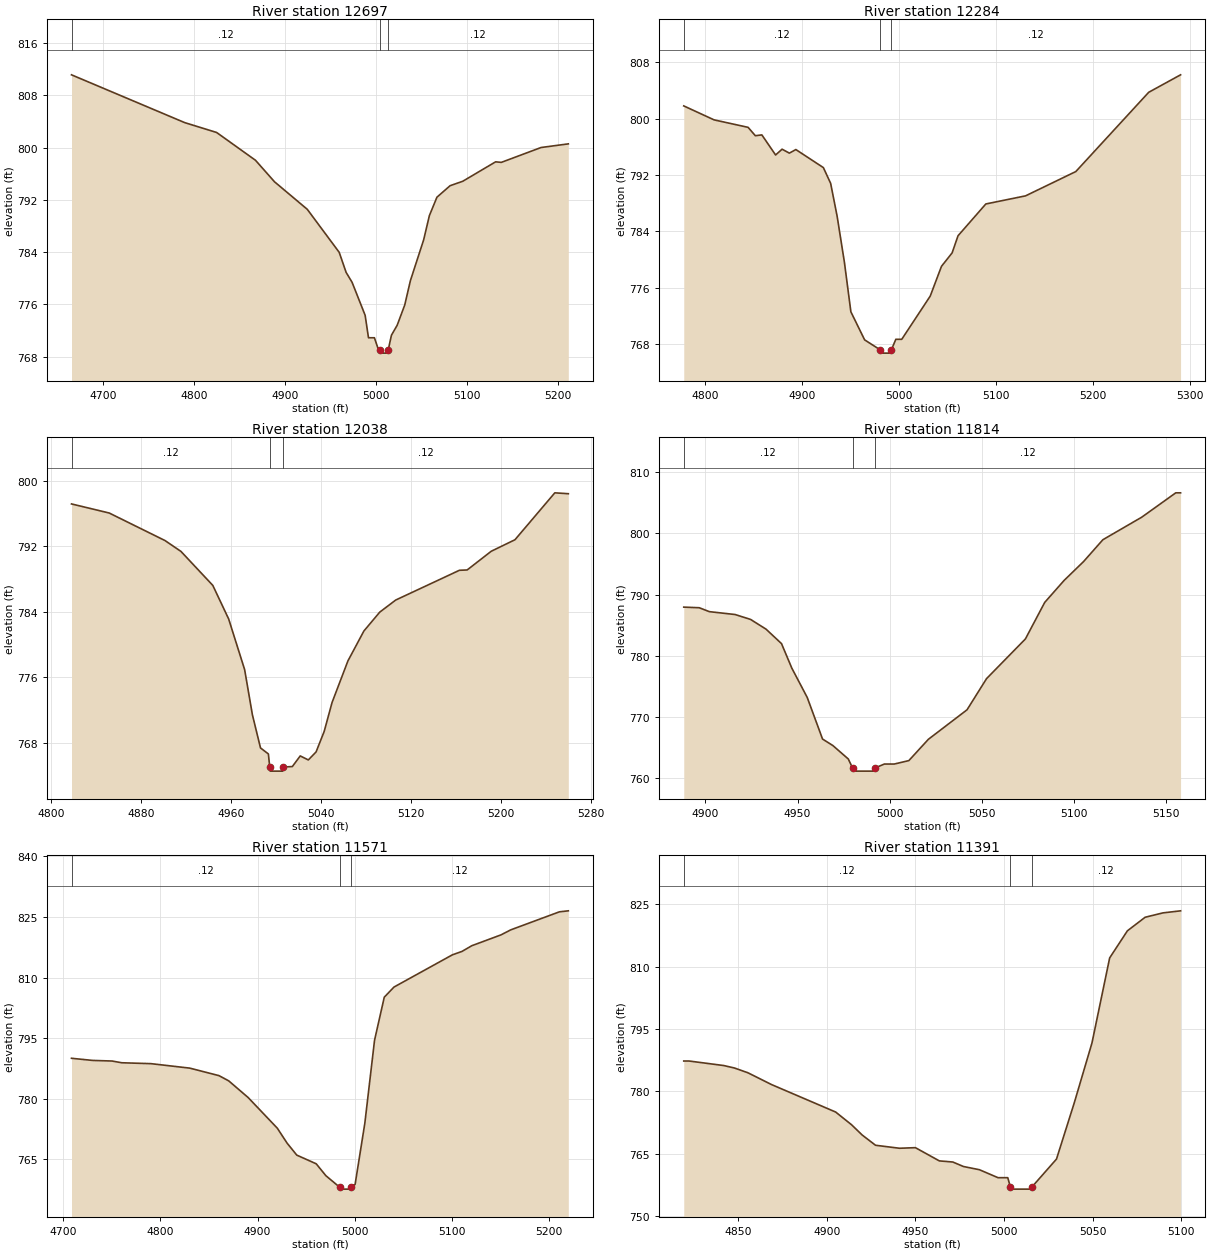
Type RM Length L Ch R = 1 ,12697   ,413,413,413
BEGIN DESCRIPTION:
Dry Comal Creek Tributary 13 20.0
END DESCRIPTION:
XS GIS Cut Line= 3
      2218322.36      13795256.9        2218075.       13795475.
      2217944.72     13795647.56
#Sta/Elev= 30
  4665.4  811.12  4789.8  803.81  4824.9   802.3  4867.6  798.05  4888.5  794.76
  4924.5  790.55  4959.6  783.97  4967.2   780.9  4973.8  779.37  4988.1  774.34
  4991.8   770.9  4998.3   770.9  5002.5  769.17    5004  769.05  5004.5  768.55
    5013  768.55  5013.5  769.05    5017  771.29  5023.3  772.81  5031.6   775.9
  5037.9  779.66  5052.4  785.87  5058.7  789.58    5067   792.4  5081.5  794.16
  5095.4  794.84  5131.5  797.81  5137.8  797.73  5181.4     800  5211.4  800.56
#Mann= 3 ,-1 , 0
  4665.4     .12       0    5004     .05       0  5013.5     .12       0
Bank Sta=5004,5013.5
XS Rating Curve= 0 ,0
Exp/Cntr=0.3,0.1

Type RM Length L Ch R = 1 ,12284   ,246,246,246
BEGIN DESCRIPTION:
Dry Comal Creek Tributary 13 19.0
END DESCRIPTION:
XS GIS Cut Line= 3
      2217973.38     13795009.52        2217825.       13795175.
      2217559.61     13795293.25
#Sta/Elev= 30
  4777.7  801.81    4809  799.83  4844.1  798.77  4851.6  797.58  4858.3   797.7
  4872.5  794.85  4879.2  795.67  4886.7  795.11  4893.4  795.62  4921.8  793.06
  4929.3  790.83    4936  786.17  4943.5  779.65  4950.2   772.6  4964.4  768.62
  4980.1  767.24  4980.6  766.74  4991.6  766.74  4992.1  767.24  4996.6   768.7
  5002.7   768.7  5032.1  774.83  5043.7  779.05  5054.7  780.96  5060.8  783.39
  5089.5   787.9  5130.5  789.05  5182.4   792.5  5257.6  803.74  5290.5  806.22
#Mann= 3 ,-1 , 0
  4777.7     .12       0  4980.1     .05       0  4992.1     .12       0
Bank Sta=4980.1,4992.1
XS Rating Curve= 0 ,0
Exp/Cntr=0.3,0.1

Type RM Length L Ch R = 1 ,12038   ,224,224,224
BEGIN DESCRIPTION:
X18984
END DESCRIPTION:
XS GIS Cut Line= 2
      2217810.27     13794852.78      2217502.93     13795169.87
#Sta/Elev= 30
  4818.2   797.2  4851.7  796.09  4901.3  792.72  4915.5  791.39  4943.8  787.23
  4957.9  783.12  4972.1  776.92    4979  771.39  4986.2  767.34  4993.2   766.6
  4994.4     765  4994.9   764.5  5005.9   764.5  5006.4     765  5014.5  765.06
  5021.5  766.36  5028.7  765.87  5035.6  766.85  5042.8  769.36  5049.8   772.9
  5063.9  777.99  5078.1  781.65  5092.2  783.96  5106.4  785.44    5163  789.08
  5169.9  789.12  5191.3  791.41  5212.4  792.82  5247.8  798.56  5259.8  798.45
#Mann= 3 ,-1 , 0
  4818.2     .12       0  4994.4     .05       0  5006.4     .12       0
Bank Sta=4994.4,5006.4
XS Rating Curve= 0 ,0
Exp/Cntr=0.3,0.1

Type RM Length L Ch R = 1 ,11814   ,243,243,243
BEGIN DESCRIPTION:
Dry Comal Creek Tributary 13 18.0
END DESCRIPTION:
XS GIS Cut Line= 3
      2217624.97     13794775.01        2217525.       13794825.
      2217374.99       13794875.
#Sta/Elev= 30
  4888.2  787.95  4896.6  787.85  4902.1  787.21  4916.1  786.74  4924.5  785.94
  4932.9  784.35  4941.3  781.99  4946.9  777.99  4955.3  773.18  4963.6   766.4
  4969.2  765.34  4977.6  763.14  4979.9  761.66  4980.4  761.16  4991.5  761.16
    4992  761.66  4997.2  762.32  5002.6  762.32  5010.5  762.88  5021.1  766.36
  5042.1  771.18  5052.7  776.27  5073.8  782.75  5084.3  788.72  5094.8   792.3
  5105.4  795.39  5115.9  798.96    5137  802.64  5155.5  806.62  5158.1  806.62
#Mann= 3 ,-1 , 0
  4888.2     .12       0  4979.9     .05       0    4992     .12       0
Bank Sta=4979.9,4992
XS Rating Curve= 0 ,0
Exp/Cntr=0.3,0.1

Type RM Length L Ch R = 1 ,11571   ,180,180,180
BEGIN DESCRIPTION:
X18981
END DESCRIPTION:
XS GIS Cut Line= 2
      2217676.73     13794636.86      2217165.75     13794632.04
#Sta/Elev= 30
  4708.6  790.01  4730.3  789.48  4750.3  789.33  4760.3   788.9  4790.3  788.68
  4830.3  787.57  4860.3  785.71  4870.3  784.42  4890.3  780.29  4920.3   772.7
  4930.3  769.02  4940.3  766.04  4960.3  763.89  4970.3  760.93  4984.3  758.12
  4984.8  757.62  4995.9  757.62  4996.4  758.12  5000.3  758.79  5010.3  773.92
  5020.3  794.48  5030.3  805.13  5040.3  807.64  5100.3  815.61  5110.3  816.47
  5120.3  817.87  5150.4  820.56  5160.4   821.8  5210.4  826.26  5219.6  826.51
#Mann= 3 ,-1 , 0
  4708.6     .12       0  4984.3     .05       0  4996.4     .12       0
Bank Sta=4984.3,4996.4
XS Rating Curve= 0 ,0
Exp/Cntr=0.3,0.1

Type RM Length L Ch R = 1 ,11391   ,192,192,192
BEGIN DESCRIPTION:
Dry Comal Creek Tributary 13 17.0
END DESCRIPTION:
XS GIS Cut Line= 3
      2217575.02     13794575.01        2217425.       13794475.
        2217325.       13794475.
#Sta/Elev= 30
  4819.3  787.27  4822.3  787.27  4841.9  786.18  4847.9  785.59  4855.4  784.46
  4868.9  781.59    4905     775    4914  771.93    4920  769.46  4927.5  767.01
    4941  766.29    4950  766.43  4963.5  763.25  4971.1  762.98  4977.1   761.9
  4986.1  761.13  4996.6  759.21  5002.1  759.21  5003.6  756.96  5004.1  756.46
  5015.2  756.46  5015.7  756.96  5029.6  763.69  5039.6  777.18  5049.6  791.59
  5059.6  812.07  5069.6  818.58  5079.6  821.84  5089.6  822.89  5099.6  823.39
#Mann= 3 ,-1 , 0
  4819.3     .12       0  5003.6     .05       0  5015.7     .12       0
Bank Sta=5003.6,5015.7
XS Rating Curve= 0 ,0
Exp/Cntr=0.3,0.1

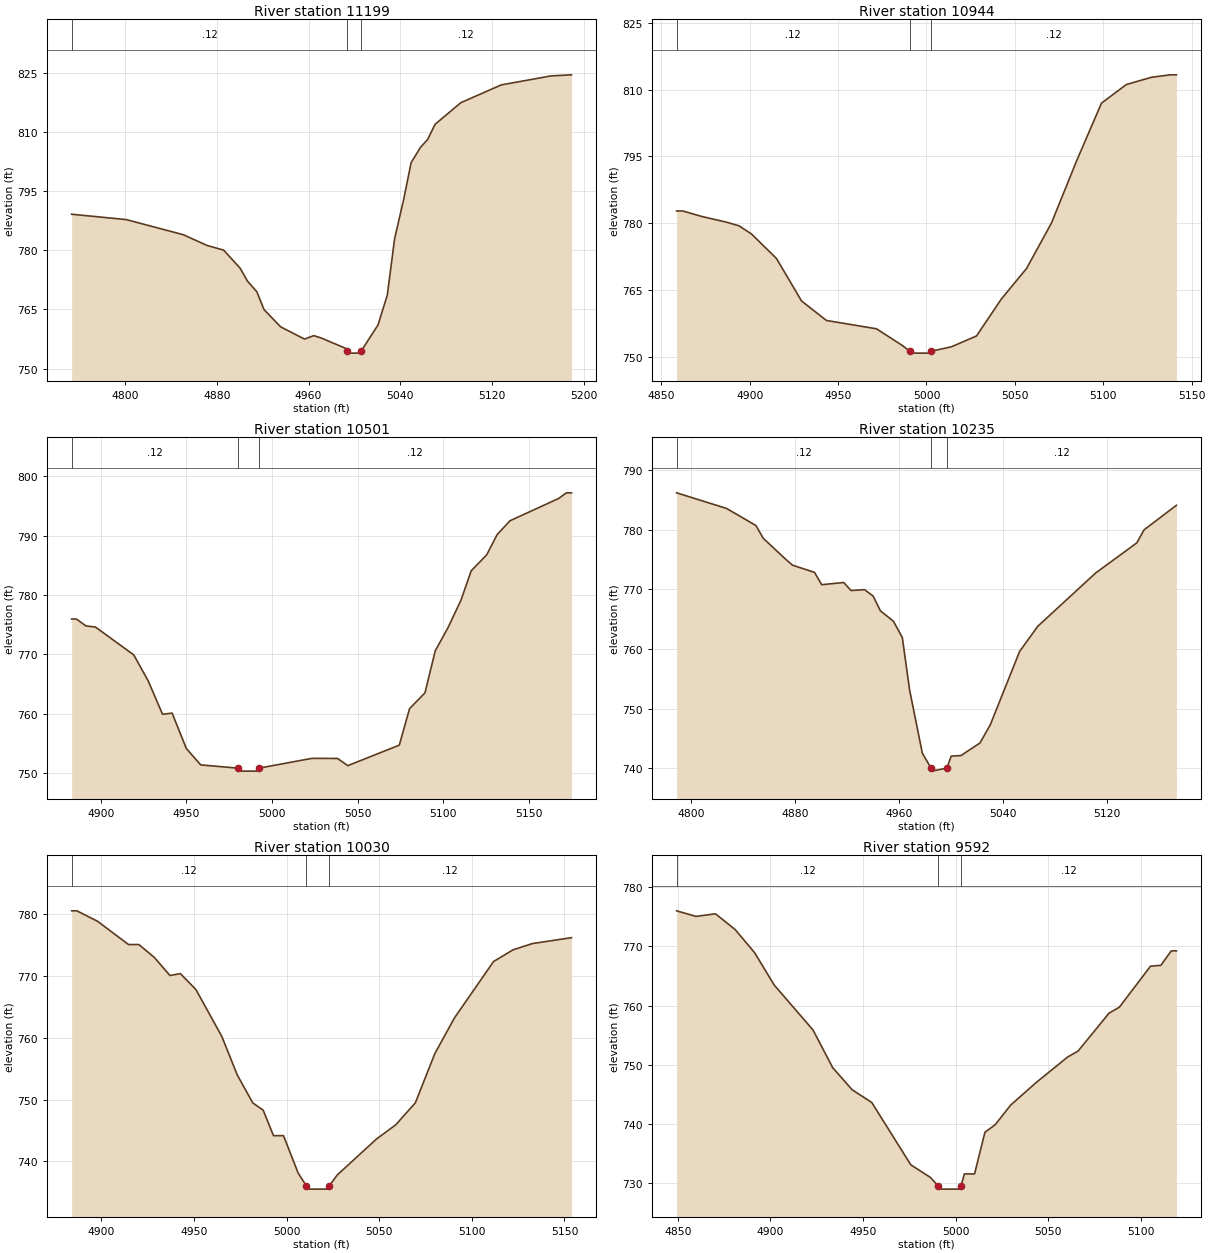
Type RM Length L Ch R = 1 ,11199   ,255,255,255
BEGIN DESCRIPTION:
X18982
END DESCRIPTION:
XS GIS Cut Line= 2
       2217753.9     13794492.26      2217411.57     13794222.25
#Sta/Elev= 30
  4753.4  789.17    4801  787.81  4850.7  783.98  4871.5  781.25    4886  780.06
  4900.4  775.46  4906.8  772.17  4914.9  769.52  4921.2  764.97  4935.7  760.59
  4956.5  757.48  4964.6  758.36  4970.9  757.78  4993.4  755.01  4993.8  754.42
  4994.3  753.92  5005.4  753.92  5005.9  754.42  5020.6  761.05  5028.7  768.61
  5035.1  782.93  5043.1  793.05  5049.5  802.26  5057.6  806.12  5063.9  808.14
  5070.4  811.99  5092.8  817.47  5128.1  821.99  5171.4  824.27  5189.4  824.55
#Mann= 3 ,-1 , 0
  4753.4     .12       0  4993.8     .05       0  5005.9     .12       0
Bank Sta=4993.8,5005.9
XS Rating Curve= 0 ,0
Exp/Cntr=0.3,0.1

Type RM Length L Ch R = 1 ,10944   ,443,443,443
BEGIN DESCRIPTION:
Dry Comal Creek Tributary 13 16.0
END DESCRIPTION:
XS GIS Cut Line= 3
      2217874.98     13794324.98        2217775.       13794225.
      2217675.02     13794125.02
#Sta/Elev= 27
  4858.6  782.78  4862.1  782.78  4872.7  781.56  4886.9  780.26  4893.9  779.46
    4901  777.61  4915.1  772.14  4929.3   762.6  4943.4  758.22  4971.7  756.36
  4985.9  752.73  4990.4   751.4  4990.9   750.9    5002   750.9  5002.5   751.4
  5003.5   751.4  5014.1  752.32  5028.3  754.75  5042.4  763.06  5056.6  769.88
  5070.7  780.07  5084.9  793.99    5099  806.96  5113.1  811.14  5127.3  812.76
  5137.9  813.31  5141.4  813.31
#Mann= 3 ,-1 , 0
  4858.6     .12       0  4990.4     .05       0  5002.5     .12       0
Bank Sta=4990.4,5002.5
XS Rating Curve= 0 ,0
Exp/Cntr=0.3,0.1

Type RM Length L Ch R = 1 ,10501   ,266,266,266
BEGIN DESCRIPTION:
Dry Comal Creek Tributary 13 15.0
END DESCRIPTION:
XS GIS Cut Line= 3
      2218224.98     13794174.96        2218175.       13794075.
      2218025.03     13793975.02
#Sta/Elev= 30
    4883  775.94  4885.8  775.94  4891.3  774.79  4896.9  774.59  4919.3  769.89
  4927.7  765.52  4936.1  759.89  4941.7  760.08    4950  754.11  4958.4  751.35
  4980.3   750.8  4980.8   750.3  4991.9   750.3  4992.4   750.8  5023.3  752.45
  5038.3  752.44  5044.3  751.22  5074.4  754.68  5080.4  760.84  5089.4   763.5
  5095.4  770.58  5102.9  774.51  5110.4   779.1  5116.4  784.07  5125.5  786.78
  5131.5  790.15    5139   792.5  5167.5  796.27    5172  797.22    5175  797.22
#Mann= 3 ,-1 , 0
    4883     .12       0  4980.3     .05       0  4992.4     .12       0
Bank Sta=4980.3,4992.4
XS Rating Curve= 0 ,0
Exp/Cntr=0.3,0.1

Type RM Length L Ch R = 1 ,10235   ,205,205,205
BEGIN DESCRIPTION:
X18983
END DESCRIPTION:
XS GIS Cut Line= 2
      2218486.61     13794145.12      2218318.37     13793799.04
#Sta/Elev= 30
  4788.9  786.21  4827.4  783.59    4850  780.72  4855.7  778.56  4872.5  775.14
  4878.1  774.07  4895.1  772.86  4900.6  770.79  4917.6  771.16  4923.2  769.81
  4933.6  769.96  4940.2  768.89  4945.8  766.41  4955.8  764.67  4962.7  761.92
  4968.3  753.11  4978.1  742.52  4984.8     740  4985.3   739.5    4997     740
  5000.3  742.01  5007.9  742.12  5022.5  744.23  5030.4  747.27    5053  759.59
    5067  763.82  5111.5  772.75  5143.2  777.81  5148.8     780  5173.7  784.12
#Mann= 3 ,-1 , 0
  4788.9     .12       0  4984.8     .05       0    4997     .12       0
Bank Sta=4984.8,4997
XS Rating Curve= 0 ,0
Exp/Cntr=0.3,0.1

Type RM Length L Ch R = 1 ,10030   ,438,438,438
BEGIN DESCRIPTION:
Dry Comal Creek Tributary 13 14.0
END DESCRIPTION:
XS GIS Cut Line= 3
        2218625.       13793975.        2218575.       13793875.
        2218525.     13793725.01
#Sta/Elev= 30
  4883.9  780.51  4886.7  780.51  4897.9  778.82  4914.6  775.06  4920.2  775.06
  4928.6  772.96    4937  770.05  4942.6  770.36    4951  767.78    4965   760.2
  4973.3  753.99  4981.7  749.46  4987.3  748.29  4992.9  744.16  4998.3  744.16
  5006.2  738.11  5010.7  736.02  5011.2  735.52  5022.4  735.52  5022.9  736.02
  5027.3   737.8  5048.4   743.6  5058.9  745.92  5069.5  749.48    5080  757.43
  5090.6   763.2  5111.7  772.31  5122.2   774.2  5132.7  775.22  5153.8  776.17
#Mann= 3 ,-1 , 0
  4883.9     .12       0  5010.7     .05       0  5022.9     .12       0
Bank Sta=5010.7,5022.9
XS Rating Curve= 0 ,0
Exp/Cntr=0.3,0.1

Type RM Length L Ch R = 1 ,9592    ,454,454,454
BEGIN DESCRIPTION:
Dry Comal Creek Tributary 13 13.0
END DESCRIPTION:
XS GIS Cut Line= 3
      2218924.99     13793724.96        2218875.       13793575.
      2218774.98     13793524.99
#Sta/Elev= 30
  4849.3  776.01  4859.8  775.07  4870.3  775.51  4880.9  772.86  4891.4  768.96
    4902  763.49    4923  755.88  4933.6  749.53  4944.1   745.8  4954.7  743.65
  4975.8  733.12  4986.3  731.01  4990.7  729.52  4991.2  729.02  5002.4  729.02
  5002.9  729.52  5004.7  731.59  5010.2  731.59  5015.8  738.62  5021.4  739.91
  5029.7  743.21  5043.7  747.08  5060.5  751.33  5066.1  752.33  5082.8  758.73
  5088.4  759.74  5105.2  766.66  5110.8  766.81  5116.4  769.25  5119.2  769.25
#Mann= 3 ,-1 , 0
  4849.3     .12       0  4990.7     .05       0  5002.9     .12       0
Bank Sta=4990.7,5002.9
XS Rating Curve= 0 ,0
Exp/Cntr=0.3,0.1

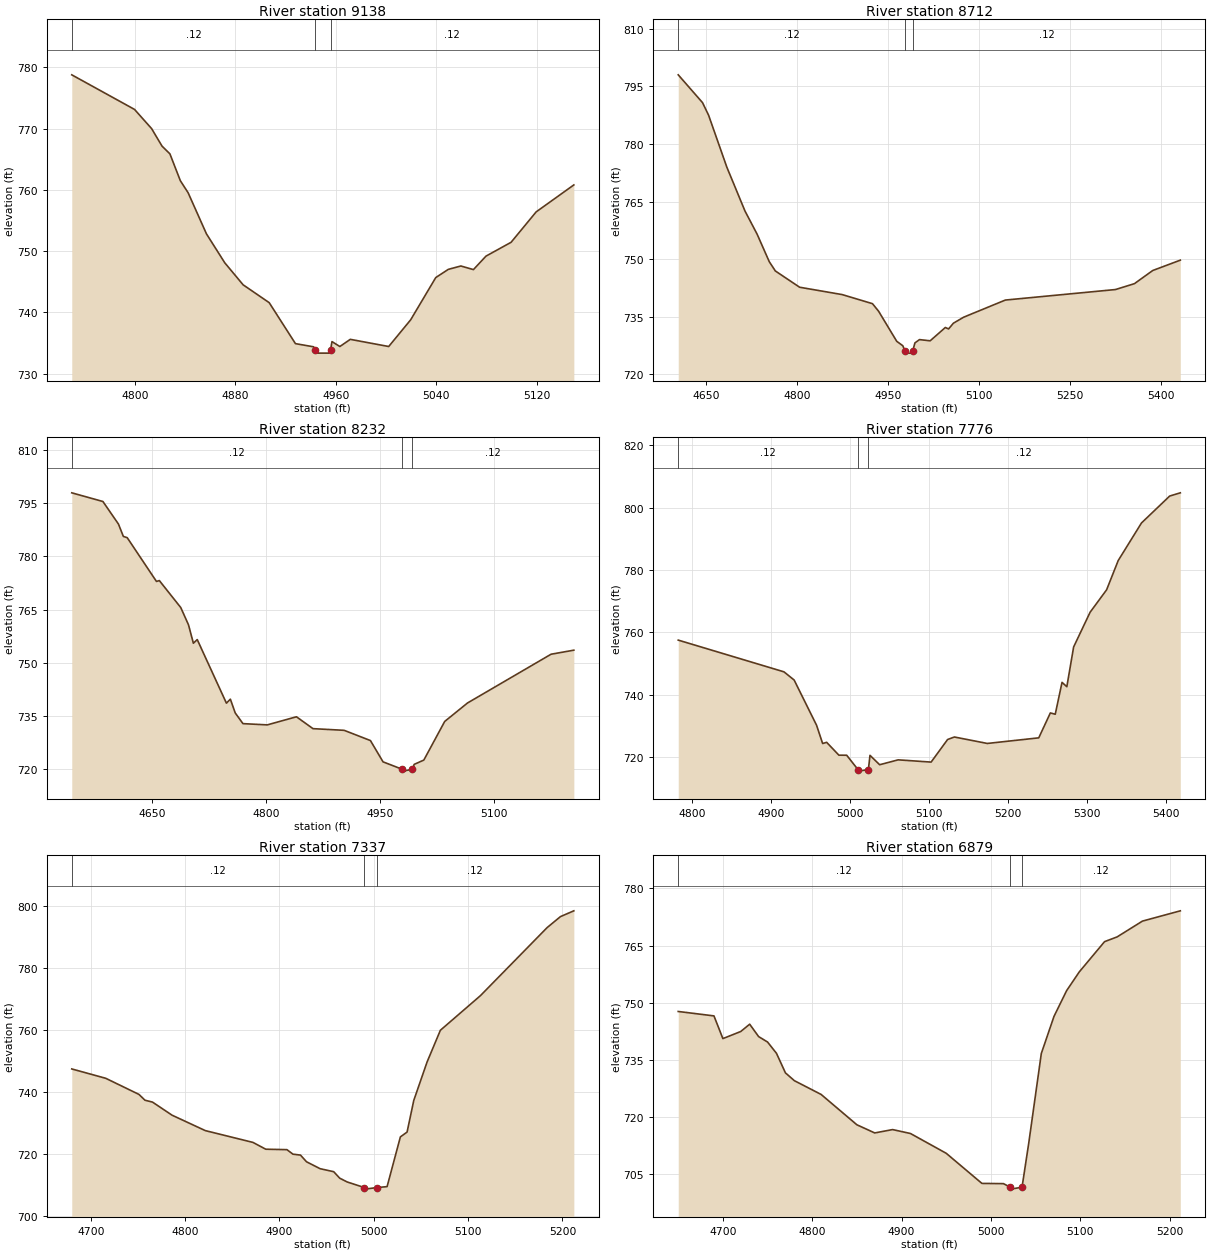
Type RM Length L Ch R = 1 ,9138    ,426,426,426
BEGIN DESCRIPTION:
Dry Comal Creek Tributary 13 12.0
END DESCRIPTION:
XS GIS Cut Line= 3
      2219325.02     13793375.02        2219125.       13793225.
      2218975.03       13793225.
#Sta/Elev= 30
  4749.6  778.79  4799.6  773.14  4813.2  770.01  4821.5  767.15  4827.8  765.88
  4836.1   761.5  4842.3  759.53  4856.9  752.82  4871.5  748.09  4886.1   744.5
  4906.9  741.58  4927.8  734.89  4942.3  734.37  4943.5  733.84    4944  733.34
  4955.3  733.34  4955.8  733.84  4956.9  735.22  4963.2  734.42  4971.5  735.59
  5002.1  734.42  5019.6  738.78  5039.6  745.68  5049.6  747.02  5059.6  747.57
  5069.6  746.98  5079.6  749.18  5099.6  751.44  5119.6  756.41  5149.6  760.81
#Mann= 3 ,-1 , 0
  4749.6     .12       0  4943.5     .05       0  4955.8     .12       0
Bank Sta=4943.5,4955.8
XS Rating Curve= 0 ,0
Exp/Cntr=0.3,0.1

Type RM Length L Ch R = 1 ,8712    ,480,480,480
BEGIN DESCRIPTION:
Dry Comal Creek Tributary 13 11.0
END DESCRIPTION:
XS GIS Cut Line= 3
      2219725.01       13792875.        2219325.       13792875.
      2218925.01     13793024.99
#Sta/Elev= 30
  4604.6  798.01  4644.6  790.77  4654.6   787.5  4684.6     774  4714.6  762.53
  4734.6   756.5  4754.6  749.34  4764.6  746.93  4804.6  742.69  4874.6  740.78
  4924.6  738.41  4934.6  736.47  4964.6  728.61  4974.6  727.45  4978.4  726.03
  4978.9  725.53  4990.3  725.53  4990.8  726.03  4994.6   728.2  5002.1  729.05
  5019.7  728.74  5044.7  732.21    5050  731.83    5058  733.33  5074.9  734.89
  5143.5  739.35    5325  742.09  5356.2  743.62  5386.4  747.05  5431.8  749.74
#Mann= 3 ,-1 , 0
  4604.6     .12       0  4978.4     .05       0  4990.8     .12       0
Bank Sta=4978.4,4990.8
XS Rating Curve= 0 ,0
Exp/Cntr=0.3,0.1

Type RM Length L Ch R = 1 ,8232    ,456,456,456
BEGIN DESCRIPTION:
Dry Comal Creek Tributary 13 10.0
END DESCRIPTION:
XS GIS Cut Line= 3
      2219775.05     13792525.01        2219325.       13792425.
      2219125.02       13792425.
#Sta/Elev= 30
  4543.9  797.84  4584.9   795.4  4605.4  789.04  4611.8  785.58  4616.9  785.22
  4655.4  772.91  4659.2  773.15  4687.4  765.56  4697.6  760.69    4704  755.53
  4709.1  756.55  4747.5  738.66  4752.7  739.79  4759.1  735.91  4769.3   732.9
  4801.3  732.55  4839.7  734.83  4861.5  731.49  4902.5  731.02  4937.1  728.14
  4953.7  722.15  4979.2  720.04  4979.7  719.54  4992.3  720.04  4994.7  721.44
  5007.4  722.65  5034.9  733.52  5064.9  738.71  5174.9  752.43  5204.9  753.57
#Mann= 3 ,-1 , 0
  4543.9     .12       0  4979.2     .05       0  4992.3     .12       0
Bank Sta=4979.2,4992.3
XS Rating Curve= 0 ,0
Exp/Cntr=0.3,0.1

Type RM Length L Ch R = 1 ,7776    ,439,439,439
BEGIN DESCRIPTION:
Dry Comal Creek Tributary 13 9.0
END DESCRIPTION:
XS GIS Cut Line= 3
      2219575.02       13792075.        2219375.       13792025.
      2219024.99       13791775.
#Sta/Elev= 30
    4782  757.54    4916  747.36  4928.9  744.73  4957.3  730.23    4965  724.36
  4970.1  724.74  4985.6  720.62  4995.5   720.6  5009.8     716  5010.3   715.5
    5023     716    5025  720.56  5037.3  717.55  5060.7  719.12  5102.5   718.4
  5123.4  725.65    5132  726.45  5173.7  724.38  5238.9  726.18  5253.6  734.17
  5259.8  733.75  5268.4  743.98  5274.5  742.59  5283.1  755.34    5304  766.49
  5324.9  773.68  5339.6  783.07  5369.1  795.13  5404.8  803.76  5418.3   804.8
#Mann= 3 ,-1 , 0
    4782     .12       0  5009.8     .05       0    5023     .12       0
Bank Sta=5009.8,5023
XS Rating Curve= 0 ,0
Exp/Cntr=0.3,0.1

Type RM Length L Ch R = 1 ,7337    ,458,458,458
BEGIN DESCRIPTION:
Dry Comal Creek Tributary 13 8.0
END DESCRIPTION:
XS GIS Cut Line= 3
      2219524.98     13791874.98        2219325.       13791625.
      2219174.97     13791474.97
#Sta/Elev= 30
  4679.8   747.5  4715.8  744.48    4751  739.28  4757.4   737.4  4765.4  736.79
  4786.2  732.55  4821.4  727.58  4871.9  723.77  4885.5  721.57  4907.9  721.43
  4914.3  719.97  4922.3  719.67  4928.7  717.51  4943.1  715.28  4957.5  714.31
  4963.9  712.21  4971.9  710.98  4990.1  709.18  4990.6  708.68  5003.3  709.18
  5014.1  709.49  5028.2  725.55  5035.3  727.11  5042.4  737.34  5056.5  749.74
  5070.6  759.99  5113.1  771.18  5183.8  793.16  5197.9   796.7  5212.1  798.57
#Mann= 3 ,-1 , 0
  4679.8     .12       0  4990.1     .05       0  5003.3     .12       0
Bank Sta=4990.1,5003.3
XS Rating Curve= 0 ,0
Exp/Cntr=0.3,0.1

Type RM Length L Ch R = 1 ,6879    ,477,477,477
BEGIN DESCRIPTION:
Dry Comal Creek Tributary 13 7.0
END DESCRIPTION:
XS GIS Cut Line= 3
        2219675.     13791774.98        2219675.       13791425.
      2219525.01     13791275.01
#Sta/Elev= 30
    4650   747.7    4690  746.54    4700  740.58    4720  742.45    4730  744.36
    4740  741.11    4750  739.68    4760  736.72    4770  731.59    4780  729.54
    4810  725.92    4850  717.96    4870  715.82    4890   716.7    4910  715.67
    4950  710.48    4990  702.57  5014.1  702.51  5021.7  701.57  5022.2  701.07
  5034.9  701.57  5042.4  713.11  5056.5  736.68  5070.7  746.42  5084.8  753.16
    5099  758.09  5127.3  766.03  5141.4  767.28  5169.7  771.42  5212.1  774.12
#Mann= 3 ,-1 , 0
    4650     .12       0  5021.7     .05       0  5034.9     .12       0
Bank Sta=5021.7,5034.9
XS Rating Curve= 0 ,0
Exp/Cntr=0.3,0.1

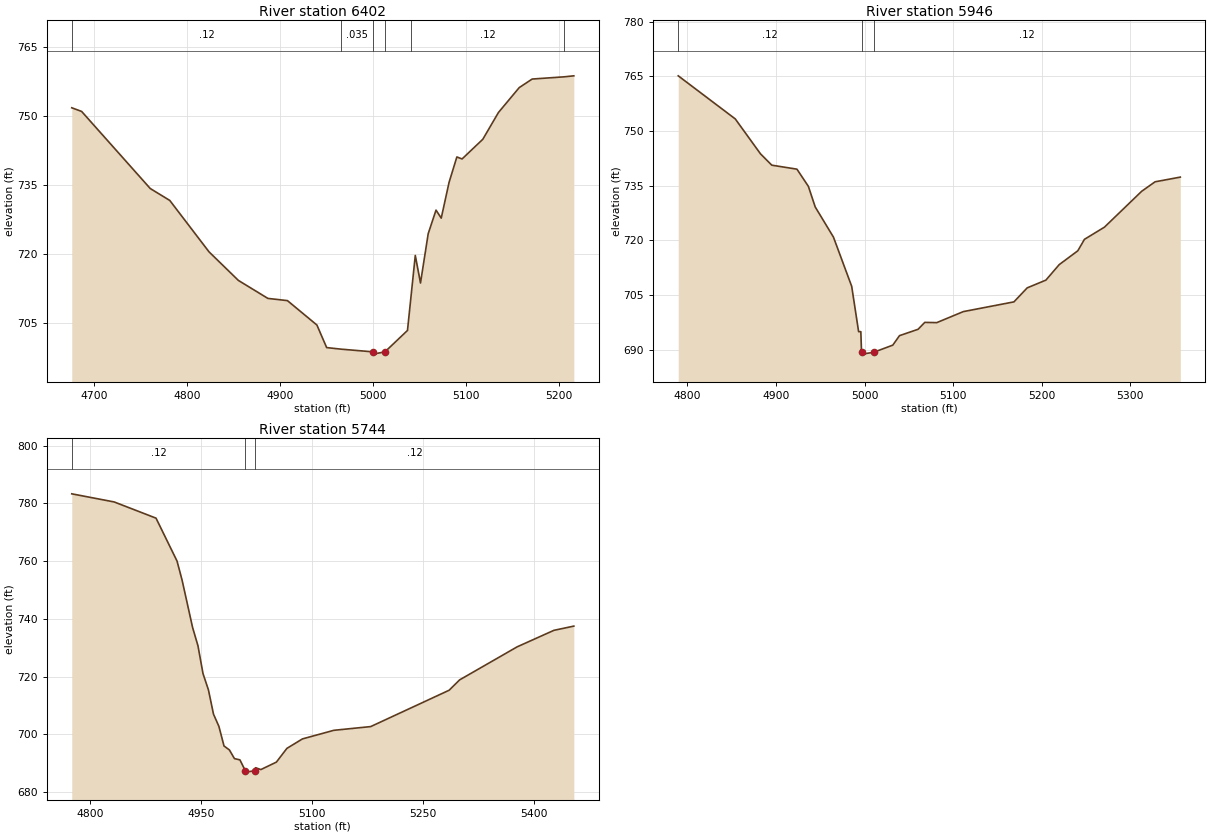
Type RM Length L Ch R = 1 ,6402    ,456,456,456
BEGIN DESCRIPTION:
Dry Comal Creek Tributary 13 6.0
END DESCRIPTION:
XS GIS Cut Line= 3
      2220024.99     13791825.03        2220125.       13791525.
      2220024.98     13791324.97
#Sta/Elev= 30
    4676  751.83  4686.6  751.04  4760.4   734.3  4781.4  731.71  4823.6  720.55
  4855.2  714.34  4886.9  710.44  4907.9  709.96  4939.6  704.66  4950.1  699.76
    4966  699.41  4999.6  698.84  5000.1  698.34  5012.8  698.84    5037  703.48
  5041.3  711.82  5045.4  719.77    5051  713.79  5059.3   724.5  5067.7  729.61
  5073.3  727.87  5081.7  735.62  5090.1  741.15  5095.7  740.72    5118  744.99
  5134.8   750.8  5157.2  756.22  5171.1  758.07  5205.3  758.55  5215.9  758.77
#Mann= 6 ,-1 , 0
    4676     .12       0    4966    .035       0  4999.6    .035       0
  5012.8    .035       0  5041.3     .12       0  5205.3    .035       0
Bank Sta=4999.6,5012.8
XS Rating Curve= 0 ,0
Exp/Cntr=0.3,0.1

Type RM Length L Ch R = 1 ,5946    ,202,202,202
BEGIN DESCRIPTION:
Dry Comal Creek Tributary 13 5.0
END DESCRIPTION:
XS GIS Cut Line= 3
        2220575.     13791874.99        2220525.       13791675.
        2220325.       13791375.
#Sta/Elev= 30
  4789.7  765.17  4854.1  753.33  4882.5  743.76  4895.3  740.63  4923.7  739.53
  4936.6  734.81  4944.3  729.16  4964.9  720.87  4985.5  707.34  4993.3   694.9
  4995.8   694.9  4996.6  689.23  4997.1  688.73  5010.2  689.23  5031.9   691.2
  5039.4   693.8  5060.4  695.55    5068  697.45  5081.5  697.38  5111.5  700.41
  5168.6  703.08  5183.6  706.93  5204.7  709.06  5219.7  713.31  5240.7  717.11
  5248.2  720.26  5270.8  723.61  5312.8  733.46  5327.9  736.06  5356.4  737.35
#Mann= 3 ,-1 , 0
  4789.7     .12       0  4996.6     .05       0  5010.2     .12       0
Bank Sta=4996.6,5010.2
XS Rating Curve= 0 ,0
Exp/Cntr=0.3,0.1

Type RM Length L Ch R = 1 ,5744    ,254,254,254
BEGIN DESCRIPTION:
X18980
END DESCRIPTION:
XS GIS Cut Line= 2
      2220872.84     13791778.15      2220376.35     13791315.41
#Sta/Elev= 30
    4775   783.3  4832.3  780.49  4888.9  774.88  4917.3  760.02  4924.1  753.45
  4938.3  737.06  4945.6  730.68  4952.4  721.06  4959.8  715.36  4966.6     707
  4973.9  702.79  4980.8  695.99  4988.1  694.62  4994.9  691.62  5002.3  691.19
  5009.6  687.44  5010.1  686.94  5023.2  687.44  5023.3  688.47  5030.6  687.82
  5051.6  690.41  5065.8  695.16  5086.8  698.44  5129.3  701.42  5179.1  702.71
  5285.1  715.29  5299.3  718.88    5377  730.31  5426.8  736.04  5453.7   737.5
#Mann= 3 ,-1 , 0
    4775     .12       0  5009.6     .05       0  5023.2     .12       0
Bank Sta=5009.6,5023.2
XS Rating Curve= 0 ,0
Exp/Cntr=0.3,0.1