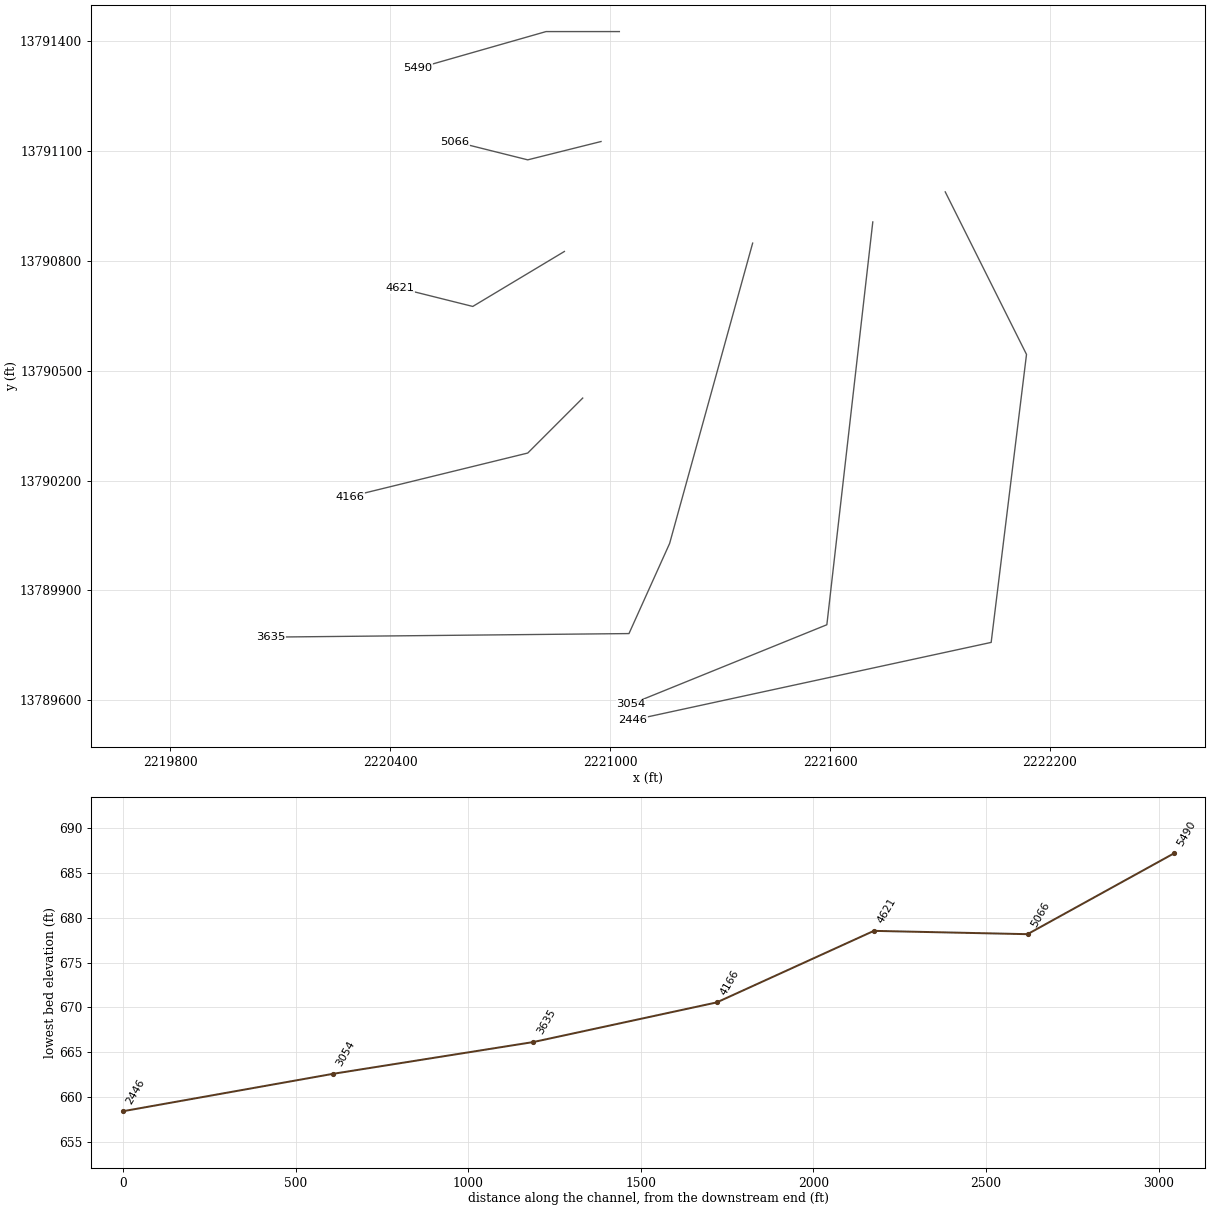
HEC-RAS study Dry Comal Creek Tributary 13.prj: Dry Comal Creek Tributary 13 Base Level Engineering

--- Dry Comal Creek Tributary 13.g01 (geometry) --- (continued)

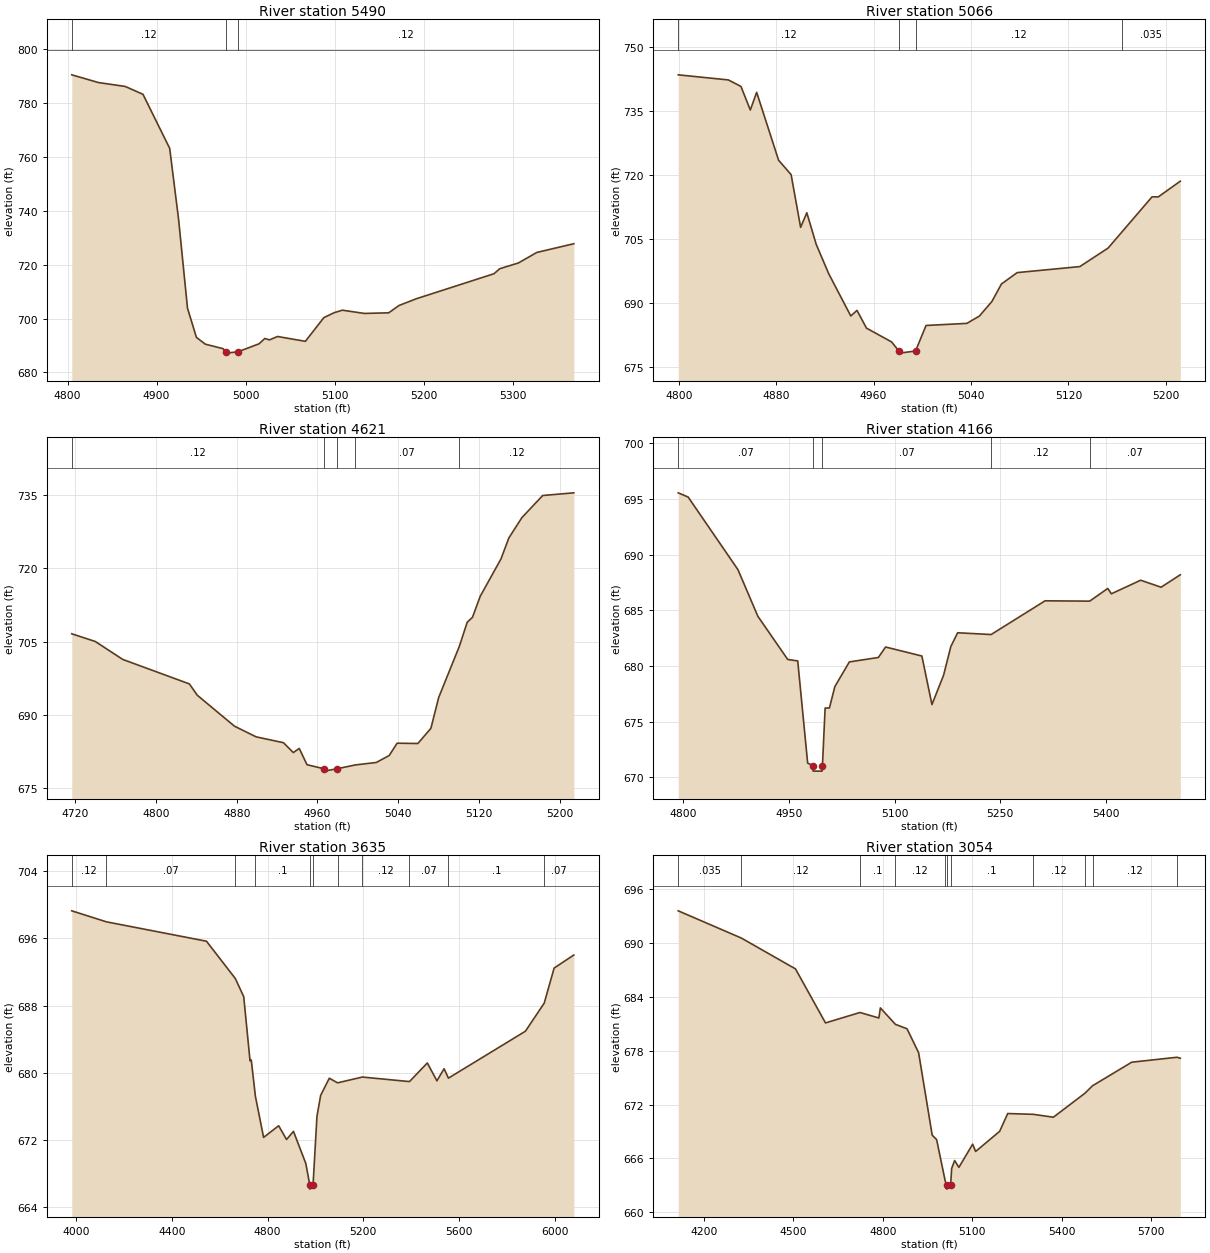
Type RM Length L Ch R = 1 ,5490    ,424,424,424
BEGIN DESCRIPTION:
Dry Comal Creek Tributary 13 4.0
END DESCRIPTION:
XS GIS Cut Line= 3
      2221024.96       13791425.        2220825.       13791425.
      2220474.97     13791324.99
#Sta/Elev= 30
  4804.7  790.58  4834.7  787.71  4864.7  786.27  4884.7  783.34  4914.7  763.27
  4924.7  736.89  4934.7  703.89  4944.7  693.05  4954.7  690.51  4974.7  688.83
  4977.9  687.68  4978.4  687.18  4991.5  687.68  5015.1  690.65  5021.6  692.62
  5026.8   692.1  5035.9  693.36  5067.1  691.56  5087.9  700.38  5099.6  702.22
  5108.7  703.13  5133.4  701.93  5160.7  702.15  5172.4  704.89  5191.9   707.4
    5279  716.68  5285.5  718.55  5306.3  720.66  5327.1  724.59  5368.7  727.83
#Mann= 3 ,-1 , 0
  4804.7     .12       0  4977.9     .05       0  4991.5     .12       0
Bank Sta=4977.9,4991.5
XS Rating Curve= 0 ,0
Exp/Cntr=0.3,0.1

Type RM Length L Ch R = 1 ,5066    ,445,445,445
BEGIN DESCRIPTION:
Dry Comal Creek Tributary 13 3.0
END DESCRIPTION:
XS GIS Cut Line= 3
      2220974.95     13791124.99        2220775.       13791075.
      2220574.96     13791125.01
#Sta/Elev= 30
  4799.6  743.57  4840.8  742.37  4851.1  740.84  4858.8   735.3    4864  739.46
    4882  723.51  4892.3  720.12  4900.1  707.73  4905.2  711.15  4912.9  703.74
  4923.2  696.82  4941.3   686.9  4946.4  688.21  4954.2  684.04  4974.8  680.81
  4980.8  678.67  4981.3  678.17  4994.5  678.67  5003.1  684.67  5036.6  685.16
  5046.9  686.88  5057.2  690.31    5065  694.41  5077.9  697.09  5129.4  698.51
  5152.6  702.86  5164.3  706.76  5188.7   714.9  5193.8  714.88  5211.9  718.58
#Mann= 4 ,-1 , 0
  4799.6     .12       0  4980.8     .05       0  4994.5     .12       0
  5164.3    .035       0
Bank Sta=4980.8,4994.5
XS Rating Curve= 0 ,0
Exp/Cntr=0.3,0.1

Type RM Length L Ch R = 1 ,4621    ,455,455,455
BEGIN DESCRIPTION:
Dry Comal Creek Tributary 13 2.0
END DESCRIPTION:
XS GIS Cut Line= 3
        2220875.       13790825.        2220625.       13790675.
        2220425.       13790725.
#Sta/Elev= 30
  4716.5  706.62  4739.8  705.05    4767  701.38  4833.1  696.37  4840.9  694.06
  4877.8  687.73  4899.2  685.55  4926.4  684.35  4936.1  682.33    4942  683.18
  4949.7  679.85  4966.2  679.04  4966.7  678.54  4979.9  679.04  4997.4   679.8
  5018.4  680.31  5031.2  681.74    5039  684.25  5059.6  684.19  5072.5  687.29
  5080.2  693.58  5100.7  704.06  5108.5  708.98  5113.7  709.98  5121.4  714.29
    5142  721.94  5149.8  726.22  5162.7  730.37  5183.3  734.89  5214.2  735.44
#Mann= 5 ,-1 , 0
  4716.5     .12       0  4966.2     .05       0  4979.9     .12       0
  4997.4     .07       0  5100.7     .12       0
Bank Sta=4966.2,4979.9
XS Rating Curve= 0 ,0
Exp/Cntr=0.3,0.1

Type RM Length L Ch R = 1 ,4166    ,531,531,531
BEGIN DESCRIPTION:
Dry Comal Creek Tributary 13 1.0
END DESCRIPTION:
XS GIS Cut Line= 3
      2220924.98     13790424.98        2220775.       13790275.
      2220288.49     13790155.84
#Sta/Elev= 30
  4792.7  695.56  4806.8  695.18  4877.5  688.66  4905.8  684.47  4948.2  680.59
  4962.4  680.46  4976.5  671.28  4983.8  671.06  4984.3  670.56    4997  670.56
  4997.5  671.06  5001.3  676.23  5007.4  676.23  5015.1  678.15  5035.7  680.37
  5076.9  680.77  5087.2  681.71  5138.7   680.9    5153  676.54  5169.5  679.17
  5179.8  681.75  5189.5  682.99    5237  682.83  5313.7  685.86    5377  685.83
  5402.7  686.97  5407.8  686.49  5449.4  687.71  5478.4  687.08  5505.7   688.2
#Mann= 5 ,-1 , 0
  4792.7     .07       0  4983.8     .05       0  4997.5     .07       0
    5237     .12       0    5377     .07       0
Bank Sta=4983.8,4997.5
XS Rating Curve= 0 ,0
Exp/Cntr=0.3,0.1

Type RM Length L Ch R = 1 ,3635    ,581,581,581
BEGIN DESCRIPTION:
X18979
END DESCRIPTION:
XS GIS Cut Line= 4
      2221388.68     13790847.77      2221162.11     13790028.27
      2221051.24     13789782.41      2220072.63     13789772.77
#Sta/Elev= 30
  3981.7  699.29  4126.4  697.98  4544.8  695.67  4665.5  691.22  4700.5  689.06
  4726.8  681.43    4732  681.53  4749.1  677.23  4783.5   672.3  4846.5  673.69
  4879.4  672.05  4908.4  673.02  4960.2  669.18  4976.5  666.64    4977  666.14
  4990.2  666.64  5006.5  674.79    5022  677.31  5058.2  679.35  5092.8   678.8
  5196.3  679.49  5393.3  678.95  5467.9  681.17  5507.9  679.04  5537.9  680.48
  5556.1  679.36  5877.9  684.95  5956.4  688.29  5997.9  692.47  6080.3  694.03
#Mann= 11 ,-1 , 0
  3981.7     .12       0  4126.4     .07       0  4665.5     .12       0
  4749.1      .1       0  4976.5     .05       0  4990.2      .1       0
  5092.8      .1       0  5196.3     .12       0  5393.3     .07       0
  5556.1      .1       0  5956.4     .07       0
Bank Sta=4976.5,4990.2
XS Rating Curve= 0 ,0
Exp/Cntr=0.3,0.1

Type RM Length L Ch R = 1 ,3054    ,608,608,608
BEGIN DESCRIPTION:
X18978
END DESCRIPTION:
XS GIS Cut Line= 3
      2221716.49      13790905.6      2221591.16     13789806.52
      2221056.53     13789589.78
#Sta/Elev= 30
  4113.8  693.55  4325.4  690.52  4506.9  687.09  4607.5  681.08    4723  682.24
  4786.3  681.63  4791.4  682.75  4841.9  680.92  4880.8  680.43  4919.6  677.77
  4965.2  668.59    4980   668.1  5009.1  663.45  5013.3  663.09  5013.8  662.59
  5027.1  663.09  5030.3  664.88  5040.4  665.77  5054.6  665.01  5100.8  667.59
  5110.8  666.78  5191.3  669.02  5218.3     671  5304.5  670.91  5371.4  670.59
  5477.3  673.26  5502.7  674.09    5634  676.71  5785.6  677.26  5796.9  677.15
#Mann= 11 ,-1 , 0
  4113.8    .035       0  4325.4     .12       0    4723      .1       0
  4841.9     .12       0  5009.1      .1       0  5013.3     .05       0
  5027.1      .1       0  5304.5     .12       0  5477.3      .1       0
  5502.7     .12       0  5785.6     .07       0
Bank Sta=5013.3,5027.1
XS Rating Curve= 0 ,0
Exp/Cntr=0.3,0.1

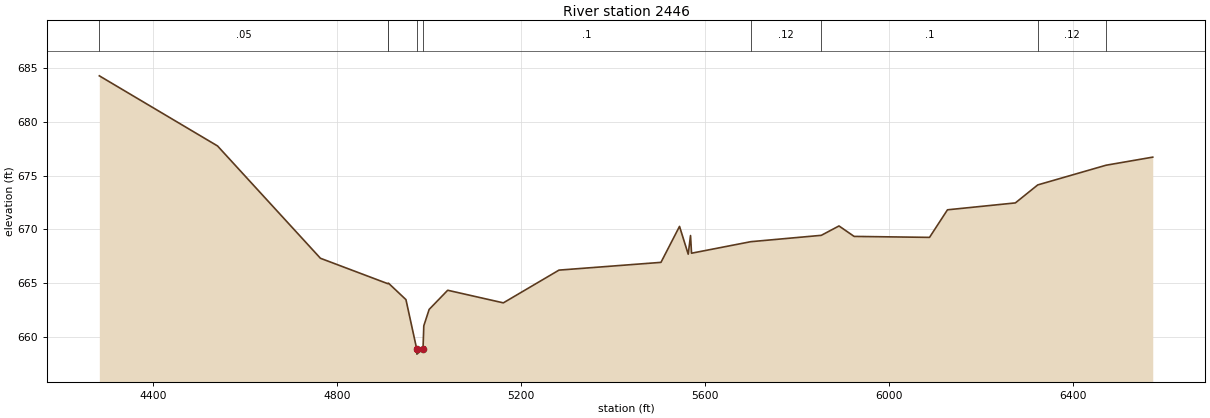
Type RM Length L Ch R = 1 ,2446    ,0,0,0
BEGIN DESCRIPTION:
X18977
END DESCRIPTION:
XS GIS Cut Line= 4
      2221914.15     13790987.59       2222135.9     13790544.08
      2222039.48     13789758.31      2221060.92     13789546.21
#Sta/Elev= 30
    4284  684.26  4540.8  677.75  4764.4  667.32  4910.8  664.96    4912     665
  4912.2  665.01  4950.2  663.48  4973.5  658.92    4974  658.42  4987.3  658.92
    4989  661.05  5000.6  662.57  5040.9  664.35  5161.8  663.18  5282.7  666.22
  5504.3  666.94  5544.6  670.28  5563.5   667.7  5568.5  669.43  5570.7  667.79
  5699.5  668.86  5852.7  669.45  5891.1  670.32    5924  669.35  6087.8  669.26
  6126.8  671.82  6274.3  672.46  6322.9  674.13  6471.4  675.96  6572.8  676.71
#Mann= 10 ,-1 , 0
    4284     .05       0  4910.8      .1       0    4912    .035       0
  4912.2      .1       0  4973.5     .05       0  4987.3      .1       0
  5699.5     .12       0  5852.7      .1       0  6322.9     .12       0
  6471.4     .07       0
Bank Sta=4973.5,4987.3
XS Rating Curve= 0 ,0
Exp/Cntr=0.3,0.1

Chan Stop Cuts=-1
Use User Specified Reach Order=0
Composite Channel Slope=5