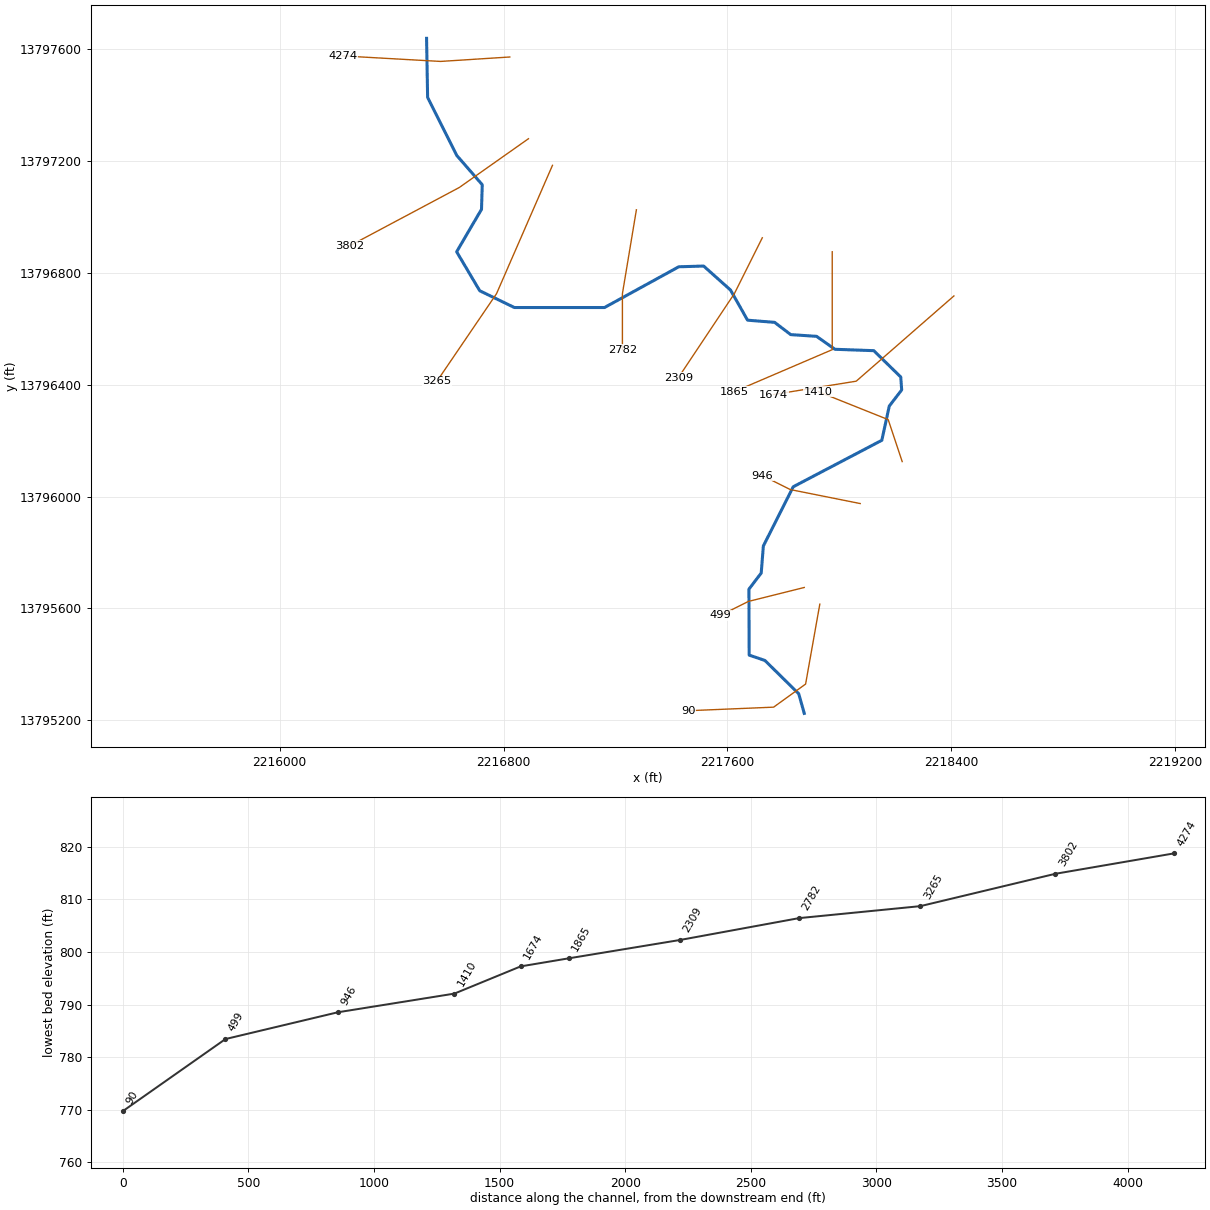
--- Dry Comal Creek Tributary 14.prj (project) ---

Proj Title=Dry Comal Creek Tributary 14 Base Level Engineering
Current Plan=p01
Default Exp/Contr=0.3,0.1
English Units
Geom File=g01
Flow File=f01
Plan File=p01
BEGIN DESCRIPTION:
Dry Comal Creek Tributary 14
END DESCRIPTION:

--- Dry Comal Creek Tributary 14.p01 (plan) ---

Plan Title=Multiple Run
Short Identifier=Multiple
Geom File=g01
Flow File=f01
Subcritical Flow
K Sum by GR= 0
Std Step Tol= 0.01
Critical Tol= 0.01
Num of Std Step Trials= 20
Max Error Tol= 0.3
Flow Tol Ratio= 0.001
Split Flow NTrial= 30
Split Flow Tol= 0.02
Split Flow Ratio= 0.02
Log Output Level= 0
Friction Slope Method= 1
Unsteady Friction Slope Method= 2
Unsteady Bridges Friction Slope Method= 1
Parabolic Critical Depth
Global Vel Dist=  1 , 1 , 1
Global Log Level= 0
CheckData=True
Encroach Param= -1, 0, 0, 0
BEGIN DESCRIPTION:
Multiple Run
END DESCRIPTION:

--- Dry Comal Creek Tributary 14.f01 (steady flow) ---

Flow Title=Multiple
Number of Profiles=7
Profile Names=10-year,25-year,50-year,1pct_min,100-year,1pct_plu,500-year
River Rch & RM= Dry Comal Creek ,Reach-1,4274
     978    1638    2256    1504    3002    5989    5261
Boundary for River Rch & Prof#=Dry Comal Creek ,Reach-1,1
Up Type=0
Dn Type=3
Dn Slope=0.005
Boundary for River Rch & Prof#=Dry Comal Creek ,Reach-1,2
Up Type=0
Dn Type=3
Dn Slope=0.005
Boundary for River Rch & Prof#=Dry Comal Creek ,Reach-1,3
Up Type=0
Dn Type=3
Dn Slope=0.005
Boundary for River Rch & Prof#=Dry Comal Creek ,Reach-1,4
Up Type=0
Dn Type=3
Dn Slope=0.005
Boundary for River Rch & Prof#=Dry Comal Creek ,Reach-1,5
Up Type=0
Dn Type=3
Dn Slope=0.005
Boundary for River Rch & Prof#=Dry Comal Creek ,Reach-1,6
Up Type=0
Dn Type=3
Dn Slope=0.005
Boundary for River Rch & Prof#=Dry Comal Creek ,Reach-1,7
Up Type=0
Dn Type=3
Dn Slope=0.005

--- Dry Comal Creek Tributary 14.g01 (geometry) ---

Geom Title=Existing Conditions

River Reach=Dry Comal Creek ,Reach-1
Reach XY= 30
      2216525.00     13797637.85      2216528.75     13797426.55
      2216633.16     13797218.95      2216724.06     13797114.52
      2216721.33     13797026.59      2216632.50     13796875.00
      2216714.99     13796735.63      2216838.91     13796675.67
      2217161.09     13796675.67      2217426.59     13796821.33
      2217515.37     13796823.91      2217611.38     13796738.23
      2217672.33     13796630.42      2217769.02     13796622.64
      2217826.60     13796578.85      2217919.02     13796572.64
      2217984.67     13796526.39      2218123.55     13796521.46
      2218219.92     13796427.31      2218223.22     13796381.14
      2218178.89     13796323.41      2218152.28     13796201.10
      2217835.63     13796035.00      2217728.83     13795823.42
      2217721.14     13795726.60      2217677.26     13795669.06
      2217678.07     13795433.30      2217734.37     13795414.10
      2217855.22     13795295.09      2217875.00     13795225.00

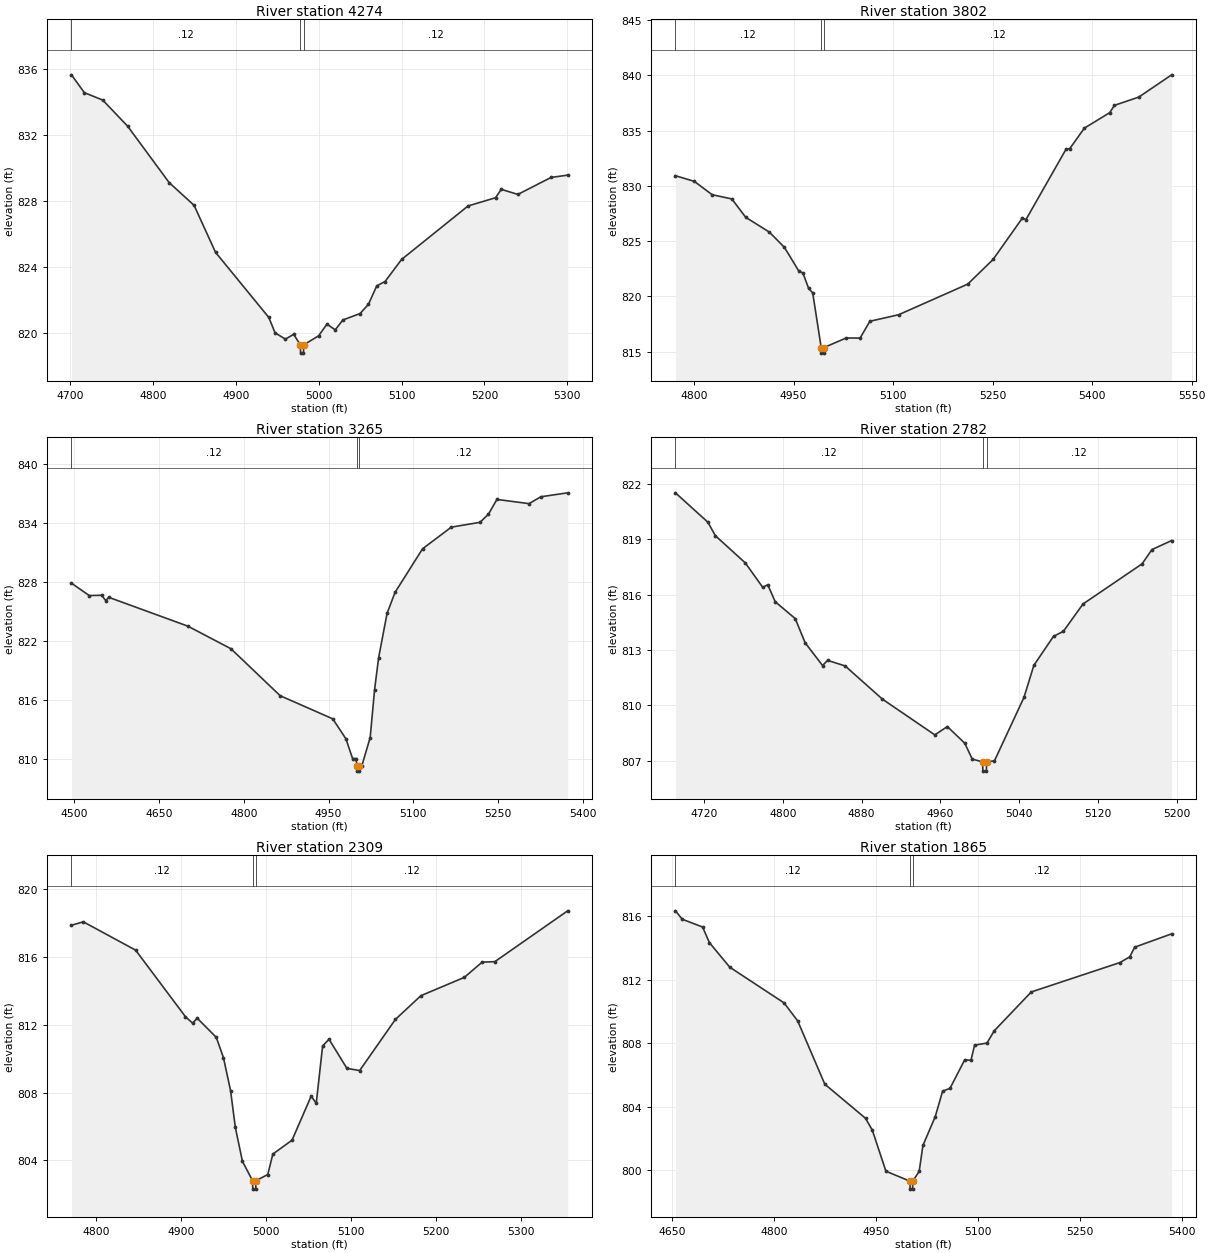
Type RM Length L Ch R = 1,4274,472,472,472
BEGIN DESCRIPTION:
Dry Comal Creek Tributary 14 9.0
END DESCRIPTION:
XS GIS Cut Line= 3
      2216822.57     13797571.18      2216574.97     13797555.30
      2216225.04     13797575.00
#Sta/Elev= 30
  4701.8  835.63  4717.3  834.55  4739.5  834.10  4769.5  832.52  4819.6  829.10
  4849.7  827.72  4875.6  824.87  4939.9  820.92  4947.4  819.99  4959.9  819.61
  4969.9  819.90  4977.9  819.26  4978.2  818.76  4981.7  818.76  4981.9  819.26
  5000.0  819.81  5010.0  820.52  5020.0  820.17  5029.2  820.77  5050.0  821.16
  5060.1  821.72  5070.1  822.84  5080.1  823.10  5100.1  824.44  5180.2  827.68
  5213.4  828.18  5220.3  828.69  5240.3  828.38  5280.4  829.41  5300.4  829.55
#Mann=3,-1,0
  4701.8    0.12       0  4977.9    0.05       0  4981.9    0.12       0
Bank Sta=4977.9,4981.9
Exp/Cntr=0.3,0.1

Type RM Length L Ch R = 1,3802,537,537,537
BEGIN DESCRIPTION:
Dry Comal Creek Tributary 14 8.0
END DESCRIPTION:
XS GIS Cut Line= 3
      2216889.31     13797279.12      2216641.64     13797104.48
      2216248.95     13796895.47
#Sta/Elev= 30
  4771.9  830.92  4800.3  830.41  4827.3  829.20  4856.9  828.82  4877.8  827.16
  4913.5  825.82  4936.2  824.44  4957.9  822.30  4964.0  822.13  4972.7  820.73
  4978.8  820.33  4991.6  815.38  4991.9  814.88  4995.4  814.88  4995.6  815.38
  5029.3  816.25  5050.2  816.24  5065.0  817.76  5108.3  818.35  5212.5  821.12
  5250.7  823.35  5294.7  827.08  5300.3  826.96  5360.6  833.31  5366.3  833.37
  5388.3  835.22  5426.5  836.62  5433.6  837.28  5470.4  838.03  5519.8  840.04
#Mann=3,-1,0
  4771.9    0.12       0  4991.6    0.05       0  4995.6    0.12       0
Bank Sta=4991.6,4995.6
Exp/Cntr=0.3,0.1

Type RM Length L Ch R = 1,3265,483,483,483
BEGIN DESCRIPTION:
Dry Comal Creek Tributary 14 7.0
END DESCRIPTION:
XS GIS Cut Line= 3
      2216975.00     13797183.85      2216775.00     13796725.00
      2216562.26     13796412.36
#Sta/Elev= 30
  4494.7  827.85  4526.2  826.59  4548.0  826.62  4555.4  826.08  4560.8  826.41
  4700.7  823.48  4777.1  821.18  4864.3  816.40  4957.4  814.05  4980.8  812.01
  4992.5  810.01  4998.3  810.01  5000.7  809.23  5001.0  808.73  5004.5  808.73
  5004.7  809.23  5008.8  809.25  5023.7  812.15  5031.5  817.02  5038.6  820.25
  5053.6  824.78  5067.8  826.92  5116.5  831.35  5167.4  833.55  5218.2  834.04
  5233.2  834.87  5248.1  836.37  5305.0  835.94  5326.0  836.64  5373.4  837.04
#Mann=3,-1,0
  4494.7    0.12       0  5000.7    0.05       0  5004.7    0.12       0
Bank Sta=5000.7,5004.7
Exp/Cntr=0.3,0.1

Type RM Length L Ch R = 1,2782,473,473,473
BEGIN DESCRIPTION:
Dry Comal Creek Tributary 14 6.0
END DESCRIPTION:
XS GIS Cut Line= 3
      2217275.00     13797025.02      2217225.00     13796725.00
      2217225.00     13796524.95
#Sta/Elev= 30
  4690.8  821.50  4723.8  819.91  4731.4  819.18  4761.8  817.71  4779.5  816.39
  4784.6  816.53  4792.2  815.61  4812.5  814.70  4822.6  813.39  4840.3  812.16
  4845.4  812.44  4863.2  812.14  4901.2  810.34  4954.4  808.41  4967.1  808.86
  4984.8  807.96  4992.4  807.10  5003.0  806.95  5003.2  806.45  5006.7  806.45
  5007.0  806.95  5015.0  807.01  5045.0  810.44  5055.0  812.17  5075.0  813.74
  5085.0  814.01  5105.0  815.49  5165.0  817.66  5175.0  818.43  5195.0  818.92
#Mann=3,-1,0
  4690.8    0.12       0  5003.0    0.05       0  5007.0    0.12       0
Bank Sta=5003,5007
Exp/Cntr=0.3,0.1

Type RM Length L Ch R = 1,2309,444,444,444
BEGIN DESCRIPTION:
Dry Comal Creek Tributary 14 5.0
END DESCRIPTION:
XS GIS Cut Line= 3
      2217725.00     13796925.01      2217625.00     13796725.00
      2217424.98     13796424.98
#Sta/Elev= 30
  4770.9  817.88  4784.9  818.08  4846.4  816.41  4905.1  812.48  4913.5  812.10
  4919.0  812.39  4941.4  811.26  4949.8  810.07  4958.2  808.12  4963.8  805.95
  4972.2  803.94  4984.1  802.80  4984.4  802.30  4987.9  802.30  4988.1  802.80
  5002.0  803.16  5008.0  804.37  5030.6  805.19  5053.1  807.79  5059.1  807.37
  5066.6  810.75  5074.1  811.15  5095.2  809.43  5110.2  809.30  5152.3  812.32
  5182.3  813.72  5233.4  814.80  5254.4  815.70  5269.4  815.73  5355.1  818.73
#Mann=3,-1,0
  4770.9    0.12       0  4984.1    0.05       0  4988.1    0.12       0
Bank Sta=4984.1,4988.1
Exp/Cntr=0.3,0.1

Type RM Length L Ch R = 1,1865,191,191,191
BEGIN DESCRIPTION:
Dry Comal Creek Tributary 14 4.0
END DESCRIPTION:
XS GIS Cut Line= 3
      2217975.00     13796874.98      2217975.00     13796525.00
      2217624.97     13796374.99
#Sta/Elev= 30
  4654.6  816.33  4664.6  815.80  4694.6  815.31  4704.6  814.33  4734.6  812.78
  4814.6  810.53  4834.6  809.40  4874.6  805.41  4934.6  803.26  4944.6  802.51
  4964.6  799.93  5000.0  799.30  5000.3  798.80  5003.9  798.80  5004.1  799.30
  5013.6  799.92  5019.1  801.55  5037.2  803.36  5048.1  804.97  5059.0  805.15
  5080.7  806.95  5089.8  806.91  5095.2  807.87  5113.4  808.00  5124.3  808.78
  5178.7  811.22  5309.2  813.07  5323.7  813.43  5331.0  814.04  5385.4  814.88
#Mann=3,-1,0
  4654.6    0.12       0  5000.0    0.05       0  5004.1    0.12       0
Bank Sta=5000,5004.1
Exp/Cntr=0.3,0.1

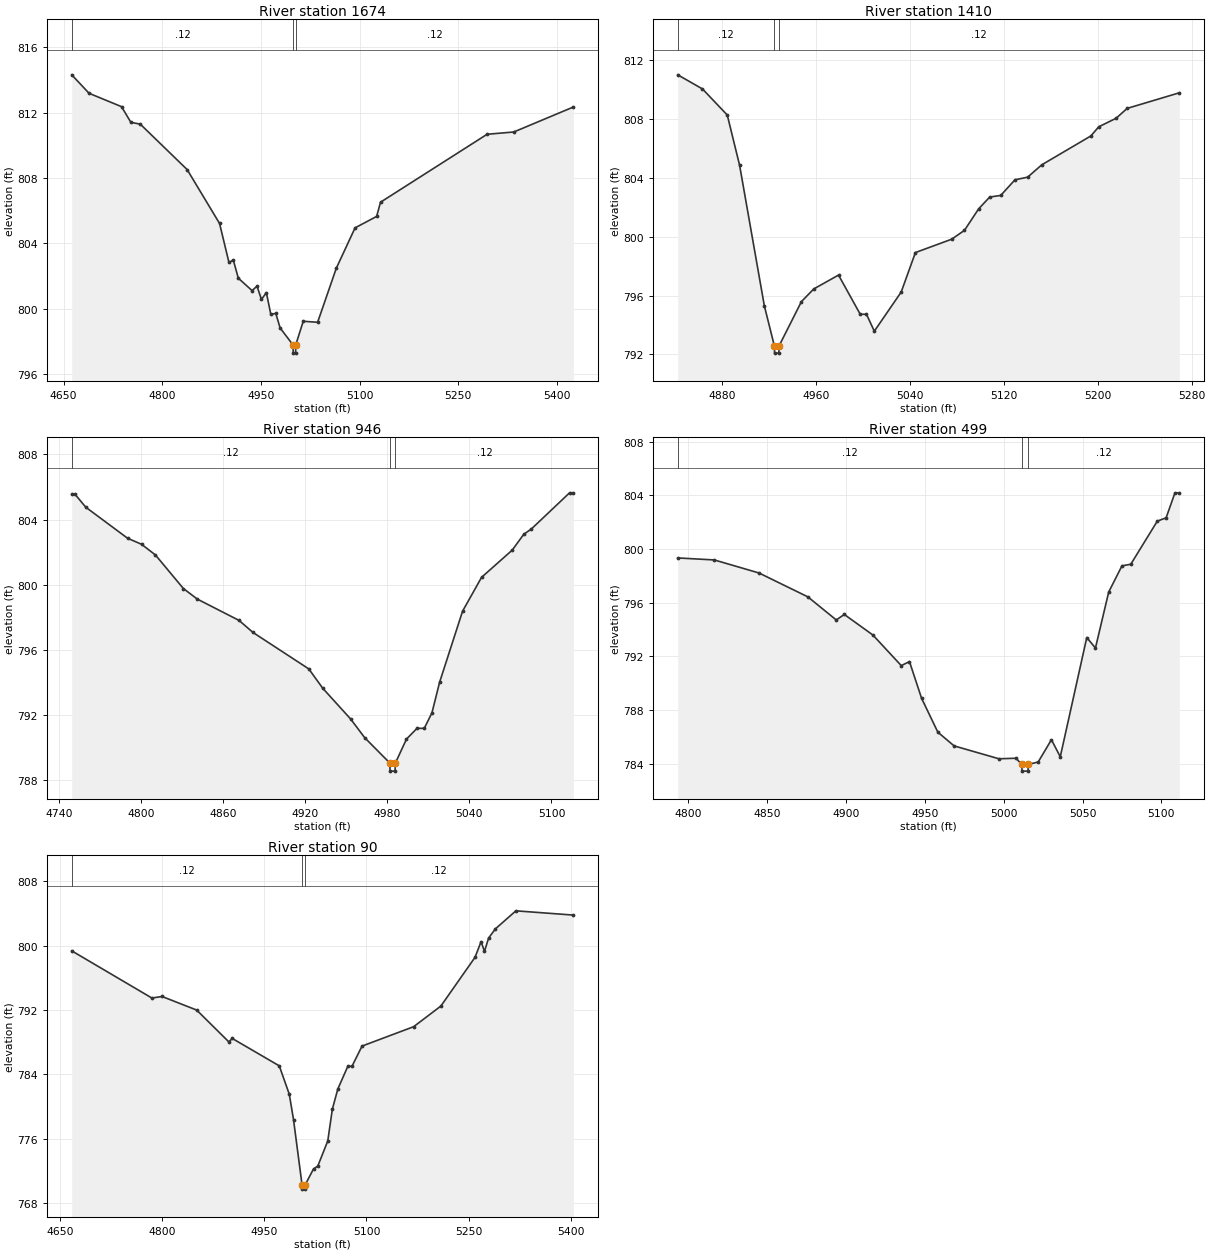
Type RM Length L Ch R = 1,1674,264,264,264
BEGIN DESCRIPTION:
X18987
END DESCRIPTION:
XS GIS Cut Line= 3
      2218410.00     13796717.15      2218060.78     13796412.38
      2217765.51     13796364.75
#Sta/Elev= 30
  4662.4  814.31  4688.7  813.18  4738.1  812.36  4752.3  811.40  4766.6  811.29
  4837.8  808.51  4887.1  805.21  4901.4  802.82  4908.0  802.97  4915.6  801.86
  4936.5  801.10  4944.1  801.37  4950.7  800.56  4958.3  800.97  4965.0  799.65
  4972.6  799.70  4979.2  798.81  4998.8  797.77  4999.1  797.27  5002.7  797.27
  5002.9  797.77  5014.3  799.22  5036.2  799.16  5064.6  802.47  5093.1  804.94
  5125.9  805.64  5131.8  806.51  5293.8  810.67  5334.4  810.81  5425.0  812.34
#Mann=3,-1,0
  4662.4    0.12       0  4998.8    0.05       0  5002.9    0.12       0
Bank Sta=4998.8,5002.9
Exp/Cntr=0.3,0.1

Type RM Length L Ch R = 1,1410,464,464,464
BEGIN DESCRIPTION:
Dry Comal Creek Tributary 14 3.0
END DESCRIPTION:
XS GIS Cut Line= 3
      2218225.00     13796125.01      2218175.00     13796275.00
      2217924.96     13796375.01
#Sta/Elev= 30
  4842.1  810.99  4863.2  810.03  4884.3  808.26  4894.8  804.85  4915.9  795.30
  4924.4  792.59  4924.6  792.09  4928.2  792.09  4928.5  792.59  4947.5  795.59
  4958.0  796.45  4979.1  797.39  4997.6  794.73  5002.9  794.73  5009.6  793.58
  5032.5  796.24  5044.6  798.92  5075.6  799.83  5086.4  800.43  5098.5  801.89
  5107.9  802.69  5117.3  802.80  5129.4  803.86  5140.2  804.04  5152.3  804.88
  5194.1  806.84  5200.8  807.46  5215.6  808.04  5225.0  808.71  5269.5  809.77
#Mann=3,-1,0
  4842.1    0.12       0  4924.4    0.05       0  4928.5    0.12       0
Bank Sta=4924.4,4928.5
Exp/Cntr=0.3,0.1

Type RM Length L Ch R = 1,946,447,447,447
BEGIN DESCRIPTION:
Dry Comal Creek Tributary 14 2.0
END DESCRIPTION:
XS GIS Cut Line= 3
      2218074.97     13795975.01      2217825.00     13796025.00
      2217725.02     13796074.99
#Sta/Elev= 30
  4749.3  805.54  4751.8  805.54  4759.5  804.76  4790.1  802.85  4800.3  802.48
  4810.5  801.82  4830.9  799.76  4841.1  799.11  4871.6  797.80  4881.8  797.06
  4922.6  794.82  4932.8  793.63  4953.2  791.74  4963.4  790.60  4981.8  789.04
  4982.0  788.54  4985.6  788.54  4985.9  789.04  4994.0  790.51  5001.7  791.17
  5007.0  791.17  5012.6  792.12  5018.2  794.00  5035.0  798.37  5048.9  800.45
  5071.3  802.12  5079.7  803.09  5085.3  803.42  5113.2  805.64  5116.0  805.64
#Mann=3,-1,0
  4749.3    0.12       0  4981.8    0.05       0  4985.9    0.12       0
Bank Sta=4981.8,4985.9
Exp/Cntr=0.3,0.1

Type RM Length L Ch R = 1,499,409,409,409
BEGIN DESCRIPTION:
Dry Comal Creek Tributary 14 1.0
END DESCRIPTION:
XS GIS Cut Line= 3
      2217875.00     13795675.00      2217675.00     13795625.00
      2217574.96     13795574.98
#Sta/Elev= 30
  4793.4  799.33  4816.6  799.18  4844.9  798.21  4875.9  796.43  4893.9  794.71
  4899.0  795.12  4917.1  793.59  4935.1  791.31  4940.3  791.61  4948.0  788.87
  4958.3  786.35  4968.6  785.33  4997.0  784.37  5007.9  784.41  5011.4  783.95
  5011.7  783.45  5015.4  783.45  5015.7  783.95  5021.9  784.13  5030.3  785.79
  5035.9  784.52  5052.7  793.40  5058.2  792.62  5066.6  796.79  5075.0  798.74
  5080.6  798.86  5097.4  802.07  5103.0  802.32  5108.6  804.18  5111.4  804.18
#Mann=3,-1,0
  4793.4    0.12       0  5011.4    0.05       0  5015.7    0.12       0
Bank Sta=5011.4,5015.7
Exp/Cntr=0.3,0.1

Type RM Length L Ch R = 1,90,0,0,0
BEGIN DESCRIPTION:
X18986
END DESCRIPTION:
XS GIS Cut Line= 4
      2217930.62     13795615.53      2217879.82     13795329.77
      2217765.52     13795247.22      2217460.72     13795234.52
#Sta/Elev= 30
  4667.4  799.37  4785.0  793.50  4800.0  793.69  4850.8  792.00  4898.0  788.04
  4903.0  788.47  4972.0  785.06  4986.7  781.53  4992.9  778.37  5005.5  770.22
  5005.8  769.72  5009.5  769.72  5009.8  770.22  5022.3  772.24  5028.5  772.58
  5043.2  775.72  5049.9  779.66  5057.9  782.17  5072.6  785.00  5078.8  785.02
  5093.5  787.52  5169.2  789.93  5209.2  792.50  5259.3  798.56  5268.2  800.51
  5273.2  799.31  5279.3  800.97  5289.3  802.11  5319.3  804.35  5403.7  803.82
#Mann=3,-1,0
  4667.4    0.12       0  5005.5    0.05       0  5009.8    0.12       0
Bank Sta=5005.5,5009.8
Exp/Cntr=0.3,0.1

Chan Stop Cuts=-1