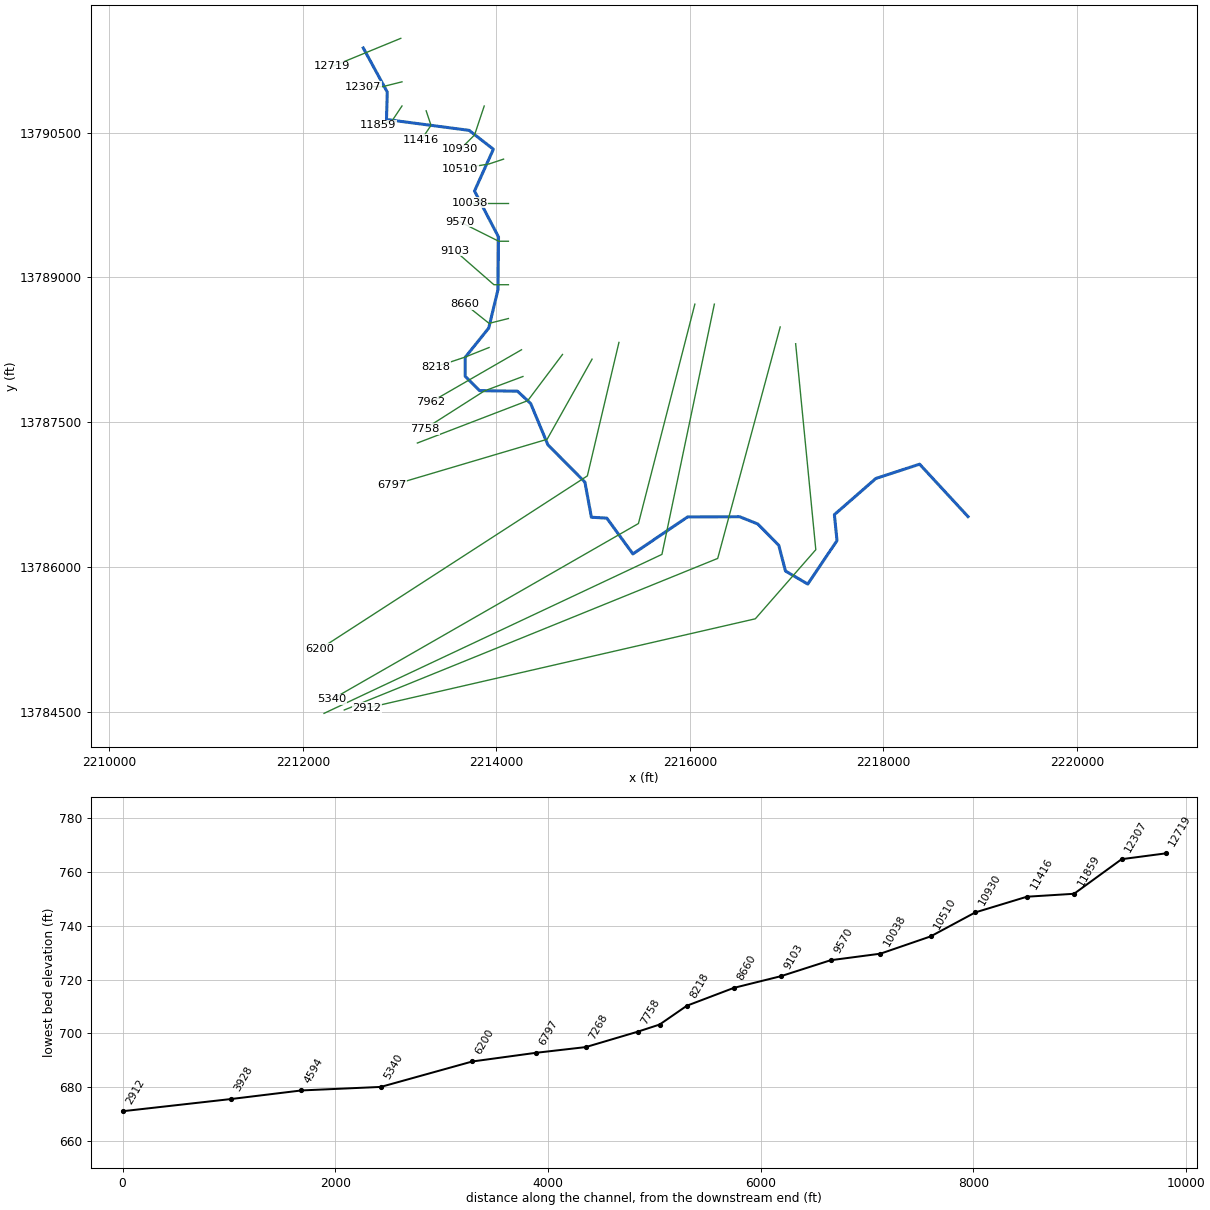
--- Dry Comal Creek Tributary 18.prj (project) ---

Proj Title=Dry Comal Creek Tributary 18 Base Level Engineering
Current Plan=p01
Default Exp/Contr=0.3,0.1
English Units
Geom File=g01
Flow File=f01
Plan File=p01
BEGIN DESCRIPTION:
Dry Comal Creek Tributary 18
END DESCRIPTION:

--- Dry Comal Creek Tributary 18.p01 (plan) ---

Plan Title=Multiple Run
Short Identifier=Multiple
Geom File=g01
Flow File=f01
Subcritical Flow
K Sum by GR= 0
Std Step Tol= 0.01
Critical Tol= 0.01
Num of Std Step Trials= 20
Max Error Tol= 0.3
Flow Tol Ratio= 0.001
Split Flow NTrial= 30
Split Flow Tol= 0.02
Split Flow Ratio= 0.02
Log Output Level= 0
Friction Slope Method= 1
Unsteady Friction Slope Method= 2
Unsteady Bridges Friction Slope Method= 1
Parabolic Critical Depth
Global Vel Dist=  1 , 1 , 1
Global Log Level= 0
CheckData=True
Encroach Param= -1, 0, 0, 0
BEGIN DESCRIPTION:
Multiple Run
END DESCRIPTION:

--- Dry Comal Creek Tributary 18.f01 (steady flow) ---

Flow Title=Multiple
Number of Profiles=7
Profile Names=10-year,25-year,50-year,1pct_min,100-year,1pct_plu,500-year
River Rch & RM= Dry Comal Creek ,Reach-1,12719
    1083    1829    2536    1702    3396    6776    6029
River Rch & RM= Dry Comal Creek ,Reach-1,10930
    1284    2189    3053    2060    4111    8202    7379
River Rch & RM= Dry Comal Creek ,Reach-1,8660
    1506    2574    3595    2426    4840    9657    8692
Boundary for River Rch & Prof#=Dry Comal Creek ,Reach-1,1
Up Type=0
Dn Type=3
Dn Slope=0.005
Boundary for River Rch & Prof#=Dry Comal Creek ,Reach-1,2
Up Type=0
Dn Type=3
Dn Slope=0.005
Boundary for River Rch & Prof#=Dry Comal Creek ,Reach-1,3
Up Type=0
Dn Type=3
Dn Slope=0.005
Boundary for River Rch & Prof#=Dry Comal Creek ,Reach-1,4
Up Type=0
Dn Type=3
Dn Slope=0.005
Boundary for River Rch & Prof#=Dry Comal Creek ,Reach-1,5
Up Type=0
Dn Type=3
Dn Slope=0.005
Boundary for River Rch & Prof#=Dry Comal Creek ,Reach-1,6
Up Type=0
Dn Type=3
Dn Slope=0.005
Boundary for River Rch & Prof#=Dry Comal Creek ,Reach-1,7
Up Type=0
Dn Type=3
Dn Slope=0.005

--- Dry Comal Creek Tributary 18.g01 (geometry) ---

Geom Title=Existing Conditions

River Reach=Dry Comal Creek ,Reach-1
Reach XY= 30
      2212625.00     13791375.00      2212873.18     13790918.88
      2212864.82     13790635.32      2213719.07     13790522.75
      2213969.60     13790327.43      2213774.71     13789895.18
      2214022.76     13789419.07      2214017.41     13788875.01
      2213921.45     13788476.47      2213678.54     13788173.54
      2213678.53     13787976.46      2213826.46     13787828.54
      2214219.15     13787822.94      2214355.22     13787695.09
      2214532.70     13787268.53      2214915.69     13786881.66
      2214982.70     13786518.43      2215142.08     13786508.85
      2215411.62     13786138.52      2215976.55     13786521.25
      2216514.50     13786523.78      2216701.87     13786448.82
      2216919.53     13786227.45      2216988.47     13785961.43
      2217218.95     13785826.58      2217521.18     13786276.59
      2217494.21     13786545.00      2217922.57     13786919.48
      2218375.01     13787067.47      2218875.00     13786525.00

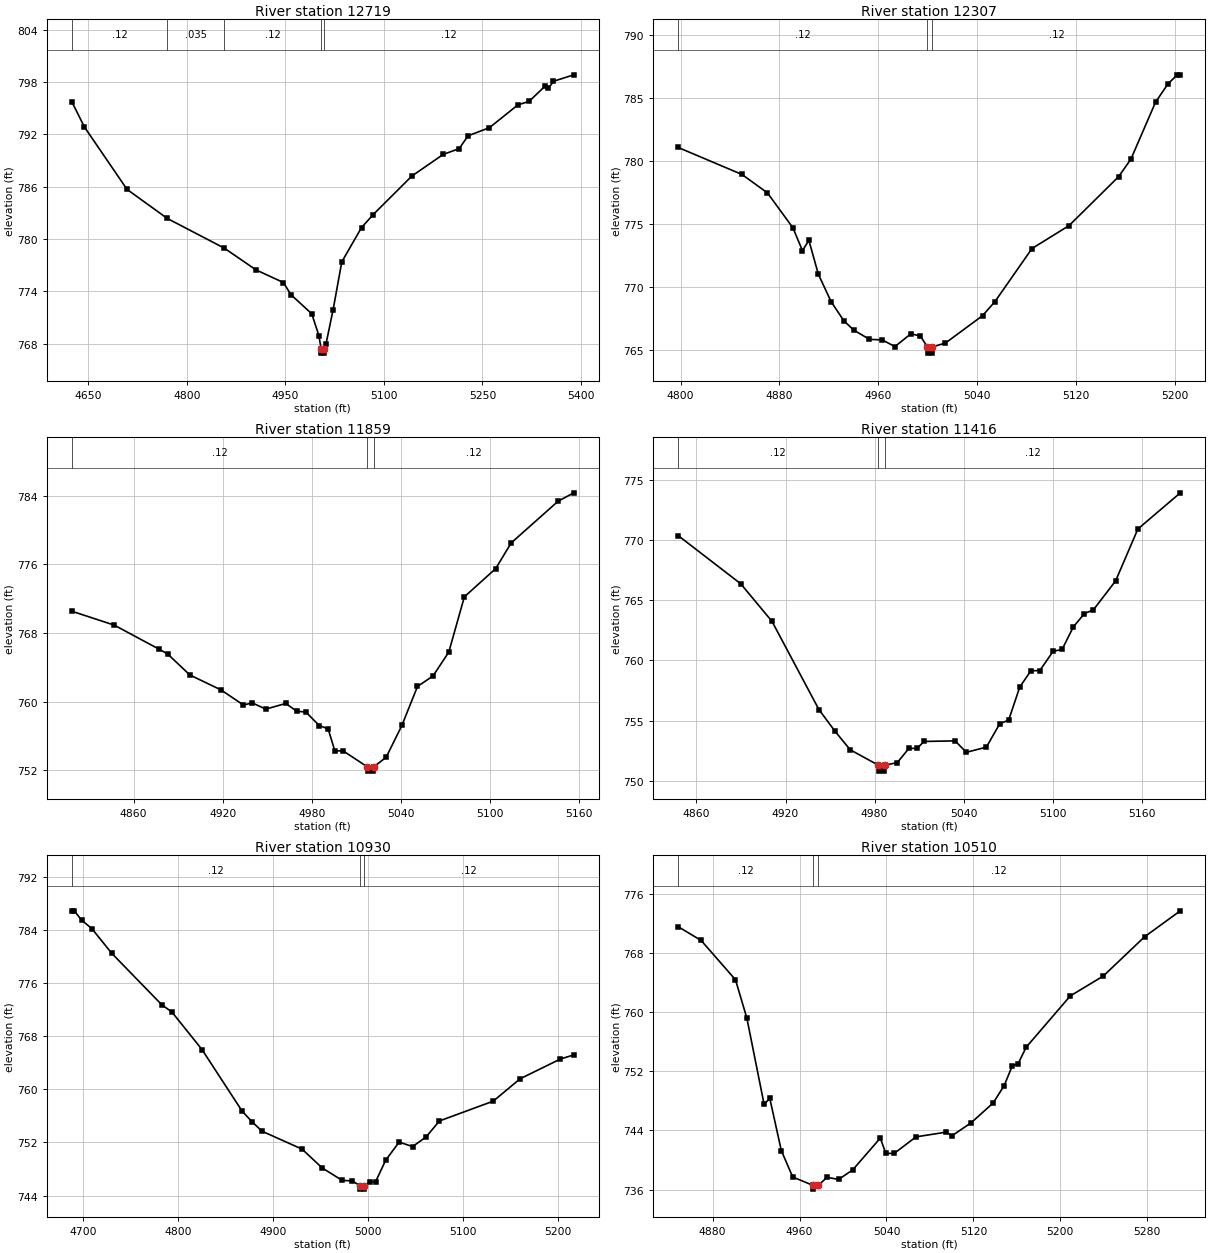
Type RM Length L Ch R = 1,12719,412,412,412
BEGIN DESCRIPTION:
X18993
END DESCRIPTION:
XS GIS Cut Line= 2
      2213012.75     13791475.24      2212306.24     13791184.49
#Sta/Elev= 30
  4625.1  795.77  4644.3  792.86  4709.2  785.70  4770.4  782.37  4857.2  778.96
  4905.4  776.47  4947.1  775.02  4958.7  773.62  4990.3  771.43  5001.1  768.94
  5004.5  767.42  5004.8  766.92  5008.4  766.92  5008.7  767.42  5012.1  768.02
  5022.8  771.91  5036.0  777.39  5066.0  781.32  5083.9  782.82  5142.6  787.23
  5190.5  789.72  5214.5  790.37  5228.2  791.85  5260.7  792.78  5303.9  795.39
  5321.1  795.80  5345.1  797.53  5350.5  797.28  5358.0  798.10  5389.1  798.84
#Mann=5,-1,0
  4625.1    0.12       0  4770.4   0.035       0  4857.2    0.12       0
  5004.5    0.05       0  5008.7    0.12       0
Bank Sta=5004.5,5008.7
Exp/Cntr=0.3,0.1

Type RM Length L Ch R = 1,12307,448,448,448
BEGIN DESCRIPTION:
Dry Comal Creek Tributary 18 14.0
END DESCRIPTION:
XS GIS Cut Line= 3
      2213025.03     13791025.01      2212825.00     13790975.00
      2212624.99     13790975.00
#Sta/Elev= 30
  4798.1  781.08  4849.7  778.94  4870.3  777.48  4890.9  774.71  4898.6  772.90
  4903.8  773.72  4911.5  771.02  4921.8  768.86  4932.1  767.34  4939.9  766.62
  4952.8  765.87  4963.1  765.83  4973.4  765.30  4986.3  766.31  4994.0  766.14
  4999.6  765.28  4999.9  764.78  5003.6  764.78  5003.8  765.28  5014.3  765.58
  5044.3  767.75  5054.3  768.86  5084.3  773.07  5114.3  774.89  5154.3  778.76
  5164.3  780.15  5184.3  784.68  5194.3  786.12  5201.8  786.84  5204.3  786.84
#Mann=3,-1,0
  4798.1    0.12       0  4999.6    0.05       0  5003.8    0.12       0
Bank Sta=4999.6,5003.8
Exp/Cntr=0.3,0.1

Type RM Length L Ch R = 1,11859,443,443,443
BEGIN DESCRIPTION:
Dry Comal Creek Tributary 18 13.0
END DESCRIPTION:
XS GIS Cut Line= 3
      2213025.01     13790775.01      2212925.00     13790625.00
      2212775.01     13790575.00
#Sta/Elev= 30
  4818.3  770.54  4846.9  768.92  4876.9  766.14  4882.9  765.56  4897.9  763.11
  4919.0  761.36  4934.0  759.61  4940.0  759.86  4949.0  759.13  4962.5  759.79
  4970.0  758.89  4976.1  758.79  4985.1  757.22  4991.1  756.83  4995.6  754.27
  5001.2  754.27  5017.5  752.41  5017.8  751.91  5021.6  751.91  5021.8  752.41
  5030.2  753.52  5040.8  757.23  5051.3  761.77  5061.8  763.00  5072.4  765.77
  5082.9  772.21  5104.0  775.50  5114.5  778.50  5146.2  783.37  5156.7  784.33
#Mann=3,-1,0
  4818.3    0.12       0  5017.5    0.05       0  5021.8    0.12       0
Bank Sta=5017.5,5021.8
Exp/Cntr=0.3,0.1

Type RM Length L Ch R = 1,11416,486,486,486
BEGIN DESCRIPTION:
Dry Comal Creek Tributary 18 12.0
END DESCRIPTION:
XS GIS Cut Line= 3
      2213275.01     13790724.98      2213325.00     13790575.00
      2213224.98     13790424.98
#Sta/Elev= 30
  4847.7  770.35  4889.8  766.36  4910.9  763.24  4942.5  755.93  4953.1  754.17
  4963.6  752.59  4982.5  751.32  4982.8  750.82  4986.6  750.82  4986.9  751.32
  4995.3  751.52  5003.2  752.71  5008.8  752.71  5013.3  753.28  5034.3  753.33
  5041.9  752.38  5055.4  752.81  5064.4  754.75  5070.4  755.05  5077.9  757.80
  5085.4  759.14  5091.4  759.16  5100.4  760.76  5106.4  760.91  5114.0  762.78
  5121.5  763.89  5127.5  764.19  5142.5  766.60  5157.5  770.90  5186.1  773.90
#Mann=3,-1,0
  4847.7    0.12       0  4982.5    0.05       0  4986.9    0.12       0
Bank Sta=4982.5,4986.9
Exp/Cntr=0.3,0.1

Type RM Length L Ch R = 1,10930,420,420,420
BEGIN DESCRIPTION:
Dry Comal Creek Tributary 18 11.0
END DESCRIPTION:
XS GIS Cut Line= 3
      2213874.99     13790774.97      2213775.00     13790475.00
      2213625.02     13790325.02
#Sta/Elev= 30
  4688.4  786.86  4691.0  786.86  4698.9  785.44  4709.5  784.19  4730.5  780.46
  4783.2  772.71  4793.8  771.63  4825.4  765.99  4867.6  756.73  4878.1  755.11
  4888.7  753.69  4930.8  750.99  4951.9  748.17  4973.0  746.29  4983.5  746.22
  4991.9  745.48  4992.2  744.98  4996.0  744.98  4996.3  745.48  5002.0  746.09
  5008.1  746.09  5018.7  749.33  5032.9  752.06  5047.0  751.38  5061.2  752.83
  5075.3  755.24  5131.9  758.22  5160.2  761.59  5202.6  764.56  5216.7  765.18
#Mann=3,-1,0
  4688.4    0.12       0  4991.9    0.05       0  4996.3    0.12       0
Bank Sta=4991.9,4996.3
Exp/Cntr=0.3,0.1

Type RM Length L Ch R = 1,10510,472,472,472
BEGIN DESCRIPTION:
Dry Comal Creek Tributary 18 10.0
END DESCRIPTION:
XS GIS Cut Line= 3
      2214074.99     13790225.00      2213925.00     13790175.00
      2213625.04     13790125.01
#Sta/Elev= 30
  4848.3  771.55  4869.4  769.69  4901.0  764.38  4911.5  759.17  4927.3  747.56
  4932.6  748.32  4943.2  741.27  4953.7  737.70  4972.5  736.56  4972.8  736.06
  4977.1  736.56  4985.3  737.66  4995.9  737.37  5008.9  738.66  5034.3  742.96
  5039.4  740.91  5047.0  740.88  5067.2  743.13  5095.1  743.77  5100.2  743.27
  5117.9  745.03  5138.2  747.71  5148.3  750.05  5155.9  752.76  5161.0  752.97
  5168.6  755.25  5209.2  762.19  5239.6  764.88  5277.6  770.19  5310.5  773.70
#Mann=3,-1,0
  4848.3    0.12       0  4972.5    0.05       0  4977.1    0.12       0
Bank Sta=4972.5,4977.1
Exp/Cntr=0.3,0.1

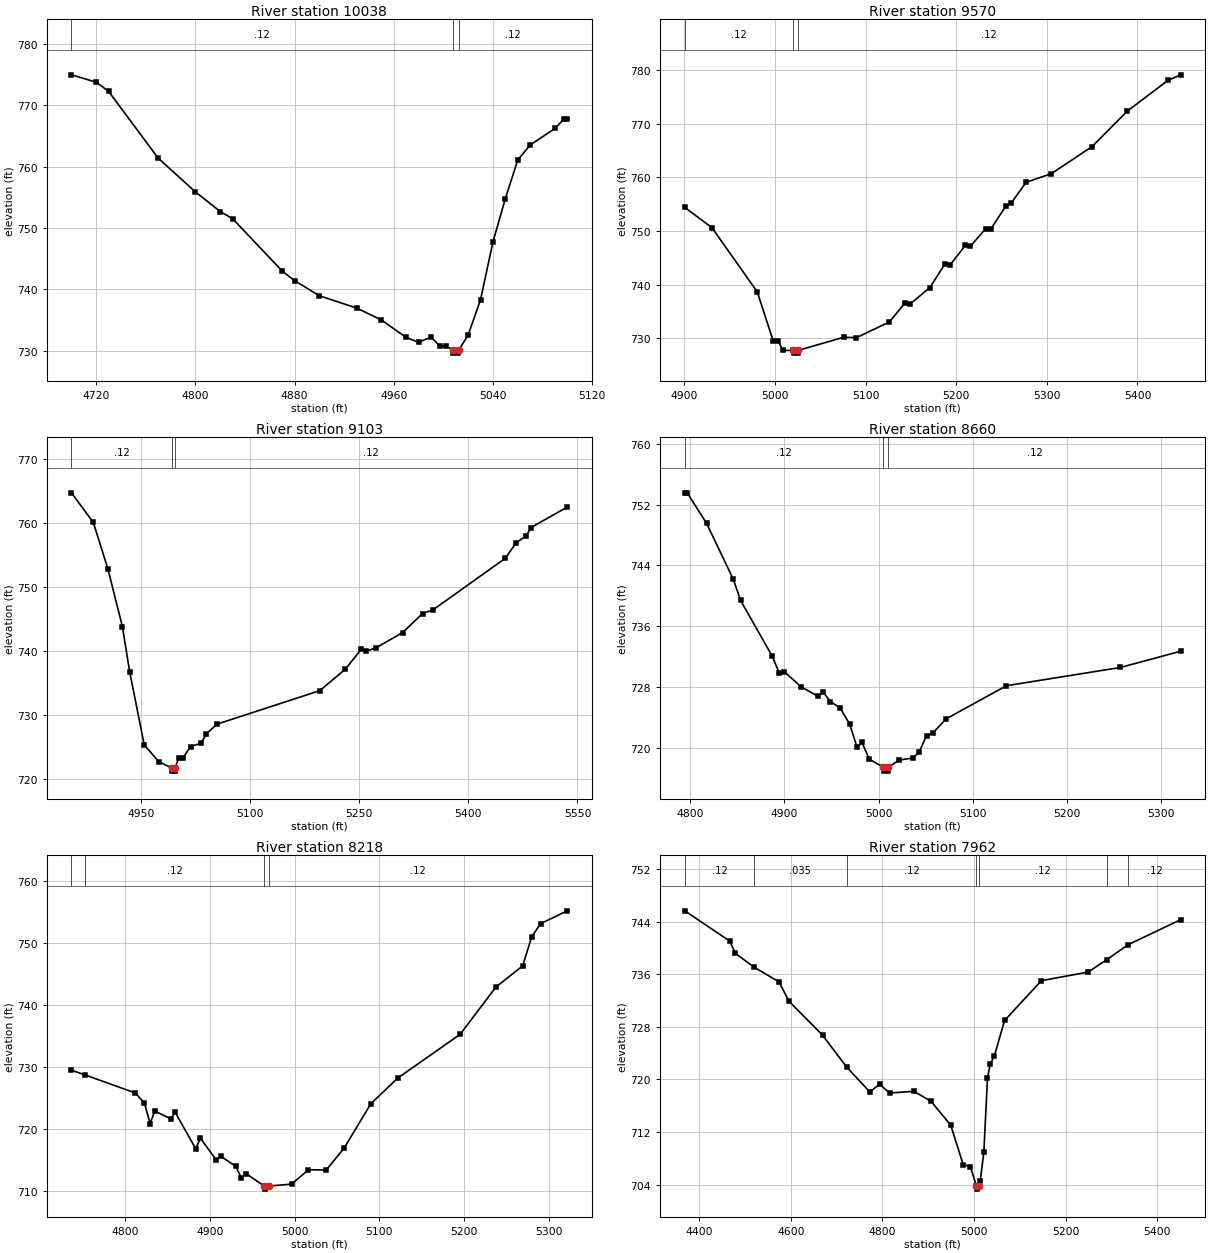
Type RM Length L Ch R = 1,10038,468,468,468
BEGIN DESCRIPTION:
Dry Comal Creek Tributary 18 9.0
END DESCRIPTION:
XS GIS Cut Line= 3
      2214124.99     13789775.00      2213825.00     13789775.00
      2213724.99     13789775.00
#Sta/Elev= 30
  4700.0  774.93  4720.0  773.73  4730.0  772.23  4770.0  761.36  4800.0  755.88
  4820.0  752.68  4830.0  751.52  4870.0  743.00  4880.0  741.44  4900.0  738.98
  4930.0  736.98  4950.0  735.04  4970.0  732.19  4980.0  731.41  4990.0  732.25
  4997.5  730.74  5002.5  730.74  5007.5  730.14  5007.9  729.64  5012.1  729.64
  5012.4  730.14  5020.0  732.58  5030.0  738.33  5040.0  747.73  5050.0  754.78
  5060.0  761.06  5070.0  763.50  5090.0  766.21  5097.5  767.77  5100.0  767.77
#Mann=3,-1,0
  4700.0    0.12       0  5007.5    0.05       0  5012.4    0.12       0
Bank Sta=5007.5,5012.4
Exp/Cntr=0.3,0.1

Type RM Length L Ch R = 1,9570,467,467,467
BEGIN DESCRIPTION:
Dry Comal Creek Tributary 18 8.0
END DESCRIPTION:
XS GIS Cut Line= 3
      2214125.00     13789375.00      2214025.00     13789375.00
      2213625.01     13789574.99
#Sta/Elev= 30
  4900.4  754.38  4930.4  750.59  4980.4  738.63  4997.9  729.54  5003.2  729.54
  5008.8  727.72  5020.3  727.71  5020.7  727.21  5024.9  727.21  5025.3  727.71
  5075.9  730.17  5089.8  730.09  5126.2  733.02  5143.0  736.48  5148.5  736.28
  5170.9  739.43  5187.7  743.89  5193.3  743.67  5210.0  747.28  5215.6  747.14
  5232.4  750.38  5238.0  750.31  5254.8  754.65  5260.3  755.11  5277.1  759.05
  5305.1  760.68  5349.8  765.70  5388.9  772.35  5433.6  778.05  5447.6  779.09
#Mann=3,-1,0
  4900.4    0.12       0  5020.3    0.05       0  5025.3    0.12       0
Bank Sta=5020.3,5025.3
Exp/Cntr=0.3,0.1

Type RM Length L Ch R = 1,9103,443,443,443
BEGIN DESCRIPTION:
Dry Comal Creek Tributary 18 7.0
END DESCRIPTION:
XS GIS Cut Line= 3
      2214124.96     13788925.00      2213975.00     13788925.00
      2213574.97     13789275.02
#Sta/Elev= 30
  4854.5  764.70  4884.5  760.08  4904.5  752.86  4924.5  743.84  4934.5  736.78
  4954.5  725.38  4974.5  722.76  4992.0  721.78  4992.3  721.28  4996.6  721.28
  4997.0  721.78  5002.0  723.35  5007.8  723.35  5018.2  725.12  5032.5  725.62
  5040.0  727.09  5054.3  728.60  5195.7  733.83  5230.8  737.17  5252.7  740.27
  5259.3  739.97  5273.5  740.55  5309.6  742.89  5337.1  745.87  5351.4  746.44
  5451.0  754.50  5465.3  756.86  5479.5  757.99  5486.1  759.29  5536.0  762.48
#Mann=3,-1,0
  4854.5    0.12       0  4992.0    0.05       0  4997.0    0.12       0
Bank Sta=4992,4997
Exp/Cntr=0.3,0.1

Type RM Length L Ch R = 1,8660,442,442,442
BEGIN DESCRIPTION:
Dry Comal Creek Tributary 18 6.0
END DESCRIPTION:
XS GIS Cut Line= 3
      2214124.99     13788575.00      2213925.00     13788525.00
      2213675.00     13788725.00
#Sta/Elev= 30
  4794.3  753.56  4796.9  753.56  4817.5  749.53  4845.8  742.18  4853.6  739.39
  4887.1  732.06  4894.8  729.78  4899.9  730.02  4918.0  728.00  4936.0  726.78
  4941.2  727.32  4948.9  726.08  4959.2  725.25  4969.5  723.08  4977.2  720.05
  4982.4  720.71  4990.1  718.51  5005.1  717.43  5005.5  716.93  5009.8  716.93
  5010.2  717.43  5022.1  718.40  5036.5  718.65  5042.9  719.41  5050.9  721.59
  5057.3  721.90  5071.7  723.81  5135.7  728.17  5256.6  730.57  5320.6  732.71
#Mann=3,-1,0
  4794.3    0.12       0  5005.1    0.05       0  5010.2    0.12       0
Bank Sta=5005.1,5010.2
Exp/Cntr=0.3,0.1

Type RM Length L Ch R = 1,8218,256,256,256
BEGIN DESCRIPTION:
Dry Comal Creek Tributary 18 5.0
END DESCRIPTION:
XS GIS Cut Line= 3
      2213925.04     13788275.02      2213675.00     13788175.00
      2213375.03     13788075.01
#Sta/Elev= 30
  4736.4  729.44  4752.0  728.71  4811.8  725.78  4822.6  724.14  4829.3  720.85
  4834.7  722.87  4853.6  721.62  4859.0  722.65  4883.2  716.77  4888.6  718.51
  4907.4  714.98  4912.8  715.58  4930.3  713.97  4937.0  712.11  4942.4  712.80
  4964.0  710.79  4964.4  710.29  4969.3  710.79  4996.3  711.09  5016.2  713.41
  5037.3  713.37  5058.4  716.91  5090.0  724.06  5121.7  728.18  5195.4  735.23
  5237.6  742.84  5269.2  746.25  5279.8  750.92  5290.3  753.05  5321.9  755.12
#Mann=4,-1,0
  4736.4   0.035       0  4752.0    0.12       0  4964.0    0.05       0
  4969.3    0.12       0
Bank Sta=4964,4969.3
Exp/Cntr=0.3,0.1

Type RM Length L Ch R = 1,7962,204,204,204
BEGIN DESCRIPTION:
X18992
END DESCRIPTION:
XS GIS Cut Line= 2
      2214260.42     13788251.75      2213322.94     13787710.10
#Sta/Elev= 30
  4368.5  745.63  4466.7  741.03  4478.7  739.20  4519.7  737.06  4574.4  734.82
  4595.9  731.89  4669.3  726.72  4722.0  721.86  4772.5  718.09  4794.0  719.25
  4815.6  717.92  4868.7  718.18  4906.0  716.67  4949.1  713.05  4976.4  707.03
  4992.1  706.73  5005.2  703.80  5005.7  703.30  5010.6  703.80  5013.7  704.57
  5021.5  708.89  5029.5  720.19  5035.2  722.26  5044.6  723.59  5066.8  728.95
  5147.2  735.01  5249.1  736.31  5289.5  738.18  5336.7  740.48  5451.2  744.28
#Mann=7,-1,0
  4368.5    0.12       0  4519.7   0.035       0  4722.0    0.12       0
  5005.2    0.05       0  5010.6    0.12       0  5289.5   0.035       0
  5336.7    0.12       0
Bank Sta=5005.2,5010.6
Exp/Cntr=0.3,0.1

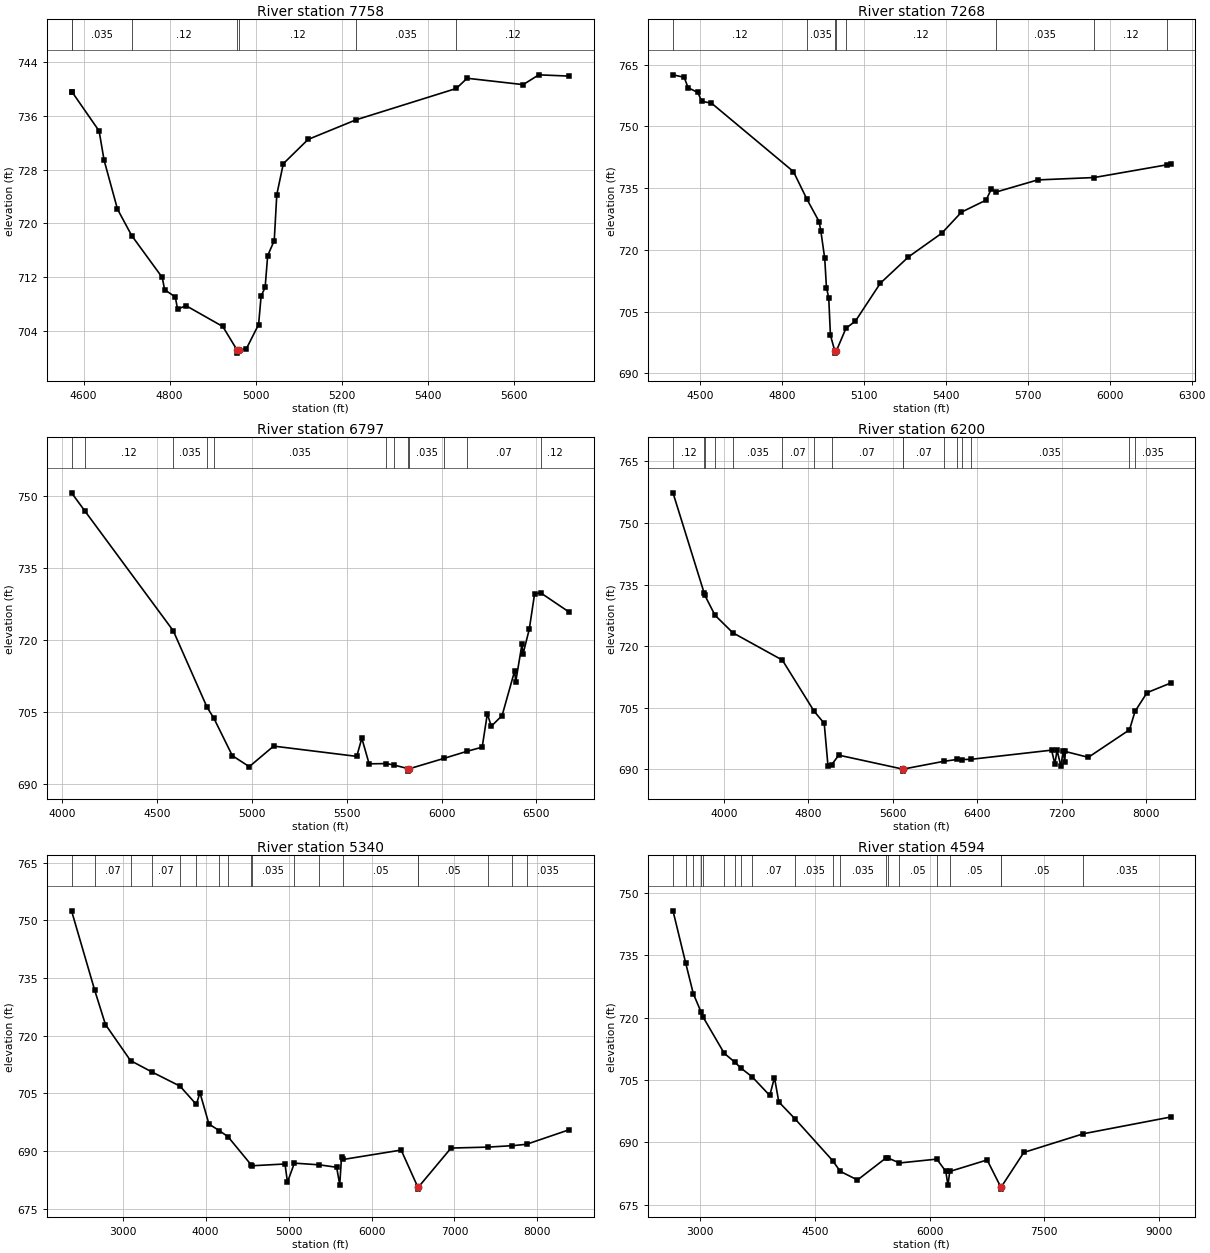
Type RM Length L Ch R = 1,7758,490,490,490
BEGIN DESCRIPTION:
Dry Comal Creek Tributary 18 4.0
END DESCRIPTION:
XS GIS Cut Line= 3
      2214274.98     13787974.99      2213875.00     13787825.00
      2213260.43     13787432.31
#Sta/Elev= 30
  4572.0  739.54  4573.6  739.54  4636.1  733.76  4647.6  729.42  4678.8  722.11
  4711.8  718.18  4782.9  711.93  4788.3  710.12  4813.2  709.02  4818.5  707.21
  4838.1  707.73  4923.5  704.63  4956.4  701.16  4956.9  700.66  4961.8  701.16
  4977.8  701.24  5006.8  704.91  5012.7  709.19  5022.0  710.44  5027.9  715.18
  5043.2  717.43  5049.1  724.28  5064.3  728.89  5121.8  732.50  5233.1  735.42
  5466.5  740.10  5491.5  741.62  5621.8  740.67  5658.2  742.13  5728.5  741.94
#Mann=7,-1,0
  4572.0    0.12       0  4573.6   0.035       0  4711.8    0.12       0
  4956.4    0.05       0  4961.8    0.12       0  5233.1   0.035       0
  5466.5    0.12       0
Bank Sta=4956.4,4961.8
Exp/Cntr=0.3,0.1

Type RM Length L Ch R = 1,7268,471,471,471
BEGIN DESCRIPTION:
Dry Comal Creek Tributary 18 3.0
END DESCRIPTION:
XS GIS Cut Line= 3
      2214684.04     13788203.14      2214325.00     13787725.00
      2213184.01     13787286.46
#Sta/Elev= 30
  4402.3  762.50  4443.0  761.91  4457.6  759.37  4493.0  758.22  4507.6  756.06
  4543.0  755.63  4843.0  739.00  4892.3  732.30  4936.7  726.88  4943.0  724.68
  4957.5  717.91  4963.8  710.82  4972.1  708.37  4978.4  699.26  4994.4  695.42
  4994.8  694.92  4999.8  695.42  5035.1  700.95  5069.9  702.71  5160.9  711.89
  5263.9  718.29  5385.9  724.05  5457.8  729.16  5547.9  732.08  5567.2  734.81
  5583.5  734.02  5736.5  736.98  5943.4  737.56  6210.4  740.66  6222.6  740.90
#Mann=8,-1,0
  4402.3    0.12       0  4892.3   0.035       0  4994.4   0.035       0
  4999.8   0.035       0  5035.1    0.12       0  5583.5   0.035       0
  5943.4    0.12       0  6210.4   0.035       0
Bank Sta=4994.4,4999.8
Exp/Cntr=0.3,0.1

Type RM Length L Ch R = 1,6797,597,597,597
BEGIN DESCRIPTION:
Dry Comal Creek Tributary 18 2.0
END DESCRIPTION:
XS GIS Cut Line= 3
      2214989.59     13788154.51      2214525.00     13787325.00
      2212921.89     13786849.49
#Sta/Elev= 30
  4048.9  750.73  4117.9  747.02  4585.2  722.00  4763.4  706.07  4798.8  703.83
  4896.5  696.00  4985.9  693.71  5114.4  697.99  5552.5  695.85  5579.2  699.64
  5617.7  694.30  5707.4  694.35  5747.2  694.07  5824.7  693.28  5825.2  692.78
  5830.2  693.28  6012.8  695.44  6132.3  696.89  6213.8  697.77  6240.9  704.71
  6261.8  702.13  6318.7  704.34  6385.2  713.69  6390.4  711.33  6423.6  719.23
  6428.9  717.12  6462.1  722.34  6490.1  729.68  6521.9  729.91  6671.8  725.91
#Mann=12,-1,0
  4048.9   0.035       0  4117.9    0.12       0  4585.2   0.035       0
  4763.4    0.12       0  4798.8   0.035       0  5707.4    0.12       0
  5747.2   0.035       0  5824.7   0.035       0  5830.2   0.035       0
  6012.8    0.12       0  6132.3    0.07       0  6521.9    0.12       0
Bank Sta=5824.7,5830.2
Exp/Cntr=0.3,0.1

Type RM Length L Ch R = 1,6200,860,860,860
BEGIN DESCRIPTION:
Dry Comal Creek Tributary 18 1.0
END DESCRIPTION:
XS GIS Cut Line= 3
      2215267.38     13788328.15      2214940.99     13786946.20
      2212178.59     13785155.50
#Sta/Elev= 30
  3517.4  757.33  3813.5  732.85  3819.2  732.36  3915.3  727.52  4084.3  723.25
  4553.0  716.60  4855.4  704.09  4949.6  701.20  4985.9  690.70  5020.9  691.14
  5087.5  693.45  5692.5  690.06  5693.0  689.56  5698.0  690.06  6080.6  691.94
  6210.5  692.41  6259.0  692.39  6337.9  692.43  7103.6  694.67  7133.9  691.27
  7155.0  694.66  7191.3  690.72  7212.4  694.40  7227.5  691.87  7233.5  694.34
  7451.0  692.92  7841.0  699.63  7893.4  704.11  8007.2  708.67  8229.4  710.99
#Mann=16,-1,0
  3517.4    0.12       0  3813.5    0.07       0  3819.2    0.12       0
  3915.3    0.07       0  4084.3   0.035       0  4553.0    0.07       0
  4855.4   0.035       0  5020.9    0.07       0  5692.5   0.035       0
  5698.0    0.07       0  6080.6    0.07       0  6210.5    0.12       0
  6259.0    0.07       0  6337.9   0.035       0  7841.0    0.05       0
  7893.4   0.035       0
Bank Sta=5692.5,5698
Exp/Cntr=0.3,0.1

Type RM Length L Ch R = 1,5340,746,746,746
BEGIN DESCRIPTION:
X18991
END DESCRIPTION:
XS GIS Cut Line= 3
      2216052.10     13788723.96      2215468.77     13786453.15
      2212302.09     13784633.70
#Sta/Elev= 30
  2384.4  752.49  2664.5  731.77  2793.0  722.92  3095.1  713.54  3360.2  710.50
  3691.6  706.90  3888.7  702.13  3932.0  705.19  4040.6  697.04  4166.8  695.29
  4269.1  693.77  4552.6  686.34  4555.8  686.18  4957.1  686.65  4987.0  681.90
  5070.0  686.87  5369.6  686.43  5579.6  685.80  5617.0  681.29  5638.6  688.44
  5660.3  687.83  6357.4  690.27  6558.8  680.61  6559.3  680.11  6564.3  680.61
  6958.4  690.79  7403.9  691.04  7698.7  691.41  7868.3  691.77  8381.1  695.54
#Mann=18,-1,0
  2384.4    0.12       0  2664.5    0.07       0  3095.1    0.12       0
  3360.2    0.07       0  3691.6    0.12       0  3888.7   0.035       0
  4166.8    0.07       0  4269.1   0.035       0  4552.6    0.07       0
  4555.8   0.035       0  5070.0    0.05       0  5369.6   0.035       0
  5660.3    0.05       0  6558.8   0.035       0  6564.3    0.05       0
  7403.9   0.035       0  7698.7    0.07       0  7868.3   0.035       0
Bank Sta=6558.8,6564.3
Exp/Cntr=0.3,0.1

Type RM Length L Ch R = 1,4594,666,666,666
BEGIN DESCRIPTION:
X18990
END DESCRIPTION:
XS GIS Cut Line= 3
      2216253.48     13788723.94      2215711.83     13786133.70
      2212219.35     13784488.14
#Sta/Elev= 30
  2644.5  745.64  2809.2  733.20  2910.4  725.73  3013.5  721.26  3034.4  720.24
  3315.1  711.41  3455.1  709.27  3530.5  707.91  3680.9  705.75  3910.2  701.29
  3971.5  705.60  4028.6  699.74  4240.3  695.68  4731.7  685.66  4832.9  683.06
  5057.5  681.00  5429.1  686.27  5456.0  686.28  5606.7  685.08  6094.8  686.01
  6212.4  683.07  6240.7  679.74  6264.1  683.04  6753.0  685.81  6931.6  679.30
  6932.0  678.80  6937.2  679.30  7232.8  687.61  8012.0  692.10  9151.5  696.11
#Mann=20,-1,0
  2644.5    0.12       0  2809.2    0.07       0  2910.4   0.035       0
  3013.5   0.045       0  3034.4    0.07       0  3315.1    0.12       0
  3455.1    0.07       0  3530.5    0.12       0  3680.9    0.07       0
  4240.3   0.035       0  4731.7    0.07       0  4832.9   0.035       0
  5429.1    0.07       0  5456.0   0.035       0  5606.7    0.05       0
  6094.8   0.035       0  6264.1    0.05       0  6931.6   0.035       0
  6937.2    0.05       0  8012.0   0.035       0
Bank Sta=6931.6,6937.2
Exp/Cntr=0.3,0.1

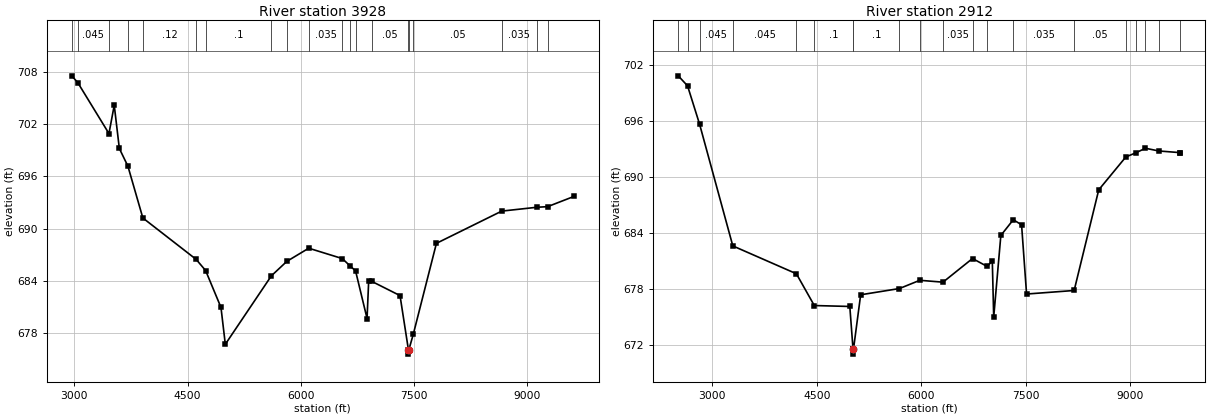
Type RM Length L Ch R = 1,3928,1016,1016,1016
BEGIN DESCRIPTION:
X18989
END DESCRIPTION:
XS GIS Cut Line= 3
      2216934.05     13788487.89      2216288.21     13786092.04
      2212428.55     13784523.18
#Sta/Elev= 30
  2967.1  707.54  3045.8  706.77  3459.4  700.91  3529.4  704.16  3597.0  699.20
  3710.6  697.16  3908.3  691.22  4613.6  686.47  4739.0  685.19  4942.6  680.95
  5000.1  676.72  5610.0  684.58  5814.8  686.24  6104.7  687.75  6548.8  686.56
  6653.8  685.70  6724.6  685.15  6876.8  679.68  6898.4  684.01  6937.3  683.95
  7313.4  682.31  7424.5  676.09  7424.9  675.59  7430.2  676.09  7488.3  677.85
  7795.3  688.31  8660.2  692.01  9125.7  692.45  9267.3  692.52  9614.8  693.69
#Mann=20,-1,0
  2967.1    0.07       0  3045.8   0.045       0  3459.4   0.035       0
  3710.6   0.045       0  3908.3    0.12       0  4613.6    0.12       0
  4739.0     0.1       0  5610.0   0.035       0  5814.8    0.07       0
  6104.7   0.035       0  6548.8   0.035       0  6653.8    0.05       0
  6724.6   0.035       0  6937.3    0.05       0  7424.5    0.05       0
  7430.2   0.035       0  7488.3    0.05       0  8660.2   0.035       0
  9125.7    0.07       0  9267.3   0.035       0
Bank Sta=7424.5,7430.2
Exp/Cntr=0.3,0.1

Type RM Length L Ch R = 1,2912,0,0,0
BEGIN DESCRIPTION:
X18988
END DESCRIPTION:
XS GIS Cut Line= 4
      2217093.77     13788314.24      2217302.10     13786182.31
      2216677.10     13785467.04      2212663.24     13784543.43
#Sta/Elev= 30
  2510.7  700.85  2644.4  699.78  2817.5  695.67  3294.5  682.65  4207.5  679.67
  4464.7  676.27  4974.8  676.17  5021.3  671.57  5021.8  671.07  5027.1  671.57
  5130.5  677.42  5688.3  678.09  5980.1  678.97  6313.1  678.77  6736.9  681.30
  6948.7  680.45  7021.2  681.06  7041.4  675.03  7144.0  683.77  7322.7  685.45
  7441.6  684.91  7513.4  677.50  8196.7  677.88  8549.8  688.65  8939.3  692.17
  9079.0  692.60  9220.9  693.10  9411.7  692.81  9720.4  692.63  9721.4  692.63
#Mann=20,-1,0
  2510.7   0.045       0  2644.4   0.035       0  2817.5   0.045       0
  3294.5   0.045       0  4207.5    0.12       0  4464.7     0.1       0
  5021.3    0.05       0  5027.1     0.1       0  5688.3    0.07       0
  5980.1   0.035       0  6313.1   0.035       0  6736.9    0.05       0
  6948.7   0.035       0  7322.7   0.035       0  8196.7    0.05       0
  8939.3   0.035       0  9079.0    0.05       0  9220.9   0.035       0
  9411.7    0.07       0  9720.4   0.035       0
Bank Sta=5021.3,5027.1
Exp/Cntr=0.3,0.1

Chan Stop Cuts=-1