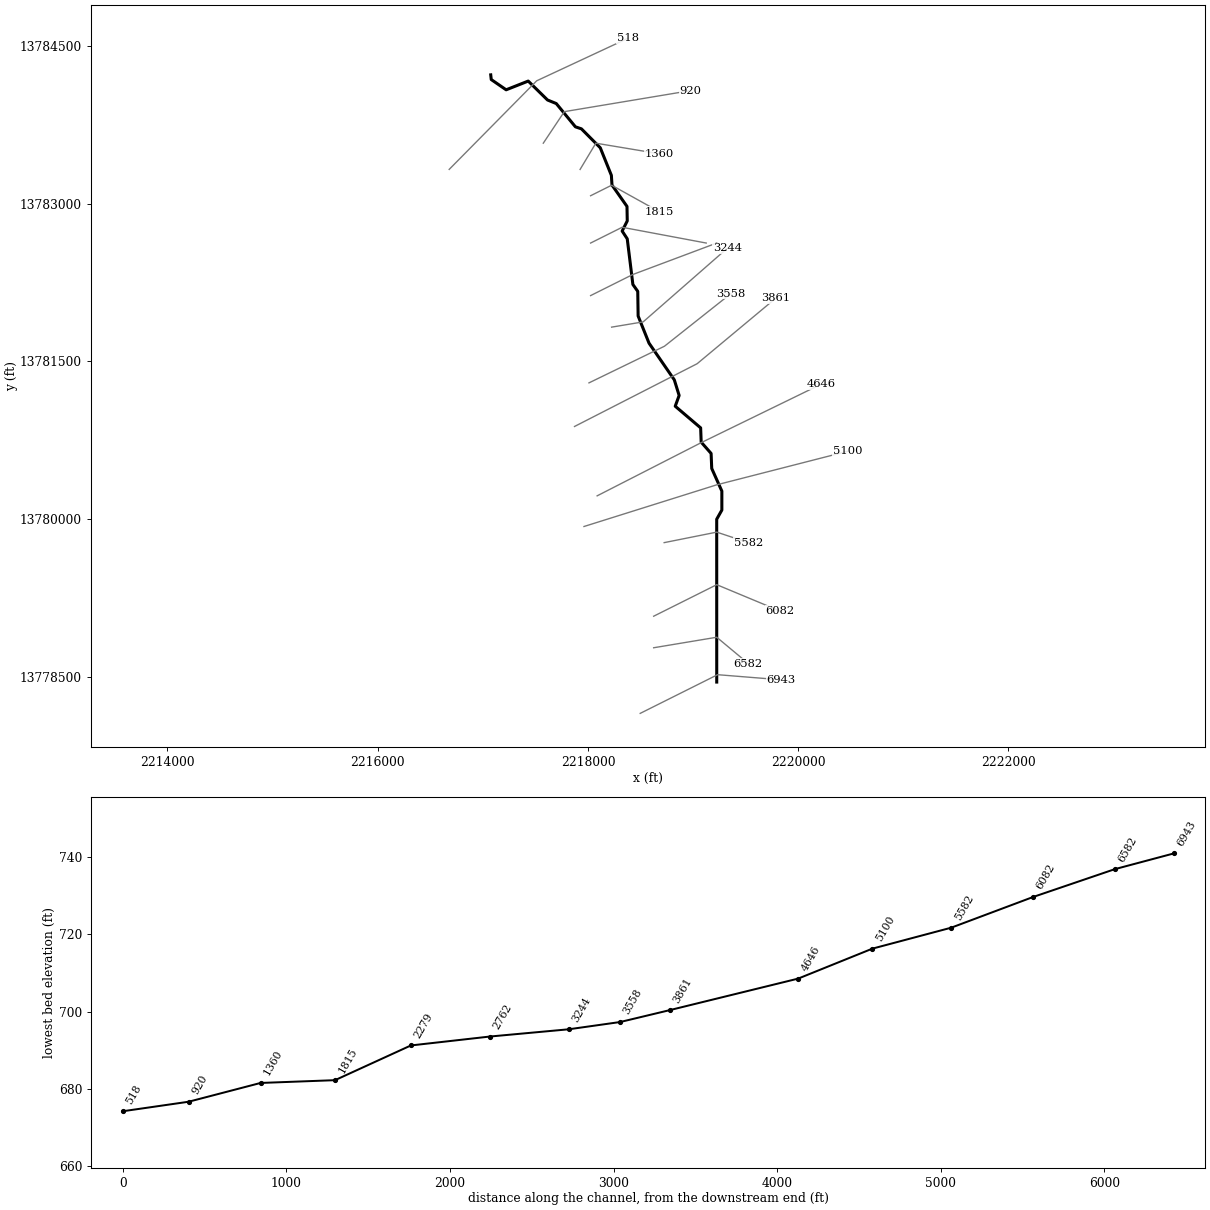
--- Dry Comal Creek Tributary 19.prj (project) ---

Proj Title=Dry Comal Creek Tributary 19 Base Level Engineering
Current Plan=p01
Default Exp/Contr=0.3,0.1
English Units
Geom File=g01
Flow File=f01
Plan File=p01
BEGIN DESCRIPTION:
Dry Comal Creek Tributary 19
END DESCRIPTION:

--- Dry Comal Creek Tributary 19.p01 (plan) ---

Plan Title=Multiple Run
Short Identifier=Multiple
Geom File=g01
Flow File=f01
Subcritical Flow
K Sum by GR= 0
Std Step Tol= 0.01
Critical Tol= 0.01
Num of Std Step Trials= 20
Max Error Tol= 0.3
Flow Tol Ratio= 0.001
Split Flow NTrial= 30
Split Flow Tol= 0.02
Split Flow Ratio= 0.02
Log Output Level= 0
Friction Slope Method= 1
Unsteady Friction Slope Method= 2
Unsteady Bridges Friction Slope Method= 1
Parabolic Critical Depth
Global Vel Dist=  1 , 1 , 1
Global Log Level= 0
CheckData=True
Encroach Param= -1, 0, 0, 0
BEGIN DESCRIPTION:
Multiple Run
END DESCRIPTION:

--- Dry Comal Creek Tributary 19.f01 (steady flow) ---

Flow Title=Multiple
Number of Profiles=7
Profile Names=10-year,25-year,50-year,1pct_min,100-year,1pct_plu,500-year
River Rch & RM= Dry Comal Creek ,Reach-1,6943
    1004    1690    2337    1565    3122    6230    5518
River Rch & RM= Dry Comal Creek ,Reach-1,3861
    1353    2306    3215    2167    4324    8627    7749
Boundary for River Rch & Prof#=Dry Comal Creek ,Reach-1,1
Up Type=0
Dn Type=3
Dn Slope=0.005
Boundary for River Rch & Prof#=Dry Comal Creek ,Reach-1,2
Up Type=0
Dn Type=3
Dn Slope=0.005
Boundary for River Rch & Prof#=Dry Comal Creek ,Reach-1,3
Up Type=0
Dn Type=3
Dn Slope=0.005
Boundary for River Rch & Prof#=Dry Comal Creek ,Reach-1,4
Up Type=0
Dn Type=3
Dn Slope=0.005
Boundary for River Rch & Prof#=Dry Comal Creek ,Reach-1,5
Up Type=0
Dn Type=3
Dn Slope=0.005
Boundary for River Rch & Prof#=Dry Comal Creek ,Reach-1,6
Up Type=0
Dn Type=3
Dn Slope=0.005
Boundary for River Rch & Prof#=Dry Comal Creek ,Reach-1,7
Up Type=0
Dn Type=3
Dn Slope=0.005

--- Dry Comal Creek Tributary 19.g01 (geometry) ---

Geom Title=Existing Conditions

River Reach=Dry Comal Creek ,Reach-1
Reach XY= 30
      2219225.00     13778448.59      2219224.72     13779997.84
      2219273.62     13780084.66      2219273.62     13780265.34
      2219177.39     13780480.53      2219171.44     13780623.53
      2219077.08     13780730.87      2219071.92     13780866.69
      2218830.11     13781072.71      2218867.41     13781174.99
      2218821.38     13781323.50      2218580.84     13781672.71
      2218477.26     13781930.94      2218473.62     13782165.34
      2218427.26     13782230.94      2218373.60     13782665.35
      2218325.24     13782739.10      2218373.77     13782835.50
      2218371.26     13782973.44      2218228.62     13783176.50
      2218222.67     13783269.03      2218117.14     13783531.17
      2217937.98     13783711.27      2217880.62     13783730.62
      2217698.47     13783951.98      2217615.32     13783985.78
      2217431.74     13784165.87      2217221.59     13784082.80
      2217079.92     13784180.32      2217075.00     13784225.00

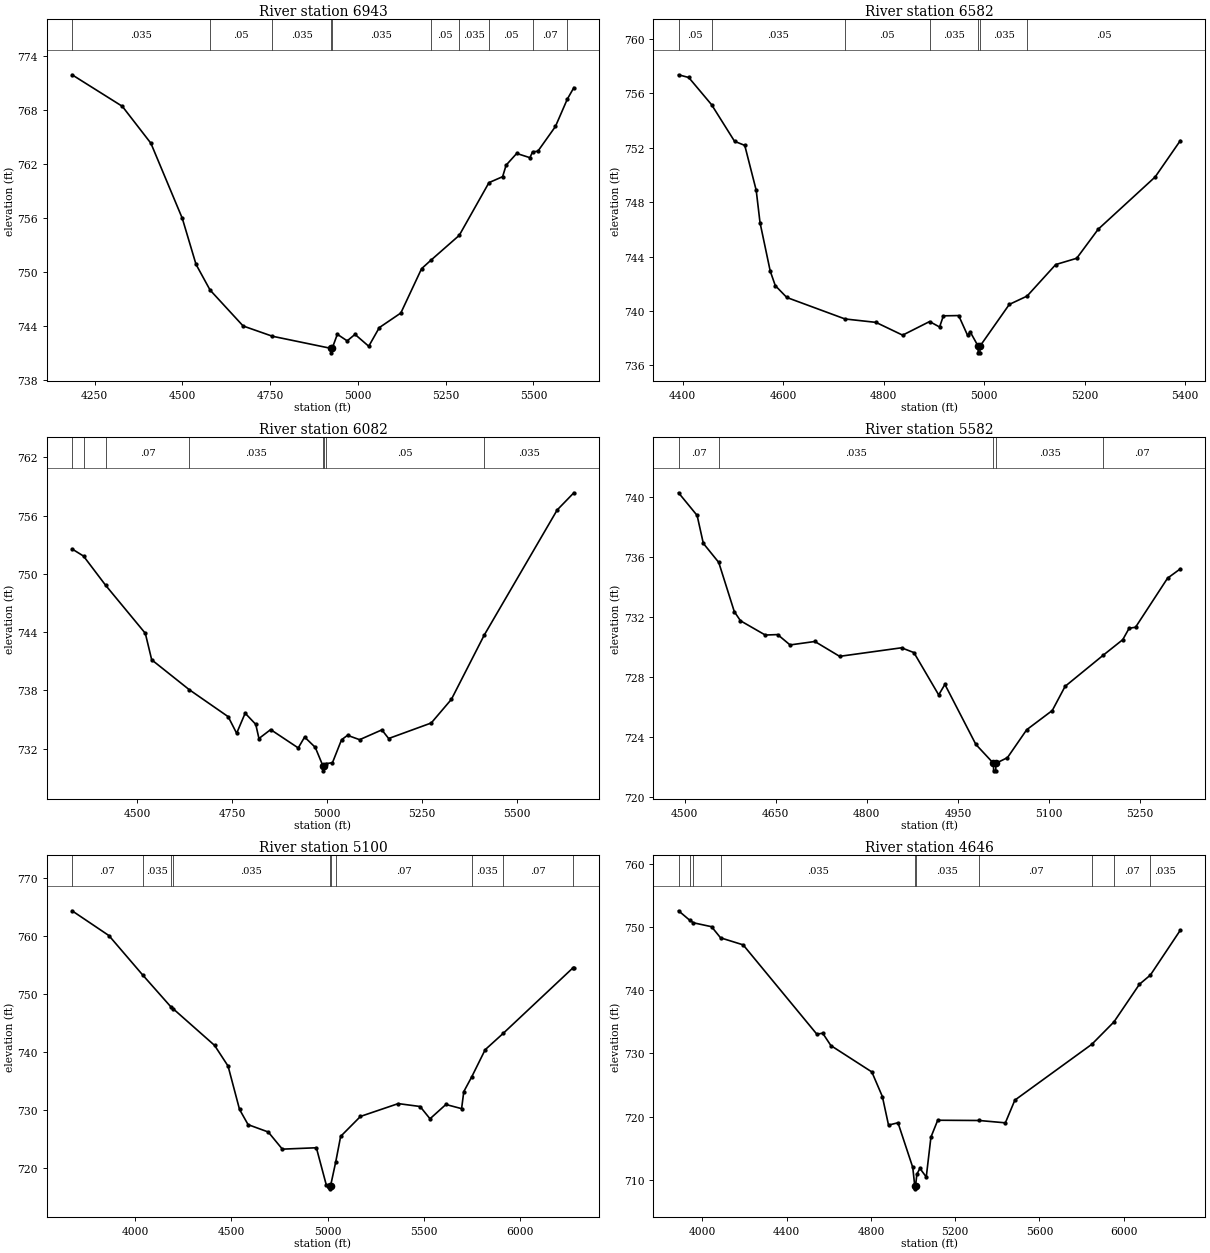
Type RM Length L Ch R = 1,6943,361,361,361
BEGIN DESCRIPTION:
X18996
END DESCRIPTION:
XS GIS Cut Line= 3
      2218497.03     13778150.73      2219233.10     13778518.77
      2219837.29     13778470.16
#Sta/Elev= 30
  4186.1  771.87  4329.2  768.37  4410.6  764.27  4500.0  755.94  4539.1  750.83
  4579.1  747.98  4673.3  743.99  4756.8  742.85  4922.9  741.51  4923.1  741.01
  4926.9  741.51  4941.6  743.07  4969.6  742.34  4991.9  743.06  5031.0  741.74
  5061.1  743.81  5122.4  745.43  5181.5  750.35  5207.8  751.28  5288.8  754.05
  5373.4  759.90  5412.3  760.56  5422.3  761.84  5452.4  763.14  5490.0  762.67
  5497.7  763.32  5512.6  763.38  5562.7  766.13  5596.7  769.18  5615.2  770.44
#Mann=10,-1,0
  4186.1   0.035       0  4579.1    0.05       0  4756.8   0.035       0
  4922.9   0.035       0  4926.9   0.035       0  5207.8    0.05       0
  5288.8   0.035       0  5373.4    0.05       0  5497.7    0.07       0
  5596.7    0.05       0
Bank Sta=4922.9,4926.9
Exp/Cntr=0.3,0.1

Type RM Length L Ch R = 1,6582,500,500,500
BEGIN DESCRIPTION:
Dry Comal Creek Tributary 19 13.0
END DESCRIPTION:
XS GIS Cut Line= 3
      2218624.98     13778775.00      2219225.00     13778875.00
      2219524.99     13778625.01
#Sta/Elev= 30
  4391.7  757.37  4412.0  757.17  4457.5  755.17  4503.2  752.48  4523.5  752.18
  4546.3  748.88  4553.9  746.50  4574.2  742.94  4584.3  741.87  4607.2  741.00
  4723.1  739.42  4784.6  739.17  4837.8  738.23  4891.4  739.23  4911.3  738.83
  4918.9  739.65  4949.3  739.67  4967.1  738.21  4972.1  738.48  4987.9  737.43
  4988.1  736.93  4991.6  736.93  4991.9  737.43  5050.1  740.49  5085.4  741.10
  5142.5  743.42  5184.2  743.88  5227.1  746.02  5340.4  749.86  5390.5  752.53
#Mann=7,-1,0
  4391.7    0.05       0  4457.5   0.035       0  4723.1    0.05       0
  4891.4   0.035       0  4987.9   0.035       0  4991.9   0.035       0
  5085.4    0.05       0
Bank Sta=4987.9,4991.9
Exp/Cntr=0.3,0.1

Type RM Length L Ch R = 1,6082,500,500,500
BEGIN DESCRIPTION:
Dry Comal Creek Tributary 19 12.0
END DESCRIPTION:
XS GIS Cut Line= 3
      2218625.02     13779075.01      2219225.00     13779375.00
      2219825.00     13779125.00
#Sta/Elev= 30
  4329.2  752.57  4359.3  751.84  4417.5  748.83  4522.0  743.88  4538.8  741.15
  4637.7  738.07  4740.1  735.29  4762.4  733.58  4784.8  735.65  4812.7  734.50
  4821.1  733.04  4851.9  733.96  4924.5  732.07  4941.3  733.19  4969.3  732.13
  4989.6  730.21  4989.9  729.71  4993.6  730.21  4997.6  730.45  5014.6  730.55
  5038.5  732.91  5054.2  733.37  5086.1  732.92  5144.6  733.93  5162.5  733.04
  5274.6  734.64  5327.7  737.08  5414.0  743.69  5606.1  756.59  5650.0  758.36
#Mann=8,-1,0
  4329.2    0.05       0  4359.3   0.035       0  4417.5    0.07       0
  4637.7   0.035       0  4989.6    0.05       0  4993.6   0.035       0
  4997.6    0.05       0  5414.0   0.035       0
Bank Sta=4989.6,4993.6
Exp/Cntr=0.3,0.1

Type RM Length L Ch R = 1,5582,482,482,482
BEGIN DESCRIPTION:
Dry Comal Creek Tributary 19 11.0
END DESCRIPTION:
XS GIS Cut Line= 3
      2218724.98     13779775.00      2219225.00     13779875.00
      2219524.95     13779775.02
#Sta/Elev= 30
  4490.1  740.29  4520.7  738.78  4530.9  736.92  4556.3  735.65  4581.9  732.37
  4592.1  731.76  4632.9  730.81  4653.3  730.84  4673.7  730.15  4714.5  730.38
  4755.3  729.39  4857.2  729.96  4877.6  729.64  4918.4  726.82  4928.6  727.52
  4979.6  723.52  5008.6  722.26  5008.8  721.76  5012.3  721.76  5012.6  722.26
  5031.6  722.64  5063.3  724.50  5105.4  725.78  5126.5  727.39  5189.4  729.47
  5221.4  730.50  5231.9  731.26  5242.5  731.33  5295.2  734.60  5316.2  735.22
#Mann=5,-1,0
  4490.1    0.07       0  4556.3   0.035       0  5008.6   0.035       0
  5012.6   0.035       0  5189.4    0.07       0
Bank Sta=5008.6,5012.6
Exp/Cntr=0.3,0.1

Type RM Length L Ch R = 1,5100,454,454,454
BEGIN DESCRIPTION:
Dry Comal Creek Tributary 19 10.0
END DESCRIPTION:
XS GIS Cut Line= 3
      2217962.25     13779928.48      2219225.00     13780325.00
      2220469.18     13780643.76
#Sta/Elev= 30
  3672.2  764.32  3863.7  760.04  4038.4  753.27  4188.4  747.64  4196.1  747.45
  4412.8  741.09  4482.9  737.52  4542.5  730.04  4587.0  727.41  4691.8  726.14
  4765.1  723.18  4941.9  723.42  4993.1  717.04  5011.6  716.83  5011.8  716.33
  5015.6  716.83  5042.6  720.99  5068.0  725.38  5171.2  728.83  5367.4  731.04
  5480.9  730.54  5532.5  728.42  5615.1  730.89  5696.7  730.17  5708.0  733.11
  5748.9  735.63  5819.1  740.34  5912.2  743.14  6273.2  754.40  6280.1  754.52
#Mann=10,-1,0
  3672.2    0.07       0  4038.4   0.035       0  4188.4    0.07       0
  4196.1   0.035       0  5011.6   0.035       0  5015.6   0.035       0
  5042.6    0.07       0  5748.9   0.035       0  5912.2    0.07       0
  6273.2   0.035       0
Bank Sta=5011.6,5015.6
Exp/Cntr=0.3,0.1

Type RM Length L Ch R = 1,4646,785,785,785
BEGIN DESCRIPTION:
Dry Comal Creek Tributary 19 9.0
END DESCRIPTION:
XS GIS Cut Line= 3
      2218087.31     13780220.18      2219075.00     13780725.00
      2220219.22     13781282.66
#Sta/Elev= 30
  3886.9  752.54  3939.1  751.07  3957.6  750.64  4043.7  750.02  4086.6  748.26
  4193.6  747.15  4543.5  733.02  4571.3  733.18  4610.1  731.22  4804.5  727.05
  4854.5  723.16  4883.8  718.64  4928.7  719.01  4998.9  711.94  5008.1  709.06
  5008.4  708.56  5012.2  709.06  5018.4  710.88  5032.7  711.80  5062.9  710.43
  5085.1  716.74  5117.3  719.41  5314.2  719.37  5438.4  719.00  5483.5  722.59
  5849.1  731.43  5953.9  734.96  6075.0  740.92  6126.8  742.37  6269.0  749.47
#Mann=10,-1,0
  3886.9    0.07       0  3939.1   0.035       0  3957.6    0.07       0
  4086.6   0.035       0  5008.1   0.035       0  5012.2   0.035       0
  5314.2    0.07       0  5849.1   0.035       0  5953.9    0.07       0
  6126.8   0.035       0
Bank Sta=5008.1,5012.2
Exp/Cntr=0.3,0.1

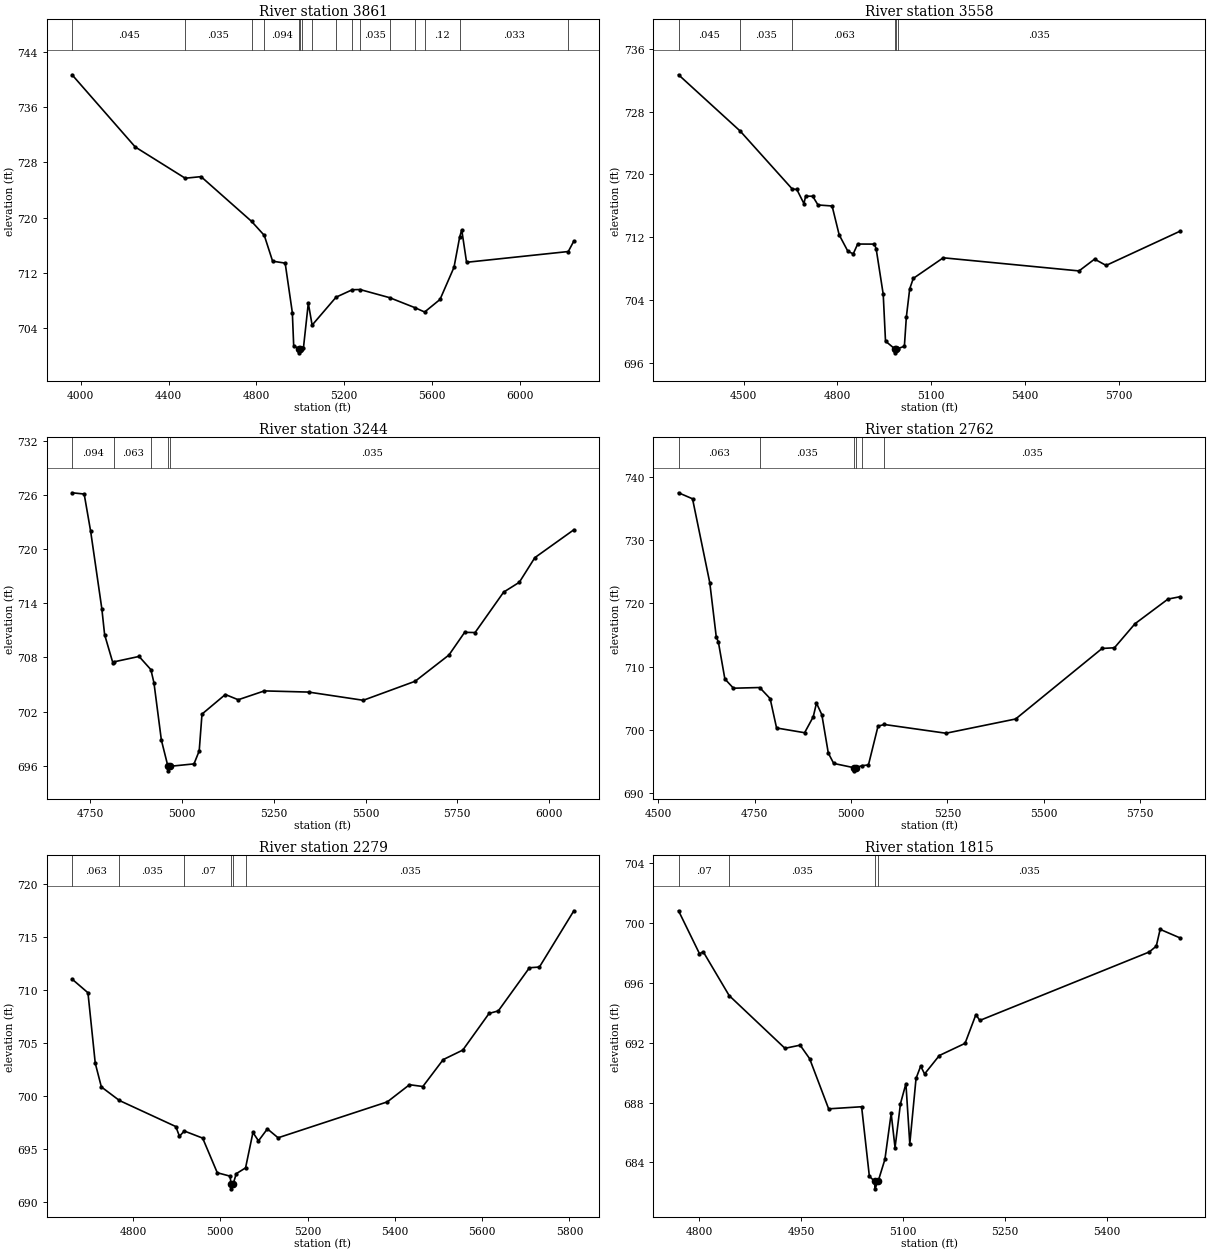
Type RM Length L Ch R = 1,3861,303,303,303
BEGIN DESCRIPTION:
X18995
END DESCRIPTION:
XS GIS Cut Line= 3
      2217871.99     13780879.88      2219038.66     13781477.10
      2219787.41     13782101.06
#Sta/Elev= 30
  3960.7  740.71  4248.4  730.24  4475.9  725.71  4548.1  725.94  4778.0  719.46
  4836.1  717.42  4874.0  713.68  4931.2  713.40  4963.9  706.22  4970.0  701.45
  4995.5  700.89  4995.9  700.39  5000.1  700.89  5007.5  701.03  5014.4  701.09
  5036.6  707.59  5054.0  704.41  5163.0  708.46  5236.9  709.54  5272.0  709.57
  5406.9  708.39  5522.1  706.94  5566.4  706.31  5636.4  708.13  5700.1  712.79
  5725.9  717.17  5735.3  718.23  5757.4  713.52  6220.6  715.08  6246.0  716.60
#Mann=16,-1,0
  3960.7   0.045       0  4475.9   0.035       0  4778.0   0.063       0
  4836.1   0.094       0  4995.5    0.05       0  5000.1   0.094       0
  5007.5   0.035       0  5054.0    0.12       0  5163.0   0.035       0
  5236.9    0.12       0  5272.0   0.035       0  5406.9    0.12       0
  5522.1   0.035       0  5566.4    0.12       0  5725.9   0.033       0
  6220.6    0.07       0
Bank Sta=4995.5,5000.1
Exp/Cntr=0.3,0.1

Type RM Length L Ch R = 1,3558,314,314,314
BEGIN DESCRIPTION:
Dry Comal Creek Tributary 19 7.0
END DESCRIPTION:
XS GIS Cut Line= 3
      2218009.53     13781294.73      2218727.89     13781643.55
      2219359.96     13782144.36
#Sta/Elev= 30
  4292.0  732.68  4489.2  725.52  4655.5  718.16  4670.4  718.09  4693.0  716.30
  4698.6  717.24  4721.1  717.23  4738.1  716.12  4783.2  715.99  4805.8  712.32
  4833.9  710.21  4850.9  709.91  4865.0  711.15  4918.6  711.14  4924.2  710.52
  4946.7  704.76  4954.0  698.80  4983.9  697.81  4984.3  697.31  4988.7  697.81
  4994.5  697.86  5014.4  698.15  5020.7  701.87  5031.4  705.45  5042.9  706.78
  5138.7  709.40  5573.0  707.73  5622.7  709.23  5659.6  708.43  5897.0  712.80
#Mann=6,-1,0
  4292.0   0.045       0  4489.2   0.035       0  4655.5   0.063       0
  4983.9   0.035       0  4988.7   0.063       0  4994.5   0.035       0
Bank Sta=4983.9,4988.7
Exp/Cntr=0.3,0.1

Type RM Length L Ch R = 1,3244,482,482,482
BEGIN DESCRIPTION:
Dry Comal Creek Tributary 19 6.0
END DESCRIPTION:
XS GIS Cut Line= 3
      2218224.98     13781825.00      2218525.00     13781875.00
      2219325.02     13782575.02
#Sta/Elev= 30
  4700.2  726.25  4733.2  726.11  4750.9  721.96  4781.3  713.40  4788.9  710.52
  4811.7  707.35  4815.5  707.52  4882.7  708.11  4914.9  706.65  4923.3  705.19
  4943.5  698.84  4961.4  695.93  4961.7  695.43  4966.3  695.93  5032.4  696.20
  5046.6  697.64  5054.2  701.72  5117.8  703.89  5152.9  703.31  5224.1  704.29
  5344.6  704.16  5493.6  703.25  5635.0  705.36  5727.1  708.27  5769.8  710.78
  5798.3  710.76  5876.1  715.24  5918.8  716.33  5961.1  719.06  6067.4  722.15
#Mann=5,-1,0
  4700.2   0.094       0  4815.5   0.063       0  4914.9   0.035       0
  4961.4   0.035       0  4966.3   0.035       0
Bank Sta=4961.4,4966.3
Exp/Cntr=0.3,0.1

Type RM Length L Ch R = 1,2762,483,483,483
BEGIN DESCRIPTION:
Dry Comal Creek Tributary 19 5.0
END DESCRIPTION:
XS GIS Cut Line= 3
      2218025.02     13782125.01      2218425.00     13782325.00
      2219225.00     13782625.00
#Sta/Elev= 30
  4552.8  737.47  4589.1  736.52  4633.8  723.28  4650.6  714.73  4656.2  713.88
  4673.0  708.06  4695.3  706.60  4763.3  706.71  4790.4  704.96  4807.1  700.32
  4879.8  699.57  4902.2  702.08  4910.6  704.25  4924.5  702.42  4941.3  696.35
  4955.3  694.72  5007.3  694.05  5007.7  693.55  5012.2  694.05  5029.2  694.37
  5045.4  694.48  5070.3  700.61  5086.7  700.87  5246.5  699.49  5427.2  701.74
  5651.5  712.88  5683.5  712.99  5736.9  716.79  5822.4  720.68  5854.4  721.06
#Mann=6,-1,0
  4552.8   0.063       0  4763.3   0.035       0  5007.3   0.035       0
  5012.2   0.035       0  5029.2    0.07       0  5086.7   0.035       0
Bank Sta=5007.3,5012.2
Exp/Cntr=0.3,0.1

Type RM Length L Ch R = 1,2279,464,464,464
BEGIN DESCRIPTION:
Dry Comal Creek Tributary 19 4.0
END DESCRIPTION:
XS GIS Cut Line= 3
      2218024.97     13782624.98      2218325.00     13782775.00
      2219125.01     13782625.00
#Sta/Elev= 30
  4660.6  711.04  4697.0  709.75  4713.7  703.10  4727.7  700.86  4769.0  699.58
  4898.2  697.12  4906.6  696.20  4917.6  696.70  4959.7  696.03  4993.2  692.76
  5022.3  692.44  5024.9  691.74  5025.3  691.24  5029.9  691.74  5036.7  692.67
  5058.0  693.22  5074.9  696.56  5087.6  695.77  5108.0  696.90  5132.5  696.06
  5382.7  699.45  5433.5  701.07  5464.1  700.90  5510.7  703.44  5555.6  704.34
  5615.8  707.80  5637.0  708.04  5708.2  712.11  5731.1  712.18  5810.0  717.49
#Mann=6,-1,0
  4660.6   0.063       0  4769.0   0.035       0  4917.6    0.07       0
  5024.9    0.05       0  5029.9    0.07       0  5058.0   0.035       0
Bank Sta=5024.9,5029.9
Exp/Cntr=0.3,0.1

Type RM Length L Ch R = 1,1815,455,455,455
BEGIN DESCRIPTION:
Dry Comal Creek Tributary 19 3.0
END DESCRIPTION:
XS GIS Cut Line= 3
      2218024.96     13783074.98      2218225.00     13783175.00
      2218674.97     13782925.01
#Sta/Elev= 30
  4769.3  700.80  4800.1  697.94  4805.7  698.06  4843.8  695.14  4925.9  691.62
  4948.2  691.83  4962.2  690.93  4990.2  687.58  5038.7  687.72  5050.1  683.08
  5057.9  682.74  5058.3  682.24  5063.0  682.74  5073.0  684.21  5082.2  687.27
  5087.9  684.99  5095.9  687.93  5103.9  689.26  5109.6  685.25  5118.8  689.61
  5125.6  690.43  5131.4  689.91  5153.1  691.14  5190.9  691.95  5206.9  693.87
  5212.6  693.48  5462.0  698.05  5472.3  698.44  5478.0  699.56  5507.7  698.98
#Mann=4,-1,0
  4769.3    0.07       0  4843.8   0.035       0  5057.9   0.035       0
  5063.0   0.035       0
Bank Sta=5057.9,5063
Exp/Cntr=0.3,0.1

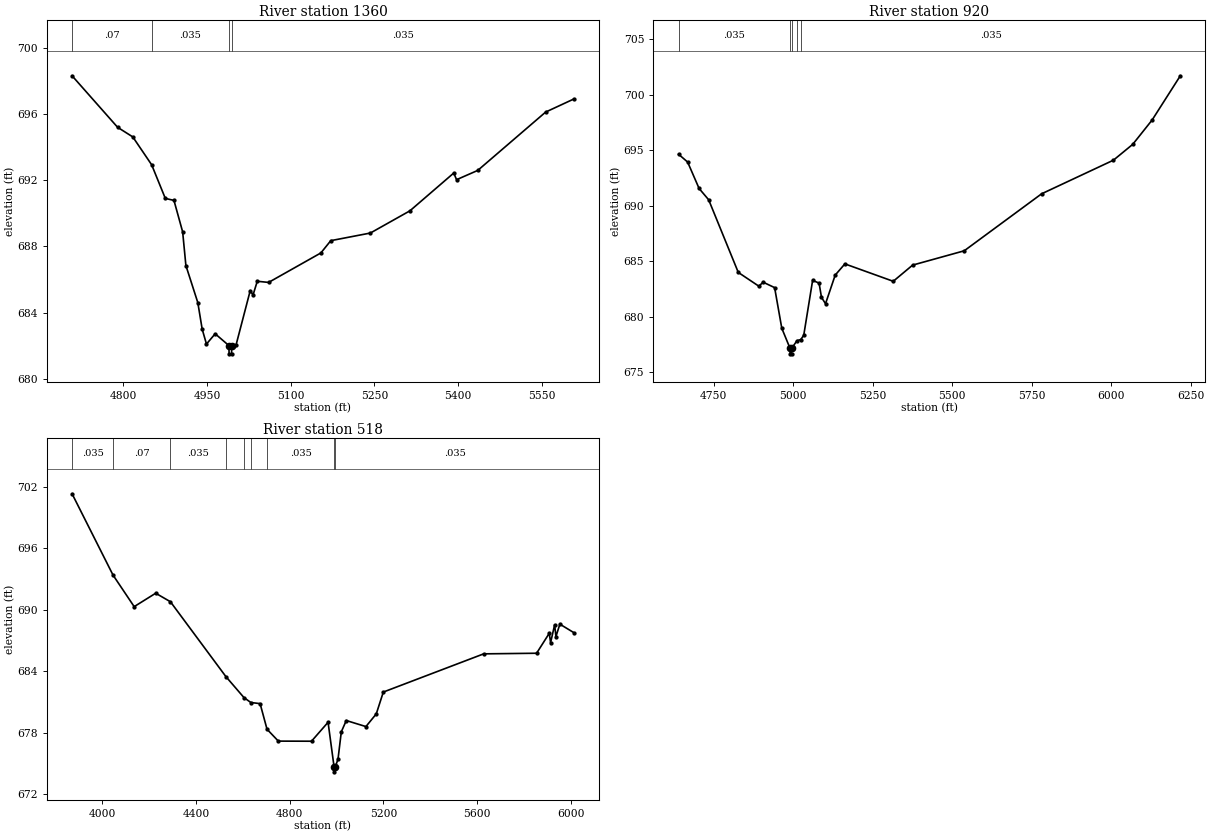
Type RM Length L Ch R = 1,1360,440,440,440
BEGIN DESCRIPTION:
Dry Comal Creek Tributary 19 2.0
END DESCRIPTION:
XS GIS Cut Line= 3
      2217924.99     13783324.98      2218075.00     13783575.00
      2218674.95     13783475.01
#Sta/Elev= 30
  4708.0  698.30  4789.7  695.19  4816.9  694.61  4850.7  692.93  4875.2  690.90
  4890.7  690.78  4906.3  688.88  4912.1  686.85  4933.5  684.61  4941.3  683.01
  4949.0  682.11  4964.6  682.73  4989.2  682.02  4989.6  681.52  4994.0  681.52
  4994.4  682.02  5002.1  682.06  5027.5  685.34  5032.5  685.07  5040.1  685.90
  5060.4  685.83  5154.2  687.61  5171.9  688.35  5242.9  688.81  5313.8  690.15
  5392.4  692.43  5397.5  692.03  5435.5  692.59  5557.2  696.11  5607.8  696.90
#Mann=4,-1,0
  4708.0    0.07       0  4850.7   0.035       0  4989.2   0.035       0
  4994.4   0.035       0
Bank Sta=4989.2,4994.4
Exp/Cntr=0.3,0.1

Type RM Length L Ch R = 1,920,402,402,402
BEGIN DESCRIPTION:
Dry Comal Creek Tributary 19 1.0
END DESCRIPTION:
XS GIS Cut Line= 3
      2217574.99     13783574.98      2217775.00     13783875.00
      2218974.97     13784075.00
#Sta/Elev= 30
  4639.4  694.65  4668.0  693.94  4704.0  691.56  4734.1  690.54  4827.2  683.99
  4891.8  682.75  4905.3  683.11  4941.4  682.62  4963.9  678.96  4989.8  677.15
  4990.3  676.65  4994.7  676.65  4995.1  677.15  5011.5  677.83  5023.6  677.94
  5032.9  678.32  5060.8  683.27  5081.1  683.03  5088.7  681.74  5101.4  681.17
  5131.8  683.75  5162.2  684.76  5314.2  683.19  5375.1  684.65  5537.3  685.94
  5780.6  691.08  6006.2  694.11  6067.0  695.54  6127.8  697.73  6216.5  701.72
#Mann=5,-1,0
  4639.4   0.035       0  4989.8   0.035       0  4995.1   0.035       0
  5011.5    0.07       0  5023.6   0.035       0
Bank Sta=4989.8,4995.1
Exp/Cntr=0.3,0.1

Type RM Length L Ch R = 1,518,0,0,0
BEGIN DESCRIPTION:
X18994
END DESCRIPTION:
XS GIS Cut Line= 3
      2216679.79     13783325.57      2217512.15     13784168.29
      2218379.10     13784572.41
#Sta/Elev= 30
  3872.0  701.34  4046.8  693.40  4137.0  690.32  4228.8  691.63  4291.6  690.80
  4528.3  683.49  4605.4  681.44  4634.8  680.96  4674.3  680.85  4703.8  678.35
  4752.1  677.19  4893.6  677.18  4964.3  679.03  4989.8  674.69  4990.3  674.19
  4995.3  674.69  5006.7  675.43  5020.8  678.10  5042.0  679.20  5125.8  678.61
  5170.0  679.85  5200.0  681.98  5628.2  685.71  5854.0  685.77  5908.1  687.72
  5913.7  686.80  5931.0  688.55  5936.5  687.40  5953.3  688.61  6013.0  687.78
#Mann=9,-1,0
  3872.0   0.035       0  4046.8    0.07       0  4291.6   0.035       0
  4528.3    0.07       0  4605.4   0.063       0  4634.8    0.07       0
  4703.8   0.035       0  4989.8   0.035       0  4995.3   0.035       0
Bank Sta=4989.8,4995.3
Exp/Cntr=0.3,0.1

Chan Stop Cuts=-1