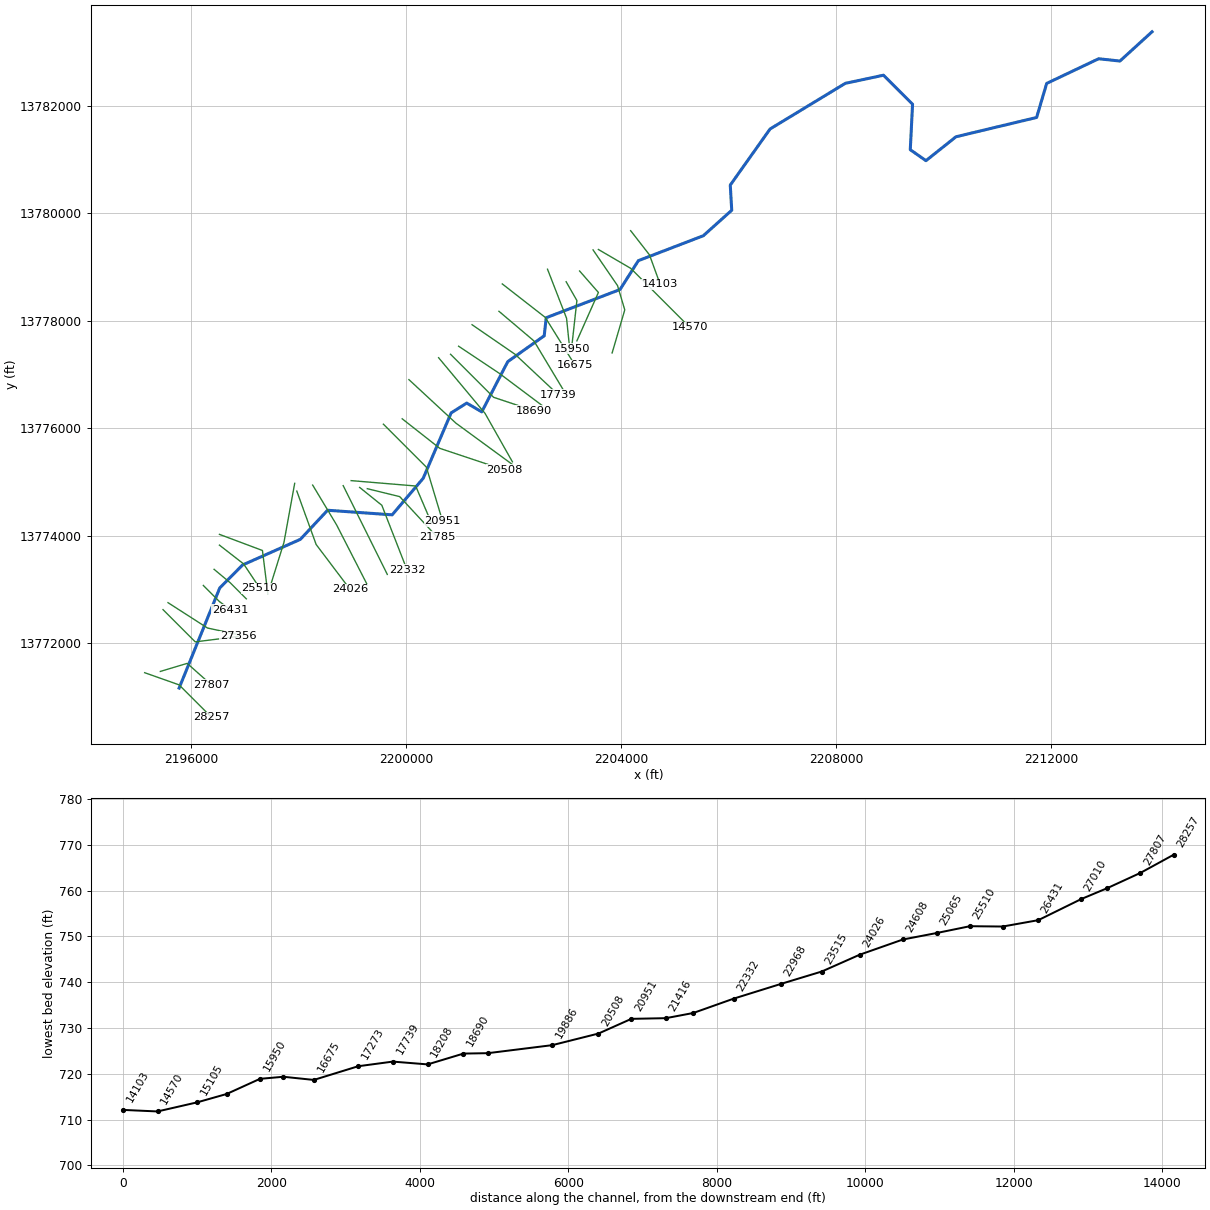
--- Dry Comal Creek Tributary 24.prj (project) ---

Proj Title=Dry Comal Creek Tributary 24 Base Level Engineering
Current Plan=p01
Default Exp/Contr=0.3,0.1
English Units
Geom File=g01
Flow File=f01
Plan File=p01
Y Axis Title=Elevation
X Axis Title(PF)=Main Channel Distance
X Axis Title(XS)=Station
BEGIN DESCRIPTION:
Dry Comal Creek Tributary 24
END DESCRIPTION:
DSS Export Rating Curves= 0
DSS Export Rating Curve Sorted= 0
DSS Export Volume Flow Curves= 0
DXF OffsetX= 0
DXF OffsetY= 0
DXF ScaleX= 1
DXF ScaleY= 10

--- Dry Comal Creek Tributary 24.p01 (plan) ---

Plan Title=Multiple Run
Short Identifier=Multiple
Geom File=g01
Flow File=f01
Subcritical Flow
K Sum by GR= 0
Std Step Tol= 0.01
Critical Tol= 0.01
Num of Std Step Trials= 20
Max Error Tol= 0.3
Flow Tol Ratio= 0.001
Split Flow NTrial= 30
Split Flow Tol= 0.02
Split Flow Ratio= 0.02
Log Output Level= 0
Friction Slope Method= 1
Unsteady Friction Slope Method= 2
Unsteady Bridges Friction Slope Method= 1
Parabolic Critical Depth
Global Vel Dist=  1 , 1 , 1
Global Log Level= 0
CheckData=True
Encroach Param= -1, 0, 0, 0
BEGIN DESCRIPTION:
Multiple Run
END DESCRIPTION:

--- Dry Comal Creek Tributary 24.f01 (steady flow) ---

Flow Title=Multiple
Program Version=4.10
Number of Profiles= 7
Profile Names=10-year,25-year,50-year,1pct_min,100-year,1pct_plu,500-year
River Rch & RM=Dry Comal Creek,Reach-1         ,28257
     311     478     621     391     780    1557    1217
River Rch & RM=Dry Comal Creek,Reach-1         ,27356
     545     864    1147     736    1469    2931    2385
River Rch & RM=Dry Comal Creek,Reach-1         ,25065
     912    1493    2024    1326    2645    5277    4475
River Rch & RM=Dry Comal Creek,Reach-1         ,24026
    1109    1843    2523    1667    3326    6636    5731
River Rch & RM=Dry Comal Creek,Reach-1         ,20951
    1496    2513    3467    2307    4603    9185    8043
River Rch & RM=Dry Comal Creek,Reach-1         ,19886
    1651    2795    3872    2587    5162   10299    9094
River Rch & RM=Dry Comal Creek,Reach-1         ,17273
    1806    3051    4223    2818    5622   11218    9875
River Rch & RM=Dry Comal Creek,Reach-1         ,14570
    2207    3754    5219    3495    6973   13912   12337
River Rch & RM=Dry Comal Creek,Reach-1         ,10510
    2220    3764    5221    3487    6958   13882   12247
River Rch & RM=Dry Comal Creek,Reach-1         ,5424
    2332    3958    5495    3672    7326   14617   12909
River Rch & RM=Dry Comal Creek,Reach-1         ,2600
    2843    4867    6796    4566    9111   18178   16230
Boundary for River Rch & Prof#=Dry Comal Creek,Reach-1         , 1
Up Type= 0
Dn Type= 3
Dn Slope=0.005
Boundary for River Rch & Prof#=Dry Comal Creek,Reach-1         , 2
Up Type= 0
Dn Type= 3
Dn Slope=0.005
Boundary for River Rch & Prof#=Dry Comal Creek,Reach-1         , 3
Up Type= 0
Dn Type= 3
Dn Slope=0.005
Boundary for River Rch & Prof#=Dry Comal Creek,Reach-1         , 4
Up Type= 0
Dn Type= 3
Dn Slope=0.005
Boundary for River Rch & Prof#=Dry Comal Creek,Reach-1         , 5
Up Type= 0
Dn Type= 3
Dn Slope=0.005
Boundary for River Rch & Prof#=Dry Comal Creek,Reach-1         , 6
Up Type= 0
Dn Type= 3
Dn Slope=0.005
Boundary for River Rch & Prof#=Dry Comal Creek,Reach-1         , 7
Up Type= 0
Dn Type= 3
Dn Slope=0.005
DSS Import GetInterval= 0
DSS Import GetPeak= 0
DSS Import FillOption= 0

--- Dry Comal Creek Tributary 24.g01 (geometry) ---

Geom Title=Existing Conditions
Program Version=4.10

River Reach=Dry Comal Creek ,Reach-1
Reach XY= 30
        2195775.     13771165.93      2196530.45     13773027.47
      2196954.91     13773455.21      2198031.19     13773932.83
      2198536.33      13774473.6      2199738.32     13774388.37
      2200316.02     13775068.28      2200835.47     13776284.82
      2201124.99     13776467.47      2201405.03     13776303.97
      2201888.63     13777238.21      2202566.87     13777718.92
       2202604.4     13778055.79      2203977.59     13778580.14
      2204318.55     13779117.25      2205527.31     13779580.83
       2206055.4     13780054.84      2206028.33     13780523.31
      2206768.93     13781566.87      2208168.33      13782415.7
      2208878.31     13782566.93      2209419.54     13782027.45
      2209377.24     13781180.93      2209669.29     13780976.89
      2210226.47     13781421.46       2211727.3     13781780.83
      2211914.95     13782414.41      2212881.11      13782873.2
      2213277.42     13782830.53        2213875.       13783375.

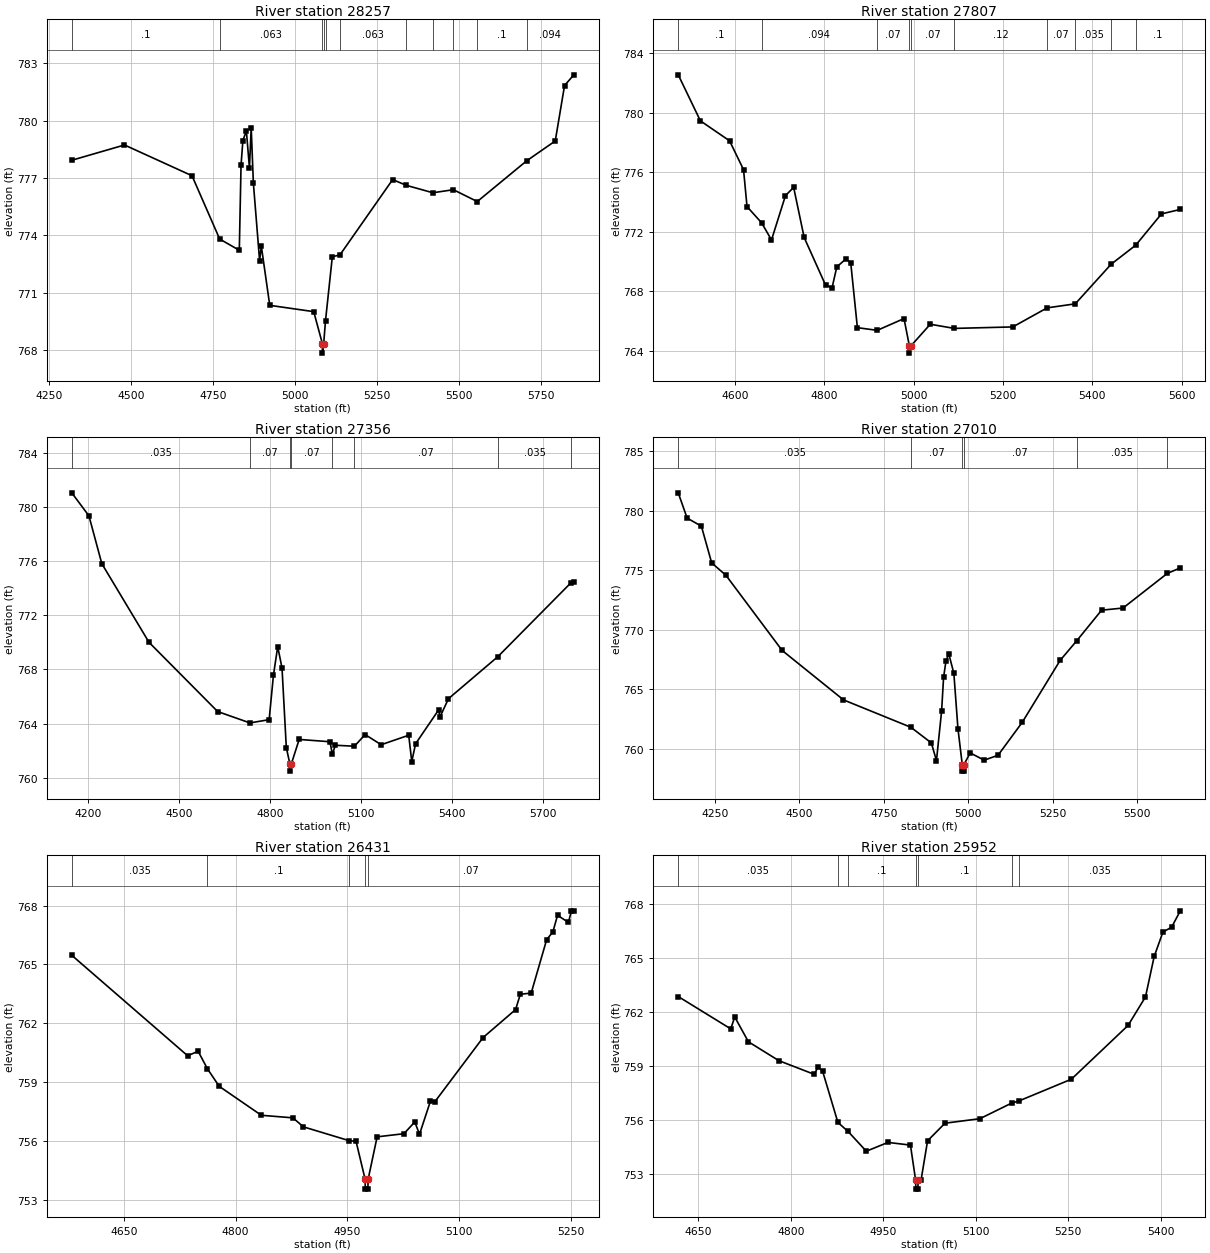
Type RM Length L Ch R = 1 ,28257   ,450,450,450
BEGIN DESCRIPTION:
Dry Comal Creek Tributary 24 46.0
END DESCRIPTION:
XS GIS Cut Line= 3
      2195133.71     13771451.52        2195775.       13771225.
      2196375.03     13770624.97
#Sta/Elev= 30
    4320  777.93  4480.5  778.73  4686.1  777.12  4770.3  773.81  4830.1  773.22
  4835.4  777.68    4841  778.96  4851.6  779.47    4861  777.53  4866.3  779.64
  4872.9  776.74  4891.9  772.68  4897.2  773.43  4922.8  770.34  5056.7  770.01
    5083  768.34  5083.2  767.84    5087  768.34  5092.6  769.54  5113.3  772.88
  5136.6  772.98  5297.1  776.92  5338.3  776.62  5419.5  776.23  5481.9  776.39
  5554.6  775.77    5705   777.9  5792.1  778.94  5820.4  781.84  5848.7   782.4
#Mann= 11 ,-1 , 0
    4320      .1       0  4770.3    .063       0    5083     .05       0
    5087    .063       0  5092.6    .094       0  5136.6    .063       0
  5338.3    .094       0  5419.5      .1       0  5481.9    .094       0
  5554.6      .1       0    5705    .094       0
Bank Sta=5083,5087
XS Rating Curve= 0 ,0
Exp/Cntr=0.3,0.1

Type RM Length L Ch R = 1 ,27807   ,451,451,451
BEGIN DESCRIPTION:
Dry Comal Creek Tributary 24 45.0
END DESCRIPTION:
XS GIS Cut Line= 3
      2195424.98       13771475.        2195925.       13771625.
      2196374.99     13771225.01
#Sta/Elev= 30
  4473.1  782.54  4522.7  779.45    4588  778.11  4619.3  776.17  4627.1  773.69
  4659.8   772.6  4681.9  771.45  4713.2  774.43  4731.5  774.98    4755  771.62
  4802.9  768.42  4817.6  768.25  4828.1  769.64    4849  770.19  4859.4  769.89
  4874.2  765.56  4918.6  765.38  4978.6  766.17  4990.5  764.35  4990.8  763.85
  4994.5  764.35  5037.4  765.79  5091.2  765.51  5222.2  765.61    5299  766.89
    5362  767.16  5442.3  769.82  5497.4   771.1    5555   773.2  5597.2   773.5
#Mann= 10 ,-1 , 0
  4473.1      .1       0  4659.8    .094       0  4918.6     .07       0
  4990.5     .05       0  4994.5     .07       0  5091.2     .12       0
    5299     .07       0    5362    .035       0  5442.3    .063       0
  5497.4      .1       0
Bank Sta=4990.5,4994.5
XS Rating Curve= 0 ,0
Exp/Cntr=0.3,0.1

Type RM Length L Ch R = 1 ,27356   ,346,346,346
BEGIN DESCRIPTION:
Dry Comal Creek Tributary 24 44.0
END DESCRIPTION:
XS GIS Cut Line= 3
        2195475.       13772625.        2196075.       13772025.
      2196875.05     13772125.01
#Sta/Elev= 30
  4146.8  781.04  4203.4  779.34  4245.8  775.81  4401.4     770  4627.6  764.89
    4734  764.05  4797.3  764.29  4811.5  767.57  4825.6  769.69  4839.8  768.09
  4853.9  762.23    4866  760.99  4866.3  760.49    4870  760.99  4896.3  762.83
  4997.8  762.66  5005.8  761.73  5015.5   762.4  5078.4  762.33  5113.7  763.19
  5166.6  762.44  5257.3  763.14  5267.4   761.2    5280  762.51  5355.6     765
  5360.6   764.5  5388.4  765.84  5551.5  768.95  5792.6  774.41  5801.6  774.49
#Mann= 8 ,-1 , 0
  4146.8    .035       0    4734     .07       0    4866     .05       0
    4870     .07       0  5005.8     .12       0  5078.4     .07       0
  5551.5    .035       0  5792.6    .094       0
Bank Sta=4866,4870
XS Rating Curve= 0 ,0
Exp/Cntr=0.3,0.1

Type RM Length L Ch R = 1 ,27010   ,579,579,579
BEGIN DESCRIPTION:
Dry Comal Creek Tributary 24 43.0
END DESCRIPTION:
XS GIS Cut Line= 3
      2195567.99      13772754.3      2196302.47     13772282.51
       2196902.9     13772153.85
#Sta/Elev= 30
  4141.5   781.5  4167.8  779.38  4210.1   778.7  4240.5  775.62  4282.7  774.58
  4449.2  768.27  4630.9  764.12  4830.6  761.82  4891.1  760.51  4906.3  759.02
  4921.5  763.17  4927.4  766.02  4934.3  767.35  4942.6     768  4957.8  766.35
  4969.9  761.71  4982.9  758.64  4983.2  758.14  4986.7  758.14  4986.9  758.64
  5006.1  759.67  5047.7  759.06  5088.6  759.47  5160.2  762.23  5272.7  767.44
  5321.4  769.07  5395.4  771.65  5458.9  771.83  5589.7  774.73  5628.5   775.2
#Mann= 6 ,-1 , 0
  4141.5    .035       0  4830.6     .07       0  4982.9     .05       0
  4986.9     .07       0  5321.4    .035       0  5589.7    .094       0
Bank Sta=4982.9,4986.9
XS Rating Curve= 0 ,0
Exp/Cntr=0.3,0.1

Type RM Length L Ch R = 1 ,26431   ,479,479,479
BEGIN DESCRIPTION:
Dry Comal Creek Tributary 24 42.0
END DESCRIPTION:
XS GIS Cut Line= 3
        2196225.       13773075.        2196525.       13772775.
      2196725.03     13772624.98
#Sta/Elev= 30
    4580  765.47  4735.6  760.34  4749.7  760.57  4762.1  759.68    4778  758.78
  4834.6   757.3    4877  757.17  4891.1  756.71  4952.9     756  4961.8  755.97
    4974  754.03  4974.2  753.53  4977.7  753.53    4978  754.03  4990.1   756.2
  5026.1  756.36  5040.7  756.96    5047  756.33  5061.6  758.01  5067.8     758
  5132.4  761.27  5176.1   762.7  5182.4  763.48    5197  763.54  5217.8  766.27
  5226.1  766.66  5232.4  767.51    5247  767.15  5251.1  767.74  5254.3  767.74
#Mann= 5 ,-1 , 0
    4580    .035       0  4762.1      .1       0  4952.9     .07       0
    4974     .05       0    4978     .07       0
Bank Sta=4974,4978
XS Rating Curve= 0 ,0
Exp/Cntr=0.3,0.1

Type RM Length L Ch R = 1 ,25952   ,442,442,442
BEGIN DESCRIPTION:
Dry Comal Creek Tributary 24 41.0
END DESCRIPTION:
XS GIS Cut Line= 3
      2196425.03     13773374.97        2196725.       13773125.
      2197024.97     13772825.03
#Sta/Elev= 30
  4617.2  762.86  4702.4  761.06  4708.9  761.72  4731.1  760.34  4780.5  759.29
  4837.8  758.53  4844.3  758.94  4851.5   758.7  4876.3  755.85  4892.8  755.35
  4922.4  754.25  4957.6  754.74    4994  754.59  5002.4  752.64  5002.7  752.14
  5006.2  752.14  5006.4  752.64  5011.2  752.64  5021.8  754.83  5050.1  755.81
  5106.7  756.06  5158.3  756.93  5169.5  757.04  5255.2  758.26  5347.1  761.25
  5375.4  762.84  5389.5  765.09  5403.7  766.45  5417.8  766.72  5431.9  767.63
#Mann= 7 ,-1 , 0
  4617.2    .035       0  4876.3     .12       0  4892.8      .1       0
  5002.4     .05       0  5006.4      .1       0  5158.3     .07       0
  5169.5    .035       0
Bank Sta=5002.4,5006.4
XS Rating Curve= 0 ,0
Exp/Cntr=0.3,0.1

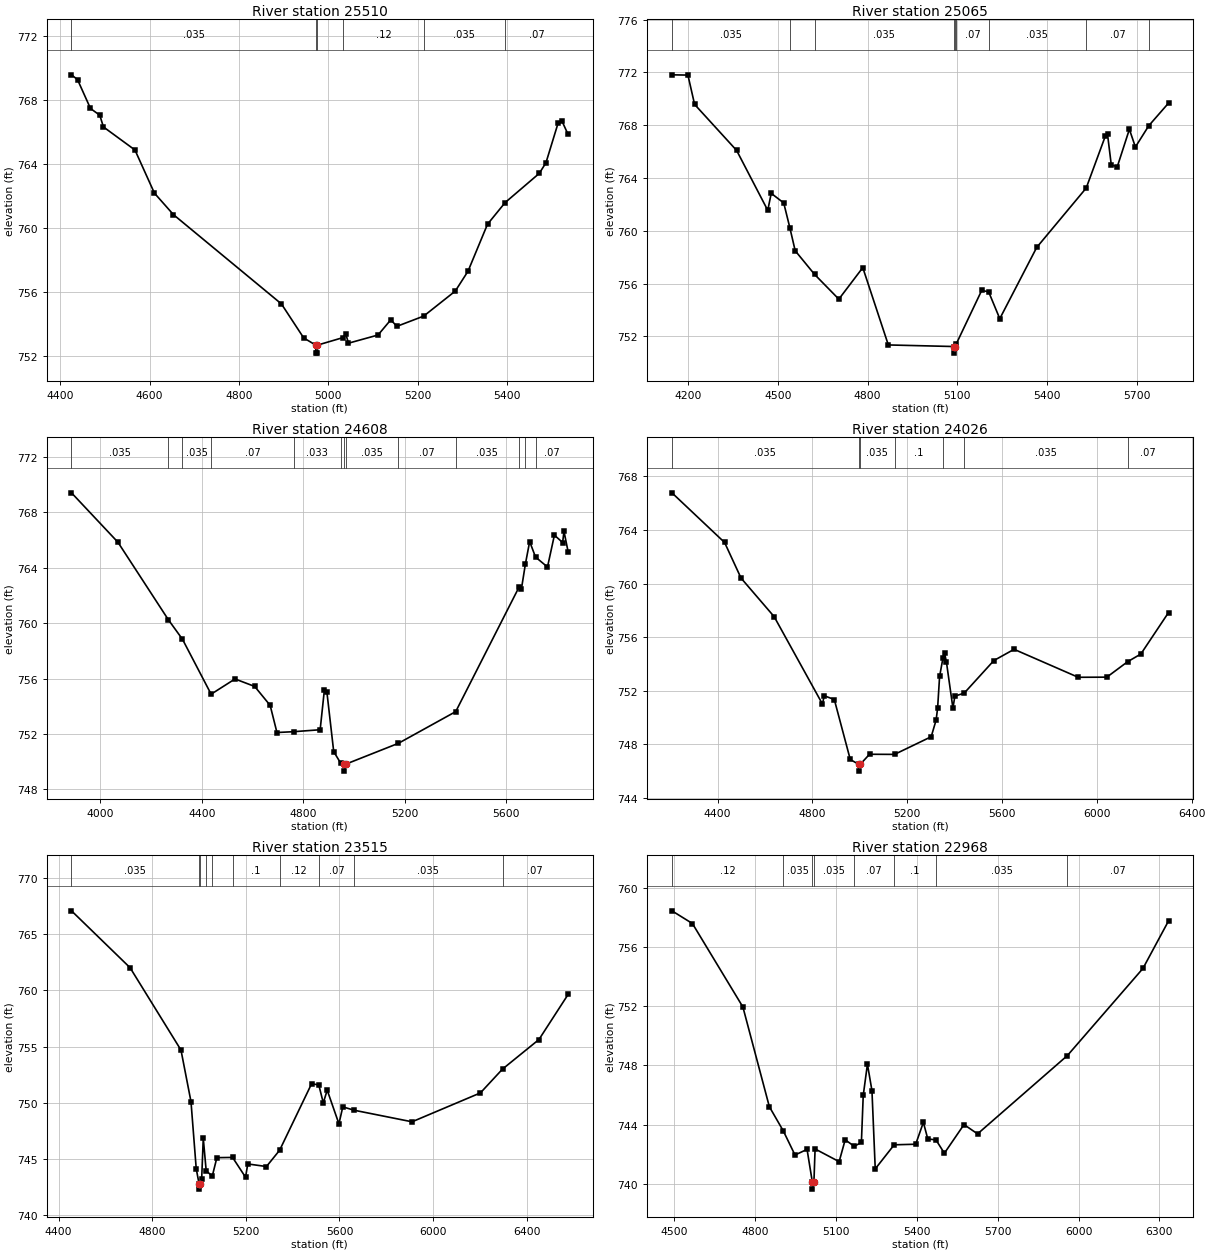
Type RM Length L Ch R = 1 ,25510   ,445,445,445
BEGIN DESCRIPTION:
Dry Comal Creek Tributary 24 40.0
END DESCRIPTION:
XS GIS Cut Line= 3
      2196525.03     13773824.98        2196975.       13773475.
      2197275.01     13773024.98
#Sta/Elev= 30
  4425.5  769.57    4439  769.27    4468  767.47  4488.8  767.05  4496.9  766.32
  4567.5  764.88    4611  762.19  4653.5  760.85  4895.1  755.28  4944.9  753.16
  4971.8  752.71  4972.1  752.21  4975.6  752.21  4975.8  752.71    5033  753.18
  5039.1   753.4  5045.1  752.83  5111.2  753.34  5139.8  754.29  5153.3  753.88
  5213.4  754.52    5284  756.08  5312.5  757.32  5356.1  760.25  5395.5   761.6
  5471.8  763.42  5486.8  764.08  5513.8  766.54  5522.9  766.67  5536.4  765.85
#Mann= 6 ,-1 , 0
  4425.5    .035       0  4971.8    .035       0  4975.8    .035       0
    5033     .12       0  5213.4    .035       0  5395.5     .07       0
Bank Sta=4971.8,4975.8
XS Rating Curve= 0 ,0
Exp/Cntr=0.3,0.1

Type RM Length L Ch R = 1 ,25065   ,457,457,457
BEGIN DESCRIPTION:
Dry Comal Creek Tributary 24 39.0
END DESCRIPTION:
XS GIS Cut Line= 3
      2196524.96     13774025.02        2197325.       13773725.
        2197425.     13772924.97
#Sta/Elev= 30
  4145.8  771.82  4199.2   771.8  4221.5  769.58  4362.1  766.09  4466.2  761.55
  4477.8  762.84  4519.6  762.11    4540  760.24  4557.9  758.49  4622.6   756.7
  4703.9  754.82    4784  757.21  4869.4  751.35  5088.4  751.23  5088.8  750.73
  5093.4  751.23  5096.2  751.41  5181.6  755.48  5204.8  755.38  5242.1  753.34
  5365.6  758.74  5531.1  763.24  5594.8  767.16  5602.4  767.31    5615  764.99
  5635.1  764.86  5675.5  767.69  5695.6  766.35  5740.6  767.97  5806.5  769.68
#Mann= 9 ,-1 , 0
  4145.8    .035       0    4540     .07       0  4622.6    .035       0
  5088.4    .035       0  5093.4    .035       0  5096.2     .07       0
  5204.8    .035       0  5531.1     .07       0  5740.6    .035       0
Bank Sta=5088.4,5093.4
XS Rating Curve= 0 ,0
Exp/Cntr=0.3,0.1

Type RM Length L Ch R = 1 ,24608   ,582,582,582
BEGIN DESCRIPTION:
Dry Comal Creek Tributary 24 38.0
END DESCRIPTION:
XS GIS Cut Line= 3
        2197925.     13774974.98        2197725.       13773875.
      2197474.99     13773074.97
#Sta/Elev= 30
  3887.1  769.42    4070  765.85    4269  760.24  4324.2  758.84  4437.1  754.87
  4531.2  755.97  4608.7  755.43  4669.7  754.06  4696.4   752.1  4762.5  752.16
  4866.6   752.3  4883.1  755.15  4893.3     755    4920  750.72  4947.6  749.88
  4961.9  749.81  4962.3  749.31    4967  749.81  5174.8  751.32  5400.6  753.61
  5650.4  762.62  5659.4  762.47  5675.1  764.28  5691.9   765.9  5714.9  764.78
  5762.1  764.06  5789.3  766.36  5821.8  765.83    5827  766.64  5843.3  765.17
#Mann= 13 ,-1 , 0
  3887.1    .035       0    4269     .07       0  4324.2    .035       0
  4437.1     .07       0  4762.5    .033       0  4947.6    .035       0
  4961.9    .035       0    4967    .035       0  5174.8     .07       0
  5400.6    .035       0  5650.4     .07       0  5675.1    .035       0
  5714.9     .07       0
Bank Sta=4961.9,4967
XS Rating Curve= 0 ,0
Exp/Cntr=0.3,0.1

Type RM Length L Ch R = 1 ,24026   ,511,511,511
BEGIN DESCRIPTION:
Dry Comal Creek Tributary 24 37.0
END DESCRIPTION:
XS GIS Cut Line= 3
      2197964.48     13774829.08      2198323.67     13773837.28
      2198950.45     13773006.93
#Sta/Elev= 30
  4207.3  766.78  4429.4  763.07  4498.8  760.41  4638.5  757.53  4842.3     751
  4849.8  751.62  4892.3  751.34  4959.6  746.86    4996  746.49  4996.4  745.99
  5001.3  746.49  5040.9  747.25  5146.4  747.24  5301.1  748.56  5321.9  749.81
  5328.2  750.71  5336.5  753.06    5351  754.47  5357.3  754.81  5365.2  754.16
  5392.7   750.7    5401  751.59  5440.5  751.82  5565.4  754.25  5650.8  755.09
  5921.4     753  6042.1  753.01  6129.5  754.16  6185.7  754.74  6302.5  757.84
#Mann= 7 ,-1 , 0
  4207.3    .035       0    4996    .035       0  5001.3    .035       0
  5146.4      .1       0    5351     .07       0  5440.5    .035       0
  6129.5     .07       0
Bank Sta=4996,5001.3
XS Rating Curve= 0 ,0
Exp/Cntr=0.3,0.1

Type RM Length L Ch R = 1 ,23515   ,547,547,547
BEGIN DESCRIPTION:
Dry Comal Creek Tributary 24 36.0
END DESCRIPTION:
XS GIS Cut Line= 3
      2198259.31     13774941.73      2198704.32     13774201.85
      2199277.97     13773081.36
#Sta/Elev= 30
  4454.9  767.08  4705.2  762.02  4922.8  754.69  4965.5  750.11  4987.9  744.14
  4999.8  742.82  5000.2  742.32  5005.1  742.82  5011.2  743.24    5018  746.85
  5030.5  743.95  5056.5  743.48  5076.2  745.12  5143.3  745.14  5198.6  743.38
  5208.3  744.56    5288  744.33  5344.3  745.78    5481   751.7  5511.7  751.59
    5531  749.99  5547.6  751.13  5597.7  748.13  5614.3  749.64  5662.6  749.34
  5910.2  748.31  6202.3  750.88  6296.8     753  6452.5  755.63  6577.1  759.64
#Mann= 10 ,-1 , 0
  4454.9    .035       0  4999.8    .035       0  5005.1    .035       0
  5030.5      .1       0  5056.5     .12       0  5143.3      .1       0
  5344.3     .12       0  5511.7     .07       0  5662.6    .035       0
  6296.8     .07       0
Bank Sta=4999.8,5005.1
XS Rating Curve= 0 ,0
Exp/Cntr=0.3,0.1

Type RM Length L Ch R = 1 ,22968   ,636,636,636
BEGIN DESCRIPTION:
X18997
END DESCRIPTION:
XS GIS Cut Line= 2
      2198827.65     13774930.93      2199647.84     13773279.83
#Sta/Elev= 30
  4490.6  758.47  4566.6  757.61    4754  751.96  4852.2  745.21    4904  743.57
  4947.4  741.94  4992.2  742.32  5011.6  740.13  5012.1  739.63  5017.7  740.13
    5022  742.35  5111.3  741.49  5133.7  742.97  5167.4  742.53  5193.9  742.79
  5200.7  745.97  5216.3  748.09  5233.1   746.3  5245.3     741  5315.6  742.63
  5395.5  742.67    5424  744.15  5440.3  743.03  5470.8  742.96    5502  742.06
  5574.8     744  5625.2  743.37  5958.5  748.67  6239.1  754.57  6334.2  757.79
#Mann= 8 ,-1 , 0
  4490.6     .12       0    4904    .035       0  5011.6    .035       0
  5017.7    .035       0  5167.4     .07       0  5315.6      .1       0
  5470.8    .035       0  5958.5     .07       0
Bank Sta=5011.6,5017.7
XS Rating Curve= 0 ,0
Exp/Cntr=0.3,0.1

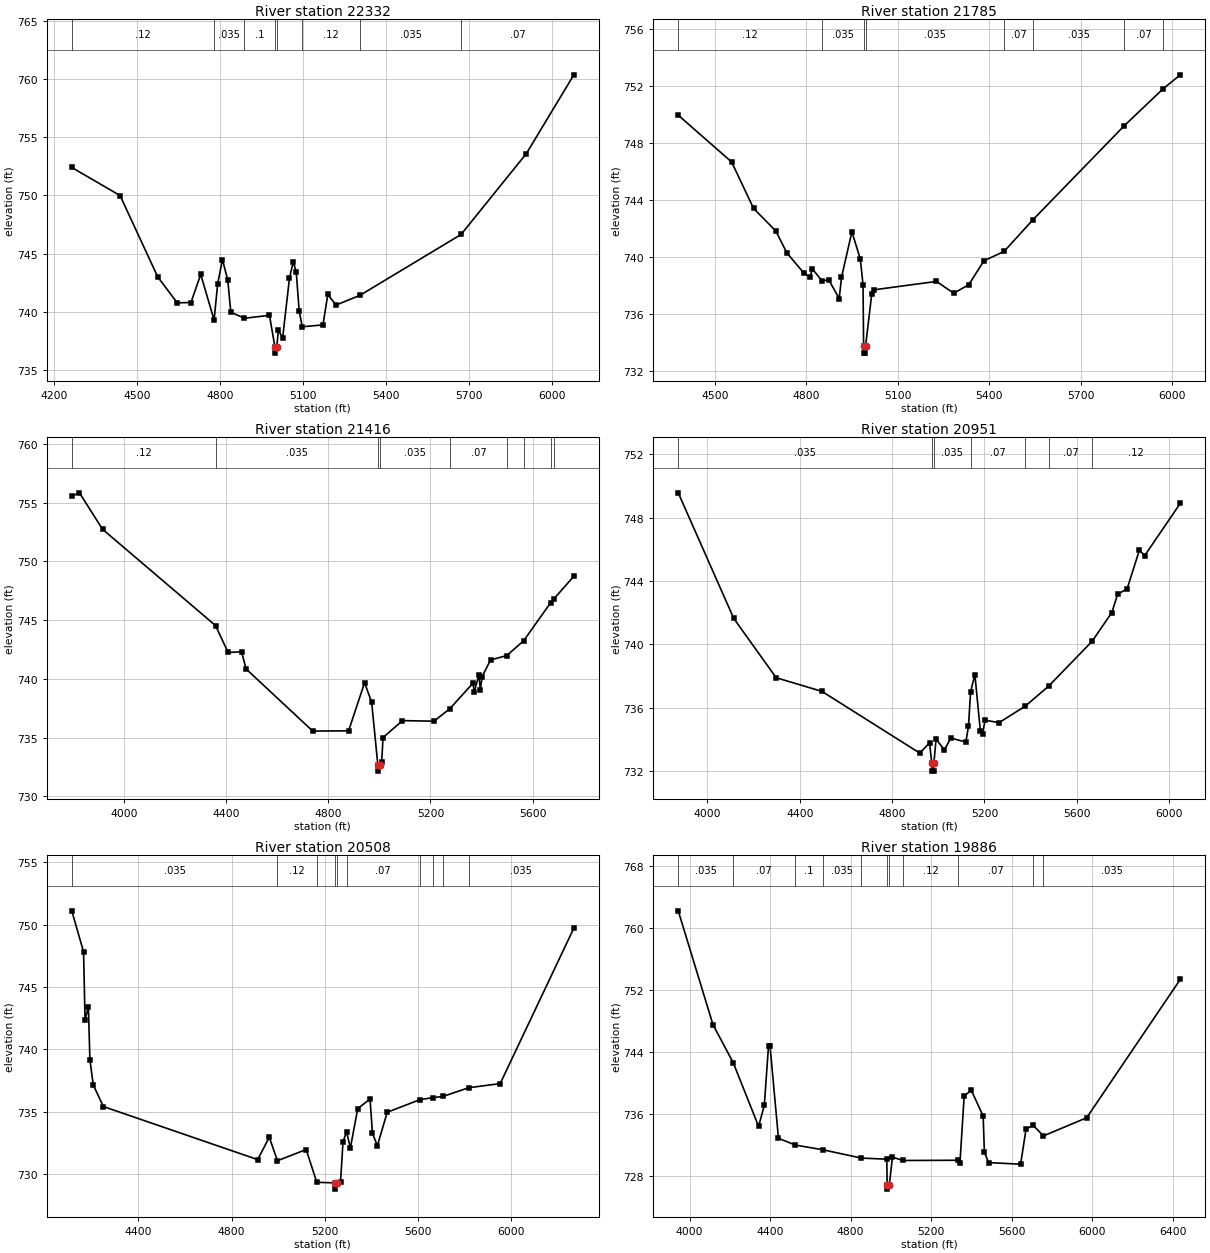
Type RM Length L Ch R = 1 ,22332   ,547,547,547
BEGIN DESCRIPTION:
X18998
END DESCRIPTION:
XS GIS Cut Line= 3
      2199133.25     13774898.79      2199546.04     13774566.41
      2200012.47     13773370.84
#Sta/Elev= 30
    4264  752.41  4438.5  749.99  4574.4  742.99  4644.9  740.75  4694.5  740.78
  4729.7   743.2    4778  739.27  4791.1  742.41  4808.2  744.48  4827.4   742.7
  4838.4  739.95  4887.4  739.42    4978  739.68  4997.9  736.92  4998.4  736.42
  5004.4  736.92  5010.2   738.4  5025.6  737.73  5050.1  742.85  5063.8  744.29
  5074.6  743.42  5085.3  740.07  5096.3  738.69  5171.2  738.85  5188.7  741.47
  5218.5  740.56  5305.1   741.4    5670  746.64  5905.9  753.61  6077.3  760.39
#Mann= 8 ,-1 , 0
    4264     .12       0    4778    .035       0  4887.4      .1       0
  4997.9     .05       0  5004.4      .1       0  5096.3     .12       0
  5305.1    .035       0    5670     .07       0
Bank Sta=4997.9,5004.4
XS Rating Curve= 0 ,0
Exp/Cntr=0.3,0.1

Type RM Length L Ch R = 1 ,21785   ,369,369,369
BEGIN DESCRIPTION:
Dry Comal Creek Tributary 24 35.0
END DESCRIPTION:
XS GIS Cut Line= 3
      2199274.99       13774875.      2199878.43     13774727.25
      2200575.01     13773974.99
#Sta/Elev= 30
  4380.1  749.96  4555.1  746.68  4627.2  743.42  4699.9  741.84  4736.4   740.3
  4791.9  738.89  4812.5  738.59  4819.6  739.18    4851  738.36  4874.3  738.39
    4908   737.1  4915.5  738.58  4949.6  741.78  4977.2  739.87  4986.1  738.07
    4988  733.77  4988.5  733.27    4994  733.27  4994.5  733.77  5014.8  737.44
  5021.6  737.71  5226.9   738.3  5283.6  737.47  5332.9  738.07  5382.8  739.75
  5448.6   740.4  5543.1  742.62  5842.8  749.22  5970.7  751.82  6026.6  752.79
#Mann= 8 ,-1 , 0
  4380.1     .12       0    4851    .035       0    4988    .035       0
  4994.5    .035       0  5448.6     .07       0  5543.1    .035       0
  5842.8     .07       0  5970.7    .035       0
Bank Sta=4988,4994.5
XS Rating Curve= 0 ,0
Exp/Cntr=0.3,0.1

Type RM Length L Ch R = 1 ,21416   ,465,465,465
BEGIN DESCRIPTION:
Dry Comal Creek Tributary 24 34.0
END DESCRIPTION:
XS GIS Cut Line= 3
      2198974.99       13775025.        2200175.       13774925.
      2200474.98     13774225.04
#Sta/Elev= 30
  3795.6  755.55  3825.7  755.83    3916  752.73  4358.5  744.53  4407.7  742.24
  4460.4   742.3    4478  740.84  4738.9  735.55  4879.4  735.57  4942.1  739.67
  4969.7     738    4994  732.64  4994.5  732.14  5000.5  732.64  5008.8  732.89
  5014.3     735  5090.4  736.44  5213.7  736.39  5275.7  737.45  5366.1  739.62
  5371.5  738.91  5389.6  740.32  5395.1  739.06  5402.3  740.19    5435   741.6
  5498.9  741.98  5564.9  743.24  5670.6  746.48  5683.9  746.82  5761.3  748.73
#Mann= 9 ,-1 , 0
  3795.6     .12       0  4358.5    .035       0    4994    .035       0
  5000.5    .035       0  5275.7     .07       0  5498.9     .12       0
  5564.9     .07       0  5670.6    .035       0  5683.9     .07       0
Bank Sta=4994,5000.5
XS Rating Curve= 0 ,0
Exp/Cntr=0.3,0.1

Type RM Length L Ch R = 1 ,20951   ,443,443,443
BEGIN DESCRIPTION:
Dry Comal Creek Tributary 24 33.0
END DESCRIPTION:
XS GIS Cut Line= 3
        2199575.       13776075.        2200375.       13775275.
        2200675.       13774275.
#Sta/Elev= 30
  3873.4  749.57  4113.8  741.64  4297.7  737.89  4495.7  737.03  4919.9  733.13
  4962.3  733.77    4972  732.49  4972.5  731.99  4980.5  731.99    4981  732.49
  4990.6  734.02  5026.5  733.32  5054.4  734.08  5119.6  733.83  5130.9  734.81
  5140.1     737  5158.8  738.09  5182.3  734.54  5191.8  734.36  5203.1  735.21
  5263.2  735.05  5377.5   736.1  5478.3  737.36  5666.6  740.19  5752.1  742.01
  5777.4  743.17  5818.2   743.5  5871.3  745.94  5894.8  745.61  6048.8  748.91
#Mann= 7 ,-1 , 0
  3873.4    .035       0    4972    .035       0    4981    .035       0
  5140.1     .07       0  5377.5    .035       0  5478.3     .07       0
  5666.6     .12       0
Bank Sta=4972,4981
XS Rating Curve= 0 ,0
Exp/Cntr=0.3,0.1

Type RM Length L Ch R = 1 ,20508   ,622,622,622
BEGIN DESCRIPTION:
Dry Comal Creek Tributary 24 32.0
END DESCRIPTION:
XS GIS Cut Line= 3
      2199924.99     13776175.01        2200625.       13775625.
      2201825.04     13775224.99
#Sta/Elev= 30
  4114.3  751.12  4164.9  747.83  4171.3  742.38  4185.7  743.41  4192.1  739.17
  4206.5  737.15  4249.9  735.41  4912.3  731.15  4962.1  732.94  4997.2  731.06
  5120.5  731.96    5166  729.33  5242.5  729.28    5243  728.78  5251.5  729.28
  5268.1  729.38  5278.6  732.59    5294  733.38  5310.2  732.08  5341.9  735.25
  5394.6  736.01  5405.1  733.26  5426.2  732.26  5468.3  734.95  5608.6  735.96
  5666.6  736.13  5707.6  736.22  5818.4  736.92  5953.2  737.25  6269.5  749.73
#Mann= 10 ,-1 , 0
  4114.3    .035       0  4997.2     .12       0    5166      .1       0
  5242.5     .05       0  5251.5      .1       0    5294     .07       0
  5608.6      .1       0  5666.6    .035       0  5707.6      .1       0
  5818.4    .035       0
Bank Sta=5242.5,5251.5
XS Rating Curve= 0 ,0
Exp/Cntr=0.3,0.1

Type RM Length L Ch R = 1 ,19886   ,867,867,867
BEGIN DESCRIPTION:
Dry Comal Creek Tributary 24 31.0
END DESCRIPTION:
XS GIS Cut Line= 3
      2200050.01     13776903.91      2200923.88     13776094.37
      2201974.98     13775325.02
#Sta/Elev= 30
  3943.7  762.21  4116.1  747.51  4217.1  742.57  4342.9  734.36  4371.2  737.07
  4392.2   744.8  4399.6  744.74  4441.5  732.82  4524.8  731.95  4662.9  731.33
  4853.8  730.26  4979.6  730.12  4981.4  726.75  4981.9  726.25  4991.7  726.75
  5007.9  730.39  5058.8  729.95  5333.4  729.98  5343.1  729.69    5364   738.3
  5399.5  739.01  5458.2   735.7  5464.4  731.02  5485.2  729.68  5644.2  729.47
  5671.3  734.02  5706.8  734.49  5757.8  733.13  5972.4  735.47  6437.5  753.36
#Mann= 11 ,-1 , 0
  3943.7    .035       0  4217.1     .07       0  4524.8      .1       0
  4662.9    .035       0  4853.8      .1       0  4981.4     .05       0
  4991.7      .1       0  5058.8     .12       0  5333.4     .07       0
  5706.8    .063       0  5757.8    .035       0
Bank Sta=4981.4,4991.7
XS Rating Curve= 0 ,0
Exp/Cntr=0.3,0.1

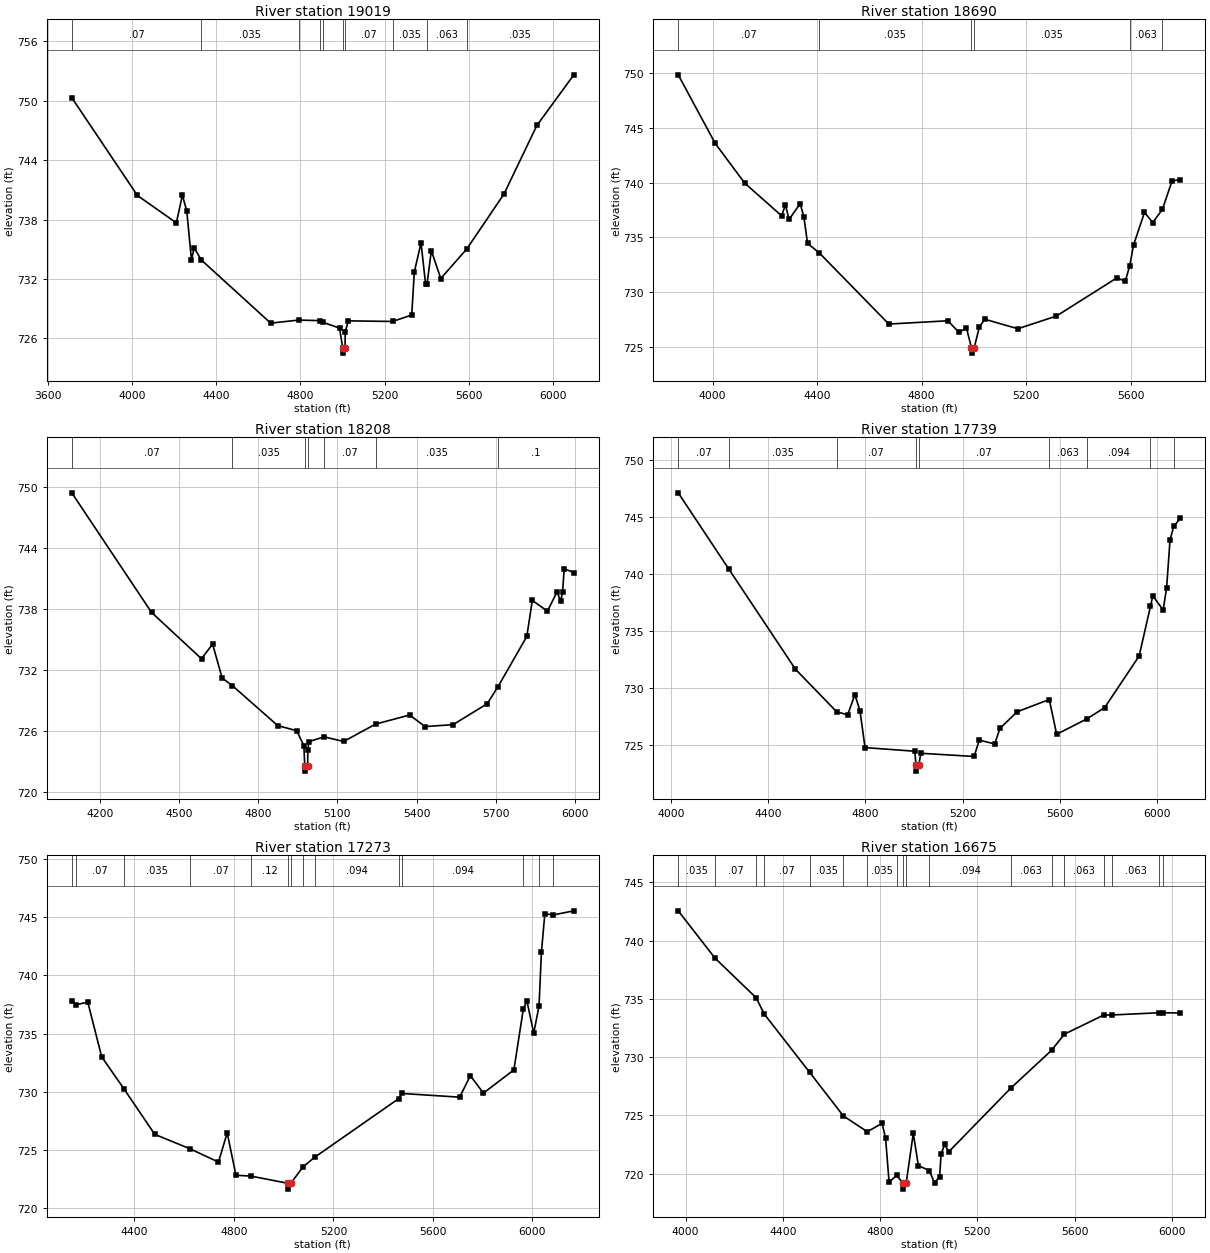
Type RM Length L Ch R = 1 ,19019   ,329,329,329
BEGIN DESCRIPTION:
Dry Comal Creek Tributary 24 30.0
END DESCRIPTION:
XS GIS Cut Line= 3
      2200602.17     13777311.41      2201465.37     13776276.65
      2201974.98     13775375.04
#Sta/Elev= 30
  3714.9  750.31  4026.5  740.43  4211.3  737.66    4240  740.46  4260.8  738.85
  4282.9  733.95  4296.2  735.13  4329.4  733.92  4659.1  727.53  4792.5  727.84
  4894.9  727.78  4907.4  727.61  4985.8  727.03  5001.2     725  5001.7   724.5
  5011.9     725  5013.1  726.64  5027.4  727.76  5237.9   727.7  5328.5  728.35
  5340.9  732.69  5372.7  735.64  5394.4  731.48  5401.3   731.5  5421.7  734.85
  5466.4  732.04  5590.5  735.04  5766.8  740.59  5922.7  747.51  6098.1  752.62
#Mann= 10 ,-1 , 0
  3714.9     .07       0  4329.4    .035       0  4792.5     .07       0
  4894.9    .035       0  4907.4     .07       0  5001.2     .05       0
  5011.9     .07       0  5237.9    .035       0  5401.3    .063       0
  5590.5    .035       0
Bank Sta=5001.2,5011.9
XS Rating Curve= 0 ,0
Exp/Cntr=0.3,0.1

Type RM Length L Ch R = 1 ,18690   ,482,482,482
BEGIN DESCRIPTION:
Dry Comal Creek Tributary 24 29.0
END DESCRIPTION:
XS GIS Cut Line= 3
      2200824.99     13777375.01        2201625.       13776575.
      2202375.04     13776324.99
#Sta/Elev= 30
  3868.3  749.87  4009.7   743.6  4122.9  739.96  4264.3  736.97  4278.4  737.98
  4292.6  736.64    4335  738.08  4349.2  736.89  4363.3  734.45  4407.4   733.6
  4674.4  727.07  4900.7  727.37  4943.1   726.3  4971.4  726.72  4990.8  724.91
  4991.3  724.41  5001.5  724.91  5020.8   726.8  5041.9  727.51  5168.3  726.64
  5315.9   727.8  5547.8   731.3  5579.4  730.98  5596.9   732.4  5611.1  734.29
  5653.2  737.28  5684.8  736.36  5721.6  737.55  5758.6  740.16  5790.3  740.29
#Mann= 6 ,-1 , 0
  3868.3     .07       0  4407.4    .035       0  4990.8    .035       0
  5001.5    .035       0  5596.9    .063       0  5721.6      .1       0
Bank Sta=4990.8,5001.5
XS Rating Curve= 0 ,0
Exp/Cntr=0.3,0.1

Type RM Length L Ch R = 1 ,18208   ,469,469,469
BEGIN DESCRIPTION:
Dry Comal Creek Tributary 24 28.0
END DESCRIPTION:
XS GIS Cut Line= 3
      2200974.98     13777525.01        2201725.       13777025.
      2202524.99       13776425.
#Sta/Elev= 30
  4094.1  749.47  4396.1  737.69  4585.4  733.12  4627.4  734.57  4663.5  731.22
  4702.4  730.47  4873.8  726.54  4945.9  726.03    4973  724.56  4976.5  722.55
    4977  722.05  4987.5  722.55    4988  724.16  4992.5  724.96  5049.8  725.43
  5123.6  724.97  5244.4  726.68  5373.6  727.58    5432  726.44  5538.2  726.63
  5667.4  728.69    5707  730.31  5817.4  735.32  5838.2  738.87  5895.5  737.81
    5932  739.72  5945.5  738.77  5952.8  739.73    5959  741.98  5995.5  741.62
#Mann= 7 ,-1 , 0
  4094.1     .07       0  4702.4    .035       0  4976.5    .035       0
  4987.5    .035       0  5049.8     .07       0  5244.4    .035       0
    5707      .1       0
Bank Sta=4976.5,4987.5
XS Rating Curve= 0 ,0
Exp/Cntr=0.3,0.1

Type RM Length L Ch R = 1 ,17739   ,466,466,466
BEGIN DESCRIPTION:
Dry Comal Creek Tributary 24 27.0
END DESCRIPTION:
XS GIS Cut Line= 3
      2201225.01     13777924.99        2202025.       13777375.
        2202825.       13776625.
#Sta/Elev= 30
  4029.2  747.14  4236.6  740.46  4511.6  731.63  4681.1  727.89  4726.7  727.61
  4756.5  729.38  4777.4  727.99  4798.4  724.73  5003.4  724.41  5008.4  723.16
  5008.9  722.66  5019.4  723.16  5028.1  724.23  5247.4  723.95  5268.9  725.39
  5332.4  725.05  5353.9  726.42  5424.7  727.88    5557  728.96  5587.4   725.9
  5712.3  727.26  5785.2  728.25  5926.9  732.78  5973.8  737.16  5983.5  738.08
    6026  736.83  6040.2   738.8  6054.3     743  6069.5  744.19  6096.6   744.9
#Mann= 9 ,-1 , 0
  4029.2     .07       0  4236.6    .035       0  4681.1     .07       0
  5008.4     .05       0  5019.4     .07       0    5557    .063       0
  5712.3    .094       0  5973.8    .063       0  6069.5    .094       0
Bank Sta=5008.4,5019.4
XS Rating Curve= 0 ,0
Exp/Cntr=0.3,0.1

Type RM Length L Ch R = 1 ,17273   ,598,598,598
BEGIN DESCRIPTION:
Dry Comal Creek Tributary 24 26.0
END DESCRIPTION:
XS GIS Cut Line= 3
      2201724.99     13778175.01        2202375.       13777625.
      2202975.01     13776624.98
#Sta/Elev= 30
  4148.5  737.81    4165  737.46  4212.8   737.7  4268.8     733    4360   730.2
    4482  726.35  4623.8  725.11    4738  723.97  4773.1  726.48  4808.3  722.84
    4868  722.77  5017.5  722.15    5018  721.65  5029.1  722.15  5076.4  723.53
  5124.3  724.38  5462.6  729.42  5474.2  729.86  5707.5  729.54  5750.2  731.39
  5802.7  729.89  5925.2  731.88  5963.3  737.12  5977.6   737.8  6004.9  735.03
  6026.3  737.36  6035.9  741.99  6049.6  745.27  6084.1  745.18  6166.2  745.53
#Mann= 14 ,-1 , 0
  4148.5    .035       0    4165     .07       0    4360    .035       0
  4623.8     .07       0    4868     .12       0  5017.5     .05       0
  5029.1     .12       0  5076.4     .07       0  5124.3    .094       0
  5462.6    .063       0  5474.2    .094       0  5963.3    .063       0
  6026.3    .094       0  6084.1      .1       0
Bank Sta=5017.5,5029.1
XS Rating Curve= 0 ,0
Exp/Cntr=0.3,0.1

Type RM Length L Ch R = 1 ,16675   ,410,410,410
BEGIN DESCRIPTION:
Dry Comal Creek Tributary 24 25.0
END DESCRIPTION:
XS GIS Cut Line= 3
      2201787.01     13778683.89      2202585.87     13778061.95
       2203142.4     13777168.29
#Sta/Elev= 30
  3969.8  742.55    4121  738.49  4290.1  735.09    4324  733.68  4510.1  728.69
  4648.7  724.95  4747.3  723.59  4808.2   724.3  4822.7  723.03  4837.1  719.25
  4867.7  719.83  4895.5  719.16    4896  718.66  4907.2  719.16  4936.7  723.45
  4957.5  720.68  5002.6  720.25  5023.9   719.2  5045.1  719.73    5051  721.69
  5066.3  722.51  5081.7  721.85  5338.2  727.34  5505.6  730.58    5558  731.96
  5719.5   733.6  5755.1  733.61  5947.1   733.8  5962.5   733.8    6035  733.78
#Mann= 18 ,-1 , 0
  3969.8    .035       0    4121     .07       0  4290.1    .035       0
    4324     .07       0  4510.1    .035       0  4648.7     .07       0
  4747.3    .035       0  4867.7     .07       0  4895.5    .035       0
  4907.2     .07       0  5002.6    .094       0  5338.2    .063       0
  5505.6    .094       0    5558    .063       0  5719.5      .1       0
  5755.1    .063       0  5947.1      .1       0  5962.5    .094       0
Bank Sta=4895.5,4907.2
XS Rating Curve= 0 ,0
Exp/Cntr=0.3,0.1

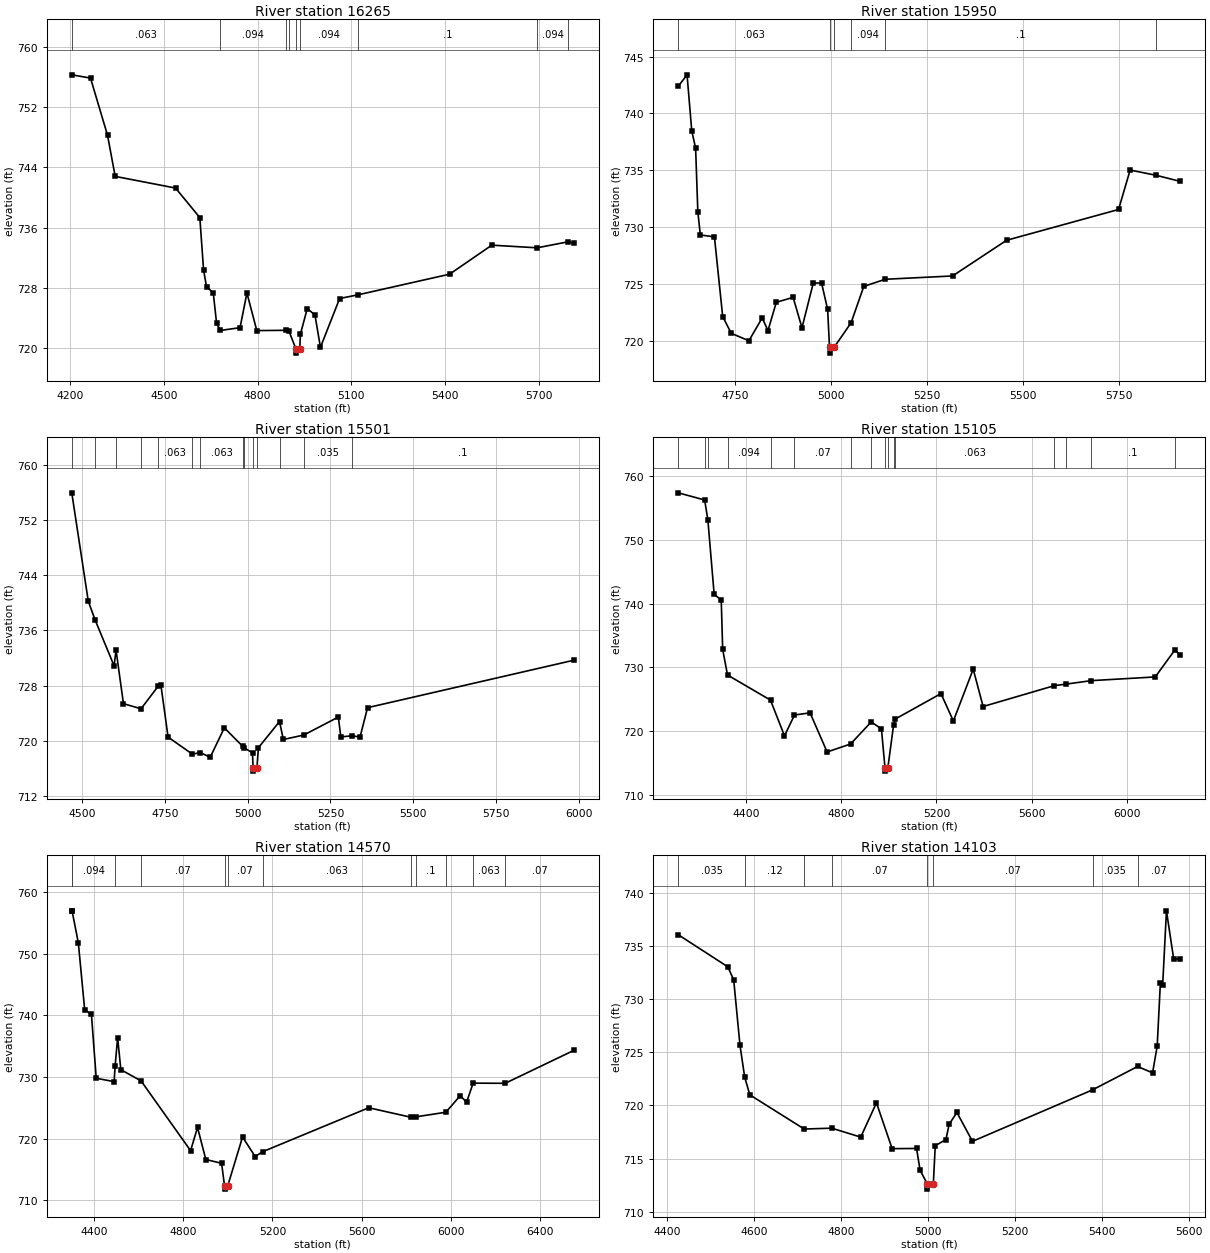
Type RM Length L Ch R = 1 ,16265   ,315,315,315
BEGIN DESCRIPTION:
Dry Comal Creek Tributary 24 24.0
END DESCRIPTION:
XS GIS Cut Line= 3
      2202628.77     13778957.25       2202982.6     13778045.87
      2203046.87     13777419.31
#Sta/Elev= 30
  4205.3  756.29  4265.3  755.86  4319.8  748.26  4344.3  742.81  4537.6  741.26
  4615.3  737.34  4627.3  730.39  4636.8  728.15  4658.3  727.37    4669  723.29
  4681.2  722.36  4744.1  722.73  4766.1  727.34  4797.7  722.34    4890  722.38
  4900.3  722.31  4923.5  719.85    4924  719.35  4935.3  719.85  4937.2  721.84
  4959.3  725.27  4983.9  724.41  5001.5  720.12  5062.9   726.6    5122  727.09
    5415  729.83  5550.1  733.68  5695.2  733.33  5793.8  734.12  5812.8  733.93
#Mann= 9 ,-1 , 0
  4205.3    .063       0  4681.2    .094       0    4890    .035       0
  4900.3    .094       0  4923.5     .05       0  4935.3    .094       0
    5122      .1       0  5695.2    .094       0  5793.8    .063       0
Bank Sta=4923.5,4935.3
XS Rating Curve= 0 ,0
Exp/Cntr=0.3,0.1

Type RM Length L Ch R = 1 ,15950   ,449,449,449
BEGIN DESCRIPTION:
Dry Comal Creek Tributary 24 23.0
END DESCRIPTION:
XS GIS Cut Line= 3
      2202975.02     13778724.97        2203175.       13778375.
        2203075.     13777475.01
#Sta/Elev= 30
  4601.5  742.38  4624.5  743.39  4636.7  738.47  4646.8  736.93  4652.6  731.33
  4659.1   729.3  4695.8  729.13  4717.4  722.12  4739.7  720.64  4785.7  719.99
  4820.3     722  4835.4  720.88    4857  723.37  4900.9  723.81    4924  721.13
  4953.5  725.07  4975.1  725.07  4990.9  722.74  4995.8   719.4  4996.3   718.9
  5007.6   719.4    5052  721.57  5085.1  724.77    5141   725.4  5316.5  725.69
  5457.3  728.83  5749.1  731.54  5779.3  735.01    5847  734.55  5910.1  734.01
#Mann= 6 ,-1 , 0
  4601.5    .063       0  4995.8     .05       0  5007.6    .063       0
    5052    .094       0    5141      .1       0    5847    .094       0
Bank Sta=4995.8,5007.6
XS Rating Curve= 0 ,0
Exp/Cntr=0.3,0.1

Type RM Length L Ch R = 1 ,15501   ,396,396,396
BEGIN DESCRIPTION:
Dry Comal Creek Tributary 24 22.0
END DESCRIPTION:
XS GIS Cut Line= 3
        2203225.       13778925.        2203575.       13778525.
        2203175.     13777624.99
#Sta/Elev= 30
  4468.6  755.94  4518.4  740.24  4538.6  737.57  4596.3  730.87  4602.4  733.11
  4624.7  725.37  4677.8  724.63  4729.9  727.92  4737.7   728.1  4759.5  720.52
  4832.7  718.06  4857.3  718.27  4886.7  717.59  4929.4  721.87  4984.7  719.19
  4987.6  719.01  5014.5  718.25  5016.1  716.09  5016.6  715.59  5027.9  716.09
  5032.3  718.99  5096.1  722.78  5107.5  720.18  5169.3  720.82  5273.7  723.43
  5281.2  720.55  5314.4  720.71  5339.3  720.54  5361.9  724.79    5985  731.67
#Mann= 14 ,-1 , 0
  4468.6    .063       0  4538.6    .035       0  4602.4    .063       0
  4677.8    .094       0  4729.9    .063       0  4832.7     .07       0
  4857.3    .063       0  4984.7    .035       0  4987.6     .07       0
  5016.1     .05       0  5027.9     .07       0  5096.1    .063       0
  5169.3    .035       0  5314.4      .1       0
Bank Sta=5016.1,5027.9
XS Rating Curve= 0 ,0
Exp/Cntr=0.3,0.1

Type RM Length L Ch R = 1 ,15105   ,535,535,535
BEGIN DESCRIPTION:
X18999
END DESCRIPTION:
XS GIS Cut Line= 4
      2203475.87     13779316.45      2203931.55     13778651.69
      2204065.58     13778201.35      2203830.27     13777399.16
#Sta/Elev= 30
    4114  757.32  4225.1   756.2  4238.6  753.08  4265.1  741.44  4294.9  740.54
  4300.9  732.82  4321.3  728.81  4502.1  724.88  4560.9  719.29    4603  722.55
  4668.5  722.89  4740.2  716.77  4838.7  718.01  4925.8  721.47  4968.7  720.37
  4983.7  714.27  4984.2  713.77  4995.6  714.27  5019.9  721.01  5027.6  721.94
  5219.1   725.9  5271.2  721.62  5354.7  729.72  5396.4  723.88  5695.3  727.14
  5745.9  727.39  5851.2  727.93  6120.4  728.51  6202.7  732.72  6225.8   731.9
#Mann= 16 ,-1 , 0
    4114    .063       0  4225.1    .094       0  4238.6    .063       0
  4321.3    .094       0  4502.1    .063       0    4603     .07       0
  4838.7      .1       0  4925.8     .07       0  4983.7     .05       0
  4995.6     .07       0  5019.9      .1       0  5027.6    .063       0
  5695.3      .1       0  5745.9    .094       0  5851.2      .1       0
  6202.7    .063       0
Bank Sta=4983.7,4995.6
XS Rating Curve= 0 ,0
Exp/Cntr=0.3,0.1

Type RM Length L Ch R = 1 ,14570   ,467,467,467
BEGIN DESCRIPTION:
Dry Comal Creek Tributary 24 21.0
END DESCRIPTION:
XS GIS Cut Line= 3
      2203574.96     13779325.02        2204175.       13778975.
        2205275.       13777875.
#Sta/Elev= 30
  4300.5  756.99  4301.8  756.99  4329.9   751.8  4358.4  740.92  4388.6  740.18
  4410.1  729.79  4490.3  729.24  4494.9  731.81    4506  736.37  4520.5  731.18
  4610.9  729.37  4833.1  718.03  4864.1  721.81  4901.3  716.59    4972  715.98
  4985.3  712.28  4985.8  711.78  4999.3  712.28  5065.9  720.25  5122.4  717.08
  5155.6  717.85  5631.6     725  5822.5  723.44  5842.1  723.52  5977.3  724.27
  6041.7  726.97    6070  725.89  6099.4     729    6243  728.97  6550.8  734.32
#Mann= 12 ,-1 , 0
  4300.5    .063       0  4301.8    .094       0  4494.9    .063       0
  4610.9     .07       0  4985.3     .05       0  4999.3     .07       0
  5155.6    .063       0  5822.5    .094       0  5842.1      .1       0
  5977.3    .094       0  6099.4    .063       0    6243     .07       0
Bank Sta=4985.3,4999.3
XS Rating Curve= 0 ,0
Exp/Cntr=0.3,0.1

Type RM Length L Ch R = 1 ,14103   ,423,423,423
BEGIN DESCRIPTION:
Dry Comal Creek Tributary 24 20.0
END DESCRIPTION:
XS GIS Cut Line= 3
      2204175.01     13779674.99        2204525.       13779225.
        2204725.       13778675.
#Sta/Elev= 30
  4425.6  736.08  4539.6  733.06  4553.2  731.83  4567.7  725.66  4578.5  722.67
  4590.3     721  4715.5  717.78  4778.8  717.86  4845.5  717.02  4881.7  720.25
  4917.8  715.93    4974  715.95  4982.1   713.9  4998.6  712.62  4999.1  712.12
  5012.6  712.62    5017  716.21  5041.6  716.79  5048.9  718.22  5066.8  719.34
  5102.7  716.62    5379  721.47  5482.6  723.67  5517.1  723.07  5527.7  725.59
    5535  731.53  5540.3  731.33    5549  738.33  5565.6  733.81  5580.9   733.8
#Mann= 8 ,-1 , 0
  4425.6    .035       0  4578.5     .12       0  4715.5      .1       0
  4778.8     .07       0  4998.6     .05       0  5012.6     .07       0
    5379    .035       0  5482.6     .07       0
Bank Sta=4998.6,5012.6
XS Rating Curve= 0 ,0
Exp/Cntr=0.3,0.1