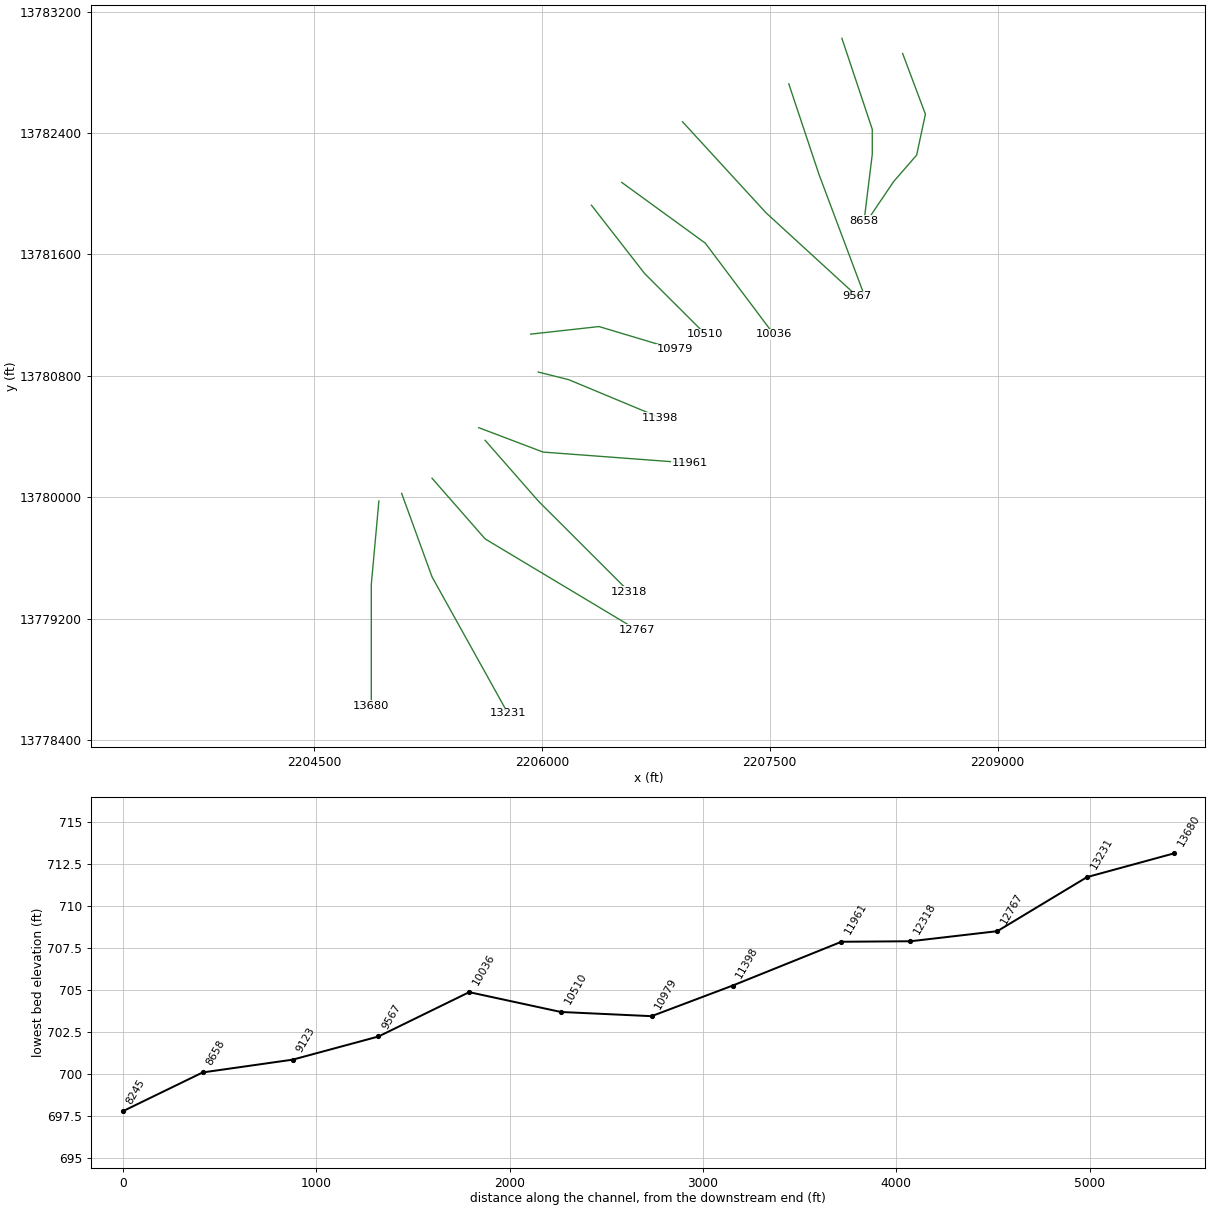
HEC-RAS study Dry Comal Creek Tributary 24.prj: Dry Comal Creek Tributary 24 Base Level Engineering

--- Dry Comal Creek Tributary 24.g01 (geometry) --- (continued)

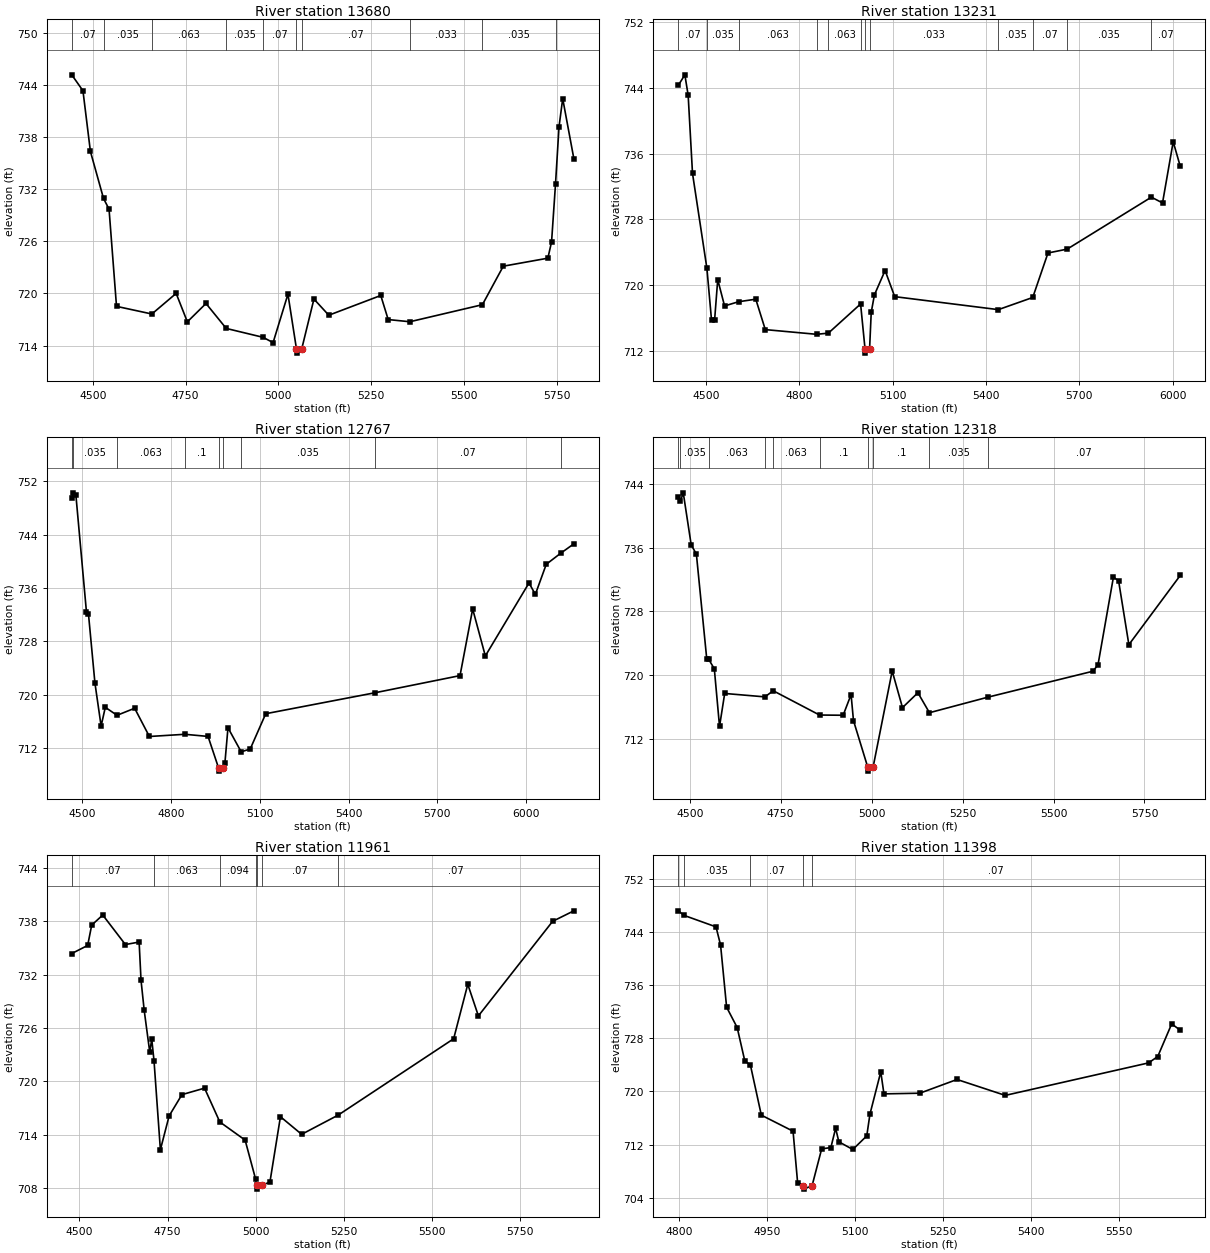
Type RM Length L Ch R = 1 ,13680   ,449,449,449
BEGIN DESCRIPTION:
Dry Comal Creek Tributary 24 19.0
END DESCRIPTION:
XS GIS Cut Line= 3
        2204925.     13779974.97        2204875.       13779425.
        2204875.     13778625.04
#Sta/Elev= 30
  4443.5  745.15  4473.6  743.32  4493.7  736.34    4529  730.93  4543.9   729.7
    4564  718.52  4659.2  717.64  4724.6  720.01  4754.8  716.74    4805  718.85
  4859.5  715.98  4958.6  714.96  4985.7  714.35  5025.7  719.92  5048.6  713.64
  5049.1  713.14  5062.9  713.64  5095.7  719.36  5135.7   717.5  5275.7  719.77
  5295.7     717  5354.1  716.75  5549.4  718.71  5605.7  723.14  5725.7  724.06
  5735.7  725.94  5746.3  732.58  5755.7  739.15  5765.7  742.41  5795.7  735.51
#Mann= 10 ,-1 , 0
  4443.5     .07       0    4529    .035       0  4659.2    .063       0
  4859.5    .035       0  4958.6     .07       0  5048.6     .05       0
  5062.9     .07       0  5354.1    .033       0  5549.4    .035       0
  5746.3    .094       0
Bank Sta=5048.6,5062.9
XS Rating Curve= 0 ,0
Exp/Cntr=0.3,0.1

Type RM Length L Ch R = 1 ,13231   ,464,464,464
BEGIN DESCRIPTION:
Dry Comal Creek Tributary 24 18.0
END DESCRIPTION:
XS GIS Cut Line= 3
        2205075.       13780025.        2205275.       13779475.
        2205775.       13778575.
#Sta/Elev= 30
  4410.2  744.29  4431.5  745.58  4442.1   743.1  4456.1  733.59  4502.4  722.04
  4517.3  715.73  4527.2  715.77  4537.2  720.67  4559.2  717.47  4604.1  717.98
  4659.6  718.29  4690.2  714.59    4855  714.02    4893  714.16  4996.7  717.71
    5011  712.23  5011.5  711.73  5025.6  712.23  5030.9  716.69  5041.2  718.82
  5075.5  721.78  5106.4   718.6  5439.7  717.02  5550.4   718.5  5599.4  723.91
  5661.1  724.38  5931.9   730.7  5967.8     730  6002.1  737.44    6025  734.43
#Mann= 12 ,-1 , 0
  4410.2     .07       0  4502.4    .035       0  4604.1    .063       0
    4855      .1       0    4893    .063       0  4996.7    .033       0
    5011    .033       0  5025.6    .033       0  5439.7    .035       0
  5550.4     .07       0  5661.1    .035       0  5931.9     .07       0
Bank Sta=5011,5025.6
XS Rating Curve= 0 ,0
Exp/Cntr=0.3,0.1

Type RM Length L Ch R = 1 ,12767   ,449,449,449
BEGIN DESCRIPTION:
Dry Comal Creek Tributary 24 17.0
END DESCRIPTION:
XS GIS Cut Line= 3
      2205275.01     13780124.99        2205625.       13779725.
      2206625.01     13779124.99
#Sta/Elev= 30
  4464.1  749.55  4469.9  750.29  4477.9  750.02  4513.9  732.33  4520.6  732.09
  4542.4  721.74  4563.3  715.29  4577.5  718.09  4617.2  716.89  4676.7  717.95
  4726.5  713.71  4846.4  714.04  4924.9  713.72  4960.3  709.01  4960.8  708.51
  4974.9  709.01  4981.8  709.68  4992.3  715.02  5036.9  711.41  5067.5  711.83
    5120  717.13    5491  720.29  5776.9  722.85  5819.7  732.85  5862.5   725.8
  6010.2  736.76  6031.6  735.04  6068.5  739.56  6116.7   741.2  6161.8  742.63
#Mann= 9 ,-1 , 0
  4464.1     .07       0  4469.9    .035       0  4617.2    .063       0
  4846.4      .1       0  4960.3     .05       0  4974.9      .1       0
  5036.9    .035       0    5491     .07       0  6116.7    .045       0
Bank Sta=4960.3,4974.9
XS Rating Curve= 0 ,0
Exp/Cntr=0.3,0.1

Type RM Length L Ch R = 1 ,12318   ,357,357,357
BEGIN DESCRIPTION:
Dry Comal Creek Tributary 24 16.0
END DESCRIPTION:
XS GIS Cut Line= 3
      2205624.97     13780375.04        2205975.       13779975.
      2206575.01     13779374.99
#Sta/Elev= 30
  4468.4  742.34  4474.5  741.84  4482.2  742.88    4504  736.35  4518.3  735.17
  4546.7  722.04  4551.8  721.99  4567.6  720.76  4581.9  713.53  4596.1  717.67
  4706.7  717.24  4729.4  718.01  4856.8  714.96  4921.7  714.93  4943.5  717.53
  4950.1  714.26  4989.3  708.41  4989.8  707.91    5004  708.41  5056.5  720.49
  5084.8  715.89  5127.2  717.76  5158.9  715.25  5320.1  717.21  5608.1  720.46
  5622.2  721.26  5664.6  732.28  5678.8  731.84  5707.1   723.8  5848.5  732.51
#Mann= 10 ,-1 , 0
  4468.4     .07       0  4474.5    .035       0  4551.8    .063       0
  4706.7    .094       0  4729.4    .063       0  4856.8      .1       0
  4989.3     .05       0    5004      .1       0  5158.9    .035       0
  5320.1     .07       0
Bank Sta=4989.3,5004
XS Rating Curve= 0 ,0
Exp/Cntr=0.3,0.1

Type RM Length L Ch R = 1 ,11961   ,563,563,563
BEGIN DESCRIPTION:
Dry Comal Creek Tributary 24 15.0
END DESCRIPTION:
XS GIS Cut Line= 3
      2205582.85     13780458.42      2206006.35      13780297.6
      2206975.03       13780225.
#Sta/Elev= 30
  4478.1  734.36  4523.2  735.27  4534.6  737.55    4566  738.69  4630.2  735.37
  4669.2  735.65  4674.6  731.34  4683.6  727.97  4699.3  723.29    4705  724.73
  4711.4  722.32  4729.5  712.31  4754.3  716.11  4790.6   718.5  4854.8  719.23
  4898.1  715.43  4969.9  713.39  4999.4  709.04  5002.6  708.38  5003.1  707.88
  5017.3  708.38  5040.1  708.63  5070.1  716.02  5130.3  714.04  5233.9   716.2
  5561.5  724.78  5601.6   730.9  5631.7  727.35  5842.3  737.98  5902.5  739.16
#Mann= 7 ,-1 , 0
  4478.1     .07       0  4711.4    .063       0  4898.1    .094       0
  4999.4     .07       0  5002.6     .05       0  5017.3     .07       0
  5233.9     .07       0
Bank Sta=5002.6,5017.3
XS Rating Curve= 0 ,0
Exp/Cntr=0.3,0.1

Type RM Length L Ch R = 1 ,11398   ,419,419,419
BEGIN DESCRIPTION:
Dry Comal Creek Tributary 24 14.0
END DESCRIPTION:
XS GIS Cut Line= 3
        2205975.       13780825.        2206175.       13780775.
      2206775.04     13780524.98
#Sta/Elev= 30
  4798.5  747.25  4808.8  746.55  4862.9  744.83  4870.7  742.09    4881  732.71
    4899  729.65  4911.9  724.65  4921.7  723.94  4940.2  716.43  4994.3  714.01
  5002.1  706.22  5011.8  705.77  5012.3  705.27  5026.7  705.77  5043.1  711.34
  5058.8  711.54  5066.9  714.46  5072.4  712.41  5096.2  711.25    5120   713.3
  5125.4  716.57  5143.9  722.96  5149.3  719.64  5210.5  719.74  5273.9  721.81
  5356.2  719.41  5600.5  724.31  5616.2  725.27    5640   730.2  5654.7  729.23
#Mann= 5 ,-1 , 0
  4798.5     .07       0  4808.8    .035       0  4921.7     .07       0
  5011.8     .05       0  5026.7     .07       0
Bank Sta=5011.8,5026.7
XS Rating Curve= 0 ,0
Exp/Cntr=0.3,0.1

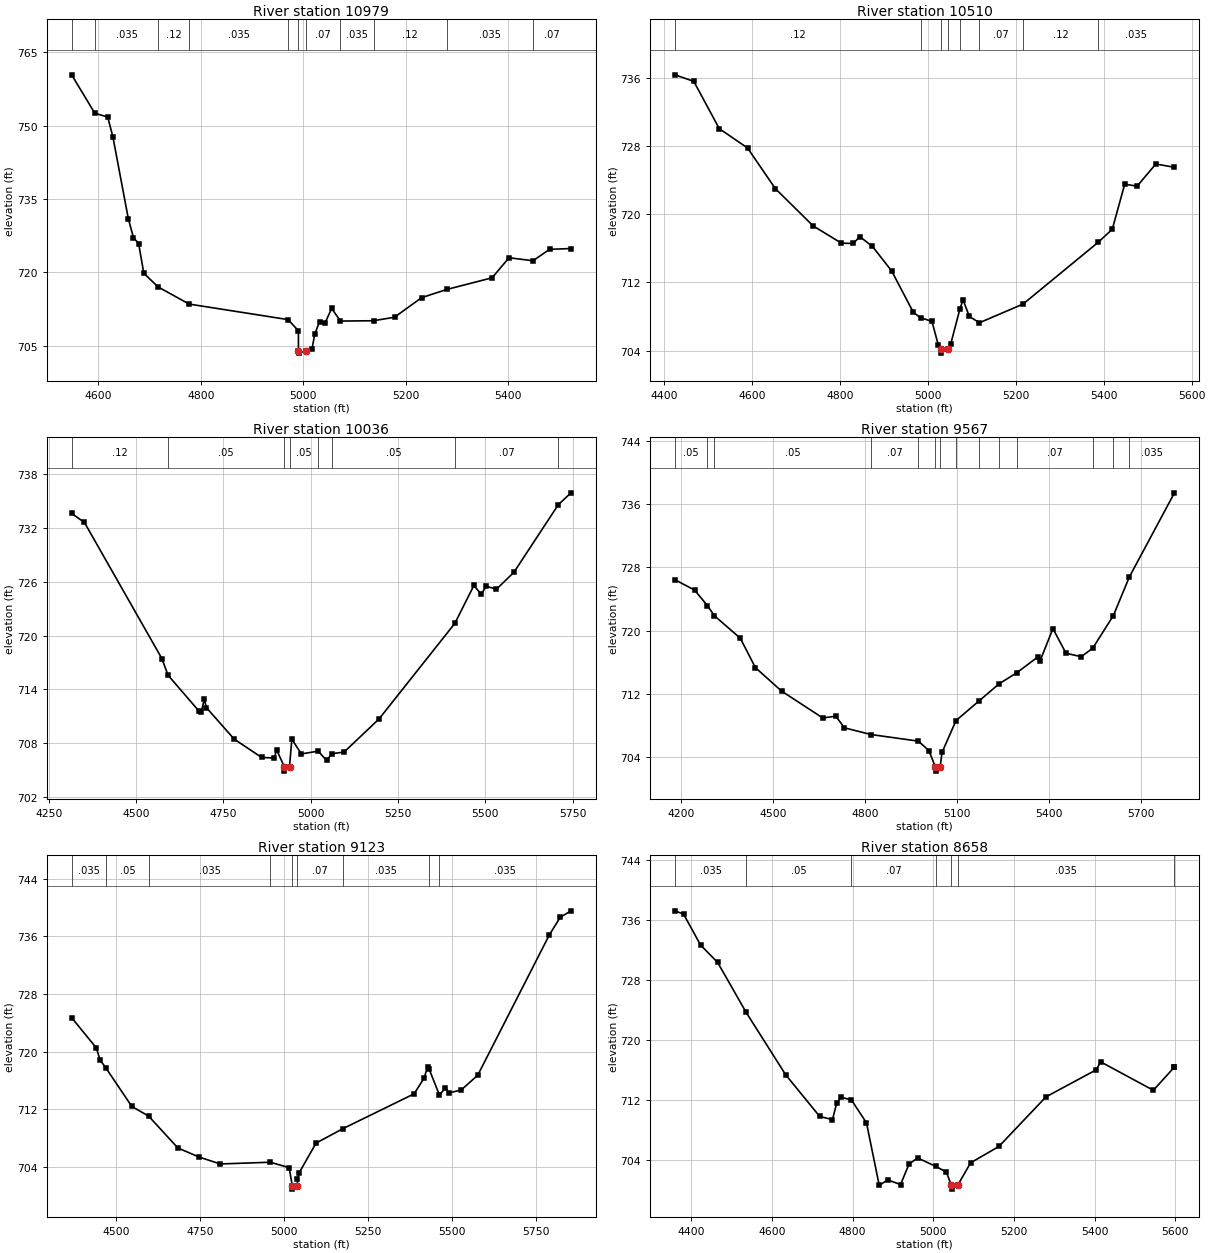
Type RM Length L Ch R = 1 ,10979   ,469,469,469
BEGIN DESCRIPTION:
Dry Comal Creek Tributary 24 13.0
END DESCRIPTION:
XS GIS Cut Line= 3
        2205925.       13781075.        2206375.       13781125.
      2206875.02     13780974.99
#Sta/Elev= 30
  4547.6  760.41  4592.9  752.54    4618  751.78  4628.1  747.74  4658.3  730.95
  4668.3  727.09  4678.4  725.87  4688.5  719.78  4716.8  716.98  4776.9  713.49
  4970.1  710.31  4990.3  708.03  4990.4  703.95  4990.9  703.45  5005.3  703.95
  5016.9   704.3  5022.1  707.33  5031.7  709.92  5042.1  709.57  5055.2   712.6
  5072.4  710.01  5136.9  710.08  5177.9   710.8  5230.9  714.81  5279.9  716.48
  5368.4  718.87  5401.4  722.97  5448.2  722.36  5480.6  724.69  5522.4  724.86
#Mann= 11 ,-1 , 0
  4547.6     .07       0  4592.9    .035       0  4716.8     .12       0
  4776.9    .035       0  4970.1     .07       0  4990.4     .05       0
  5005.3     .07       0  5072.4    .035       0  5136.9     .12       0
  5279.9    .035       0  5448.2     .07       0
Bank Sta=4990.4,5005.3
XS Rating Curve= 0 ,0
Exp/Cntr=0.3,0.1

Type RM Length L Ch R = 1 ,10510   ,474,474,474
BEGIN DESCRIPTION:
Dry Comal Creek Tributary 24 12.0
END DESCRIPTION:
XS GIS Cut Line= 3
      2206324.99     13781925.01        2206675.       13781475.
      2207075.01     13781074.99
#Sta/Elev= 30
  4425.1  736.32  4467.6  735.55  4525.6  730.01  4589.8  727.75  4653.1  722.98
  4739.1  718.61  4803.4  716.59  4830.5  716.55    4845  717.36  4873.9  716.21
  4917.4  713.35  4967.1  708.47  4983.3  707.85  5009.3  707.42  5023.5  704.69
  5030.1   704.2  5030.6   703.7  5045.2   704.2  5051.8  704.73  5072.9  708.88
  5080.1  709.95  5094.2  708.01  5117.2  707.26  5216.5  709.45  5387.4  716.69
  5419.5  718.22  5447.7   723.5    5476  723.27  5518.5  725.87  5560.9  725.48
#Mann= 8 ,-1 , 0
  4425.1     .12       0  4983.3     .07       0  5030.1     .05       0
  5045.2     .07       0  5072.9     .12       0  5117.2     .07       0
  5216.5     .12       0  5387.4    .035       0
Bank Sta=5030.1,5045.2
XS Rating Curve= 0 ,0
Exp/Cntr=0.3,0.1

Type RM Length L Ch R = 1 ,10036   ,469,469,469
BEGIN DESCRIPTION:
Dry Comal Creek Tributary 24 11.0
END DESCRIPTION:
XS GIS Cut Line= 3
      2206525.02     13782074.98        2207075.       13781675.
      2207524.97     13781075.04
#Sta/Elev= 30
  4315.2  733.64  4351.9  732.63  4573.7  717.44  4591.2  715.59  4680.3  711.56
  4686.5  711.45    4695  712.91  4701.2  711.96  4780.8  708.45  4859.2  706.41
  4895.9  706.34  4902.1  707.28  4923.9  705.38  4924.4  704.88  4939.1  705.38
  4945.8  708.44  4973.2   706.8    5021  707.11  5045.2  706.08  5060.8  706.83
  5095.2     707  5195.2  710.69  5412.6  721.37  5467.1   725.6    5488  724.63
  5502.5  725.52  5531.7  725.18  5581.7  727.07    5709  734.62  5745.2  735.94
#Mann= 8 ,-1 , 0
  4315.2     .12       0  4591.2     .05       0  4923.9     .05       0
  4939.1     .05       0    5021     .07       0  5060.8     .05       0
  5412.6     .07       0    5709     .12       0
Bank Sta=4923.9,4939.1
XS Rating Curve= 0 ,0
Exp/Cntr=0.3,0.1

Type RM Length L Ch R = 1 ,9567    ,444,444,444
BEGIN DESCRIPTION:
Dry Comal Creek Tributary 24 10.0
END DESCRIPTION:
XS GIS Cut Line= 3
      2206924.98     13782475.02        2207475.       13781875.
        2208075.       13781325.
#Sta/Elev= 30
  4181.1  726.42  4244.9  725.11  4286.1  723.17  4309.3  721.87  4393.6  719.04
  4442.9  715.32    4528  712.36  4662.4  708.96  4704.9  709.18  4733.3  707.71
  4820.4  706.86  4974.3  706.03  5008.9  704.81  5029.7  702.74  5030.2  702.24
  5044.9  702.74  5051.5  704.63  5096.9  708.63  5173.1  711.15  5237.9  713.29
    5295  714.67  5362.9  716.65  5370.3  716.12  5412.8  720.25  5455.4  717.14
  5504.7   716.7  5542.3  717.76  5609.9   721.9  5661.8  726.77    5809  737.41
#Mann= 14 ,-1 , 0
  4181.1     .05       0  4286.1     .07       0  4309.3     .05       0
  4820.4     .07       0  4974.3    .035       0  5029.7    .035       0
  5044.9    .035       0  5096.9     .07       0  5173.1    .035       0
  5237.9     .05       0    5295     .07       0  5542.3    .035       0
  5609.9     .07       0  5661.8    .035       0
Bank Sta=5029.7,5044.9
XS Rating Curve= 0 ,0
Exp/Cntr=0.3,0.1

Type RM Length L Ch R = 1 ,9123    ,465,465,465
BEGIN DESCRIPTION:
Dry Comal Creek Tributary 24 9.0
END DESCRIPTION:
XS GIS Cut Line= 3
      2207625.01     13782724.98        2207825.       13782125.
      2208124.99     13781325.03
#Sta/Elev= 30
  4367.8  724.71  4441.6  720.49  4452.1  718.85    4470   717.7    4547  712.36
  4597.2  711.01    4684  706.59  4747.3  705.32  4810.5  704.36  4959.3   704.6
  5015.4  703.85  5024.6  701.36  5025.1  700.86  5039.9  701.36  5040.3  702.27
  5045.6  703.16  5095.5  707.26  5176.3  709.29  5387.4  714.11  5417.6  716.32
  5427.4  717.89  5432.1  717.57    5463  713.94  5480.8  714.97  5491.5  714.24
    5528  714.66    5577  716.71  5790.6  736.26  5822.6  738.67  5854.6  739.57
#Mann= 9 ,-1 , 0
  4367.8    .035       0    4470     .05       0  4597.2    .035       0
  4959.3     .07       0  5024.6     .05       0  5039.9     .07       0
  5176.3    .035       0  5432.1     .07       0    5463    .035       0
Bank Sta=5024.6,5039.9
XS Rating Curve= 0 ,0
Exp/Cntr=0.3,0.1

Type RM Length L Ch R = 1 ,8658    ,413,413,413
BEGIN DESCRIPTION:
Dry Comal Creek Tributary 24 8.0
END DESCRIPTION:
XS GIS Cut Line= 4
      2207975.01     13783024.98        2208175.       13782425.
        2208175.     13782260.66      2208121.31     13781823.12
#Sta/Elev= 30
    4360  737.21  4381.1  736.76  4423.2  732.64  4465.4  730.33  4535.8  723.69
    4634  715.35  4718.4  709.79    4750  709.37  4760.5  711.57  4771.1  712.35
  4796.9     712  4834.3  708.94  4865.9   700.6    4887  701.33  4918.7  700.71
  4939.7  703.43  4960.8  704.26  5006.7  703.12  5032.4  702.37  5044.7   700.6
  5045.2   700.1  5060.2   700.6  5092.4  703.61  5162.5  705.79  5279.1   712.4
  5404.3  716.03  5414.4  717.08  5545.3  713.28  5597.4  716.37  5597.6  716.37
#Mann= 7 ,-1 , 0
    4360    .035       0  4535.8     .05       0  4796.9     .07       0
  5006.7    .035       0  5044.7     .05       0  5060.2    .035       0
  5597.4     .07       0
Bank Sta=5044.7,5060.2
XS Rating Curve= 0 ,0
Exp/Cntr=0.3,0.1

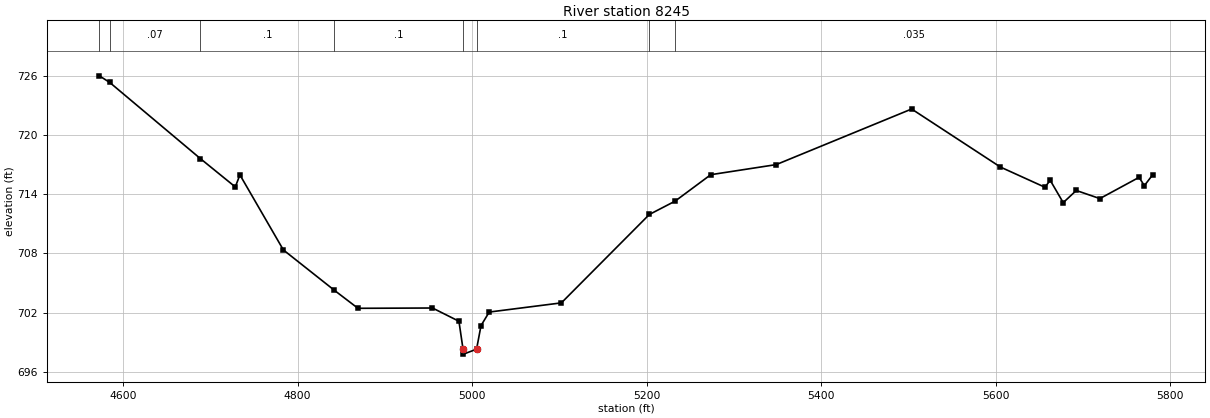
Type RM Length L Ch R = 1 ,8245    ,454,454,454
BEGIN DESCRIPTION:
Dry Comal Creek Tributary 24 7.0
END DESCRIPTION:
XS GIS Cut Line= 5
        2208375.       13782925.        2208525.       13782525.
      2208467.21     13782255.16      2208315.79     13782080.74
        2208163.     13781854.43
#Sta/Elev= 30
  4572.8  725.97  4584.7   725.3  4688.7  717.58  4728.6  714.72  4733.9  715.94
  4783.7  708.34  4842.2  704.25  4869.2  702.43  4954.6  702.46  4984.9  701.12
  4989.6  698.29  4990.1  697.79  5005.1  698.29  5010.2  700.68  5019.6  702.05
  5102.3  702.98  5203.1  711.93  5232.6  713.28  5273.5  715.96  5348.5  716.98
  5503.7  722.61  5605.5  716.73  5656.4  714.69  5662.5  715.39  5677.4  713.13
  5692.4  714.36  5719.4  713.54  5764.3  715.69  5770.4  714.85    5780  715.96
#Mann= 8 ,-1 , 0
  4572.8    .035       0  4584.7     .07       0  4688.7      .1       0
  4842.2      .1       0  4989.6     .05       0  5005.1      .1       0
  5203.1     .07       0  5232.6    .035       0
Bank Sta=4989.6,5005.1
XS Rating Curve= 0 ,0
Exp/Cntr=0.3,0.1