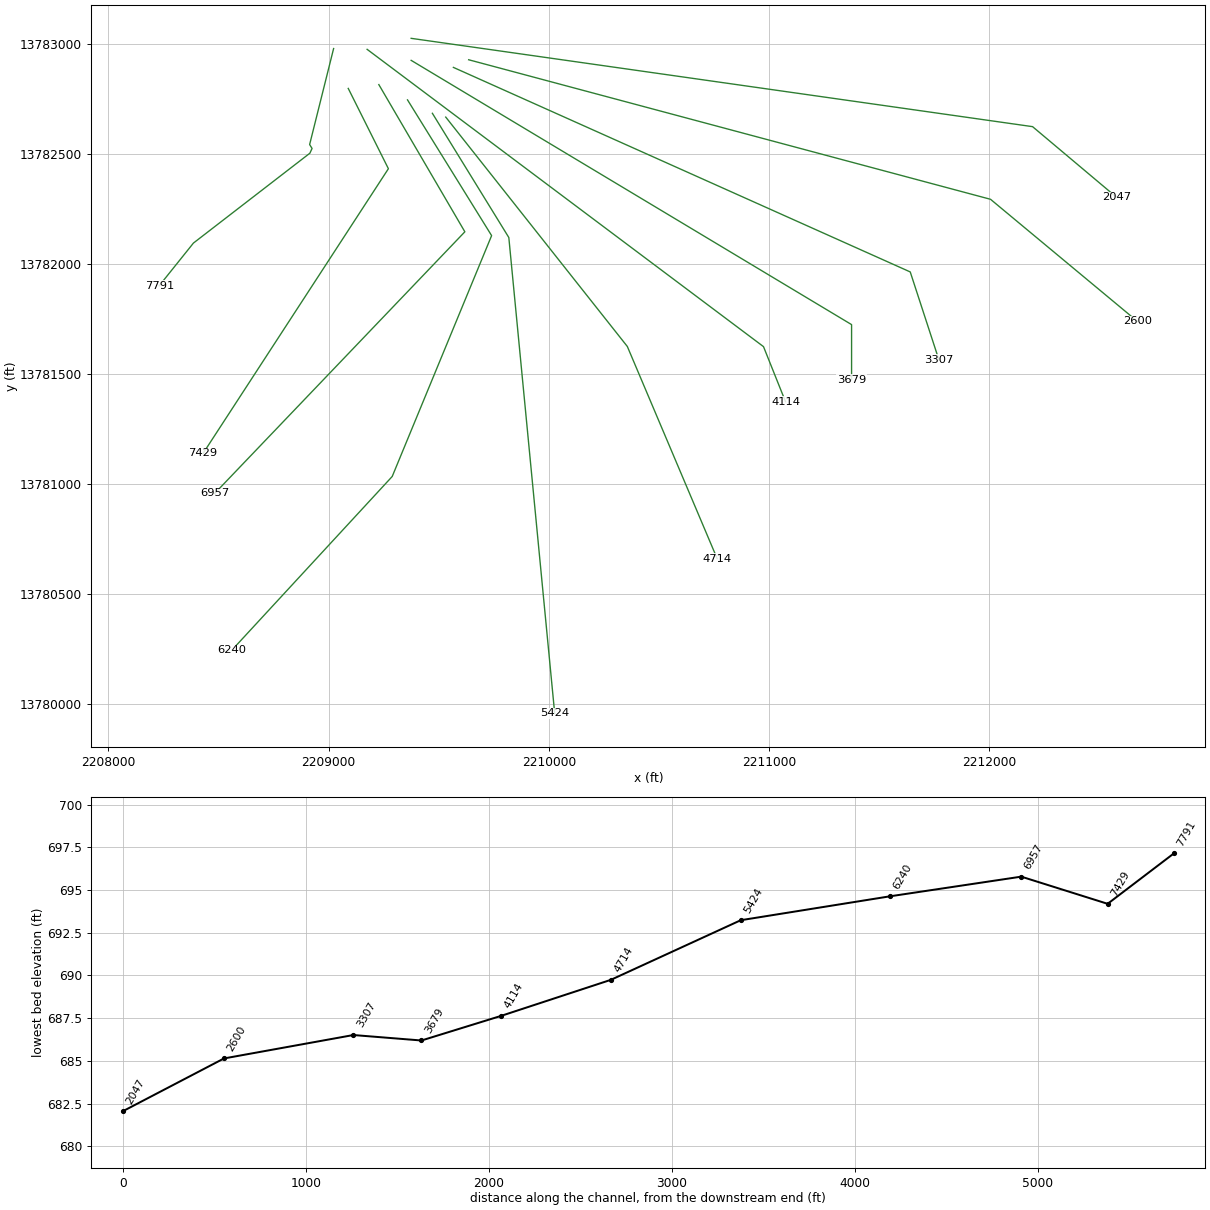
HEC-RAS study Dry Comal Creek Tributary 24.prj: Dry Comal Creek Tributary 24 Base Level Engineering

--- Dry Comal Creek Tributary 24.g01 (geometry) --- (continued)

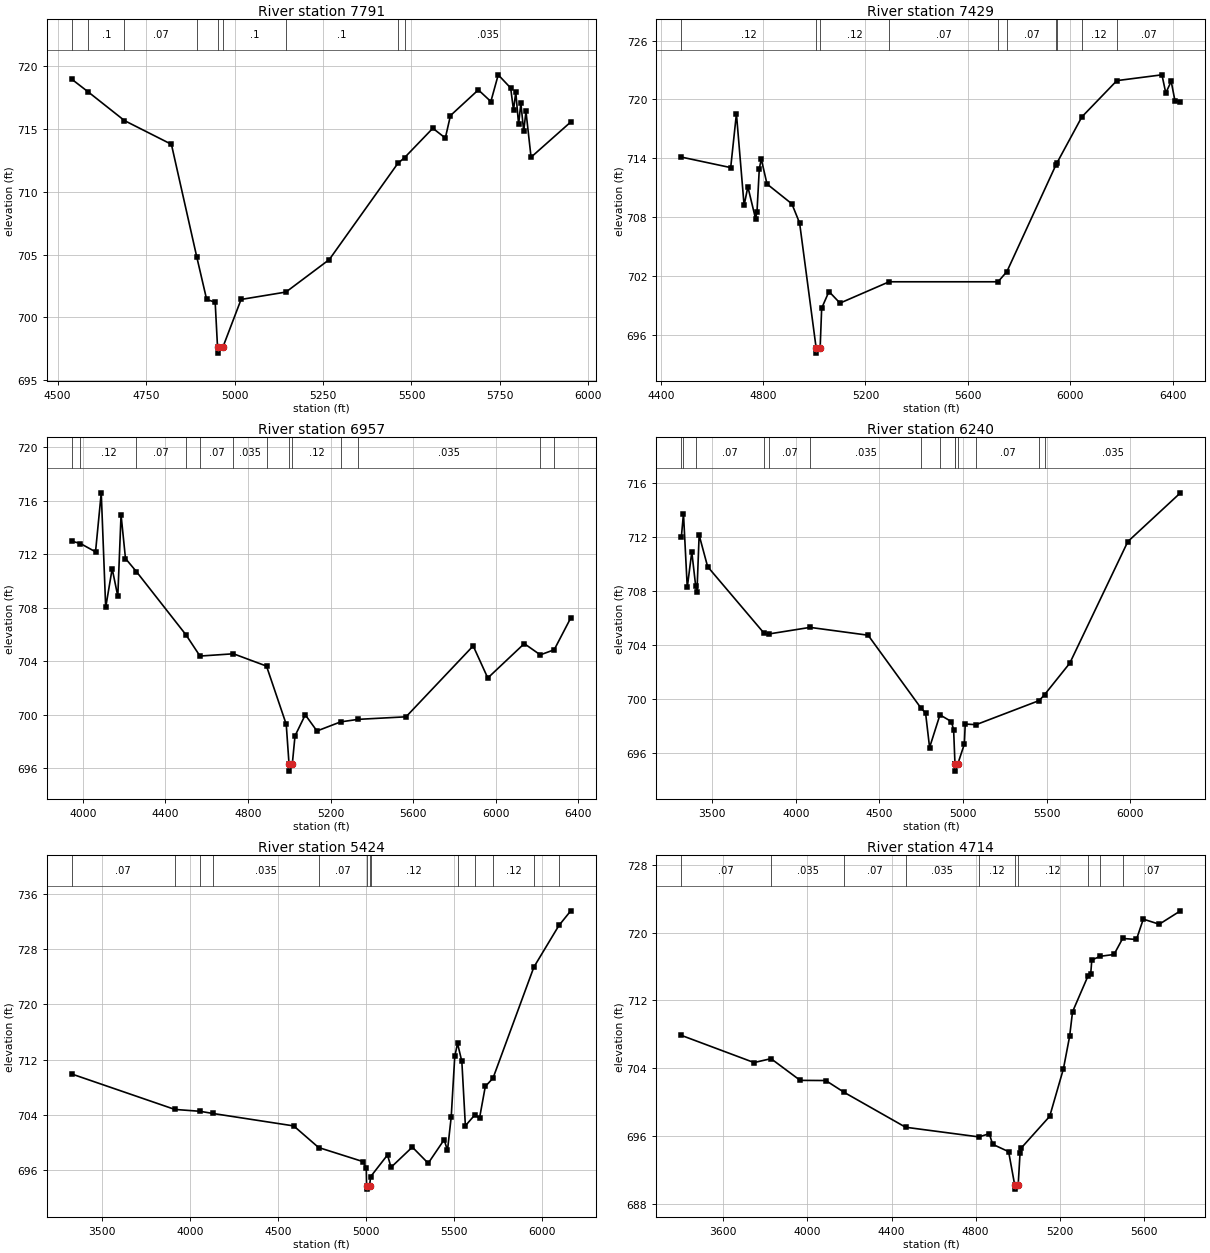
Type RM Length L Ch R = 1 ,7791    ,362,362,362
BEGIN DESCRIPTION:
Dry Comal Creek Tributary 24 6.0
END DESCRIPTION:
XS GIS Cut Line= 6
      2209022.85     13782978.64      2208913.94     13782542.69
        2208925.       13782525.      2208915.06     13782503.38
      2208386.31     13782095.33      2208230.71     13781901.31
#Sta/Elev= 30
  4539.5  718.99  4586.7  717.96  4688.9  715.68  4821.5  713.79  4893.4  704.78
    4921  701.43  4945.2  701.19  4951.8  697.64  4952.3  697.14  4967.3  697.64
  5018.4  701.42  5145.2  702.01  5267.7   704.6  5461.2  712.26  5480.5  712.73
  5560.3  715.07  5595.6  714.29  5610.1  716.08  5688.9  718.13  5724.3   717.2
  5745.1  719.33  5780.3  718.28  5788.3  716.51  5794.7  717.95  5802.7  715.37
  5809.1  717.07  5817.1  714.83  5823.5  716.41  5837.9  712.76  5950.1  715.57
#Mann= 9 ,-1 , 0
  4539.5     .07       0  4586.7      .1       0  4688.9     .07       0
  4893.4      .1       0  4951.8     .05       0  4967.3      .1       0
  5145.2      .1       0  5461.2     .07       0  5480.5    .035       0
Bank Sta=4951.8,4967.3
XS Rating Curve= 0 ,0
Exp/Cntr=0.3,0.1

Type RM Length L Ch R = 1 ,7429    ,472,472,472
BEGIN DESCRIPTION:
Dry Comal Creek Tributary 24 5.0
END DESCRIPTION:
XS GIS Cut Line= 3
      2209089.32     13782797.53      2209271.61     13782432.95
      2208429.95     13781140.09
#Sta/Elev= 30
  4480.5  714.14  4673.4  713.07  4695.8  718.55  4725.8  709.22  4740.5  711.12
  4770.6  707.86  4776.2  708.58  4785.2  712.96  4792.9  713.94  4815.3   711.4
  4912.5  709.38  4942.7  707.43  5007.4  694.69  5007.9  694.19  5022.9  694.69
  5028.9  698.76  5057.4  700.46  5100.5  699.28  5292.5  701.45    5718  701.45
  5752.7  702.49  5943.5   713.3  5947.3   713.5  6045.6  718.23  6182.3  721.92
  6358.4  722.51  6373.5  720.66  6394.6  721.85  6409.7  719.81  6430.8  719.79
#Mann= 10 ,-1 , 0
  4480.5     .12       0  5007.4     .05       0  5022.9     .12       0
  5292.5     .07       0    5718    .035       0  5752.7     .07       0
  5943.5    .035       0  5947.3     .07       0  6045.6     .12       0
  6182.3     .07       0
Bank Sta=5007.4,5022.9
XS Rating Curve= 0 ,0
Exp/Cntr=0.3,0.1

Type RM Length L Ch R = 1 ,6957    ,717,717,717
BEGIN DESCRIPTION:
Dry Comal Creek Tributary 24 4.0
END DESCRIPTION:
XS GIS Cut Line= 3
      2209228.19     13782814.94      2209618.83     13782146.49
      2208483.02     13780958.66
#Sta/Elev= 30
  3945.6  712.97  3988.3  712.79  4061.4  712.17  4089.1  716.58  4110.6  708.01
    4142  710.91  4169.3  708.85    4185  714.94  4206.5  711.67  4259.5  710.69
  4499.8  705.96  4567.4  704.38  4729.4  704.55  4889.6  703.63  4985.1  699.28
  4998.8  696.28  4999.3  695.78  5014.3  696.28  5027.6  698.41  5077.3  699.99
  5133.9  698.78  5248.4  699.46  5334.2  699.65  5565.4  699.84  5890.6  705.14
  5961.4  702.74  6138.1  705.31  6215.7  704.47    6283  704.85  6363.3  707.23
#Mann= 13 ,-1 , 0
  3945.6     .07       0  3988.3     .12       0  4259.5     .07       0
  4499.8     .12       0  4567.4     .07       0  4729.4    .035       0
  4889.6     .12       0  4998.8     .05       0  5014.3     .12       0
  5248.4     .07       0  5334.2    .035       0  6215.7     .07       0
    6283    .035       0
Bank Sta=4998.8,5014.3
XS Rating Curve= 0 ,0
Exp/Cntr=0.3,0.1

Type RM Length L Ch R = 1 ,6240    ,816,816,816
BEGIN DESCRIPTION:
X19000
END DESCRIPTION:
XS GIS Cut Line= 4
       2209358.4     13782745.49      2209740.36     13782129.13
      2209288.97     13781035.38      2208559.92     13780245.58
#Sta/Elev= 30
  3316.4  711.95  3329.3  713.71  3351.9  708.24    3379  710.87  3402.4  708.33
  3409.8  707.88  3422.9  712.12  3473.6  709.78  3812.2  704.83  3838.3  704.79
  4085.9  705.28  4432.8   704.7  4748.3  699.31  4776.3  698.93  4800.2  696.38
  4862.2   698.8  4930.7   698.3  4943.9  697.68  4951.9  695.19  4952.1  695.13
  4952.6  694.63  4967.9  695.13  5007.9  696.63  5013.3  698.12  5077.8  698.07
  5455.6  699.86  5487.1  700.29  5638.2  702.63  5985.2  711.64  6299.6  715.25
#Mann= 14 ,-1 , 0
  3316.4     .07       0  3329.3     .12       0  3402.4     .07       0
  3812.2     .12       0  3838.3     .07       0  4085.9    .035       0
  4748.3     .12       0  4862.2     .07       0  4951.9     .12       0
  4952.1     .05       0  4967.9     .12       0  5077.8     .07       0
  5455.6     .12       0  5487.1    .035       0
Bank Sta=4952.1,4967.9
XS Rating Curve= 0 ,0
Exp/Cntr=0.3,0.1

Type RM Length L Ch R = 1 ,5424    ,710,710,710
BEGIN DESCRIPTION:
X19001
END DESCRIPTION:
XS GIS Cut Line= 3
      2209471.29     13782684.65      2209818.49     13782120.45
      2210026.77     13779959.54
#Sta/Elev= 30
  3327.1  709.92  3912.8  704.78    4056  704.51  4127.1   704.2  4587.8  702.39
    4729  699.26  4979.6  697.23  4999.7  696.35  5001.4  693.73  5001.9  693.23
  5018.1  693.73  5024.8  695.05  5120.2  698.18  5140.3  696.39    5261  699.32
  5351.3  696.98  5441.7  700.39  5460.7  698.84  5481.9   703.7    5502  712.46
  5517.8  714.35  5542.2  711.73  5562.3  702.41  5616.4     704  5642.7  703.53
  5675.4  708.11  5719.1  709.31  5951.2  725.41  6093.4  731.44  6160.5  733.56
#Mann= 13 ,-1 , 0
  3327.1     .07       0  3912.8    .035       0    4056     .07       0
  4127.1    .035       0    4729     .07       0  5001.4     .05       0
  5018.1     .07       0  5024.8     .12       0  5517.8     .07       0
  5616.4      .1       0  5719.1     .12       0  5951.2    .035       0
  6093.4     .07       0
Bank Sta=5001.4,5018.1
XS Rating Curve= 0 ,0
Exp/Cntr=0.3,0.1

Type RM Length L Ch R = 1 ,4714    ,600,600,600
BEGIN DESCRIPTION:
X19002
END DESCRIPTION:
XS GIS Cut Line= 3
      2209532.04     13782667.31      2210356.68     13781625.66
      2210764.66     13780662.14
#Sta/Elev= 30
  3399.8  707.88  3745.8  704.67  3826.5  705.13  3965.4  702.57  4087.2  702.55
    4175  701.15  4467.1  697.04    4816   695.9    4865  696.28  4881.1  695.03
  4957.1  694.16  4985.9  690.24  4986.4  689.74  5002.6  690.24  5011.4  693.97
  5017.9  694.61  5152.6  698.33  5217.8  703.93  5247.4  707.77  5261.2  710.66
  5335.4  714.92  5347.5  715.06  5352.9  716.78  5394.2  717.21  5458.5  717.42
  5499.7  719.31  5565.3  719.19  5597.8  721.59  5673.9  720.99  5774.7  722.57
#Mann= 10 ,-1 , 0
  3399.8     .07       0  3826.5    .035       0    4175     .07       0
  4467.1    .035       0    4816     .12       0  4985.9     .05       0
  5002.6     .12       0  5335.4     .07       0  5394.2    .035       0
  5499.7     .07       0
Bank Sta=4985.9,5002.6
XS Rating Curve= 0 ,0
Exp/Cntr=0.3,0.1

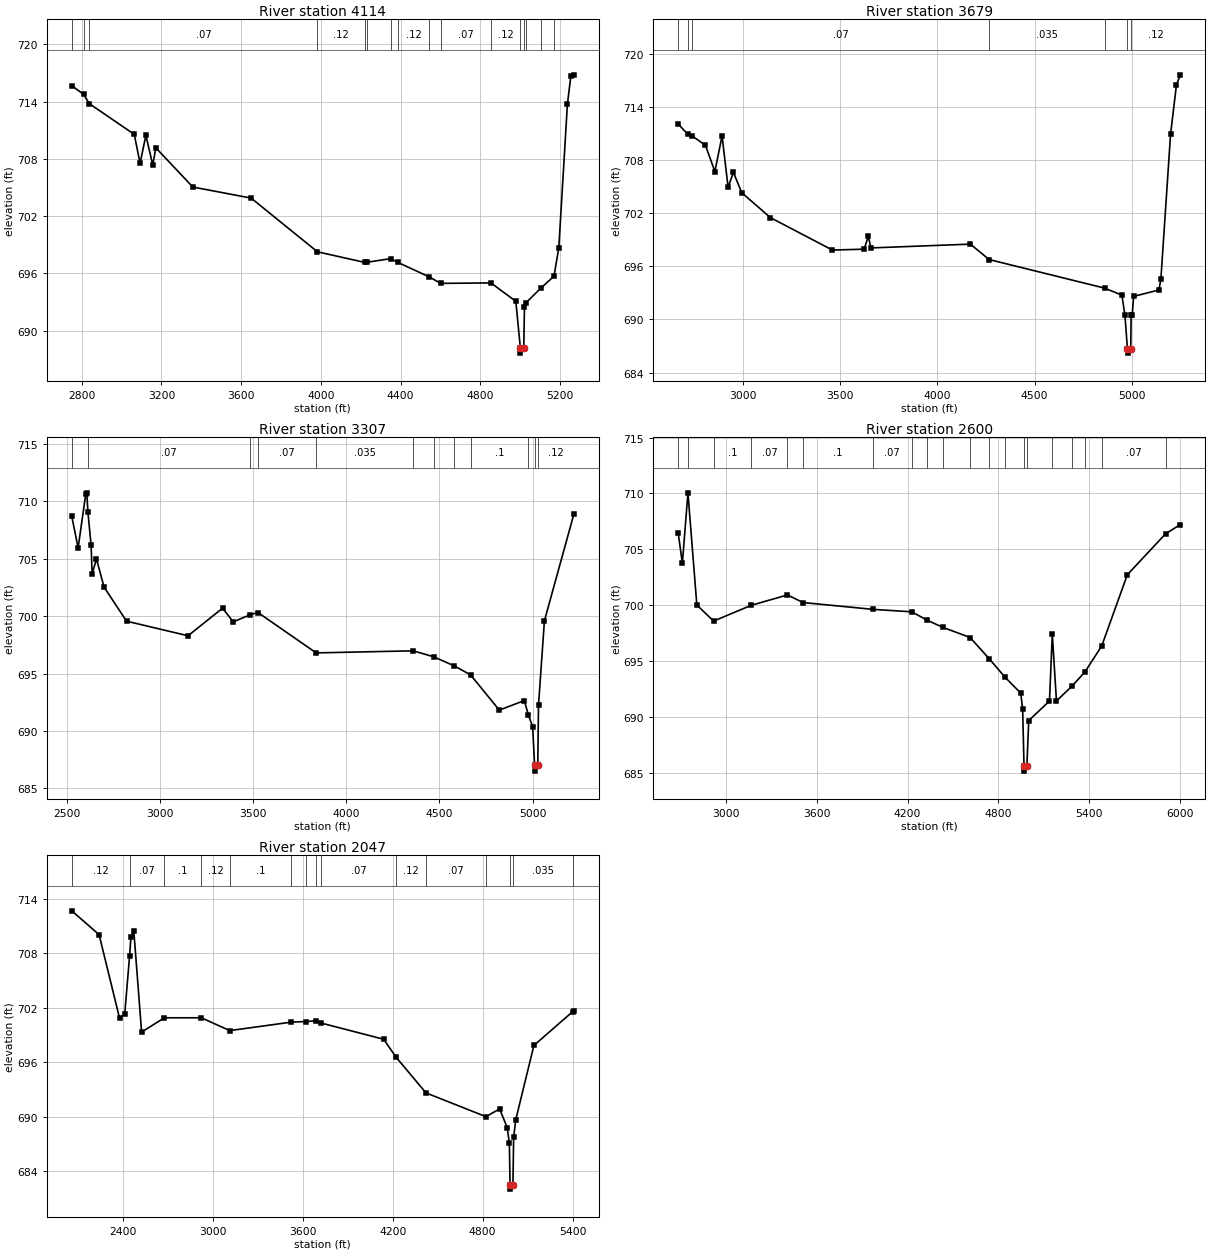
Type RM Length L Ch R = 1 ,4114    ,435,435,435
BEGIN DESCRIPTION:
Dry Comal Creek Tributary 24 3.0
END DESCRIPTION:
XS GIS Cut Line= 3
      2209174.97     13782975.02        2210975.       13781625.
        2211075.       13781375.
#Sta/Elev= 30
  2750.2  715.67  2809.9  714.74  2838.2  713.78  3063.8  710.56  3092.9  707.52
  3122.1  710.46  3156.5  707.35  3172.1  709.15  3357.5  705.04  3650.2  703.88
  3982.9  698.25  4219.9  697.14  4229.4  697.15  4349.7  697.53  4387.2  697.13
  4544.9  695.61  4601.6  694.94  4853.5  694.99  4978.4  693.06  5001.3  688.13
  5001.8  687.63  5018.1  688.13  5021.8  692.49  5029.9  692.92  5102.8  694.42
  5170.1   695.7  5194.1   698.7  5237.2  713.73  5254.7  716.71  5269.5   716.8
#Mann= 16 ,-1 , 0
  2750.2     .07       0  2809.9     .12       0  2838.2     .07       0
  3982.9     .12       0  4219.9     .07       0  4229.4     .12       0
  4349.7     .07       0  4387.2     .12       0  4544.9    .035       0
  4601.6     .07       0  4853.5     .12       0  5001.3     .05       0
  5018.1     .12       0  5029.9     .07       0  5102.8     .12       0
  5170.1     .07       0
Bank Sta=5001.3,5018.1
XS Rating Curve= 0 ,0
Exp/Cntr=0.3,0.1

Type RM Length L Ch R = 1 ,3679    ,372,372,372
BEGIN DESCRIPTION:
Dry Comal Creek Tributary 24 2.0
END DESCRIPTION:
XS GIS Cut Line= 3
      2209375.04     13782924.97        2211375.       13781725.
        2211375.     13781475.03
#Sta/Elev= 30
  2667.3  712.06  2716.7   710.9  2738.4  710.73  2807.2  709.66  2855.8   706.7
  2892.7  710.73  2923.8  704.91    2951  706.61  2993.8  704.31  3141.5  701.49
  3460.3  697.83  3623.5  697.93  3644.9  699.38  3658.5  698.07  4169.7   698.5
  4266.1  696.76  4860.4  693.53  4949.1  692.74  4964.6   690.5  4977.6  686.69
  4978.1  686.19  4994.5  686.69  4996.7  690.49  5002.1  690.49  5009.6   692.6
  5139.6  693.32  5149.6  694.53  5199.6  710.94  5229.6  716.46  5249.6  717.62
#Mann= 7 ,-1 , 0
  2667.3     .07       0  2716.7     .12       0  2738.4     .07       0
  4266.1    .035       0  4860.4     .12       0  4977.6     .05       0
  4994.5     .12       0
Bank Sta=4977.6,4994.5
XS Rating Curve= 0 ,0
Exp/Cntr=0.3,0.1

Type RM Length L Ch R = 1 ,3307    ,707,707,707
BEGIN DESCRIPTION:
X19003
END DESCRIPTION:
XS GIS Cut Line= 3
      2209566.77     13782893.01       2211641.4      13781964.2
      2211771.63     13781564.86
#Sta/Elev= 30
  2528.1  708.68  2562.2  705.94  2602.9   710.6  2608.6  710.73  2614.6  709.08
  2631.8  706.15  2637.3  703.66  2660.5  704.98  2701.4  702.52    2822  699.56
  3151.7  698.29  3336.9  700.69  3394.6   699.5  3484.7  700.12  3527.1  700.31
  3839.2   696.8  4359.8  696.98  4469.2  696.46  4578.6  695.68  4667.1  694.89
  4821.4  691.82  4955.4  692.65  4977.5  691.39  5000.2  690.39  5010.7  687.01
  5011.2  686.51  5027.6  687.01  5031.7  692.27  5063.3  699.59  5221.2  708.87
#Mann= 12 ,-1 , 0
  2528.1     .12       0  2614.6     .07       0  3484.7     .12       0
  3527.1     .07       0  3839.2    .035       0  4359.8     .07       0
  4469.2    .035       0  4578.6     .12       0  4667.1      .1       0
  4977.5     .12       0  5010.7     .05       0  5027.6     .12       0
Bank Sta=5010.7,5027.6
XS Rating Curve= 0 ,0
Exp/Cntr=0.3,0.1

Type RM Length L Ch R = 1 ,2600    ,553,553,553
BEGIN DESCRIPTION:
X19004
END DESCRIPTION:
XS GIS Cut Line= 3
      2209636.16     13782927.75      2212005.99     13782294.06
      2212673.53     13781739.23
#Sta/Elev= 30
  2683.1  706.43  2710.4  703.75  2747.3  710.05  2806.1  700.01  2916.9  698.57
  3165.5  699.98  3405.7  700.91  3508.5  700.23  3970.1  699.62  4227.9   699.4
  4330.7  698.64  4433.4  698.01  4613.7   697.1  4741.8  695.17  4844.5  693.55
  4948.8  692.12  4961.4  690.67  4970.2  685.64  4970.7  685.14  4989.5  685.64
  5001.4  689.66  5138.8  691.42  5157.5  697.41  5184.9  691.42  5288.9  692.76
  5373.3  694.02  5484.9  696.36  5653.7  702.72  5906.5  706.38  6004.2  707.21
#Mann= 20 ,-1 , 0
  2683.1     .12       0  2747.3     .07       0  2916.9      .1       0
  3165.5     .07       0  3405.7     .12       0  3508.5      .1       0
  3970.1     .07       0  4227.9    .035       0  4330.7     .07       0
  4433.4     .12       0  4613.7      .1       0  4741.8     .12       0
  4844.5      .1       0  4970.2     .05       0  4989.5      .1       0
  5157.5    .035       0  5288.9     .07       0  5373.3    .035       0
  5484.9     .07       0  5906.5    .035       0
Bank Sta=4970.2,4989.5
XS Rating Curve= 0 ,0
Exp/Cntr=0.3,0.1

Type RM Length L Ch R = 1 ,2047    ,0,0,0
BEGIN DESCRIPTION:
Dry Comal Creek Tributary 24 1.0
END DESCRIPTION:
XS GIS Cut Line= 3
      2209374.98       13783025.      2212196.96     13782623.93
      2212578.92     13782302.73
#Sta/Elev= 30
  2059.3  712.65  2241.6  710.03  2378.3  700.83  2412.8  701.34  2444.7  707.63
  2454.2  709.82  2473.4  710.39  2525.1  699.32  2677.4  700.89  2923.8  700.89
  3113.2  699.48  3523.2  700.41  3623.1  700.48  3690.6  700.56    3723  700.31
    4140  698.53  4222.5  696.56  4422.3  692.63    4822  690.02  4913.6  690.87
  4964.1  688.82  4978.4  687.14  4983.1  682.55  4983.6  682.05  5002.4  682.55
    5007  687.74  5021.3  689.69  5142.3  697.85  5401.2  701.57  5408.7  701.59
#Mann= 15 ,-1 , 0
  2059.3     .12       0  2444.7     .07       0  2677.4      .1       0
  2923.8     .12       0  3113.2      .1       0  3523.2     .12       0
  3623.1     .07       0  3690.6     .12       0    3723     .07       0
  4222.5     .12       0  4422.3     .07       0    4822    .035       0
  4983.1    .035       0  5002.4    .035       0  5401.2     .07       0
Bank Sta=4983.1,5002.4
XS Rating Curve= 0 ,0
Exp/Cntr=0.3,0.1

Chan Stop Cuts=-1
Use User Specified Reach Order=0
Composite Channel Slope=5