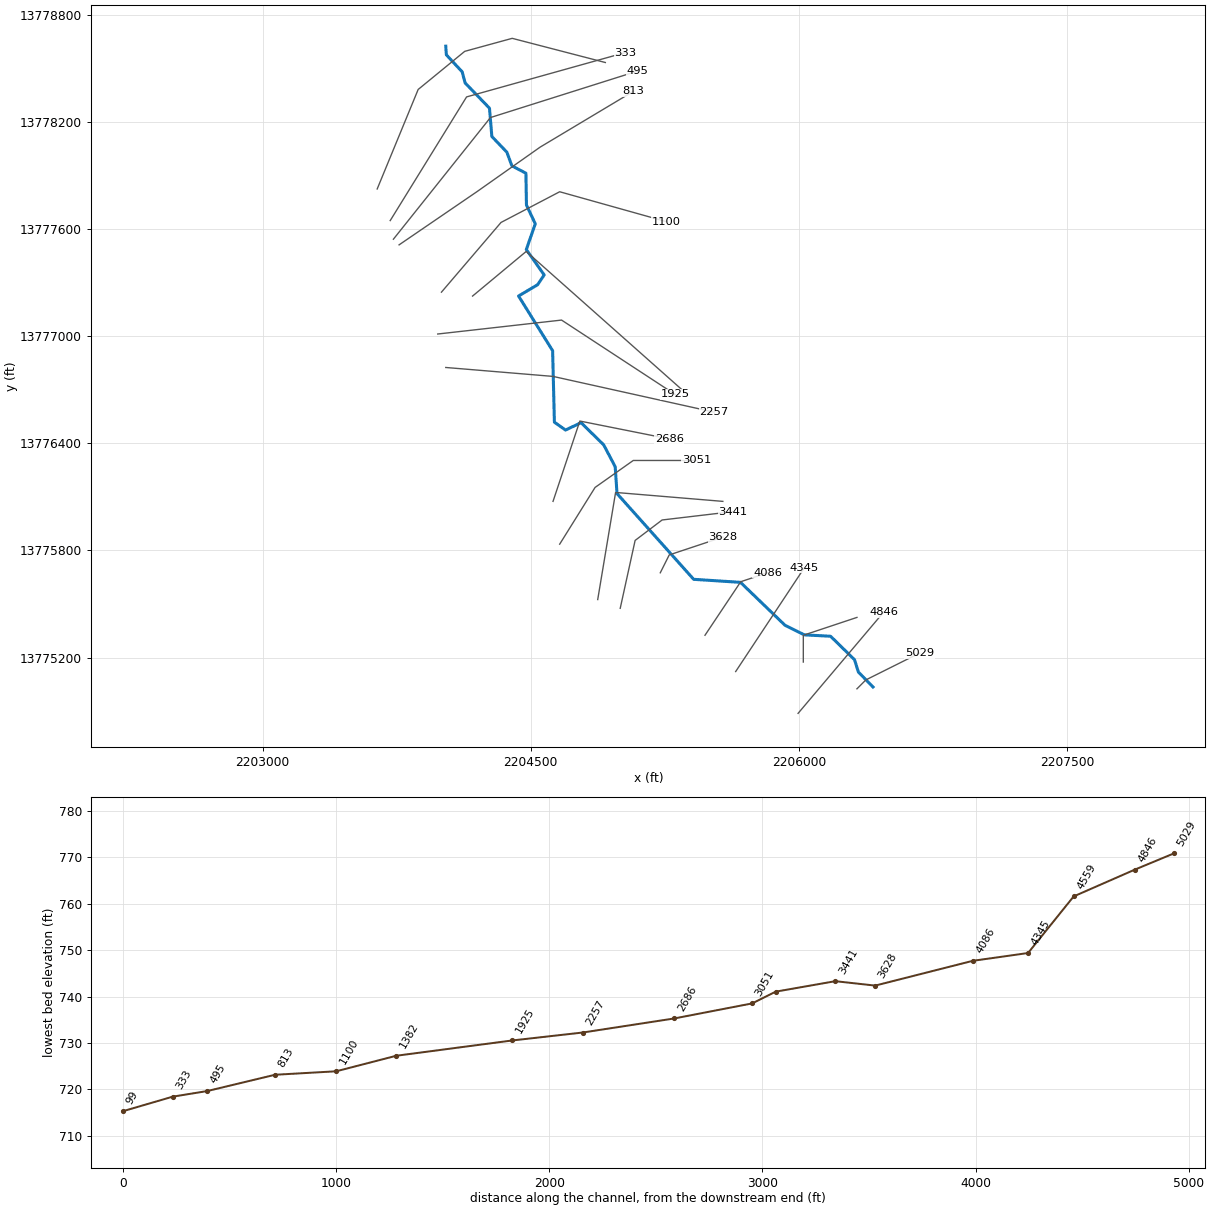
--- Dry Comal Creek Tributary 28.prj (project) ---

Proj Title=Dry Comal Creek Tributary 28 Base Level Engineering
Current Plan=p01
Default Exp/Contr=0.3,0.1
English Units
Geom File=g01
Flow File=f01
Plan File=p01
BEGIN DESCRIPTION:
Dry Comal Creek Tributary 28
END DESCRIPTION:

--- Dry Comal Creek Tributary 28.p01 (plan) ---

Plan Title=Multiple Run
Short Identifier=Multiple
Geom File=g01
Flow File=f01
Subcritical Flow
K Sum by GR= 0
Std Step Tol= 0.01
Critical Tol= 0.01
Num of Std Step Trials= 20
Max Error Tol= 0.3
Flow Tol Ratio= 0.001
Split Flow NTrial= 30
Split Flow Tol= 0.02
Split Flow Ratio= 0.02
Log Output Level= 0
Friction Slope Method= 1
Unsteady Friction Slope Method= 2
Unsteady Bridges Friction Slope Method= 1
Parabolic Critical Depth
Global Vel Dist=  1 , 1 , 1
Global Log Level= 0
CheckData=True
Encroach Param= -1, 0, 0, 0
BEGIN DESCRIPTION:
Multiple Run
END DESCRIPTION:

--- Dry Comal Creek Tributary 28.f01 (steady flow) ---

Flow Title=Multiple
Number of Profiles=7
Profile Names=10-year,25-year,50-year,1pct_min,100-year,1pct_plu,500-year
River Rch & RM= Dry Comal Creek ,Reach-1,5029
     698    1141    1547    1017    2029    4048    3450
Boundary for River Rch & Prof#=Dry Comal Creek ,Reach-1,1
Up Type=0
Dn Type=3
Dn Slope=0.005
Boundary for River Rch & Prof#=Dry Comal Creek ,Reach-1,2
Up Type=0
Dn Type=3
Dn Slope=0.005
Boundary for River Rch & Prof#=Dry Comal Creek ,Reach-1,3
Up Type=0
Dn Type=3
Dn Slope=0.005
Boundary for River Rch & Prof#=Dry Comal Creek ,Reach-1,4
Up Type=0
Dn Type=3
Dn Slope=0.005
Boundary for River Rch & Prof#=Dry Comal Creek ,Reach-1,5
Up Type=0
Dn Type=3
Dn Slope=0.005
Boundary for River Rch & Prof#=Dry Comal Creek ,Reach-1,6
Up Type=0
Dn Type=3
Dn Slope=0.005
Boundary for River Rch & Prof#=Dry Comal Creek ,Reach-1,7
Up Type=0
Dn Type=3
Dn Slope=0.005

--- Dry Comal Creek Tributary 28.g01 (geometry) ---

Geom Title=Existing Conditions

River Reach=Dry Comal Creek ,Reach-1
Reach XY= 30
      2206414.70     13775035.30      2206333.08     13775118.92
      2206311.38     13775188.21      2206177.45     13775319.53
      2206030.93     13775327.25      2205922.70     13775380.83
      2205673.54     13775621.46      2205411.68     13775638.37
      2204982.82     13776118.81      2204972.75     13776269.07
      2204908.36     13776391.68      2204781.73     13776515.85
      2204695.05     13776474.63      2204632.69     13776518.43
      2204622.76     13776919.07      2204432.20     13777225.30
      2204538.68     13777288.49      2204575.42     13777343.30
      2204475.61     13777485.62      2204525.80     13777630.03
      2204476.38     13777734.66      2204473.36     13777913.17
      2204394.74     13777954.57      2204366.82     13778031.02
      2204282.83     13778118.82      2204269.53     13778277.45
      2204133.16     13778418.95      2204116.84     13778481.05
      2204028.29     13778576.36      2204025.00     13778625.00

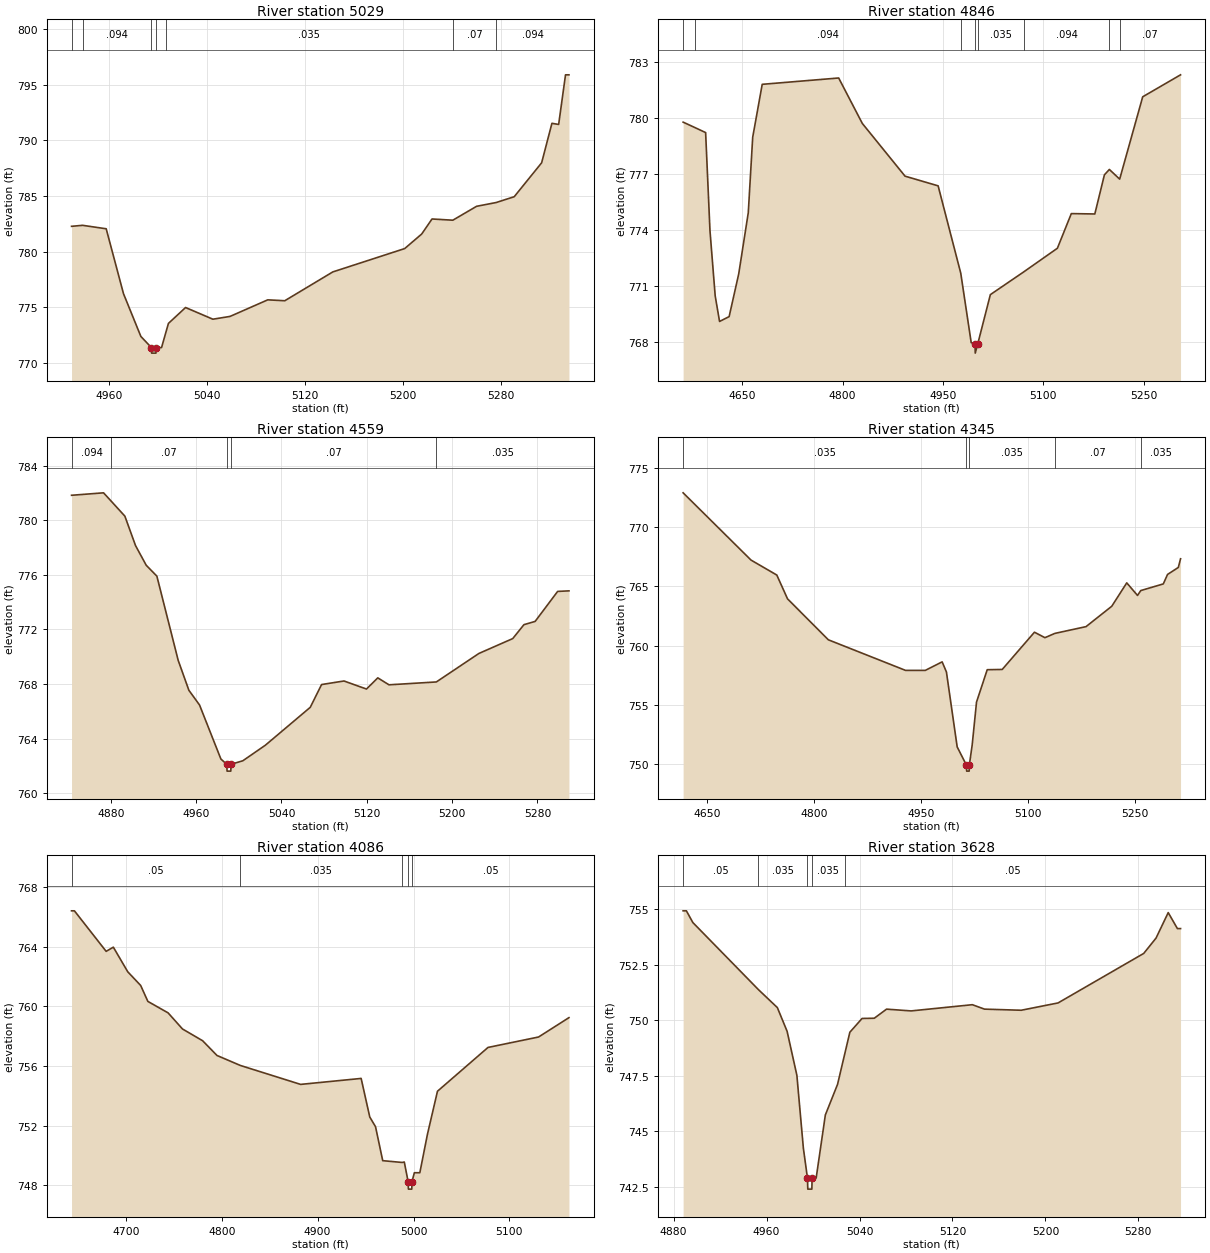
Type RM Length L Ch R = 1,5029,183,183,183
BEGIN DESCRIPTION:
Dry Comal Creek Tributary 28 10.0
END DESCRIPTION:
XS GIS Cut Line= 3
      2206324.99     13775024.99      2206375.00     13775075.00
      2206674.97     13775224.99
#Sta/Elev= 30
  4929.6  782.28  4938.6  782.37  4957.9  782.06  4972.0  776.23  4986.2  772.38
  4994.8  771.38  4995.0  770.88  4998.5  770.88  4998.8  771.38  5003.1  771.38
  5006.7  772.78  5008.7  773.55  5022.7  774.98  5045.0  773.93  5059.0  774.18
  5089.8  775.67  5103.7  775.59  5142.9  778.18  5201.6  780.28  5215.5  781.59
  5223.9  782.94  5240.9  782.83  5260.3  784.08  5276.3  784.42  5291.0  784.94
  5313.4  787.99  5321.8  791.54  5327.3  791.44  5332.9  795.90  5335.7  795.90
#Mann=7,-1,0
  4929.6     0.1       0  4938.6   0.094       0  4994.8    0.05       0
  4998.8   0.094       0  5006.7   0.035       0  5240.9    0.07       0
  5276.3   0.094       0
Bank Sta=4994.8,4998.8
Exp/Cntr=0.3,0.1

Type RM Length L Ch R = 1,4846,287,287,287
BEGIN DESCRIPTION:
X19011
END DESCRIPTION:
XS GIS Cut Line= 2
      2205995.68     13774887.48      2206474.79     13775455.11
#Sta/Elev= 30
  4562.0  779.79  4579.5  779.50  4595.6  779.23  4602.1  773.96  4609.9  770.46
  4616.4  769.09  4630.7  769.35  4645.0  771.64  4659.3  774.93  4665.9  778.98
  4680.1  781.82  4794.3  782.16  4829.6  779.72  4893.4  776.89  4942.8  776.37
  4976.6  771.68  4992.2  767.95  4998.0  767.89  4998.2  767.39  5002.0  767.89
  5020.8  770.53  5071.0  771.76  5120.9  773.02  5141.7  774.88  5176.8  774.86
  5191.1  776.96  5198.5  777.25  5213.9  776.73  5248.3  781.15  5304.8  782.33
#Mann=8,-1,0
  4562.0     0.1       0  4579.5   0.094       0  4976.6   0.035       0
  4998.0   0.035       0  5002.0   0.035       0  5071.0   0.094       0
  5198.5   0.035       0  5213.9    0.07       0
Bank Sta=4998,5002
Exp/Cntr=0.3,0.1

Type RM Length L Ch R = 1,4559,214,214,214
BEGIN DESCRIPTION:
Dry Comal Creek Tributary 28 9.0
END DESCRIPTION:
XS GIS Cut Line= 3
      2206025.00     13775174.96      2206025.00     13775325.00
      2206325.03     13775425.01
#Sta/Elev= 30
  4843.2  781.84  4873.2  782.02  4880.6  781.39  4893.2  780.31  4903.2  778.15
  4913.2  776.71  4923.2  775.91  4943.2  769.73  4953.2  767.54  4963.2  766.46
  4983.2  762.50  4988.7  762.11  4989.0  761.61  4992.5  761.61  4992.7  762.11
  5003.8  762.37  5024.9  763.51  5067.0  766.29  5077.6  767.96  5098.6  768.22
  5119.7  767.63  5130.3  768.45  5140.8  767.94  5185.2  768.15  5225.1  770.24
  5256.8  771.33  5267.3  772.35  5277.8  772.59  5298.9  774.79  5309.5  774.83
#Mann=5,-1,0
  4843.2   0.094       0  4880.6    0.07       0  4988.7    0.05       0
  4992.7    0.07       0  5185.2   0.035       0
Bank Sta=4988.7,4992.7
Exp/Cntr=0.3,0.1

Type RM Length L Ch R = 1,4345,259,259,259
BEGIN DESCRIPTION:
X19010
END DESCRIPTION:
XS GIS Cut Line= 2
      2205646.68     13775121.80      2206031.07     13775703.58
#Sta/Elev= 30
  4616.5  772.87  4711.7  767.20  4747.8  765.94  4762.9  763.93  4820.1  760.48
  4928.4  757.90  4955.9  757.90  4979.6  758.62  4985.6  757.77  5000.7  751.45
  5013.7  749.91  5014.0  749.41  5017.5  749.41  5017.7  749.91  5021.7  751.61
  5027.8  755.23  5042.8  757.96  5063.8  757.98  5109.0  761.12  5123.7  760.66
  5137.6  761.02  5181.3  761.59  5217.4  763.31  5238.4  765.28  5253.5  764.22
  5258.0  764.63  5289.6  765.19  5295.6  765.99  5310.7  766.58  5313.8  767.31
#Mann=5,-1,0
  4616.5   0.035       0  5013.7   0.035       0  5017.7   0.035       0
  5137.6    0.07       0  5258.0   0.035       0
Bank Sta=5013.7,5017.7
Exp/Cntr=0.3,0.1

Type RM Length L Ch R = 1,4086,458,458,458
BEGIN DESCRIPTION:
Dry Comal Creek Tributary 28 8.0
END DESCRIPTION:
XS GIS Cut Line= 3
      2205475.00     13775325.00      2205675.00     13775625.00
      2205825.03     13775675.01
#Sta/Elev= 30
  4643.4  766.41  4646.4  766.41  4679.5  763.69  4687.0  763.97  4702.0  762.32
  4715.5  761.40  4723.0  760.33  4744.1  759.56  4759.1  758.48  4780.1  757.69
  4795.1  756.70  4819.5  756.03  4882.3  754.76  4945.4  755.16  4954.4  752.57
  4960.4  751.92  4967.9  749.64  4988.2  749.52  4990.4  749.55  4994.4  748.23
  4994.7  747.73  4998.2  747.73  4998.4  748.23  5000.9  748.83  5006.6  748.83
  5014.5  751.40  5025.0  754.30  5077.7  757.24  5130.4  757.94  5162.1  759.24
#Mann=5,-1,0
  4643.4    0.05       0  4819.5   0.035       0  4988.2    0.05       0
  4994.4    0.05       0  4998.4    0.05       0
Bank Sta=4994.4,4998.4
Exp/Cntr=0.3,0.1

Type RM Length L Ch R = 1,3628,187,187,187
BEGIN DESCRIPTION:
Dry Comal Creek Tributary 28 7.0
END DESCRIPTION:
XS GIS Cut Line= 3
      2205224.98     13775674.97      2205275.00     13775775.00
      2205575.03     13775875.01
#Sta/Elev= 30
  4888.2  754.93  4891.0  754.93  4896.6  754.40  4953.0  751.38  4969.3  750.57
  4977.7  749.50  4986.1  747.52  4991.7  744.23  4995.2  742.89  4995.5  742.39
  4999.0  742.39  4999.2  742.89  5002.7  742.89  5010.6  745.73  5021.1  747.11
  5027.1  748.44  5031.7  749.46  5042.2  750.08  5052.7  750.09  5063.3  750.50
  5084.4  750.42  5137.1  750.70  5147.6  750.50  5179.2  750.45  5210.9  750.78
  5284.6  753.01  5295.2  753.70  5305.7  754.85  5313.6  754.13  5316.3  754.13
#Mann=5,-1,0
  4888.2    0.05       0  4953.0   0.035       0  4995.2   0.035       0
  4999.2   0.035       0  5027.1    0.05       0
Bank Sta=4995.2,4999.2
Exp/Cntr=0.3,0.1

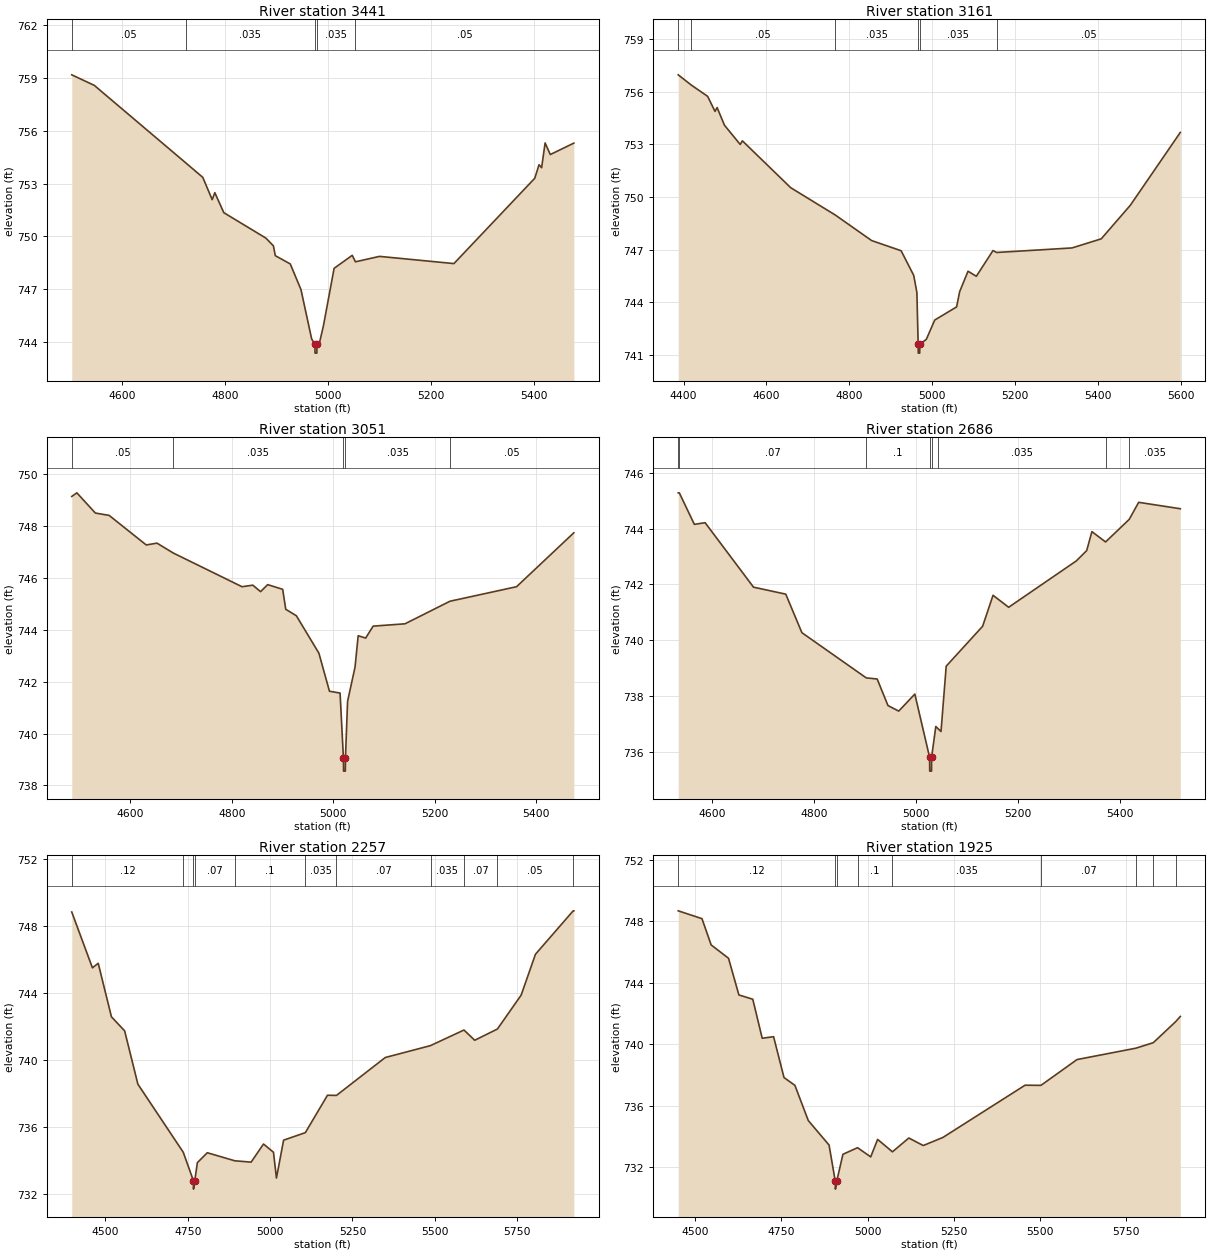
Type RM Length L Ch R = 1,3441,280,280,280
BEGIN DESCRIPTION:
X19009
END DESCRIPTION:
XS GIS Cut Line= 4
      2205000.87     13775476.03      2205084.19     13775856.19
      2205235.23     13775970.78      2205630.50     13776017.58
#Sta/Elev= 30
  4501.4  759.19  4545.2  758.59  4723.4  754.17  4756.3  753.35  4774.6  752.08
  4779.7  752.48  4797.2  751.34  4879.1  749.89  4893.7  749.45  4897.4  748.89
  4926.5  748.42  4947.3  746.96  4968.1  744.15  4974.4  743.84  4974.7  743.34
  4978.2  743.34  4978.4  743.84  4982.7  743.85  4990.9  744.88  5011.8  748.17
  5047.1  748.91  5053.3  748.54  5100.1  748.85  5244.9  748.44  5402.2  753.30
  5410.5  754.07  5415.5  753.90  5422.3  755.31  5432.4  754.65  5478.2  755.30
#Mann=5,-1,0
  4501.4    0.05       0  4723.4   0.035       0  4974.4   0.035       0
  4978.4   0.035       0  5053.3    0.05       0
Bank Sta=4974.4,4978.4
Exp/Cntr=0.3,0.1

Type RM Length L Ch R = 1,3161,110,110,110
BEGIN DESCRIPTION:
Dry Comal Creek Tributary 28 6.0
END DESCRIPTION:
XS GIS Cut Line= 3
      2204875.01     13775525.04      2204975.00     13776125.00
      2205574.98     13776075.00
#Sta/Elev= 30
  4387.3  756.98  4418.5  756.40  4458.2  755.75  4476.0  754.89  4481.0  755.11
  4498.8  754.10  4536.8  753.00  4541.9  753.21  4658.5  750.53  4765.9  748.97
  4853.6  747.51  4924.6  746.93  4955.0  745.52  4962.6  744.54  4965.7  741.58
  4965.9  741.08  4969.4  741.08  4969.7  741.58  4985.4  741.87  5005.6  742.97
  5058.3  743.72  5065.8  744.60  5085.9  745.76  5105.9  745.47  5146.1  746.94
  5154.9  746.83  5336.7  747.09  5407.0  747.61  5477.2  749.53  5597.6  753.69
#Mann=6,-1,0
  4387.3   0.035       0  4418.5    0.05       0  4765.9   0.035       0
  4965.7   0.035       0  4969.7   0.035       0  5154.9    0.05       0
Bank Sta=4965.7,4969.7
Exp/Cntr=0.3,0.1

Type RM Length L Ch R = 1,3051,365,365,365
BEGIN DESCRIPTION:
X19012
END DESCRIPTION:
XS GIS Cut Line= 4
      2204662.30     13775835.34      2204860.23     13776153.07
      2205073.78     13776304.11      2205427.98     13776304.11
#Sta/Elev= 30
  4484.6  749.14  4494.6  749.28  4531.2  748.50  4558.3  748.41  4631.5  747.27
  4652.7  747.34  4684.7  746.96  4820.3  745.66  4841.6  745.72  4856.9  745.47
  4870.9  745.74  4900.5  745.56  4906.6  744.79  4927.5  744.54  4971.9  743.10
  4992.8  741.63  5013.7  741.56  5020.3  739.05  5020.6  738.55  5024.1  738.55
  5024.3  739.05  5028.5  741.24  5043.2  742.56  5049.4  743.77  5064.2  743.68
  5078.9  744.14  5141.7  744.23  5230.4  745.10  5361.7  745.66  5474.7  747.74
#Mann=5,-1,0
  4484.6    0.05       0  4684.7   0.035       0  5020.3   0.035       0
  5024.3   0.035       0  5230.4    0.05       0
Bank Sta=5020.3,5024.3
Exp/Cntr=0.3,0.1

Type RM Length L Ch R = 1,2686,429,429,429
BEGIN DESCRIPTION:
Dry Comal Creek Tributary 28 5.0
END DESCRIPTION:
XS GIS Cut Line= 3
      2204625.00     13776075.01      2204775.00     13776525.00
      2205274.97     13776425.01
#Sta/Elev= 30
  4533.9  745.28  4536.0  745.28  4565.5  744.15  4586.6  744.21  4681.5  741.90
  4744.7  741.65  4776.3  740.27  4902.5  738.65  4923.9  738.61  4945.0  737.66
  4966.1  737.46  4997.7  738.07  5026.6  735.81  5026.9  735.31  5030.4  735.31
  5030.6  735.81  5038.8  736.91  5043.2  736.83  5049.0  736.73  5059.2  739.07
  5130.6  740.50  5151.0  741.61  5181.6  741.18  5314.2  742.84  5334.6  743.21
  5344.8  743.89  5371.6  743.52  5418.0  744.33  5436.5  744.94  5518.1  744.71
#Mann=8,-1,0
  4533.9   0.035       0  4536.0    0.07       0  4902.5     0.1       0
  5026.6    0.05       0  5030.6     0.1       0  5043.2   0.035       0
  5371.6    0.07       0  5418.0   0.035       0
Bank Sta=5026.6,5030.6
Exp/Cntr=0.3,0.1

Type RM Length L Ch R = 1,2257,332,332,332
BEGIN DESCRIPTION:
Dry Comal Creek Tributary 28 4.0
END DESCRIPTION:
XS GIS Cut Line= 3
      2204025.02     13776825.00      2204625.00     13776775.00
      2205524.98     13776575.00
#Sta/Elev= 30
  4397.9  748.81  4460.6  745.48  4478.2  745.75  4518.3  742.56  4558.4  741.72
  4598.6  738.54  4736.3  734.48  4767.2  732.78  4767.4  732.28  4771.2  732.78
  4779.2  733.86  4809.3  734.45  4892.8  733.97  4942.3  733.89  4979.9  734.97
  5010.2  734.48  5019.2  732.94  5040.9  735.20  5106.9  735.65  5174.1  737.88
  5201.4  737.87  5349.5  740.13  5486.8  740.84  5588.4  741.77  5621.0  741.16
  5689.9  741.83  5761.9  743.85  5805.4  746.29  5919.9  748.88  5921.9  748.88
#Mann=11,-1,0
  4397.9    0.12       0  4736.3    0.07       0  4767.2    0.05       0
  4771.2    0.07       0  4892.8     0.1       0  5106.9   0.035       0
  5201.4    0.07       0  5486.8   0.035       0  5588.4    0.07       0
  5689.9    0.05       0  5919.9    0.07       0
Bank Sta=4767.2,4771.2
Exp/Cntr=0.3,0.1

Type RM Length L Ch R = 1,1925,543,543,543
BEGIN DESCRIPTION:
X19008
END DESCRIPTION:
XS GIS Cut Line= 3
      2203980.07     13777012.45      2204672.73     13777090.57
      2205308.15     13776673.90
#Sta/Elev= 30
  4450.6  748.69  4519.5  748.18  4546.1  746.47  4596.5  745.60  4626.6  743.21
  4666.9  742.93  4694.3  740.39  4727.3  740.49  4757.5  737.83  4789.2  737.32
  4827.9  735.03  4888.3  733.43  4906.4  731.06  4906.7  730.56  4910.4  731.06
  4928.5  732.83  4971.0  733.26  5009.1  732.66  5029.2  733.80  5072.2  732.99
  5119.7  733.89  5161.6  733.40  5218.9  733.93  5457.0  737.33  5503.1  737.32
  5607.7  739.00  5778.3  739.74  5829.1  740.10  5894.0  741.47  5907.5  741.81
#Mann=9,-1,0
  4450.6    0.12       0  4906.4    0.05       0  4910.4    0.12       0
  4971.0     0.1       0  5072.2   0.035       0  5503.1    0.07       0
  5778.3   0.035       0  5829.1    0.07       0  5894.0    0.05       0
Bank Sta=4906.4,4910.4
Exp/Cntr=0.3,0.1

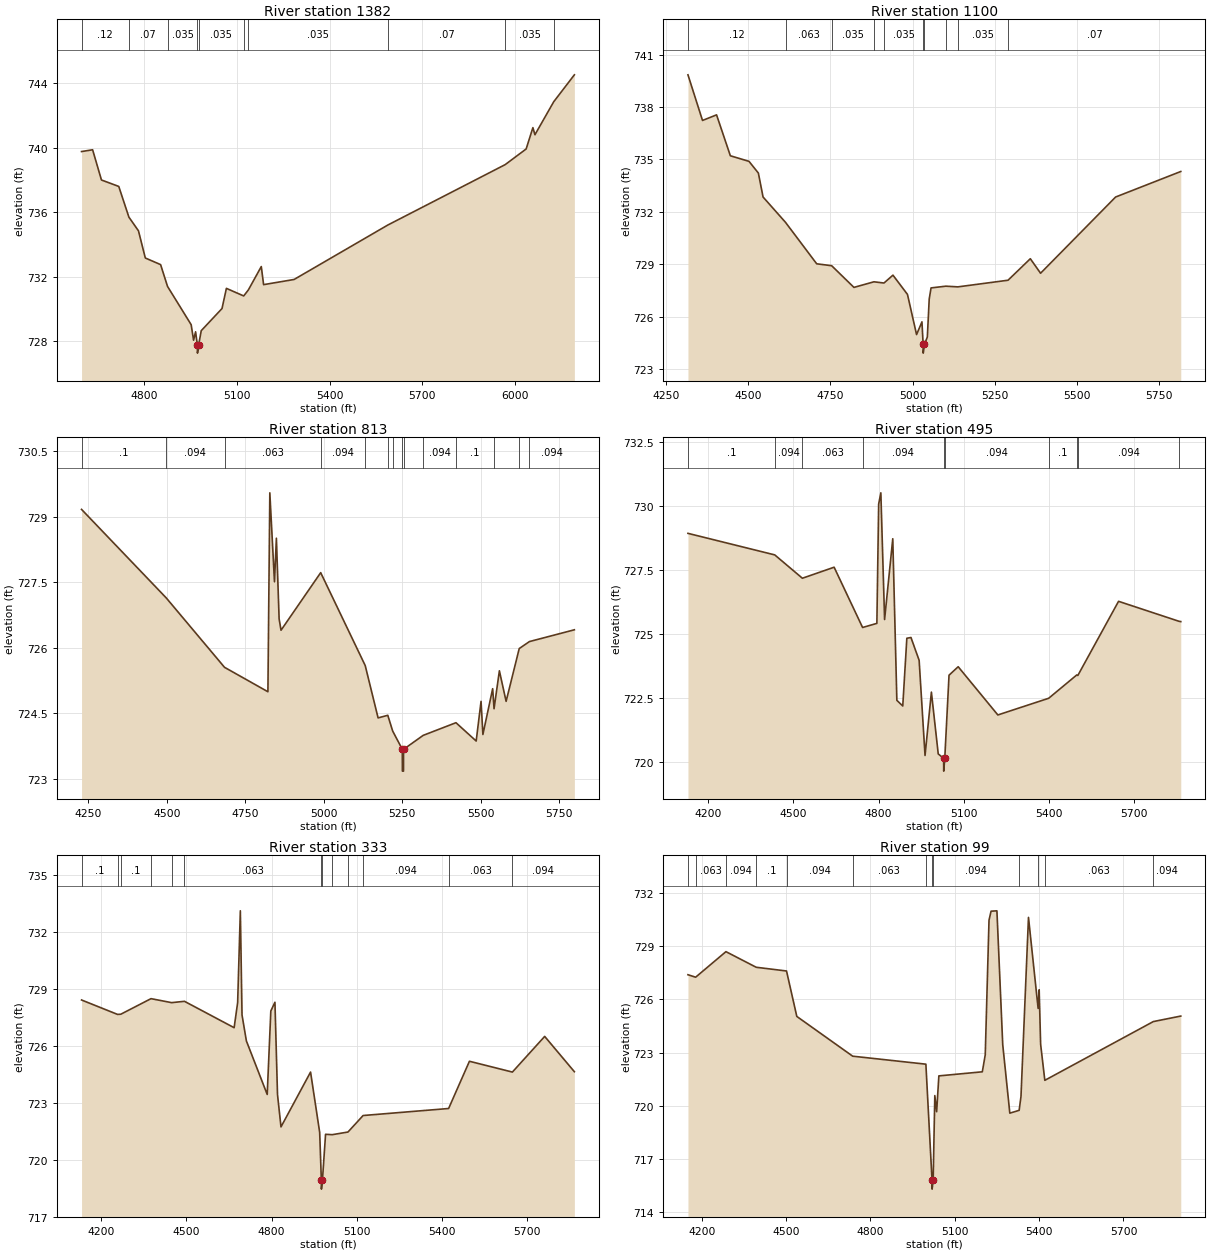
Type RM Length L Ch R = 1,1382,282,282,282
BEGIN DESCRIPTION:
Dry Comal Creek Tributary 28 3.0
END DESCRIPTION:
XS GIS Cut Line= 3
      2204175.00     13777225.00      2204475.00     13777475.00
      2205375.02     13776674.98
#Sta/Elev= 30
  4597.6  739.75  4633.4  739.86  4662.0  737.99  4718.0  737.59  4750.8  735.69
  4781.8  734.84  4803.9  733.16  4853.4  732.75  4875.8  731.40  4952.3  729.03
  4960.1  728.07  4966.6  728.59  4972.4  727.77  4972.7  727.27  4976.4  727.77
  4984.9  728.66  5052.1  730.03  5066.3  731.28  5122.3  730.81  5137.3  731.18
  5179.2  732.63  5186.7  731.51  5285.4  731.83  5588.6  735.20  5968.4  738.94
  6036.3  739.91  6058.1  741.23  6064.7  740.79  6125.4  742.83  6192.3  744.50
#Mann=10,-1,0
  4597.6    0.12       0  4750.8    0.07       0  4875.8   0.035       0
  4972.4   0.035       0  4976.4   0.035       0  5122.3    0.07       0
  5137.3   0.035       0  5588.6    0.07       0  5968.4   0.035       0
  6125.4    0.05       0
Bank Sta=4972.4,4976.4
Exp/Cntr=0.3,0.1

Type RM Length L Ch R = 1,1100,287,287,287
BEGIN DESCRIPTION:
X19007
END DESCRIPTION:
XS GIS Cut Line= 4
      2204000.85     13777246.81      2204334.19     13777637.44
      2204662.32     13777809.32      2205256.03     13777642.66
#Sta/Elev= 30
  4316.2  739.84  4360.5  737.23  4403.3  737.55  4445.3  735.21  4502.1  734.89
  4530.6  734.22  4544.9  732.85  4613.3  731.40  4708.2  729.03  4753.8  728.92
  4821.6  727.68  4882.5  728.00  4913.0  727.93  4940.4  728.38  4984.6  727.28
  5012.3  724.98  5028.7  725.71  5032.3  724.42  5032.6  723.92  5036.3  724.42
  5045.1  724.84  5050.8  727.01  5056.4  727.65  5101.4  727.75  5138.1  727.71
  5290.8  728.09  5358.7  729.32  5389.9  728.49  5618.4  732.85  5816.8  734.31
#Mann=10,-1,0
  4316.2    0.12       0  4613.3   0.063       0  4753.8   0.035       0
  4882.5    0.07       0  4913.0   0.035       0  5032.3   0.035       0
  5036.3   0.035       0  5101.4    0.07       0  5138.1   0.035       0
  5290.8    0.07       0
Bank Sta=5032.3,5036.3
Exp/Cntr=0.3,0.1

Type RM Length L Ch R = 1,813,318,318,318
BEGIN DESCRIPTION:
Dry Comal Creek Tributary 28 2.0
END DESCRIPTION:
XS GIS Cut Line= 4
      2203763.92     13777511.81      2204198.78     13777809.32
      2204552.94     13778059.32      2205075.36     13778372.49
#Sta/Elev= 30
  4228.3  729.17  4498.1  727.14  4683.6  725.55  4821.8  724.99  4827.9  729.55
  4842.7  727.51  4848.8  728.51  4857.5  726.66  4863.6  726.40  4989.9  727.72
  5131.7  725.59  5172.7  724.39  5203.6  724.45  5219.1  724.09  5249.8  723.67
  5250.1  723.17  5253.6  723.17  5253.8  723.67  5316.4  723.99  5420.7  724.28
  5485.1  723.86  5500.6  724.77  5506.5  724.01  5537.6  725.06  5542.0  724.60
  5559.0  725.47  5580.4  724.77  5622.2  725.98  5654.7  726.14  5797.8  726.41
#Mann=14,-1,0
  4228.3     0.1       0  4498.1   0.094       0  4683.6   0.063       0
  4989.9   0.094       0  5131.7   0.063       0  5203.6   0.035       0
  5219.1   0.063       0  5249.8    0.05       0  5253.8   0.063       0
  5316.4   0.094       0  5420.7     0.1       0  5542.0   0.094       0
  5622.2     0.1       0  5654.7   0.094       0
Bank Sta=5249.8,5253.8
Exp/Cntr=0.3,0.1

Type RM Length L Ch R = 1,495,162,162,162
BEGIN DESCRIPTION:
Dry Comal Creek Tributary 28 1.0
END DESCRIPTION:
XS GIS Cut Line= 3
      2203732.15     13777543.55      2204275.00     13778225.00
      2205099.56     13778485.92
#Sta/Elev= 30
  4128.4  728.93  4434.2  728.09  4531.5  727.18  4643.3  727.61  4743.6  725.26
  4793.9  725.42  4800.2  730.07  4807.9  730.51  4821.1  725.57  4849.9  728.72
  4864.3  722.42  4885.1  722.20  4899.5  724.84  4914.0  724.87  4942.8  723.98
  4963.6  720.27  4986.0  722.74  5010.1  720.33  5029.1  720.16  5029.4  719.66
  5033.1  720.16  5048.1  723.40  5080.4  723.73  5220.1  721.85  5399.1  722.50
  5498.2  723.41  5501.9  723.39  5645.3  726.28  5858.7  725.50  5864.5  725.49
#Mann=10,-1,0
  4128.4     0.1       0  4434.2   0.094       0  4531.5   0.063       0
  4743.6   0.094       0  5029.1    0.05       0  5033.1   0.094       0
  5399.1     0.1       0  5498.2   0.063       0  5501.9   0.094       0
  5858.7   0.063       0
Bank Sta=5029.1,5033.1
Exp/Cntr=0.3,0.1

Type RM Length L Ch R = 1,333,234,234,234
BEGIN DESCRIPTION:
X19006
END DESCRIPTION:
XS GIS Cut Line= 3
      2203714.38     13777647.82      2204141.48     13778340.57
      2205028.48     13778588.77
#Sta/Elev= 30
  4131.1  728.42  4257.8  727.66  4269.3  727.67  4375.6  728.49  4448.2  728.28
  4493.4  728.35  4668.2  726.96  4680.6  728.28  4690.1  733.12  4696.0  727.63
  4711.4  726.26  4784.7  723.44  4797.4  727.84  4811.9  728.30  4820.9  723.44
  4833.2  721.73  4937.3  724.62  4969.4  721.44  4975.2  718.95  4975.5  718.45
  4979.2  718.95  4990.1  721.34  5013.6  721.32  5069.0  721.46  5122.3  722.33
  5423.3  722.70  5496.6  725.19  5647.8  724.62  5761.5  726.50  5866.0  724.64
#Mann=13,-1,0
  4131.1     0.1       0  4257.8   0.094       0  4269.3     0.1       0
  4375.6   0.094       0  4448.2     0.1       0  4493.4   0.063       0
  4975.2    0.05       0  4979.2   0.063       0  5013.6   0.094       0
  5069.0   0.063       0  5122.3   0.094       0  5423.3   0.063       0
  5647.8   0.094       0
Bank Sta=4975.2,4979.2
Exp/Cntr=0.3,0.1

Type RM Length L Ch R = 1,99,0,0,0
BEGIN DESCRIPTION:
X19005
END DESCRIPTION:
XS GIS Cut Line= 5
      2203641.48     13777824.93      2203870.65     13778382.23
      2204131.07     13778595.78      2204396.69     13778668.69
      2204917.56     13778533.27
#Sta/Elev= 30
  4150.9  727.39  4178.2  727.25  4286.0  728.69  4393.7  727.81  4501.5  727.60
  4538.1  725.04  4736.9  722.80  4997.2  722.35  5019.1  715.81  5019.4  715.31
  5023.1  715.81  5029.0  720.58  5035.5  719.67  5043.4  721.69  5198.0  721.92
  5208.4  722.88  5221.8  730.46  5229.1  730.97  5249.9  730.99  5270.6  723.45
  5295.8  719.59  5329.0  719.75  5335.5  720.53  5362.2  730.62  5396.5  725.49
  5400.2  726.54  5405.4  723.47  5420.3  721.44  5806.3  724.75  5903.9  725.06
#Mann=13,-1,0
  4150.9   0.094       0  4178.2   0.063       0  4286.0   0.094       0
  4393.7     0.1       0  4501.5   0.094       0  4736.9   0.063       0
  4997.2   0.094       0  5019.1    0.05       0  5023.1   0.094       0
  5329.0   0.063       0  5396.5   0.094       0  5420.3   0.063       0
  5806.3   0.094       0
Bank Sta=5019.1,5023.1
Exp/Cntr=0.3,0.1

Chan Stop Cuts=-1