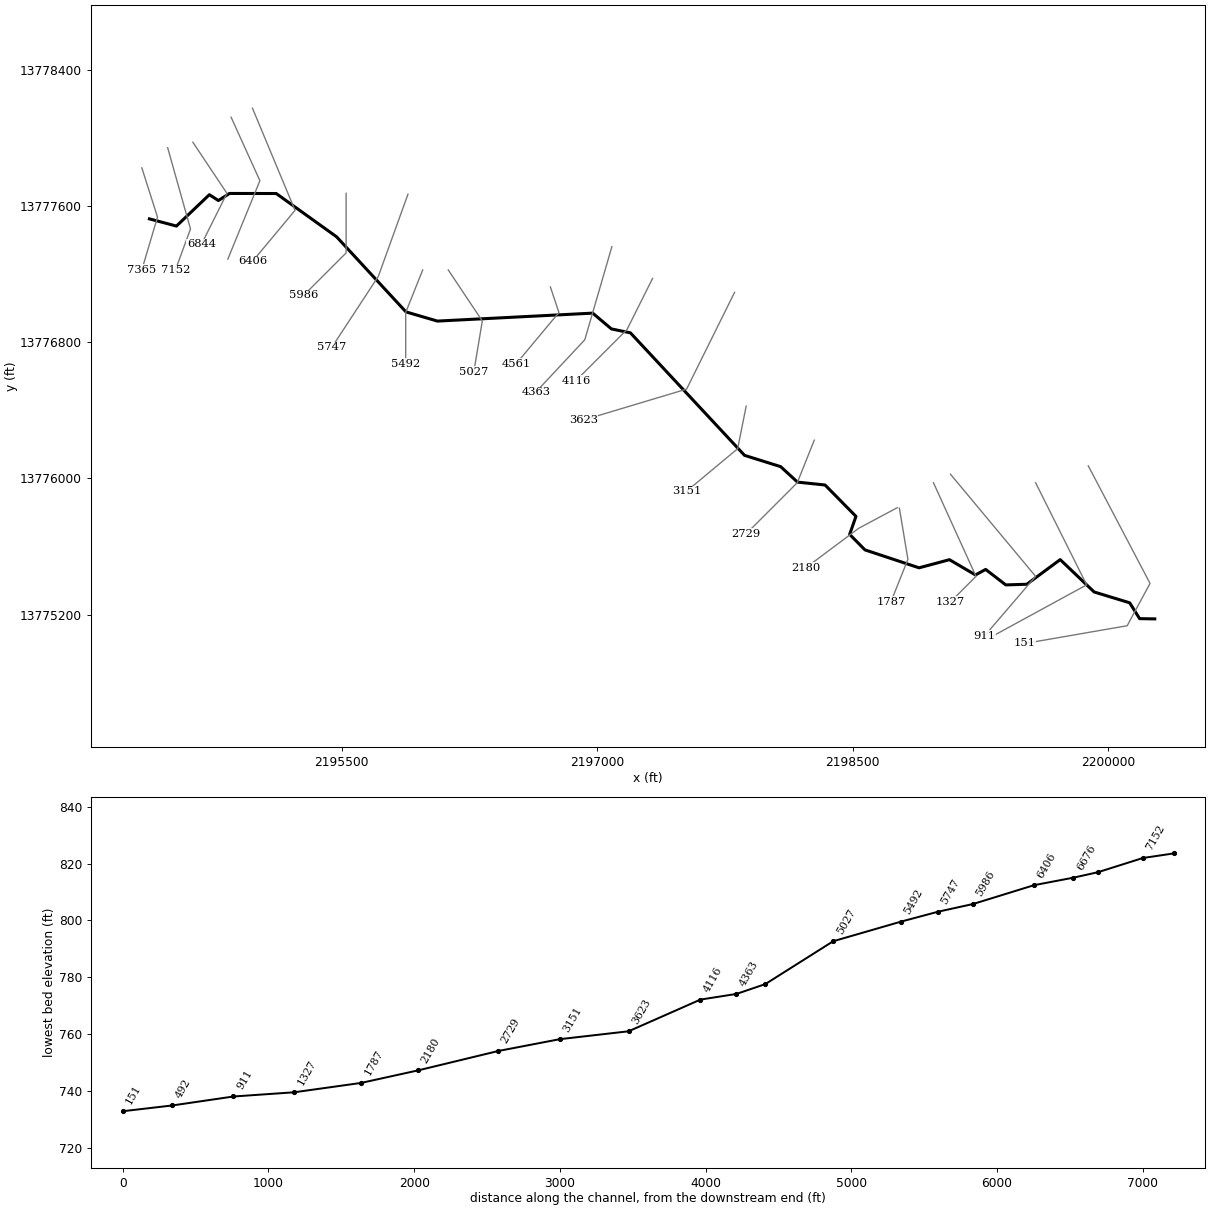
--- Dry Comal Creek Tributary 30.prj (project) ---

Proj Title=Dry Comal Creek Tributary 30 Base Level Engineering
Current Plan=p01
Default Exp/Contr=0.3,0.1
English Units
Geom File=g01
Flow File=f01
Plan File=p01
BEGIN DESCRIPTION:
Dry Comal Creek Tributary 30
END DESCRIPTION:

--- Dry Comal Creek Tributary 30.p01 (plan) ---

Plan Title=Multiple Run
Short Identifier=Multiple
Geom File=g01
Flow File=f01
Subcritical Flow
K Sum by GR= 0
Std Step Tol= 0.01
Critical Tol= 0.01
Num of Std Step Trials= 20
Max Error Tol= 0.3
Flow Tol Ratio= 0.001
Split Flow NTrial= 30
Split Flow Tol= 0.02
Split Flow Ratio= 0.02
Log Output Level= 0
Friction Slope Method= 1
Unsteady Friction Slope Method= 2
Unsteady Bridges Friction Slope Method= 1
Parabolic Critical Depth
Global Vel Dist=  1 , 1 , 1
Global Log Level= 0
CheckData=True
Encroach Param= -1, 0, 0, 0
BEGIN DESCRIPTION:
Multiple Run
END DESCRIPTION:

--- Dry Comal Creek Tributary 30.f01 (steady flow) ---

Flow Title=Multiple
Number of Profiles=7
Profile Names=10-year,25-year,50-year,1pct_min,100-year,1pct_plu,500-year
River Rch & RM= Dry Comal Creek ,Reach-1,7365
     623    1023    1390     918    1832    3654    3141
River Rch & RM= Dry Comal Creek ,Reach-1,5747
     913    1528    2104    1405    2803    5592    4919
Boundary for River Rch & Prof#=Dry Comal Creek ,Reach-1,1
Up Type=0
Dn Type=3
Dn Slope=0.005
Boundary for River Rch & Prof#=Dry Comal Creek ,Reach-1,2
Up Type=0
Dn Type=3
Dn Slope=0.005
Boundary for River Rch & Prof#=Dry Comal Creek ,Reach-1,3
Up Type=0
Dn Type=3
Dn Slope=0.005
Boundary for River Rch & Prof#=Dry Comal Creek ,Reach-1,4
Up Type=0
Dn Type=3
Dn Slope=0.005
Boundary for River Rch & Prof#=Dry Comal Creek ,Reach-1,5
Up Type=0
Dn Type=3
Dn Slope=0.005
Boundary for River Rch & Prof#=Dry Comal Creek ,Reach-1,6
Up Type=0
Dn Type=3
Dn Slope=0.005
Boundary for River Rch & Prof#=Dry Comal Creek ,Reach-1,7
Up Type=0
Dn Type=3
Dn Slope=0.005

--- Dry Comal Creek Tributary 30.g01 (geometry) ---

Geom Title=Existing Conditions

River Reach=Dry Comal Creek ,Reach-1
Reach XY= 30
      2194369.49     13777525.00      2194528.42     13777482.76
      2194721.66     13777667.01      2194774.90     13777632.81
      2194840.16     13777674.35      2195114.56     13777673.95
      2195469.38     13777419.38      2195876.50     13776978.61
      2196061.18     13776924.56      2196973.47     13776971.26
      2197083.48     13776878.50      2197195.14     13776855.37
      2197865.32     13776135.76      2198077.42     13776069.46
      2198176.47     13775978.56      2198338.32     13775961.63
      2198519.88     13775777.29      2198482.81     13775671.58
      2198572.54     13775580.52      2198890.39     13775475.09
      2199069.03     13775522.86      2199221.77     13775433.25
      2199281.66     13775465.68      2199399.89     13775374.69
      2199523.53     13775378.53      2199719.53     13775523.36
      2199918.95     13775333.16      2200127.66     13775269.55
      2200185.91     13775176.58      2200275.00     13775175.00

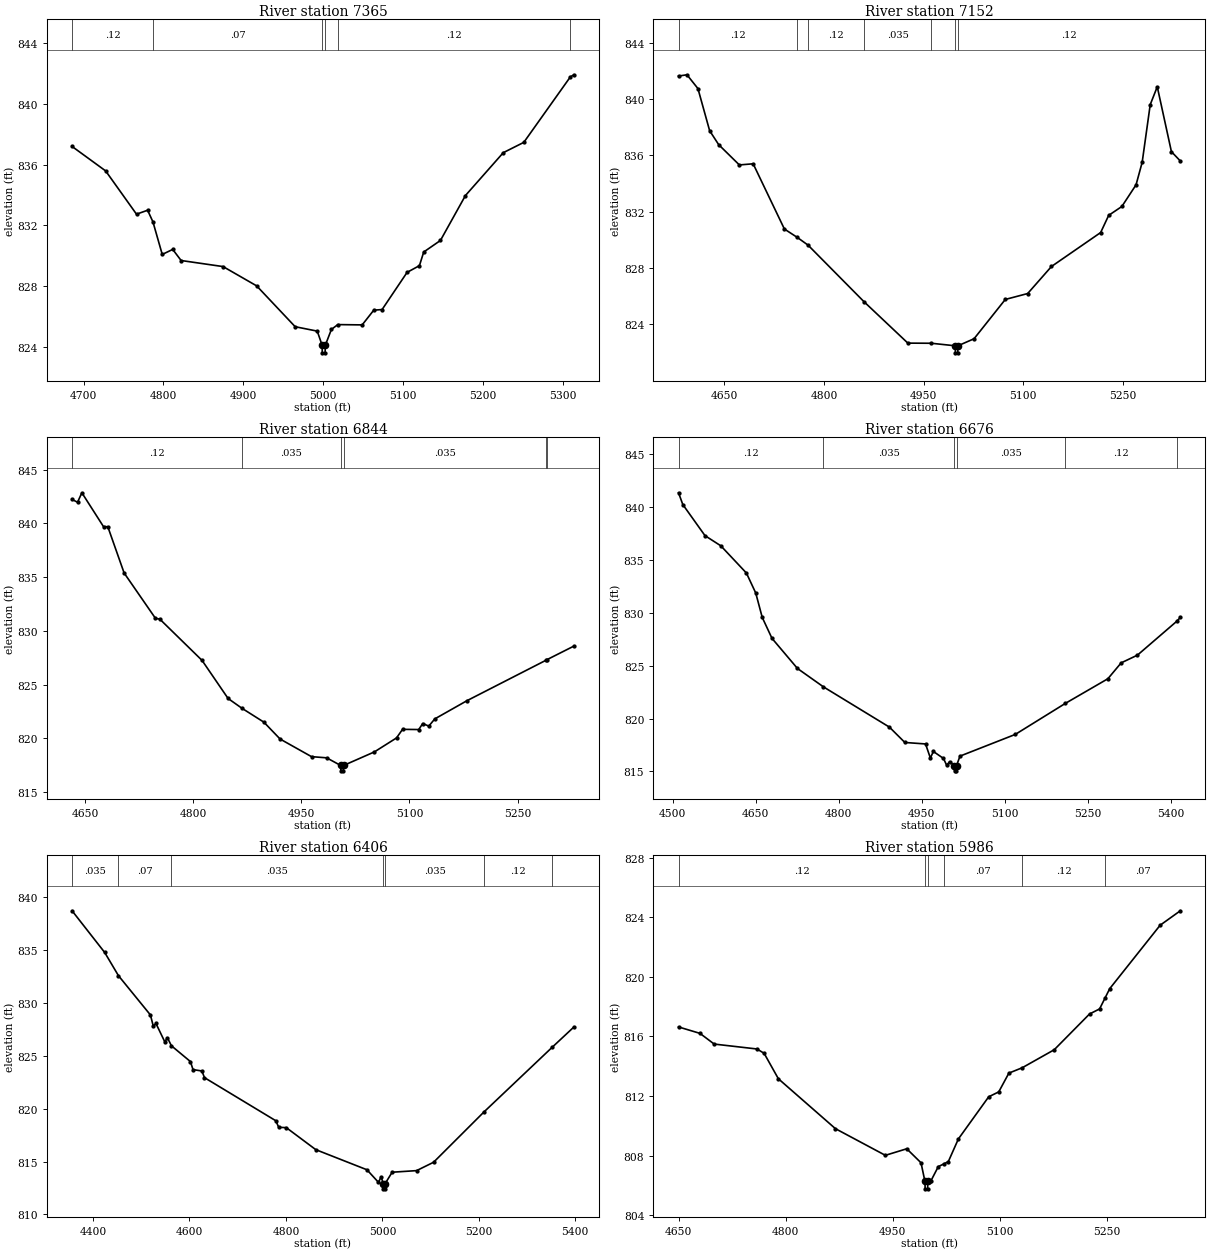
Type RM Length L Ch R = 1,7365,213,213,213
BEGIN DESCRIPTION:
Dry Comal Creek Tributary 30 16.0
END DESCRIPTION:
XS GIS Cut Line= 3
      2194325.00     13777825.00      2194417.15     13777535.57
      2194325.00     13777225.00
#Sta/Elev= 30
  4685.7  837.19  4727.7  835.58  4766.3  832.73  4780.2  832.99  4786.9  832.22
  4798.5  830.08  4811.6  830.41  4822.1  829.68  4874.6  829.28  4916.6  828.01
  4964.8  825.32  4992.4  825.03  4998.5  824.10  4998.7  823.60  5002.2  823.60
  5002.5  824.10  5010.1  825.14  5018.1  825.46  5048.6  825.44  5063.1  826.41
  5073.5  826.45  5104.8  828.90  5120.2  829.34  5125.6  830.24  5146.5  831.00
  5177.8  833.96  5225.1  836.78  5250.8  837.46  5309.0  841.77  5313.4  841.91
#Mann=6,-1,0
  4685.7    0.12       0  4786.9    0.07       0  4998.5    0.05       0
  5002.5    0.07       0  5018.1    0.12       0  5309.0   0.035       0
Bank Sta=4998.5,5002.5
Exp/Cntr=0.3,0.1

Type RM Length L Ch R = 1,7152,308,308,308
BEGIN DESCRIPTION:
X19016
END DESCRIPTION:
XS GIS Cut Line= 3
      2194476.80     13777943.12      2194610.99     13777465.99
      2194521.53     13777222.44
#Sta/Elev= 30
  4581.2  841.63  4593.9  841.72  4610.4  840.74  4628.0  837.75  4641.6  836.76
  4672.7  835.32  4693.5  835.40  4740.5  830.77  4759.7  830.18  4776.0  829.63
  4860.3  825.61  4926.3  822.67  4961.7  822.66  4997.6  822.48  4997.9  821.98
  5001.4  821.98  5001.6  822.48  5025.9  822.98  5072.9  825.77  5106.6  826.19
  5142.4  828.11  5216.4  830.52  5228.5  831.74  5248.3  832.37  5269.7  833.91
  5278.9  835.51  5291.0  839.60  5301.6  840.87  5322.9  836.26  5336.3  835.60
#Mann=7,-1,0
  4581.2    0.12       0  4759.7    0.07       0  4776.0    0.12       0
  4860.3   0.035       0  4961.7    0.12       0  4997.6    0.05       0
  5001.6    0.12       0
Bank Sta=4997.6,5001.6
Exp/Cntr=0.3,0.1

Type RM Length L Ch R = 1,6844,168,168,168
BEGIN DESCRIPTION:
Dry Comal Creek Tributary 30 15.0
END DESCRIPTION:
XS GIS Cut Line= 3
      2194624.98     13777975.03      2194825.00     13777675.00
      2194675.00     13777375.01
#Sta/Elev= 30
  4632.1  842.22  4639.7  841.96  4645.7  842.84  4675.7  839.69  4681.7  839.68
  4704.3  835.38  4747.8  831.16  4753.8  831.09  4812.4  827.25  4848.5  823.71
  4867.7  822.80  4898.1  821.51  4920.6  819.94  4964.2  818.30  4985.2  818.19
  5004.7  817.48  5004.9  816.98  5008.4  816.98  5008.7  817.48  5051.4  818.74
  5082.1  820.04  5090.5  820.84  5112.9  820.82  5118.5  821.38  5126.9  821.14
  5135.2  821.81  5180.0  823.51  5289.9  827.28  5290.5  827.31  5328.1  828.58
#Mann=6,-1,0
  4632.1    0.12       0  4867.7   0.035       0  5004.7   0.035       0
  5008.7   0.035       0  5289.9    0.12       0  5290.5   0.035       0
Bank Sta=5004.7,5008.7
Exp/Cntr=0.3,0.1

Type RM Length L Ch R = 1,6676,270,270,270
BEGIN DESCRIPTION:
X19017
END DESCRIPTION:
XS GIS Cut Line= 3
      2194849.57     13778122.05      2195018.55     13777749.29
      2194830.44     13777288.91
#Sta/Elev= 30
  4510.5  841.33  4518.2  840.22  4558.3  837.28  4586.9  836.32  4633.1  833.75
  4650.0  831.86  4661.7  829.56  4679.3  827.58  4725.4  824.73  4772.4  822.99
  4891.5  819.19  4919.4  817.74  4956.8  817.60  4965.5  816.27  4970.9  816.89
  4989.2  816.23  4994.9  815.59  5000.3  815.93  5008.8  815.56  5009.1  815.06
  5012.6  815.06  5012.8  815.56  5019.0  816.45  5118.9  818.50  5209.3  821.43
  5286.2  823.76  5310.2  825.26  5339.6  825.99  5411.1  829.21  5417.1  829.56
#Mann=6,-1,0
  4510.5    0.12       0  4772.4   0.035       0  5008.8   0.035       0
  5012.8   0.035       0  5209.3    0.12       0  5411.1   0.035       0
Bank Sta=5008.8,5012.8
Exp/Cntr=0.3,0.1

Type RM Length L Ch R = 1,6406,420,420,420
BEGIN DESCRIPTION:
Dry Comal Creek Tributary 30 14.0
END DESCRIPTION:
XS GIS Cut Line= 3
      2194975.00     13778175.01      2195225.00     13777575.00
      2194975.01     13777275.01
#Sta/Elev= 30
  4356.5  838.68  4424.2  834.74  4452.7  832.55  4519.0  828.84  4525.0  827.77
  4530.4  828.04  4548.8  826.30  4554.2  826.69  4562.5  825.93  4601.9  824.44
  4607.3  823.68  4625.7  823.55  4631.1  822.92  4779.0  818.85  4785.0  818.23
  4800.7  818.20  4861.9  816.12  4968.0  814.22  4991.9  813.03  4997.3  813.56
  5001.8  812.92  5002.0  812.42  5005.5  812.42  5005.8  812.92  5020.2  813.99
  5070.9  814.14  5106.1  814.93  5210.8  819.69  5351.6  825.77  5397.0  827.70
#Mann=7,-1,0
  4356.5   0.035       0  4452.7    0.07       0  4562.5   0.035       0
  5001.8   0.035       0  5005.8   0.035       0  5210.8    0.12       0
  5351.6    0.07       0
Bank Sta=5001.8,5005.8
Exp/Cntr=0.3,0.1

Type RM Length L Ch R = 1,5986,239,239,239
BEGIN DESCRIPTION:
Dry Comal Creek Tributary 30 13.0
END DESCRIPTION:
XS GIS Cut Line= 3
      2195525.00     13777675.01      2195525.00     13777325.00
      2195274.98     13777074.98
#Sta/Elev= 30
  4649.8  816.64  4679.8  816.21  4699.8  815.49  4759.8  815.16  4769.8  814.87
  4789.8  813.16  4869.8  809.81  4939.8  808.02  4969.8  808.46  4989.8  807.52
  4995.3  806.27  4995.6  805.77  4999.1  805.77  4999.3  806.27  5003.3  806.27
  5014.0  807.26  5021.6  807.44  5028.1  807.60  5042.2  809.12  5084.7  811.95
  5098.8  812.28  5113.0  813.54  5131.7  813.90  5176.6  815.11  5226.1  817.51
  5240.2  817.85  5247.6  818.56  5254.4  819.21  5325.1  823.47  5353.4  824.44
#Mann=6,-1,0
  4649.8    0.12       0  4995.3    0.05       0  4999.3    0.12       0
  5021.6    0.07       0  5131.7    0.12       0  5247.6    0.07       0
Bank Sta=4995.3,4999.3
Exp/Cntr=0.3,0.1

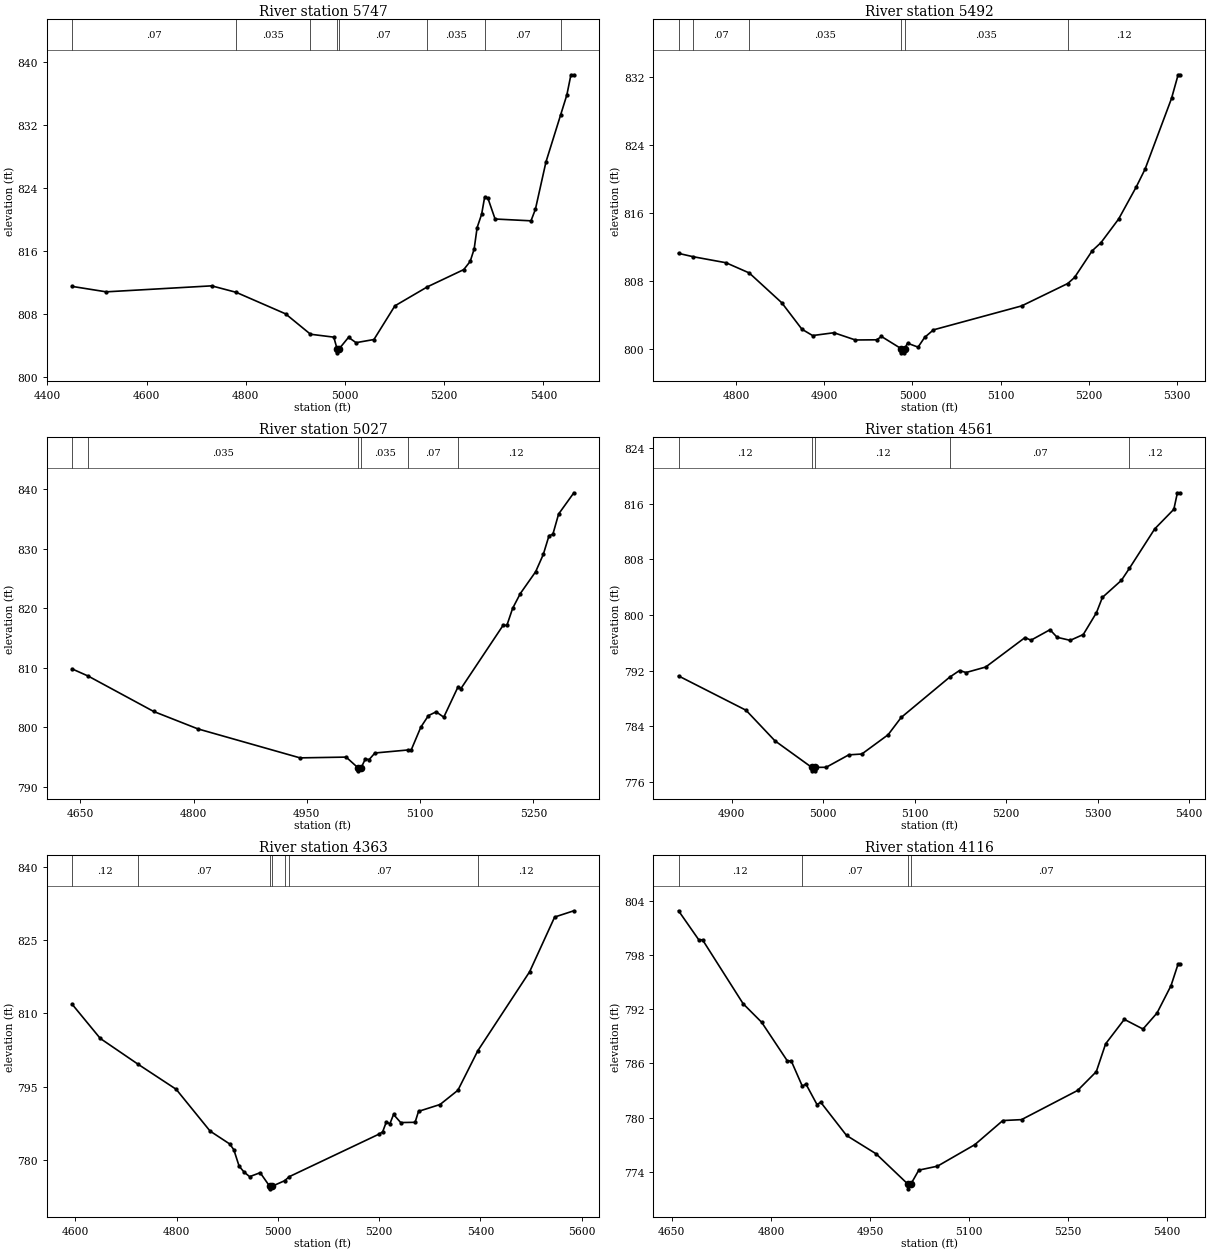
Type RM Length L Ch R = 1,5747,255,255,255
BEGIN DESCRIPTION:
X19015
END DESCRIPTION:
XS GIS Cut Line= 3
      2195888.32     13777669.73      2195714.38     13777187.66
      2195441.03     13776770.18
#Sta/Elev= 30
  4449.9  811.50  4518.7  810.81  4731.3  811.57  4780.6  810.75  4880.2  808.02
  4930.5  805.43  4977.5  805.06  4984.1  803.57  4984.3  803.07  4988.1  803.57
  5007.2  805.04  5022.3  804.36  5058.4  804.76  5100.6  809.03  5166.3  811.45
  5239.4  813.63  5252.4  814.67  5260.4  816.24  5266.4  818.96  5275.5  820.66
  5281.5  822.80  5288.3  822.66  5302.6  820.05  5375.0  819.82  5383.9  821.29
  5405.2  827.30  5434.8  833.27  5447.3  835.80  5455.5  838.35  5461.4  838.35
#Mann=8,-1,0
  4449.9    0.07       0  4780.6   0.035       0  4930.5    0.07       0
  4984.1    0.05       0  4988.1    0.07       0  5166.3   0.035       0
  5281.5    0.07       0  5434.8    0.12       0
Bank Sta=4984.1,4988.1
Exp/Cntr=0.3,0.1

Type RM Length L Ch R = 1,5492,465,465,465
BEGIN DESCRIPTION:
Dry Comal Creek Tributary 30 12.0
END DESCRIPTION:
XS GIS Cut Line= 3
      2195974.98     13777224.96      2195875.00     13776975.00
      2195875.00     13776675.01
#Sta/Elev= 30
  4734.7  811.25  4751.1  810.86  4788.5  810.15  4814.9  808.95  4851.8  805.45
  4874.7  802.34  4886.8  801.60  4911.0  801.93  4935.3  801.08  4959.5  801.10
  4964.9  801.49  4987.1  800.07  4987.4  799.57  4990.9  799.57  4991.1  800.07
  4994.5  800.70  5006.4  800.24  5013.9  801.39  5023.9  802.27  5123.9  805.08
  5176.2  807.71  5183.9  808.42  5203.9  811.55  5213.9  812.51  5233.9  815.28
  5253.9  819.05  5263.9  821.14  5293.9  829.44  5301.4  832.22  5303.9  832.22
#Mann=6,-1,0
  4734.7   0.035       0  4751.1    0.07       0  4814.9   0.035       0
  4987.1   0.035       0  4991.1   0.035       0  5176.2    0.12       0
Bank Sta=4987.1,4991.1
Exp/Cntr=0.3,0.1

Type RM Length L Ch R = 1,5027,466,466,466
BEGIN DESCRIPTION:
Dry Comal Creek Tributary 30 11.0
END DESCRIPTION:
XS GIS Cut Line= 3
      2196125.03     13777224.96      2196325.00     13776925.00
      2196275.01     13776625.05
#Sta/Elev= 30
  4639.1  809.81  4660.5  808.60  4747.2  802.65  4805.8  799.72  4941.0  794.85
  5002.1  794.98  5017.9  793.17  5018.1  792.67  5021.9  793.17  5027.5  794.66
  5032.6  794.57  5040.2  795.67  5084.2  796.18  5088.3  796.19  5101.0  800.01
  5111.1  801.96  5121.3  802.59  5131.4  801.69  5150.4  806.82  5154.2  806.51
  5210.0  817.14  5215.0  817.13  5222.6  819.99  5232.8  822.48  5253.1  826.15
  5263.2  829.05  5270.8  832.21  5275.9  832.44  5283.5  835.85  5303.7  839.42
#Mann=6,-1,0
  4639.1    0.07       0  4660.5   0.035       0  5017.9   0.035       0
  5021.9   0.035       0  5084.2    0.07       0  5150.4    0.12       0
Bank Sta=5017.9,5021.9
Exp/Cntr=0.3,0.1

Type RM Length L Ch R = 1,4561,198,198,198
BEGIN DESCRIPTION:
Dry Comal Creek Tributary 30 10.0
END DESCRIPTION:
XS GIS Cut Line= 3
      2196725.00     13777125.00      2196775.00     13776975.00
      2196525.02     13776675.02
#Sta/Elev= 30
  4841.9  791.23  4915.7  786.29  4947.3  781.89  4987.5  778.07  4987.7  777.57
  4991.2  777.57  4991.5  778.07  5003.3  778.08  5028.0  779.87  5042.3  779.99
  5071.0  782.76  5085.3  785.25  5138.2  791.04  5149.1  792.01  5156.2  791.72
  5177.7  792.51  5220.7  796.75  5227.2  796.37  5248.0  797.88  5255.8  796.79
  5270.1  796.35  5284.4  797.19  5298.8  800.33  5305.3  802.53  5326.1  804.99
  5334.9  806.73  5362.5  812.39  5383.4  815.21  5387.3  817.59  5390.5  817.59
#Mann=5,-1,0
  4841.9    0.12       0  4987.5    0.05       0  4991.5    0.12       0
  5138.2    0.07       0  5334.9    0.12       0
Bank Sta=4987.5,4991.5
Exp/Cntr=0.3,0.1

Type RM Length L Ch R = 1,4363,247,247,247
BEGIN DESCRIPTION:
X19014
END DESCRIPTION:
XS GIS Cut Line= 3
      2197086.14     13777361.57      2196927.11     13776814.89
      2196639.39     13776507.33
#Sta/Elev= 30
  4593.8  811.86  4649.5  804.85  4724.4  799.56  4799.3  794.46  4866.3  785.91
  4905.0  783.28  4913.1  782.10  4923.5  778.76  4933.3  777.54  4944.3  776.60
  4965.1  777.41  4984.0  774.61  4984.2  774.11  4988.0  774.61  5013.2  775.76
  5022.8  776.61  5200.0  785.31  5206.9  785.77  5214.2  787.81  5221.0  787.38
  5228.4  789.31  5242.5  787.66  5270.9  787.71  5277.7  789.95  5320.2  791.35
  5355.4  794.26  5394.6  802.32  5497.0  818.49  5546.4  829.67  5584.3  830.95
#Mann=7,-1,0
  4593.8    0.12       0  4724.4    0.07       0  4984.0    0.05       0
  4988.0    0.07       0  5013.2    0.12       0  5022.8    0.07       0
  5394.6    0.12       0
Bank Sta=4984,4988
Exp/Cntr=0.3,0.1

Type RM Length L Ch R = 1,4116,493,493,493
BEGIN DESCRIPTION:
Dry Comal Creek Tributary 30 9.0
END DESCRIPTION:
XS GIS Cut Line= 3
      2197324.99     13777174.98      2197175.00     13776875.00
      2196875.03     13776575.03
#Sta/Elev= 30
  4660.2  802.90  4690.9  799.68  4696.5  799.69  4758.0  792.61  4786.0  790.56
  4825.1  786.26  4830.7  786.30  4847.6  783.48  4853.0  783.73  4869.8  781.45
  4875.4  781.71  4914.5  778.03  4959.2  776.00  5007.7  772.62  5008.0  772.12
  5011.7  772.62  5023.9  774.19  5052.2  774.63  5108.7  777.01  5151.1  779.68
  5179.4  779.78  5264.3  783.01  5292.6  785.09  5306.7  788.17  5335.0  790.88
  5363.3  789.81  5384.5  791.58  5405.7  794.61  5416.3  796.98  5419.8  796.98
#Mann=4,-1,0
  4660.2    0.12       0  4847.6    0.07       0  5007.7    0.05       0
  5011.7    0.07       0
Bank Sta=5007.7,5011.7
Exp/Cntr=0.3,0.1

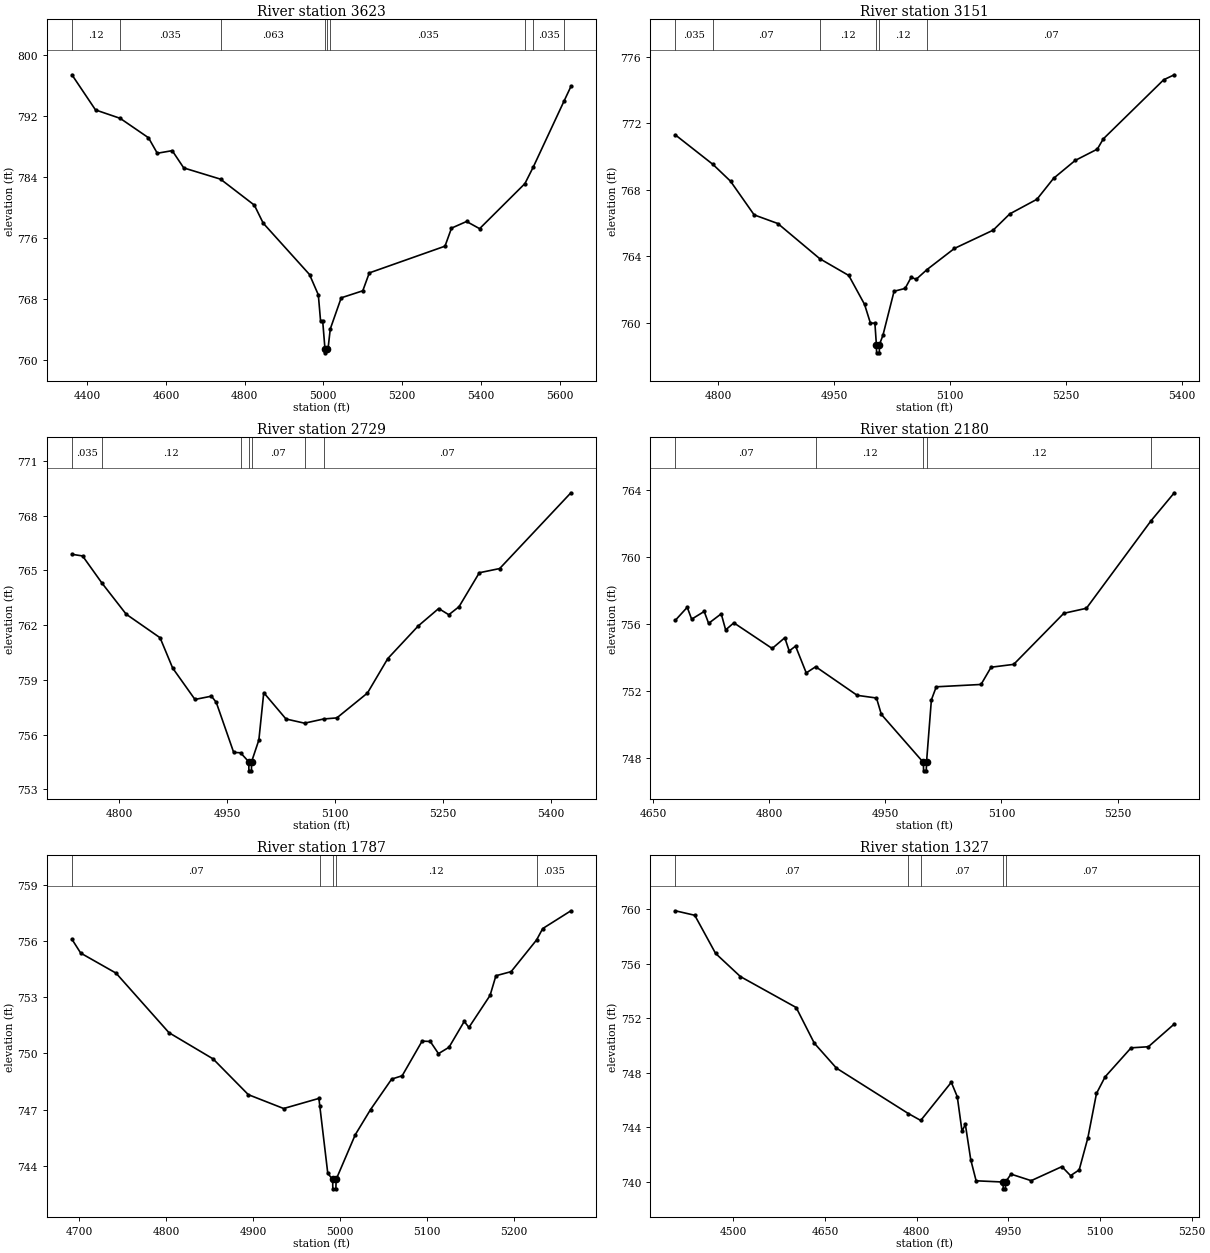
Type RM Length L Ch R = 1,3623,472,472,472
BEGIN DESCRIPTION:
Dry Comal Creek Tributary 30 8.0
END DESCRIPTION:
XS GIS Cut Line= 3
      2197806.83     13777093.20      2197525.00     13776525.00
      2196918.63     13776343.16
#Sta/Elev= 30
  4361.4  797.35  4421.3  792.75  4483.9  791.65  4555.8  789.11  4578.2  787.08
  4616.1  787.42  4645.4  785.16  4738.8  783.69  4824.7  780.29  4847.2  777.93
  4964.8  771.21  4987.2  768.55  4992.9  765.12  4998.3  765.12  5004.1  761.46
  5004.3  760.96  5008.1  761.46  5012.2  761.65  5017.5  764.08  5045.3  768.16
  5100.1  769.08  5116.6  771.42  5308.9  774.92  5325.4  777.28  5363.7  778.15
  5396.8  777.21  5511.9  783.11  5533.4  785.31  5610.9  793.87  5628.7  795.82
#Mann=9,-1,0
  4361.4    0.12       0  4483.9   0.035       0  4738.8   0.063       0
  5004.1    0.05       0  5008.1   0.063       0  5017.5   0.035       0
  5511.9    0.12       0  5533.4   0.035       0  5610.9    0.12       0
Bank Sta=5004.1,5008.1
Exp/Cntr=0.3,0.1

Type RM Length L Ch R = 1,3151,422,422,422
BEGIN DESCRIPTION:
Dry Comal Creek Tributary 30 7.0
END DESCRIPTION:
XS GIS Cut Line= 3
      2197875.00     13776425.02      2197825.00     13776175.00
      2197524.99     13775924.99
#Sta/Elev= 30
  4744.8  771.31  4793.5  769.53  4816.2  768.52  4846.8  766.49  4877.4  765.97
  4931.7  763.85  4969.2  762.84  4989.6  761.10  4997.2  759.97  5003.0  759.97
  5004.9  758.68  5005.2  758.18  5008.7  758.18  5008.9  758.68  5013.4  759.24
  5027.8  761.89  5042.1  762.06  5049.9  762.73  5056.4  762.61  5070.5  763.20
  5105.9  764.47  5156.0  765.57  5177.5  766.55  5212.6  767.43  5234.1  768.69
  5262.1  769.77  5290.7  770.45  5298.5  771.07  5376.6  774.63  5390.3  774.93
#Mann=6,-1,0
  4744.8   0.035       0  4793.5    0.07       0  4931.7    0.12       0
  5004.9    0.05       0  5008.9    0.12       0  5070.5    0.07       0
Bank Sta=5004.9,5008.9
Exp/Cntr=0.3,0.1

Type RM Length L Ch R = 1,2729,549,549,549
BEGIN DESCRIPTION:
Dry Comal Creek Tributary 30 6.0
END DESCRIPTION:
XS GIS Cut Line= 3
      2198275.00     13776224.99      2198175.00     13775975.00
      2197875.01     13775675.01
#Sta/Elev= 30
  4734.6  765.88  4749.4  765.79  4776.4  764.30  4810.0  762.60  4857.1  761.31
  4874.6  759.65  4905.6  757.93  4928.5  758.11  4935.2  757.77  4959.4  755.03
  4968.9  755.01  4980.3  754.52  4980.6  754.02  4984.1  754.02  4984.3  754.52
  4994.4  755.71  5001.2  758.30  5032.1  756.86  5057.9  756.63  5084.4  756.86
  5102.8  756.92  5145.3  758.28  5173.6  760.17  5216.0  761.96  5244.3  762.91
  5258.4  762.57  5272.6  763.01  5300.8  764.87  5329.1  765.10  5428.1  769.25
#Mann=7,-1,0
  4734.6   0.035       0  4776.4    0.12       0  4968.9    0.07       0
  4980.3    0.05       0  4984.3    0.07       0  5057.9    0.12       0
  5084.4    0.07       0
Bank Sta=4980.3,4984.3
Exp/Cntr=0.3,0.1

Type RM Length L Ch R = 1,2180,393,393,393
BEGIN DESCRIPTION:
Dry Comal Creek Tributary 30 5.0
END DESCRIPTION:
XS GIS Cut Line= 3
      2198762.00     13775828.09      2198536.30     13775707.58
      2198225.03     13775475.03
#Sta/Elev= 30
  4678.9  756.20  4694.3  756.98  4700.0  756.27  4716.2  756.73  4721.9  756.02
  4738.2  756.59  4743.9  755.63  4754.5  756.05  4804.0  754.52  4820.3  755.16
  4826.0  754.37  4834.2  754.66  4848.0  753.06  4860.2  753.43  4913.8  751.72
  4938.7  751.56  4945.0  750.58  4999.3  747.71  4999.5  747.21  5003.0  747.21
  5003.3  747.71  5009.6  751.45  5015.9  752.23  5073.7  752.37  5086.7  753.40
  5115.9  753.57  5180.6  756.62  5209.8  756.92  5293.3  762.15  5323.3  763.82
#Mann=5,-1,0
  4678.9    0.07       0  4860.2    0.12       0  4999.3    0.05       0
  5003.3    0.12       0  5293.3   0.063       0
Bank Sta=4999.3,5003.3
Exp/Cntr=0.3,0.1

Type RM Length L Ch R = 1,1787,460,460,460
BEGIN DESCRIPTION:
Dry Comal Creek Tributary 30 4.0
END DESCRIPTION:
XS GIS Cut Line= 3
      2198775.01     13775824.96      2198825.00     13775525.00
      2198724.98     13775274.96
#Sta/Elev= 30
  4691.7  756.10  4701.8  755.36  4742.4  754.29  4803.2  751.11  4853.9  749.71
  4894.4  747.80  4935.0  747.06  4975.5  747.60  4976.6  747.17  4985.7  743.60
  4991.3  743.27  4991.5  742.77  4995.0  742.77  4995.3  743.27  5017.3  745.66
  5034.8  747.00  5059.1  748.63  5071.2  748.81  5094.1  750.66  5103.5  750.64
  5112.9  749.99  5125.0  750.33  5142.5  751.71  5147.9  751.39  5172.2  753.10
  5178.9  754.15  5196.4  754.37  5225.6  756.06  5232.7  756.67  5265.1  757.62
#Mann=5,-1,0
  4691.7    0.07       0  4976.6    0.12       0  4991.3    0.05       0
  4995.3    0.12       0  5225.6   0.035       0
Bank Sta=4991.3,4995.3
Exp/Cntr=0.3,0.1

Type RM Length L Ch R = 1,1327,416,416,416
BEGIN DESCRIPTION:
Dry Comal Creek Tributary 30 3.0
END DESCRIPTION:
XS GIS Cut Line= 3
      2198975.00     13775974.99      2199225.00     13775425.00
      2199074.98     13775274.98
#Sta/Elev= 30
  4405.2  759.88  4437.0  759.55  4471.1  756.75  4511.7  755.05  4602.9  752.78
  4632.6  750.16  4668.8  748.33  4786.3  745.00  4806.7  744.49  4856.7  747.29
  4866.5  746.23  4874.2  743.70  4879.7  744.20  4888.5  741.61  4897.3  740.06
  4941.4  739.97  4941.7  739.47  4945.2  739.47  4945.4  739.97  4954.4  740.55
  4987.4  740.07  5037.6  741.10  5051.8  740.44  5065.9  740.86  5080.1  743.21
  5094.2  746.47  5108.3  747.69  5150.8  749.82  5179.1  749.90  5221.5  751.57
#Mann=5,-1,0
  4405.2    0.07       0  4786.3   0.035       0  4806.7    0.07       0
  4941.4    0.05       0  4945.4    0.07       0
Bank Sta=4941.4,4945.4
Exp/Cntr=0.3,0.1

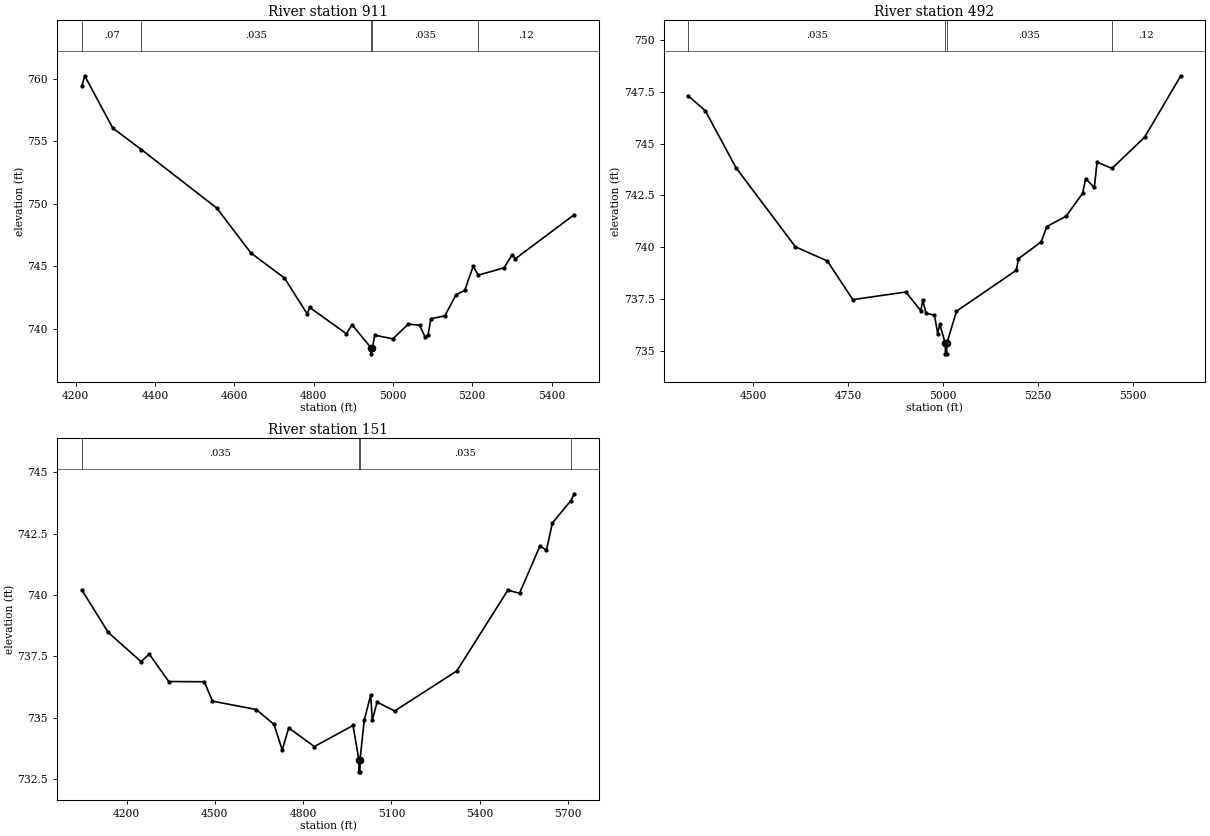
Type RM Length L Ch R = 1,911,419,419,419
BEGIN DESCRIPTION:
Dry Comal Creek Tributary 30 2.0
END DESCRIPTION:
XS GIS Cut Line= 3
      2199075.02     13776024.98      2199575.00     13775425.00
      2199274.98     13775074.98
#Sta/Elev= 30
  4215.5  759.40  4222.6  760.24  4293.6  756.05  4365.9  754.33  4555.9  749.65
  4641.8  746.06  4726.4  744.06  4783.7  741.19  4790.2  741.70  4882.6  739.60
  4896.9  740.32  4944.4  738.49  4944.6  737.99  4948.4  738.49  4954.2  739.48
  4999.8  739.19  5038.7  740.37  5067.3  740.28  5081.6  739.30  5088.7  739.52
  5095.8  740.80  5130.9  741.03  5159.5  742.73  5180.9  743.06  5202.3  744.98
  5215.5  744.29  5280.2  744.87  5301.1  745.93  5308.7  745.60  5457.5  749.13
#Mann=5,-1,0
  4215.5    0.07       0  4365.9   0.035       0  4944.4   0.035       0
  4948.4   0.035       0  5215.5    0.12       0
Bank Sta=4944.4,4948.4
Exp/Cntr=0.3,0.1

Type RM Length L Ch R = 1,492,341,341,341
BEGIN DESCRIPTION:
Dry Comal Creek Tributary 30 1.0
END DESCRIPTION:
XS GIS Cut Line= 3
      2199574.99     13775975.03      2199875.00     13775375.00
      2199325.04     13775075.02
#Sta/Elev= 30
  4329.1  747.31  4373.9  746.59  4454.9  743.83  4611.4  740.01  4695.3  739.33
  4762.4  737.46  4902.1  737.83  4941.3  736.93  4946.8  737.43  4955.2  736.80
  4977.6  736.71  4986.0  735.82  4991.6  736.27  5006.0  735.34  5006.3  734.84
  5009.8  734.84  5010.0  735.34  5035.5  736.90  5193.1  738.88  5198.8  739.44
  5258.6  740.25  5273.3  740.99  5324.1  741.49  5367.8  742.60  5375.9  743.31
  5398.6  742.88  5405.8  744.11  5445.0  743.80  5531.1  745.31  5626.4  748.28
#Mann=4,-1,0
  4329.1   0.035       0  5006.0   0.035       0  5010.0   0.035       0
  5445.0    0.12       0
Bank Sta=5006,5010
Exp/Cntr=0.3,0.1

Type RM Length L Ch R = 1,151,0,0,0
BEGIN DESCRIPTION:
X19013
END DESCRIPTION:
XS GIS Cut Line= 4
      2199884.40     13776074.30      2200247.21     13775383.47
      2200113.02     13775134.96      2199511.64     13775030.59
#Sta/Elev= 30
  4048.3  740.21  4137.9  738.48  4249.5  737.29  4277.2  737.60  4343.4  736.48
  4464.4  736.47  4492.1  735.68  4640.8  735.34  4701.3  734.73  4729.0  733.69
  4751.0  734.59  4838.2  733.83  4969.5  734.69  4989.4  733.30  4989.6  732.80
  4993.1  732.80  4993.4  733.30  5007.6  734.90  5029.5  735.92  5035.2  734.91
  5051.4  735.64  5111.0  735.28  5322.2  736.91  5495.3  740.20  5535.3  740.08
  5604.6  742.00  5626.6  741.83  5646.9  742.94  5709.6  743.85  5721.4  744.13
#Mann=4,-1,0
  4048.3   0.035       0  4989.4   0.035       0  4993.4   0.035       0
  5709.6    0.12       0
Bank Sta=4989.4,4993.4
Exp/Cntr=0.3,0.1

Chan Stop Cuts=-1