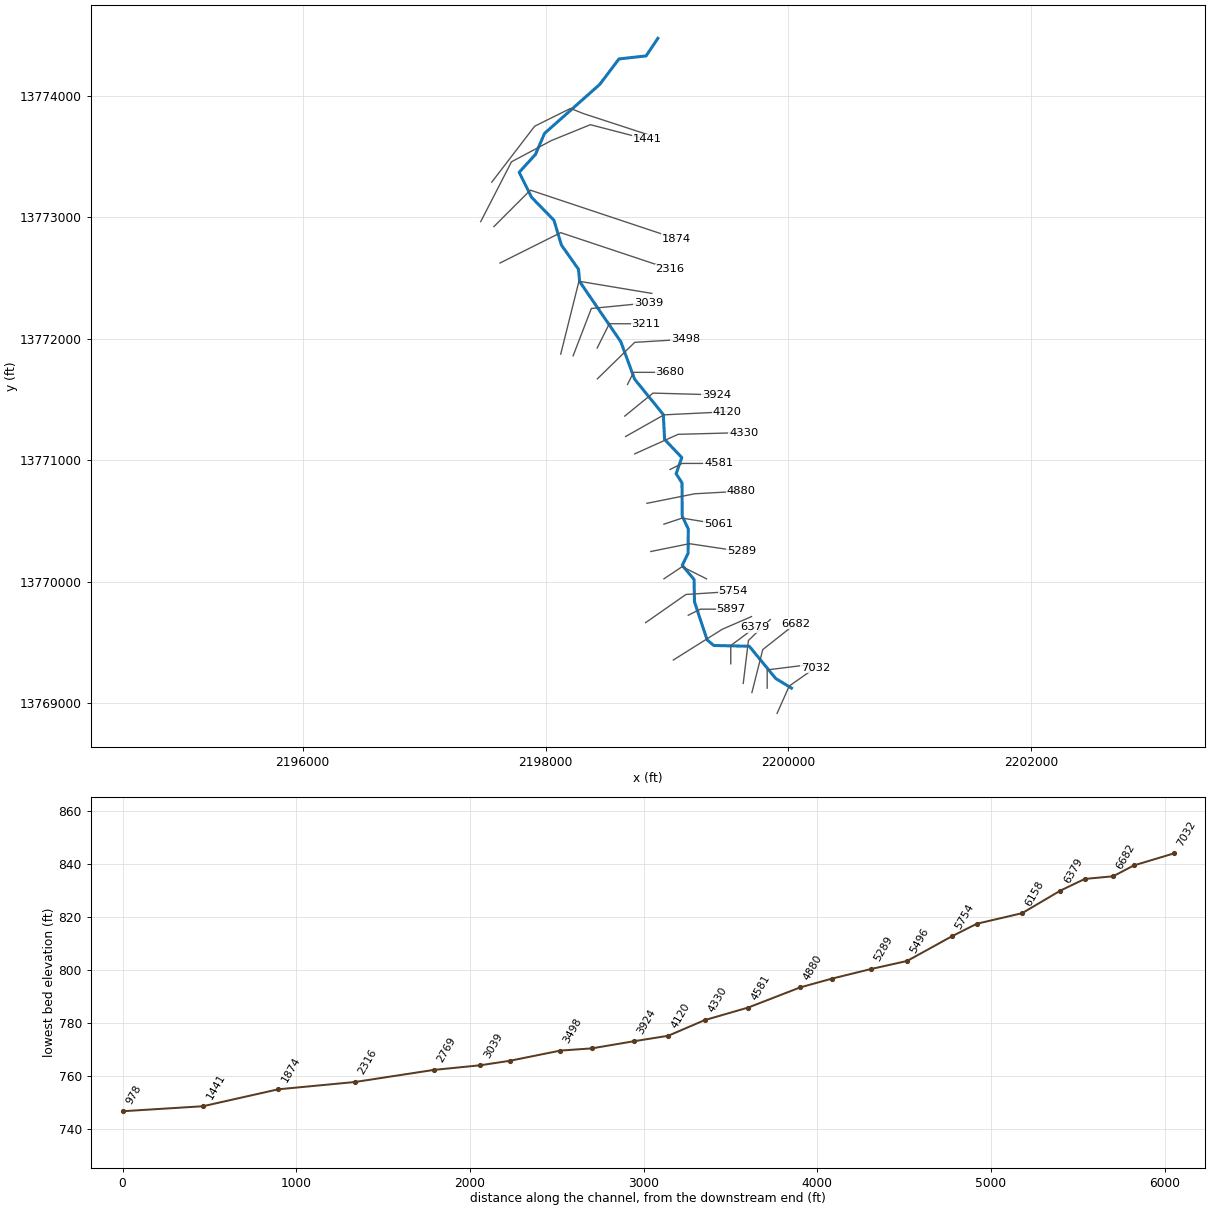
--- Dry Comal Creek Tributary 31.prj (project) ---

Proj Title=Dry Comal Creek Tributary 31 Base Level Engineering
Current Plan=p01
Default Exp/Contr=0.3,0.1
English Units
Geom File=g01
Flow File=f01
Plan File=p01
BEGIN DESCRIPTION:
Dry Comal Creek Tributary 31
END DESCRIPTION:

--- Dry Comal Creek Tributary 31.p01 (plan) ---

Plan Title=Multiple Run
Short Identifier=Multiple
Geom File=g01
Flow File=f01
Subcritical Flow
K Sum by GR= 0
Std Step Tol= 0.01
Critical Tol= 0.01
Num of Std Step Trials= 20
Max Error Tol= 0.3
Flow Tol Ratio= 0.001
Split Flow NTrial= 30
Split Flow Tol= 0.02
Split Flow Ratio= 0.02
Log Output Level= 0
Friction Slope Method= 1
Unsteady Friction Slope Method= 2
Unsteady Bridges Friction Slope Method= 1
Parabolic Critical Depth
Global Vel Dist=  1 , 1 , 1
Global Log Level= 0
CheckData=True
Encroach Param= -1, 0, 0, 0
BEGIN DESCRIPTION:
Multiple Run
END DESCRIPTION:

--- Dry Comal Creek Tributary 31.f01 (steady flow) ---

Flow Title=Multiple
Number of Profiles=7
Profile Names=10-year,25-year,50-year,1pct_min,100-year,1pct_plu,500-year
River Rch & RM= Dry Comal Creek ,Reach-1,7032
     409     652     869     562    1122    2239    1851
Boundary for River Rch & Prof#=Dry Comal Creek ,Reach-1,1
Up Type=0
Dn Type=3
Dn Slope=0.005
Boundary for River Rch & Prof#=Dry Comal Creek ,Reach-1,2
Up Type=0
Dn Type=3
Dn Slope=0.005
Boundary for River Rch & Prof#=Dry Comal Creek ,Reach-1,3
Up Type=0
Dn Type=3
Dn Slope=0.005
Boundary for River Rch & Prof#=Dry Comal Creek ,Reach-1,4
Up Type=0
Dn Type=3
Dn Slope=0.005
Boundary for River Rch & Prof#=Dry Comal Creek ,Reach-1,5
Up Type=0
Dn Type=3
Dn Slope=0.005
Boundary for River Rch & Prof#=Dry Comal Creek ,Reach-1,6
Up Type=0
Dn Type=3
Dn Slope=0.005
Boundary for River Rch & Prof#=Dry Comal Creek ,Reach-1,7
Up Type=0
Dn Type=3
Dn Slope=0.005

--- Dry Comal Creek Tributary 31.g01 (geometry) ---

Geom Title=Existing Conditions

River Reach=Dry Comal Creek ,Reach-1
Reach XY= 30
      2200025.00     13769125.00      2199894.76     13769204.58
      2199677.69     13769469.61      2199384.96     13769476.03
      2199330.40     13769522.29      2199226.22     13769835.50
      2199222.93     13770019.14      2199125.60     13770135.62
      2199173.76     13770235.50      2199175.45     13770435.19
      2199125.52     13770540.22      2199123.60     13770815.35
      2199075.10     13770890.40      2199121.87     13771023.37
      2198980.46     13771172.55      2198969.54     13771377.45
      2198733.16     13771668.95      2198619.46     13771977.42
      2198280.54     13772472.58      2198271.37     13772573.50
      2198130.77     13772772.68      2198069.17     13772977.30
      2197885.76     13773165.32      2197782.84     13773371.77
      2197916.86     13773518.94      2197991.49     13773692.05
      2198445.38     13774094.84      2198604.83     13774305.40
      2198827.70     13774330.35      2198925.00     13774475.00

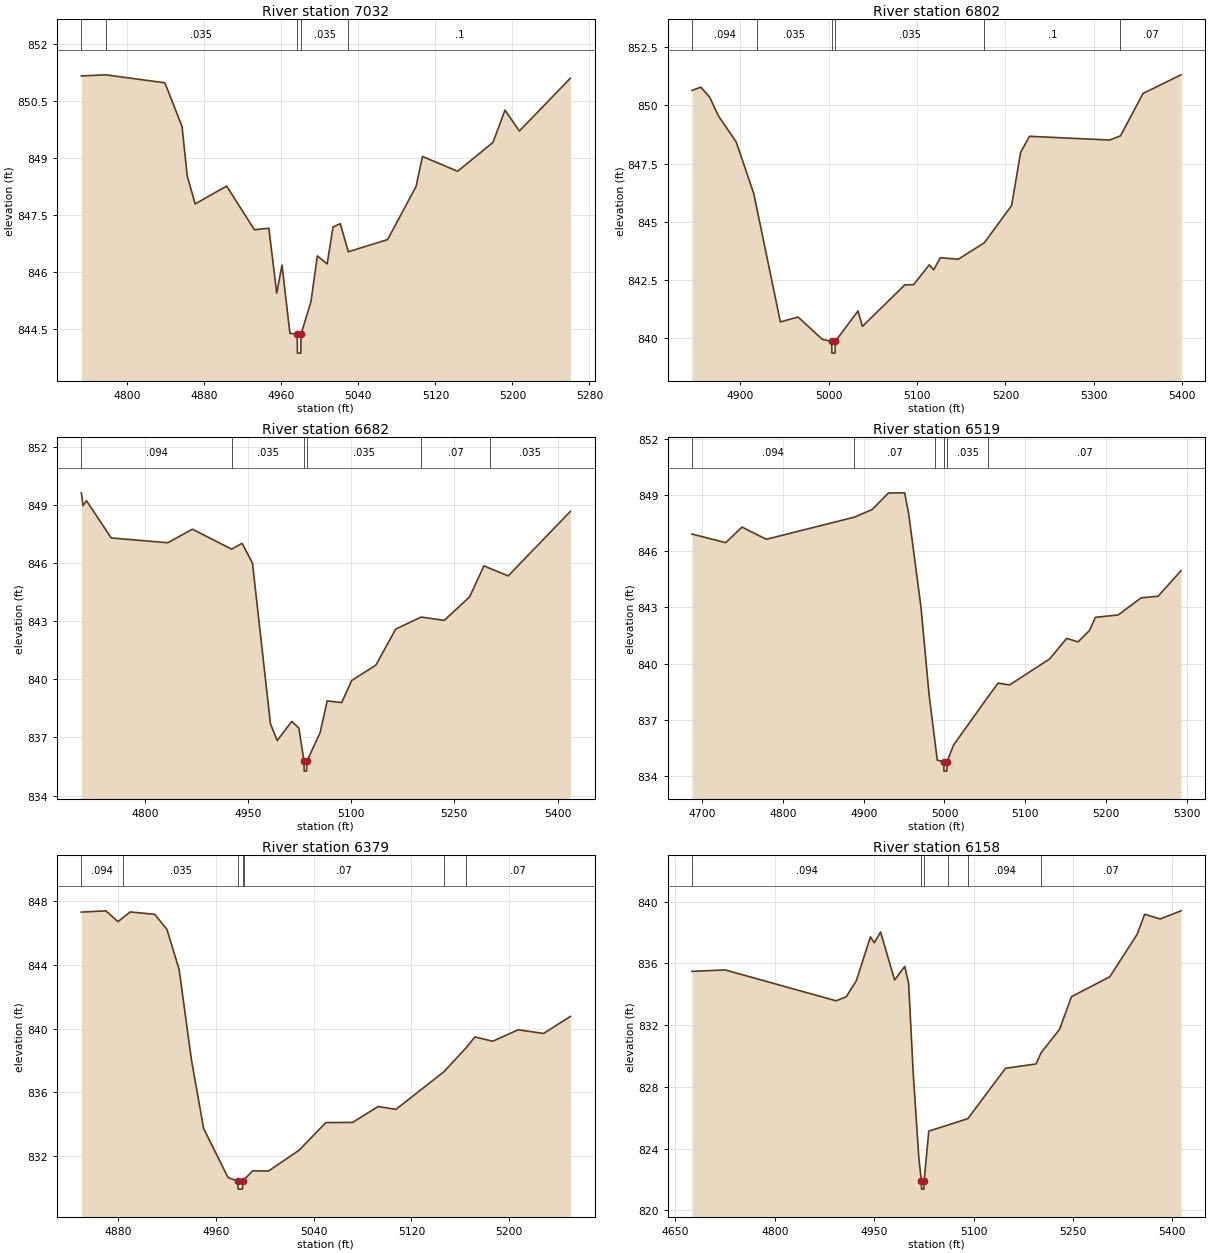
Type RM Length L Ch R = 1,7032,230,230,230
BEGIN DESCRIPTION:
X19030
END DESCRIPTION:
XS GIS Cut Line= 3
      2199906.42     13768916.97      2200006.49     13769142.12
      2200220.89     13769292.20
#Sta/Elev= 30
  4752.1  851.17  4777.2  851.20  4838.9  850.99  4856.7  849.84  4862.1  848.54
  4870.3  847.80  4903.1  848.27  4931.9  847.12  4946.9  847.16  4955.1  845.45
  4960.6  846.19  4968.8  844.39  4976.4  844.37  4976.6  843.87  4980.1  843.87
  4980.4  844.37  4990.7  845.23  4997.3  846.43  5007.5  846.22  5013.6  847.19
  5021.1  847.28  5029.5  846.54  5070.3  846.86  5099.9  848.26  5106.5  849.05
  5143.1  848.66  5179.8  849.42  5192.3  850.27  5207.2  849.72  5260.2  851.11
#Mann=5,-1,0
  4752.1     0.1       0  4777.2   0.035       0  4976.4   0.035       0
  4980.4   0.035       0  5029.5     0.1       0
Bank Sta=4976.4,4980.4
Exp/Cntr=0.3,0.1

Type RM Length L Ch R = 1,6802,120,120,120
BEGIN DESCRIPTION:
Dry Comal Creek Tributary 31 12.0
END DESCRIPTION:
XS GIS Cut Line= 3
      2199825.00     13769125.04      2199825.00     13769275.00
      2200225.03     13769325.00
#Sta/Elev= 30
  4845.5  850.64  4855.5  850.78  4865.5  850.35  4875.5  849.54  4895.5  848.43
  4915.5  846.20  4919.1  845.53  4945.5  840.70  4965.5  840.91  4993.0  839.95
  5003.5  839.86  5003.8  839.36  5007.3  839.36  5007.5  839.86  5033.3  841.17
  5038.3  840.51  5086.2  842.29  5096.2  842.30  5113.9  843.15  5118.9  842.94
  5126.5  843.46  5146.6  843.39  5176.2  844.10  5207.1  845.70  5217.2  847.98
  5227.3  848.67  5318.0  848.51  5330.2  848.69  5355.7  850.51  5398.6  851.31
#Mann=6,-1,0
  4845.5   0.094       0  4919.1   0.035       0  5003.5   0.035       0
  5007.5   0.035       0  5176.2     0.1       0  5330.2    0.07       0
Bank Sta=5003.5,5007.5
Exp/Cntr=0.3,0.1

Type RM Length L Ch R = 1,6682,163,163,163
BEGIN DESCRIPTION:
X19029
END DESCRIPTION:
XS GIS Cut Line= 3
      2199699.20     13769088.55      2199788.53     13769442.26
      2200060.01     13769656.58
#Sta/Elev= 30
  4707.9  849.64  4710.3  848.98  4715.4  849.23  4751.3  847.31  4833.4  847.06
  4869.3  847.76  4926.3  846.73  4941.5  847.03  4956.6  846.01  4982.7  837.71
  4992.5  836.84  5013.7  837.83  5024.0  837.49  5031.5  835.76  5031.8  835.26
  5035.3  835.26  5035.5  835.76  5054.9  837.25  5065.2  838.89  5086.3  838.80
  5100.7  839.94  5136.0  840.74  5164.8  842.60  5201.7  843.22  5235.3  843.05
  5272.1  844.26  5293.1  845.87  5301.3  845.74  5328.3  845.35  5418.6  848.68
#Mann=6,-1,0
  4707.9   0.094       0  4926.3   0.035       0  5031.5   0.035       0
  5035.5   0.035       0  5201.7    0.07       0  5301.3   0.035       0
Bank Sta=5031.5,5035.5
Exp/Cntr=0.3,0.1

Type RM Length L Ch R = 1,6519,140,140,140
BEGIN DESCRIPTION:
X19028
END DESCRIPTION:
XS GIS Cut Line= 3
      2199627.73     13769163.53      2199670.61     13769517.29
      2199850.20     13769689.84
#Sta/Elev= 30
  4687.4  846.92  4729.2  846.46  4749.3  847.29  4779.5  846.64  4888.4  847.82
  4910.5  848.23  4930.6  849.11  4950.7  849.12  4955.7  848.00  4970.9  843.02
  4981.0  838.32  4987.9  835.95  4991.1  834.85  4999.2  834.76  4999.4  834.26
  5002.9  834.26  5003.2  834.76  5011.2  835.65  5053.8  838.22  5066.4  838.96
  5080.5  838.86  5130.2  840.25  5151.3  841.35  5165.4  841.16  5179.6  841.77
  5186.8  842.47  5215.1  842.60  5243.4  843.51  5264.5  843.60  5292.8  844.96
#Mann=6,-1,0
  4687.4   0.094       0  4888.4    0.07       0  4987.9   0.035       0
  4999.2   0.035       0  5003.2   0.035       0  5053.8    0.07       0
Bank Sta=4999.2,5003.2
Exp/Cntr=0.3,0.1

Type RM Length L Ch R = 1,6379,221,221,221
BEGIN DESCRIPTION:
Dry Comal Creek Tributary 31 11.0
END DESCRIPTION:
XS GIS Cut Line= 3
      2199525.00     13769324.99      2199525.00     13769475.00
      2199724.99     13769624.99
#Sta/Elev= 30
  4850.0  847.33  4870.0  847.41  4880.0  846.73  4884.2  846.99  4890.0  847.34
  4910.0  847.19  4920.0  846.24  4930.0  843.71  4940.0  838.05  4950.0  833.71
  4970.0  830.62  4978.0  830.39  4978.3  829.89  4981.8  829.89  4982.0  830.39
  4982.7  830.45  4990.0  831.04  5003.1  831.03  5028.1  832.34  5050.0  834.08
  5071.9  834.09  5092.7  835.09  5107.3  834.91  5146.4  837.27  5164.7  838.78
  5171.9  839.47  5186.5  839.20  5207.3  839.92  5228.1  839.69  5250.0  840.76
#Mann=7,-1,0
  4850.0   0.094       0  4884.2   0.035       0  4978.0    0.05       0
  4982.0   0.035       0  4982.7    0.07       0  5146.4   0.035       0
  5164.7    0.07       0
Bank Sta=4978,4982
Exp/Cntr=0.3,0.1

Type RM Length L Ch R = 1,6158,261,261,261
BEGIN DESCRIPTION:
X19027
END DESCRIPTION:
XS GIS Cut Line= 3
      2199052.48     13769356.52      2199456.22     13769610.20
      2199695.64     13769713.82
#Sta/Elev= 30
  4675.2  835.48  4725.4  835.57  4892.6  833.57  4907.9  833.83  4923.2  834.88
  4944.4  837.71  4950.3  837.33  4959.7  838.03  4980.9  834.92  4996.2  835.80
  5002.1  834.68  5008.9  828.93  5017.4  823.43  5021.3  821.87  5021.6  821.37
  5025.1  821.37  5025.3  821.87  5032.5  825.13  5061.2  825.52  5091.5  825.94
  5148.2  829.20  5194.3  829.48  5201.8  830.20  5229.7  831.72  5247.8  833.84
  5305.6  835.13  5346.8  837.88  5358.1  839.18  5381.5  838.87  5412.9  839.40
#Mann=6,-1,0
  4675.2   0.094       0  5021.3    0.05       0  5025.3   0.094       0
  5061.2    0.07       0  5091.5   0.094       0  5201.8    0.07       0
Bank Sta=5021.3,5025.3
Exp/Cntr=0.3,0.1

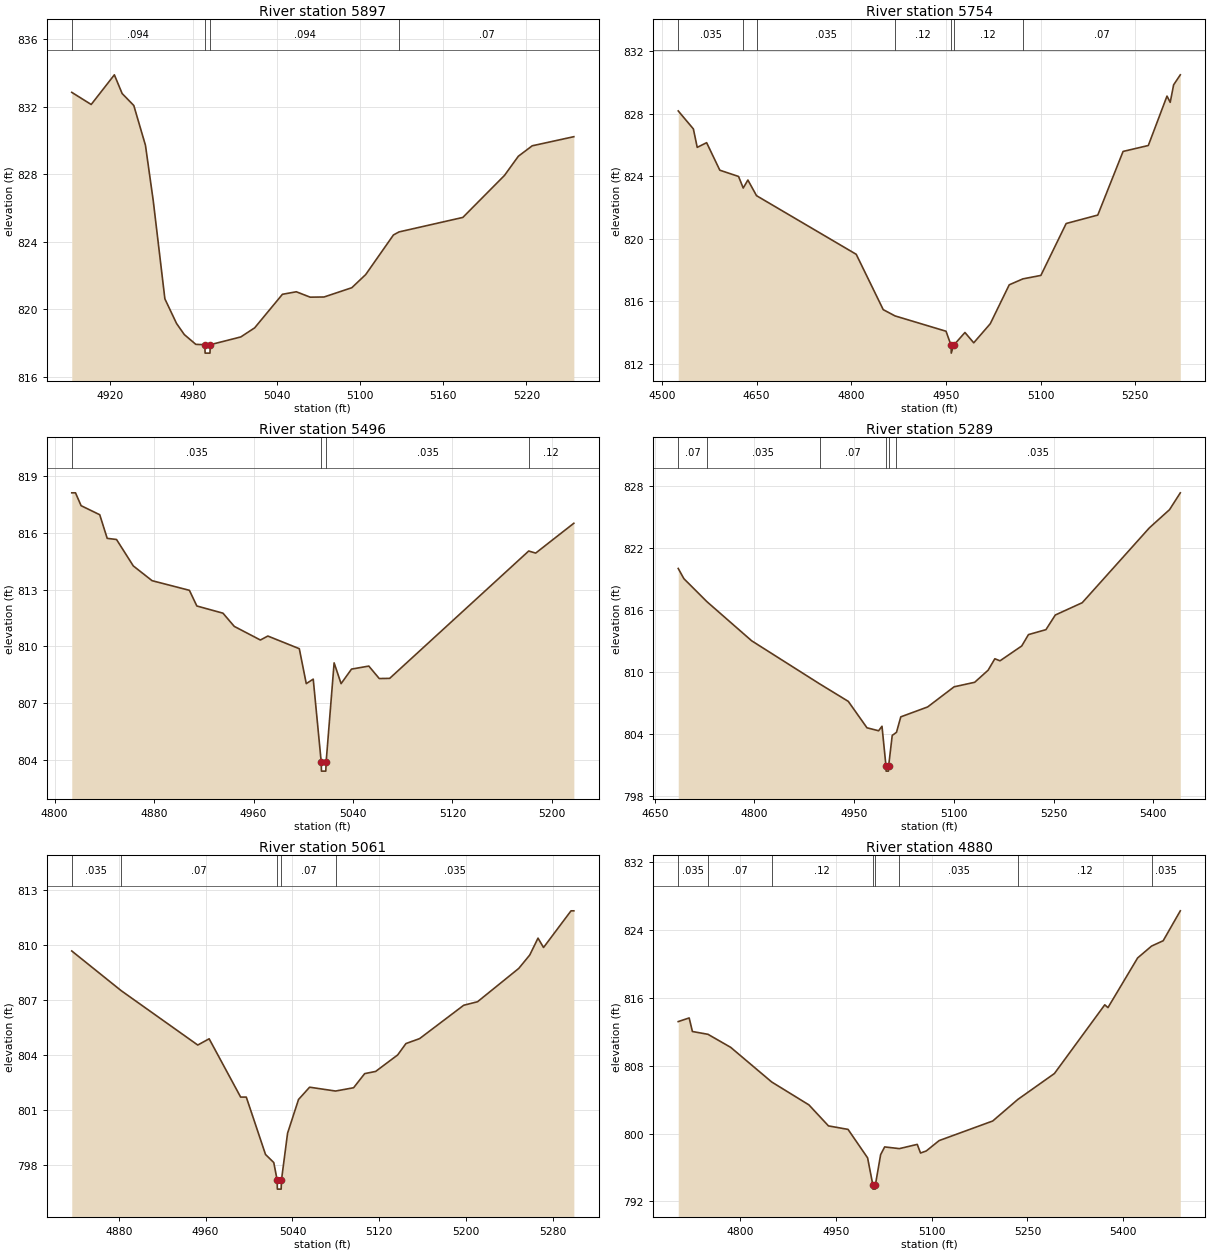
Type RM Length L Ch R = 1,5897,143,143,143
BEGIN DESCRIPTION:
Dry Comal Creek Tributary 31 10.0
END DESCRIPTION:
XS GIS Cut Line= 3
      2199175.00     13769725.00      2199275.00     13769775.00
      2199525.00     13769775.00
#Sta/Elev= 30
  4892.4  832.86  4906.4  832.14  4923.1  833.90  4928.7  832.79  4937.1  832.08
  4945.5  829.72  4951.1  826.44  4959.5  820.61  4967.9  819.15  4973.5  818.49
  4981.8  817.91  4988.2  817.89  4988.5  817.39  4992.0  817.39  4992.2  817.89
  5014.2  818.35  5024.2  818.89  5044.2  820.88  5054.2  821.03  5064.2  820.71
  5074.2  820.72  5094.2  821.27  5104.2  822.05  5124.2  824.40  5128.2  824.58
  5174.2  825.44  5204.2  827.93  5214.2  829.07  5224.2  829.69  5254.2  830.23
#Mann=4,-1,0
  4892.4   0.094       0  4988.2    0.05       0  4992.2   0.094       0
  5128.2    0.07       0
Bank Sta=4988.2,4992.2
Exp/Cntr=0.3,0.1

Type RM Length L Ch R = 1,5754,258,258,258
BEGIN DESCRIPTION:
X19026
END DESCRIPTION:
XS GIS Cut Line= 3
      2198823.77     13769663.79      2199156.08     13769896.05
      2199545.55     13769921.06
#Sta/Elev= 30
  4525.7  828.18  4549.7  827.03  4555.8  825.85  4570.7  826.15  4591.6  824.39
  4621.3  823.99  4628.7  823.25  4636.1  823.76  4649.8  822.76  4807.8  819.01
  4850.6  815.47  4869.3  815.07  4950.1  814.09  4958.1  813.19  4958.4  812.69
  4962.1  813.19  4980.1  814.01  4994.0  813.35  5020.2  814.57  5050.3  817.06
  5072.0  817.44  5100.4  817.66  5140.5  820.98  5190.6  821.52  5230.7  825.59
  5270.7  825.97  5300.3  829.13  5305.4  828.73  5310.8  829.85  5321.4  830.49
#Mann=7,-1,0
  4525.7   0.035       0  4628.7   0.094       0  4649.8   0.035       0
  4869.3    0.12       0  4958.1    0.05       0  4962.1    0.12       0
  5072.0    0.07       0
Bank Sta=4958.1,4962.1
Exp/Cntr=0.3,0.1

Type RM Length L Ch R = 1,5496,207,207,207
BEGIN DESCRIPTION:
Dry Comal Creek Tributary 31 9.0
END DESCRIPTION:
XS GIS Cut Line= 3
      2198975.04     13770025.03      2199125.00     13770125.00
      2199324.97     13770025.02
#Sta/Elev= 30
  4813.8  818.12  4816.8  818.12  4821.3  817.44  4836.3  816.96  4842.3  815.71
  4849.8  815.65  4863.3  814.25  4878.4  813.47  4908.4  812.96  4914.4  812.13
  4935.4  811.75  4944.5  811.05  4965.5  810.33  4971.5  810.54  4996.8  809.87
  5002.4  808.02  5008.0  808.26  5014.4  803.89  5014.6  803.39  5018.1  803.39
  5018.4  803.89  5024.8  809.12  5030.4  808.02  5038.8  808.79  5052.7  808.95
  5061.1  808.29  5069.5  808.30  5181.3  815.04  5186.9  814.93  5217.6  816.51
#Mann=4,-1,0
  4813.8   0.035       0  5014.4   0.035       0  5018.4   0.035       0
  5181.3    0.12       0
Bank Sta=5014.4,5018.4
Exp/Cntr=0.3,0.1

Type RM Length L Ch R = 1,5289,228,228,228
BEGIN DESCRIPTION:
X19025
END DESCRIPTION:
XS GIS Cut Line= 3
      2198866.68     13770249.79      2199184.67     13770314.10
      2199610.98     13770250.16
#Sta/Elev= 30
  4685.3  820.01  4693.8  819.02  4728.5  816.79  4795.8  813.00  4898.0  808.83
  4941.2  807.13  4969.3  804.57  4986.8  804.28  4991.9  804.72  4997.9  800.87
  4998.1  800.37  5001.6  800.37  5001.9  800.87  5007.3  803.83  5013.7  804.13
  5020.2  805.63  5060.6  806.59  5100.4  808.54  5131.4  808.98  5151.6  810.15
  5161.7  811.26  5169.5  811.06  5202.2  812.50  5212.3  813.60  5238.6  814.08
  5252.7  815.50  5293.2  816.69  5394.3  823.95  5424.6  825.71  5440.8  827.34
#Mann=6,-1,0
  4685.3    0.07       0  4728.5   0.035       0  4898.0    0.07       0
  4997.9    0.05       0  5001.9    0.07       0  5013.7   0.035       0
Bank Sta=4997.9,5001.9
Exp/Cntr=0.3,0.1

Type RM Length L Ch R = 1,5061,181,181,181
BEGIN DESCRIPTION:
Dry Comal Creek Tributary 31 8.0
END DESCRIPTION:
XS GIS Cut Line= 3
      2198974.97     13770474.99      2199125.00     13770525.00
      2199425.02     13770475.00
#Sta/Elev= 30
  4836.8  809.70  4882.2  807.54  4952.8  804.57  4963.3  804.91  4992.3  801.73
  4997.5  801.73  5015.2  798.60  5022.8  798.16  5025.9  797.21  5026.1  796.71
  5029.6  796.71  5029.9  797.21  5035.5  799.76  5045.6  801.60  5055.8  802.27
  5079.7  802.06  5096.3  802.24  5106.5  803.01  5116.6  803.13  5136.9  804.03
  5144.5  804.65  5157.1  804.92  5197.7  806.74  5210.4  806.93  5248.4  808.75
  5258.5  809.48  5266.1  810.40  5271.2  809.89  5296.5  811.89  5299.1  811.89
#Mann=5,-1,0
  4836.8   0.035       0  4882.2    0.07       0  5025.9    0.05       0
  5029.9    0.07       0  5079.7   0.035       0
Bank Sta=5025.9,5029.9
Exp/Cntr=0.3,0.1

Type RM Length L Ch R = 1,4880,299,299,299
BEGIN DESCRIPTION:
X19024
END DESCRIPTION:
XS GIS Cut Line= 3
      2198834.50     13770646.40      2199227.54     13770725.01
      2199611.72     13770746.36
#Sta/Elev= 30
  4703.7  813.21  4720.8  813.64  4725.9  812.04  4750.2  811.71  4785.8  810.17
  4850.0  806.08  4908.2  803.38  4938.8  800.90  4969.4  800.49  5000.0  797.13
  5008.2  793.94  5008.4  793.44  5011.9  793.44  5012.2  793.94  5020.4  797.51
  5026.7  798.42  5049.7  798.22  5077.7  798.72  5082.8  797.70  5091.7  797.94
  5112.0  799.17  5195.8  801.48  5235.0  804.02  5292.3  807.08  5371.1  815.19
  5376.1  814.86  5422.5  820.72  5444.3  822.12  5462.5  822.75  5489.3  826.28
#Mann=8,-1,0
  4703.7   0.035       0  4750.2    0.07       0  4850.0    0.12       0
  5008.2    0.05       0  5012.2    0.12       0  5049.7   0.035       0
  5235.0    0.12       0  5444.3   0.035       0
Bank Sta=5008.2,5012.2
Exp/Cntr=0.3,0.1

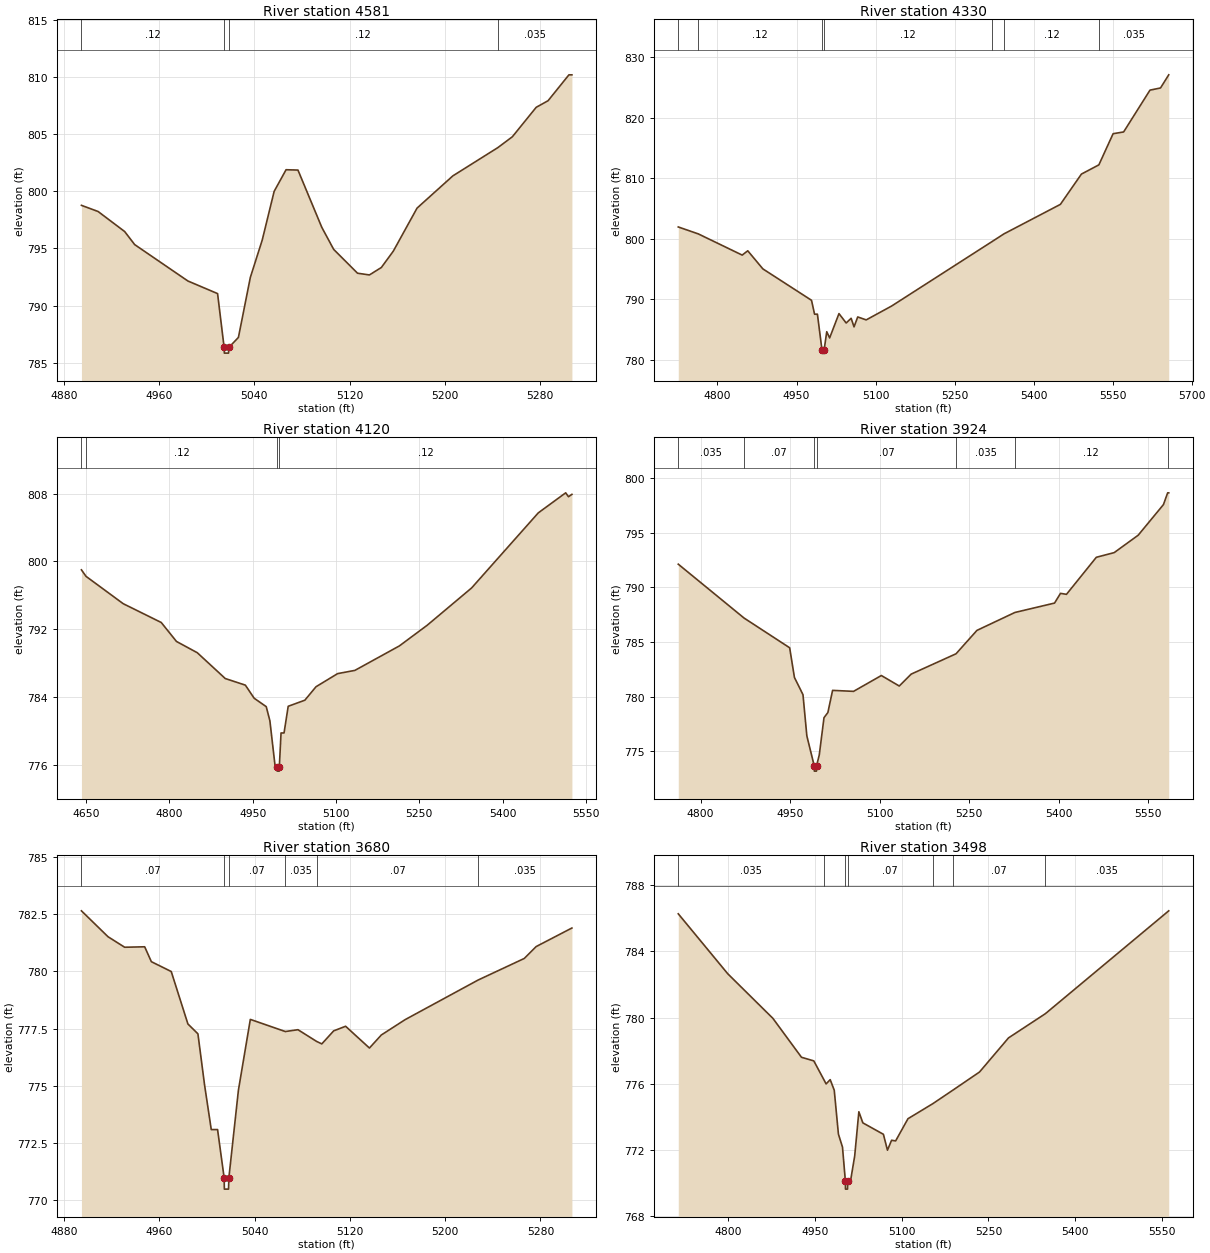
Type RM Length L Ch R = 1,4581,251,251,251
BEGIN DESCRIPTION:
Dry Comal Creek Tributary 31 7.0
END DESCRIPTION:
XS GIS Cut Line= 3
      2199025.02     13770925.01      2199125.00     13770975.00
      2199425.02     13770975.00
#Sta/Elev= 30
  4894.8  798.77  4908.8  798.23  4931.1  796.48  4939.5  795.34  4984.2  792.16
  5009.1  791.06  5014.6  786.36  5014.8  785.86  5018.3  785.86  5018.6  786.36
  5026.6  787.23  5036.6  792.47  5046.6  795.74  5056.6  799.99  5066.6  801.88
  5076.6  801.85  5096.6  796.85  5106.6  794.92  5126.6  792.84  5136.6  792.69
  5146.6  793.34  5156.6  794.76  5176.6  798.53  5206.6  801.34  5244.4  803.81
  5256.6  804.76  5276.6  807.33  5286.6  807.91  5304.1  810.17  5306.6  810.17
#Mann=4,-1,0
  4894.8    0.12       0  5014.6    0.05       0  5018.6    0.12       0
  5244.4   0.035       0
Bank Sta=5014.6,5018.6
Exp/Cntr=0.3,0.1

Type RM Length L Ch R = 1,4330,210,210,210
BEGIN DESCRIPTION:
X19023
END DESCRIPTION:
XS GIS Cut Line= 3
      2198734.41     13771053.72      2199091.77     13771214.53
      2199630.61     13771228.80
#Sta/Elev= 30
  4725.6  801.97  4763.7  800.82  4846.9  797.32  4857.5  798.03  4886.2  795.04
  4978.5  789.85  4984.3  787.55  4989.7  787.56  4998.4  781.62  4998.6  781.12
  5002.4  781.62  5007.4  784.66  5012.9  783.63  5030.6  787.65  5044.3  786.10
  5053.7  786.88  5059.2  785.46  5066.2  787.10  5082.3  786.61  5130.7  788.91
  5320.2  799.50  5343.8  800.83  5450.8  805.70  5490.8  810.71  5523.9  812.23
  5550.9  817.38  5570.9  817.67  5620.9  824.58  5640.9  824.94  5656.5  827.11
#Mann=7,-1,0
  4725.6   0.035       0  4763.7    0.12       0  4998.4    0.05       0
  5002.4    0.12       0  5320.2   0.035       0  5343.8    0.12       0
  5523.9   0.035       0
Bank Sta=4998.4,5002.4
Exp/Cntr=0.3,0.1

Type RM Length L Ch R = 1,4120,196,196,196
BEGIN DESCRIPTION:
Dry Comal Creek Tributary 31 6.0
END DESCRIPTION:
XS GIS Cut Line= 3
      2198659.41     13771196.66      2198975.00     13771375.00
      2199495.50     13771400.33
#Sta/Elev= 30
  4641.4  799.01  4649.7  798.24  4716.7  795.01  4785.2  792.79  4812.6  790.55
  4850.1  789.22  4900.5  786.17  4936.7  785.39  4952.6  783.84  4974.3  782.85
  4980.9  781.18  4990.2  775.87  4993.9  775.73  4994.2  775.23  4997.7  775.23
  4997.9  775.73  5001.0  779.74  5006.4  779.74  5013.9  782.89  5043.9  783.61
  5064.0  785.20  5102.9  786.75  5134.0  787.13  5214.1  790.02  5264.2  792.46
  5344.3  796.87  5464.4  805.74  5513.8  808.11  5518.8  807.65  5525.0  807.93
#Mann=4,-1,0
  4641.4   0.035       0  4649.7    0.12       0  4993.9    0.05       0
  4997.9    0.12       0
Bank Sta=4993.9,4997.9
Exp/Cntr=0.3,0.1

Type RM Length L Ch R = 1,3924,244,244,244
BEGIN DESCRIPTION:
X19022
END DESCRIPTION:
XS GIS Cut Line= 3
      2198652.24     13771364.58      2198884.52     13771553.98
      2199406.22     13771539.68
#Sta/Elev= 30
  4762.5  792.13  4872.7  787.20  4949.1  784.48  4957.1  781.76  4971.4  780.19
  4977.9  776.41  4990.2  773.69  4990.5  773.19  4994.0  773.19  4994.2  773.69
  4998.7  774.67  5006.6  778.08  5013.1  778.55  5021.0  780.58  5056.1  780.49
  5102.7  781.94  5132.7  780.98  5152.7  782.07  5227.8  783.93  5262.8  786.07
  5326.4  787.71  5392.8  788.57  5402.8  789.46  5412.8  789.37  5462.8  792.76
  5492.8  793.19  5532.9  794.78  5575.2  797.58  5582.3  798.66  5584.1  798.66
#Mann=7,-1,0
  4762.5   0.035       0  4872.7    0.07       0  4990.2    0.05       0
  4994.2    0.07       0  5227.8   0.035       0  5326.4    0.12       0
  5582.3   0.035       0
Bank Sta=4990.2,4994.2
Exp/Cntr=0.3,0.1

Type RM Length L Ch R = 1,3680,182,182,182
BEGIN DESCRIPTION:
Dry Comal Creek Tributary 31 5.0
END DESCRIPTION:
XS GIS Cut Line= 3
      2198675.01     13771625.02      2198725.00     13771725.00
      2199025.02     13771725.00
#Sta/Elev= 30
  4894.6  782.64  4916.9  781.51  4930.9  781.05  4947.7  781.07  4953.3  780.42
  4970.0  779.99  4984.0  777.70  4992.4  777.27  4998.0  775.03  5003.6  773.09
  5008.9  773.09  5014.4  770.99  5014.6  770.49  5018.1  770.49  5018.4  770.99
  5026.4  774.81  5036.4  777.90  5065.8  777.37  5076.4  777.45  5092.0  776.94
  5096.4  776.83  5106.4  777.40  5116.4  777.60  5136.4  776.65  5146.4  777.22
  5166.4  777.89  5227.7  779.62  5266.4  780.56  5276.4  781.08  5306.4  781.89
#Mann=6,-1,0
  4894.6    0.07       0  5014.4    0.05       0  5018.4    0.07       0
  5065.8   0.035       0  5092.0    0.07       0  5227.7   0.035       0
Bank Sta=5014.4,5018.4
Exp/Cntr=0.3,0.1

Type RM Length L Ch R = 1,3498,287,287,287
BEGIN DESCRIPTION:
X19021
END DESCRIPTION:
XS GIS Cut Line= 3
      2198427.14     13771671.87      2198734.45     13771972.03
      2199151.23     13771996.97
#Sta/Elev= 30
  4714.3  786.27  4799.8  782.65  4877.7  779.96  4927.1  777.61  4948.4  777.39
  4966.5  776.21  4969.6  776.00  4976.7  776.26  4983.7  775.62  4990.9  772.97
  4997.9  772.19  5002.9  770.15  5003.1  769.65  5006.6  769.65  5006.9  770.15
  5012.0  770.18  5019.0  771.65  5026.2  774.32  5033.1  773.65  5068.6  772.96
  5075.6  772.00  5082.7  772.60  5089.7  772.56  5111.0  773.90  5154.0  774.81
  5188.8  775.63  5234.6  776.72  5284.7  778.78  5348.3  780.24  5561.4  786.45
#Mann=7,-1,0
  4714.3   0.035       0  4966.5    0.07       0  5002.9    0.05       0
  5006.9    0.07       0  5154.0   0.035       0  5188.8    0.07       0
  5348.3   0.035       0
Bank Sta=5002.9,5006.9
Exp/Cntr=0.3,0.1

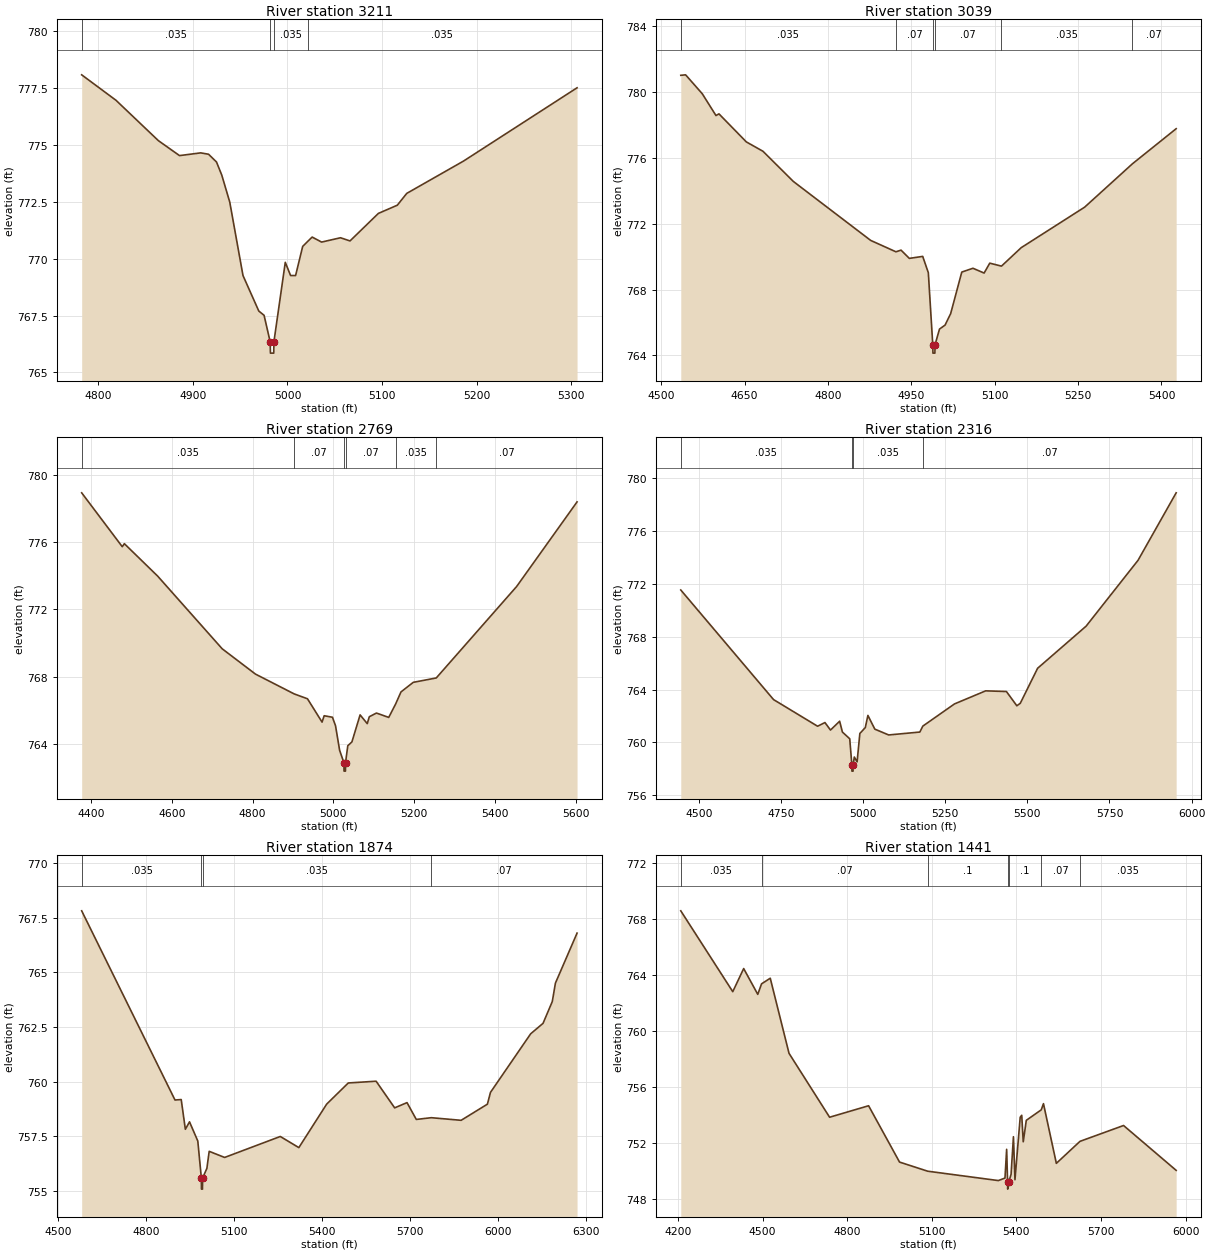
Type RM Length L Ch R = 1,3211,172,172,172
BEGIN DESCRIPTION:
Dry Comal Creek Tributary 31 4.0
END DESCRIPTION:
XS GIS Cut Line= 3
      2198425.01     13771925.02      2198525.00     13772125.00
      2198825.02     13772125.00
#Sta/Elev= 30
  4782.5  778.08  4818.8  776.96  4863.5  775.19  4885.9  774.53  4908.3  774.65
  4916.6  774.59  4925.0  774.25  4930.6  773.67  4939.0  772.49  4953.0  769.26
  4969.7  767.70  4975.3  767.51  4981.7  766.35  4982.0  765.85  4985.5  765.85
  4985.7  766.35  4997.7  769.84  5003.3  769.26  5008.6  769.26  5016.1  770.54
  5021.4  770.76  5026.1  770.95  5036.1  770.73  5056.1  770.92  5066.1  770.78
  5096.1  771.99  5116.1  772.35  5126.1  772.87  5186.1  774.29  5306.1  777.51
#Mann=4,-1,0
  4782.5   0.035       0  4981.7    0.05       0  4985.7   0.035       0
  5021.4   0.035       0
Bank Sta=4981.7,4985.7
Exp/Cntr=0.3,0.1

Type RM Length L Ch R = 1,3039,270,270,270
BEGIN DESCRIPTION:
X19020
END DESCRIPTION:
XS GIS Cut Line= 3
      2198227.08     13771861.29      2198377.14     13772250.74
      2198848.79     13772297.19
#Sta/Elev= 30
  4535.1  781.00  4543.8  781.03  4573.8  779.88  4598.4  778.56  4603.8  778.66
  4653.0  776.96  4683.0  776.39  4737.6  774.56  4876.8  770.98  4922.2  770.29
  4931.4  770.39  4946.3  769.89  4970.4  770.01  4980.5  769.02  4988.5  764.64
  4988.8  764.14  4992.3  764.14  4992.5  764.64  5000.6  765.60  5010.6  765.84
  5020.7  766.54  5040.7  769.06  5060.8  769.29  5080.9  769.00  5091.0  769.60
  5112.1  769.42  5147.6  770.54  5261.8  773.00  5347.7  775.63  5426.4  777.76
#Mann=6,-1,0
  4535.1   0.035       0  4922.2    0.07       0  4988.5    0.05       0
  4992.5    0.07       0  5112.1   0.035       0  5347.7    0.07       0
Bank Sta=4988.5,4992.5
Exp/Cntr=0.3,0.1

Type RM Length L Ch R = 1,2769,453,453,453
BEGIN DESCRIPTION:
Dry Comal Creek Tributary 31 3.0
END DESCRIPTION:
XS GIS Cut Line= 3
      2198124.99     13771874.98      2198275.00     13772475.00
      2198875.03     13772374.99
#Sta/Elev= 30
  4376.7  778.95  4477.2  775.74  4482.4  775.92  4564.8  773.99  4724.6  769.66
  4807.1  768.15  4903.0  766.97  4935.9  766.68  4972.0  765.29  4977.2  765.67
  4997.7  765.58  5005.3  765.08  5015.5  763.61  5026.1  762.87  5026.4  762.37
  5029.9  762.37  5030.1  762.87  5035.7  763.88  5045.9  764.11  5066.2  765.72
  5083.9  765.20  5089.0  765.61  5106.7  765.83  5137.1  765.57  5154.4  766.38
  5167.5  767.09  5197.9  767.66  5254.8  767.92  5453.9  773.37  5603.5  778.41
#Mann=6,-1,0
  4376.7   0.035       0  4903.0    0.07       0  5026.1    0.05       0
  5030.1    0.07       0  5154.4   0.035       0  5254.8    0.07       0
Bank Sta=5026.1,5030.1
Exp/Cntr=0.3,0.1

Type RM Length L Ch R = 1,2316,442,442,442
BEGIN DESCRIPTION:
Dry Comal Creek Tributary 31 2.0
END DESCRIPTION:
XS GIS Cut Line= 3
      2197625.04     13772625.02      2198125.00     13772875.00
      2199025.04     13772574.99
#Sta/Elev= 30
  4445.2  771.55  4727.5  763.25  4861.6  761.23  4884.0  761.51  4900.8  760.94
  4928.7  761.61  4937.1  760.79  4959.4  760.28  4965.8  758.33  4966.1  757.83
  4969.6  757.83  4969.8  758.33  4973.4  758.90  4981.8  758.53  4990.2  760.68
  5006.8  761.13  5014.7  762.05  5035.8  761.01  5078.0  760.57  5172.8  760.79
  5181.9  761.24  5278.2  762.92  5373.1  763.91  5436.3  763.86  5468.0  762.78
  5478.5  762.97  5531.2  765.62  5678.8  768.81  5836.9  773.80  5952.9  778.91
#Mann=4,-1,0
  4445.2   0.035       0  4965.8   0.035       0  4969.8   0.035       0
  5181.9    0.07       0
Bank Sta=4965.8,4969.8
Exp/Cntr=0.3,0.1

Type RM Length L Ch R = 1,1874,433,433,433
BEGIN DESCRIPTION:
Dry Comal Creek Tributary 31 1.0
END DESCRIPTION:
XS GIS Cut Line= 3
      2197575.02     13772925.02      2197875.00     13773225.00
      2199075.04     13772824.99
#Sta/Elev= 30
  4580.8  767.82  4899.0  759.16  4920.2  759.18  4934.3  757.82  4948.5  758.16
  4976.8  757.28  4988.9  755.58  4989.2  755.08  4992.7  755.08  4992.9  755.58
  5007.7  756.03  5015.6  756.81  5068.3  756.53  5258.0  757.49  5321.3  756.98
  5416.1  758.97  5489.9  759.94  5584.8  760.02  5648.0  758.80  5690.2  759.04
  5721.8  758.27  5773.0  758.35  5874.7  758.23  5964.3  758.97  5974.8  759.51
  6111.8  762.19  6154.0  762.67  6185.6  763.67  6196.2  764.51  6270.0  766.80
#Mann=4,-1,0
  4580.8   0.035       0  4988.9   0.035       0  4992.9   0.035       0
  5773.0    0.07       0
Bank Sta=4988.9,4992.9
Exp/Cntr=0.3,0.1

Type RM Length L Ch R = 1,1441,463,463,463
BEGIN DESCRIPTION:
X19019
END DESCRIPTION:
XS GIS Cut Line= 5
      2197465.99     13772965.36      2197719.68     13773458.46
      2198048.41     13773633.54      2198368.87     13773763.92
      2198837.63     13773642.39
#Sta/Elev= 30
  4209.6  768.57  4394.0  762.80  4432.7  764.45  4482.7  762.61  4496.1  763.36
  4527.0  763.76  4593.6  758.40  4737.5  753.84  4875.8  754.66  4985.6  750.64
  5085.3  749.99  5336.0  749.32  5359.6  749.50  5365.5  751.55  5368.9  749.21
  5369.2  748.71  5372.9  749.21  5381.2  749.77  5389.6  752.45  5395.0  749.38
  5413.6  753.84  5419.0  753.98  5424.4  752.09  5435.2  753.62  5488.3  754.37
  5496.1  754.81  5541.8  750.55  5625.7  752.12  5780.2  753.25  5966.8  750.05
#Mann=7,-1,0
  4209.6   0.035       0  4496.1    0.07       0  5085.3     0.1       0
  5368.9    0.05       0  5372.9     0.1       0  5488.3    0.07       0
  5625.7   0.035       0
Bank Sta=5368.9,5372.9
Exp/Cntr=0.3,0.1

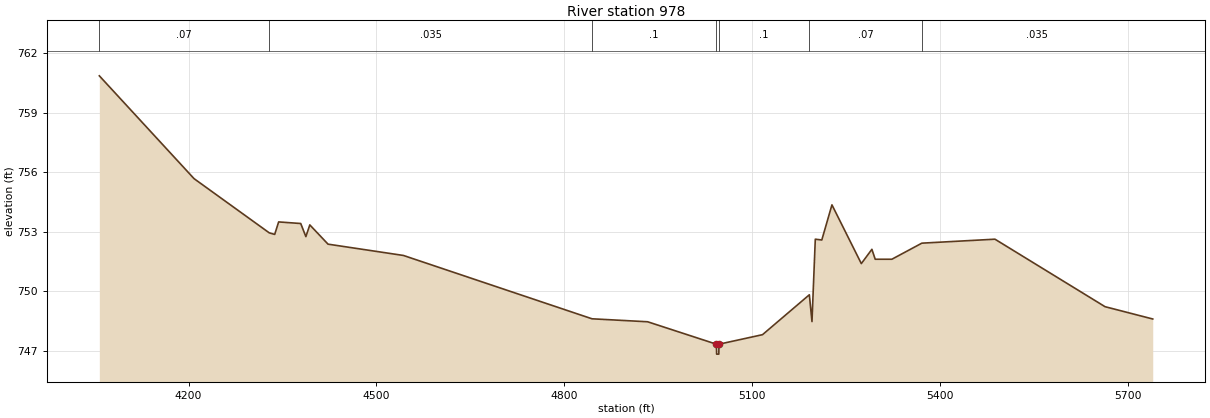
Type RM Length L Ch R = 1,978,0,0,0
BEGIN DESCRIPTION:
X19018
END DESCRIPTION:
XS GIS Cut Line= 5
      2197557.21     13773290.79      2197910.62     13773751.57
      2198205.63     13773897.95      2198312.82     13773855.07
      2198937.47     13773651.06
#Sta/Elev= 30
  4057.4  760.85  4208.7  755.67  4328.8  752.94  4337.5  752.86  4343.8  753.49
  4379.1  753.41  4387.3  752.75  4393.6  753.34  4422.7  752.37  4543.2  751.80
  4844.3  748.61  4933.2  748.46  5043.1  747.33  5043.4  746.83  5046.9  746.83
  5047.1  747.33  5116.7  747.81  5191.5  749.82  5195.7  748.47  5201.0  752.62
  5211.4  752.58  5227.6  754.35  5274.5  751.39  5291.4  752.11  5296.7  751.61
  5323.3  751.61  5371.2  752.42  5488.0  752.62  5663.8  749.22  5740.0  748.60
#Mann=7,-1,0
  4057.4    0.07       0  4328.8   0.035       0  4844.3     0.1       0
  5043.1    0.05       0  5047.1     0.1       0  5191.5    0.07       0
  5371.2   0.035       0
Bank Sta=5043.1,5047.1
Exp/Cntr=0.3,0.1

Chan Stop Cuts=-1