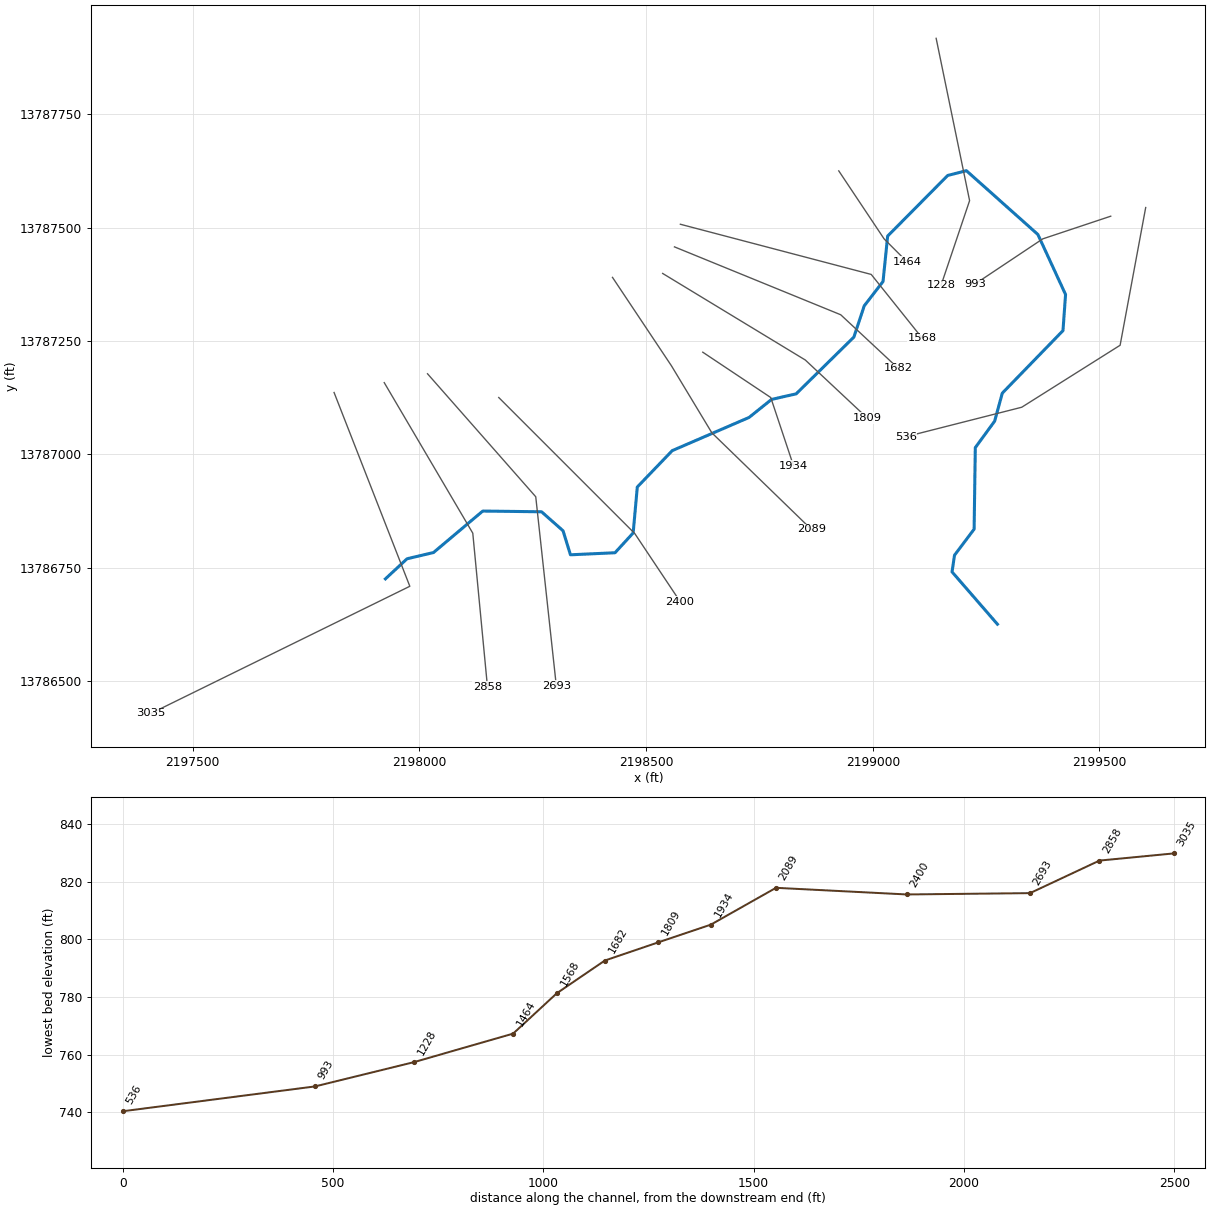
--- Dry Comal Creek Tributary 33.prj (project) ---

Proj Title=Dry Comal Creek Tributary 33 Base Level Engineering
Current Plan=p01
Default Exp/Contr=0.3,0.1
English Units
Geom File=g01
Flow File=f01
Plan File=p01
Y Axis Title=Elevation
X Axis Title(PF)=Main Channel Distance
X Axis Title(XS)=Station
BEGIN DESCRIPTION:
Dry Comal Creek Tributary 33
END DESCRIPTION:
DSS Export Rating Curves= 0
DSS Export Rating Curve Sorted= 0
DSS Export Volume Flow Curves= 0
DXF OffsetX= 0
DXF OffsetY= 0
DXF ScaleX= 1
DXF ScaleY= 10

--- Dry Comal Creek Tributary 33.p01 (plan) ---

Plan Title=Multiple Run
Short Identifier=Multiple
Geom File=g01
Flow File=f01
Subcritical Flow
K Sum by GR= 0
Std Step Tol= 0.01
Critical Tol= 0.01
Num of Std Step Trials= 20
Max Error Tol= 0.3
Flow Tol Ratio= 0.001
Split Flow NTrial= 30
Split Flow Tol= 0.02
Split Flow Ratio= 0.02
Log Output Level= 0
Friction Slope Method= 1
Unsteady Friction Slope Method= 2
Unsteady Bridges Friction Slope Method= 1
Parabolic Critical Depth
Global Vel Dist=  1 , 1 , 1
Global Log Level= 0
CheckData=True
Encroach Param= -1, 0, 0, 0
BEGIN DESCRIPTION:
Multiple Run
END DESCRIPTION:

--- Dry Comal Creek Tributary 33.f01 (steady flow) ---

Flow Title=Multiple
Number of Profiles=7
Profile Names=10-year,25-year,50-year,1pct_min,100-year,1pct_plu,500-year
River Rch & RM= Dry Comal Creek ,Reach-1,3035
     239     367     479     304     607    1211     961
Boundary for River Rch & Prof#=Dry Comal Creek ,Reach-1,1
Up Type=0
Dn Type=3
Dn Slope=0.005
Boundary for River Rch & Prof#=Dry Comal Creek ,Reach-1,2
Up Type=0
Dn Type=3
Dn Slope=0.005
Boundary for River Rch & Prof#=Dry Comal Creek ,Reach-1,3
Up Type=0
Dn Type=3
Dn Slope=0.005
Boundary for River Rch & Prof#=Dry Comal Creek ,Reach-1,4
Up Type=0
Dn Type=3
Dn Slope=0.005
Boundary for River Rch & Prof#=Dry Comal Creek ,Reach-1,5
Up Type=0
Dn Type=3
Dn Slope=0.005
Boundary for River Rch & Prof#=Dry Comal Creek ,Reach-1,6
Up Type=0
Dn Type=3
Dn Slope=0.005
Boundary for River Rch & Prof#=Dry Comal Creek ,Reach-1,7
Up Type=0
Dn Type=3
Dn Slope=0.005

--- Dry Comal Creek Tributary 33.g01 (geometry) ---

Geom Title=Existing Conditions

River Reach=Dry Comal Creek ,Reach-1
Reach XY= 30
      2197925.00     13786725.00      2197972.65     13786769.30
      2198031.08     13786783.07      2198139.70     13786874.58
      2198269.46     13786872.96      2198316.83     13786831.03
      2198333.20     13786778.08      2198431.45     13786782.60
      2198471.48     13786826.25      2198480.59     13786927.57
      2198557.69     13787007.84      2198727.20     13787081.08
      2198776.74     13787120.81      2198831.06     13787133.14
      2198958.36     13787258.32      2198981.14     13787327.17
      2199022.67     13787380.97      2199032.86     13787481.17
      2199165.32     13787614.83      2199206.59     13787625.37
      2199364.24     13787484.68      2199425.30     13787352.24
      2199419.60     13787272.57      2199285.76     13787134.68
      2199268.86     13787072.83      2199226.20     13787014.50
      2199223.60     13786834.65      2199180.35     13786777.17
      2199174.91     13786740.34      2199275.00     13786625.00

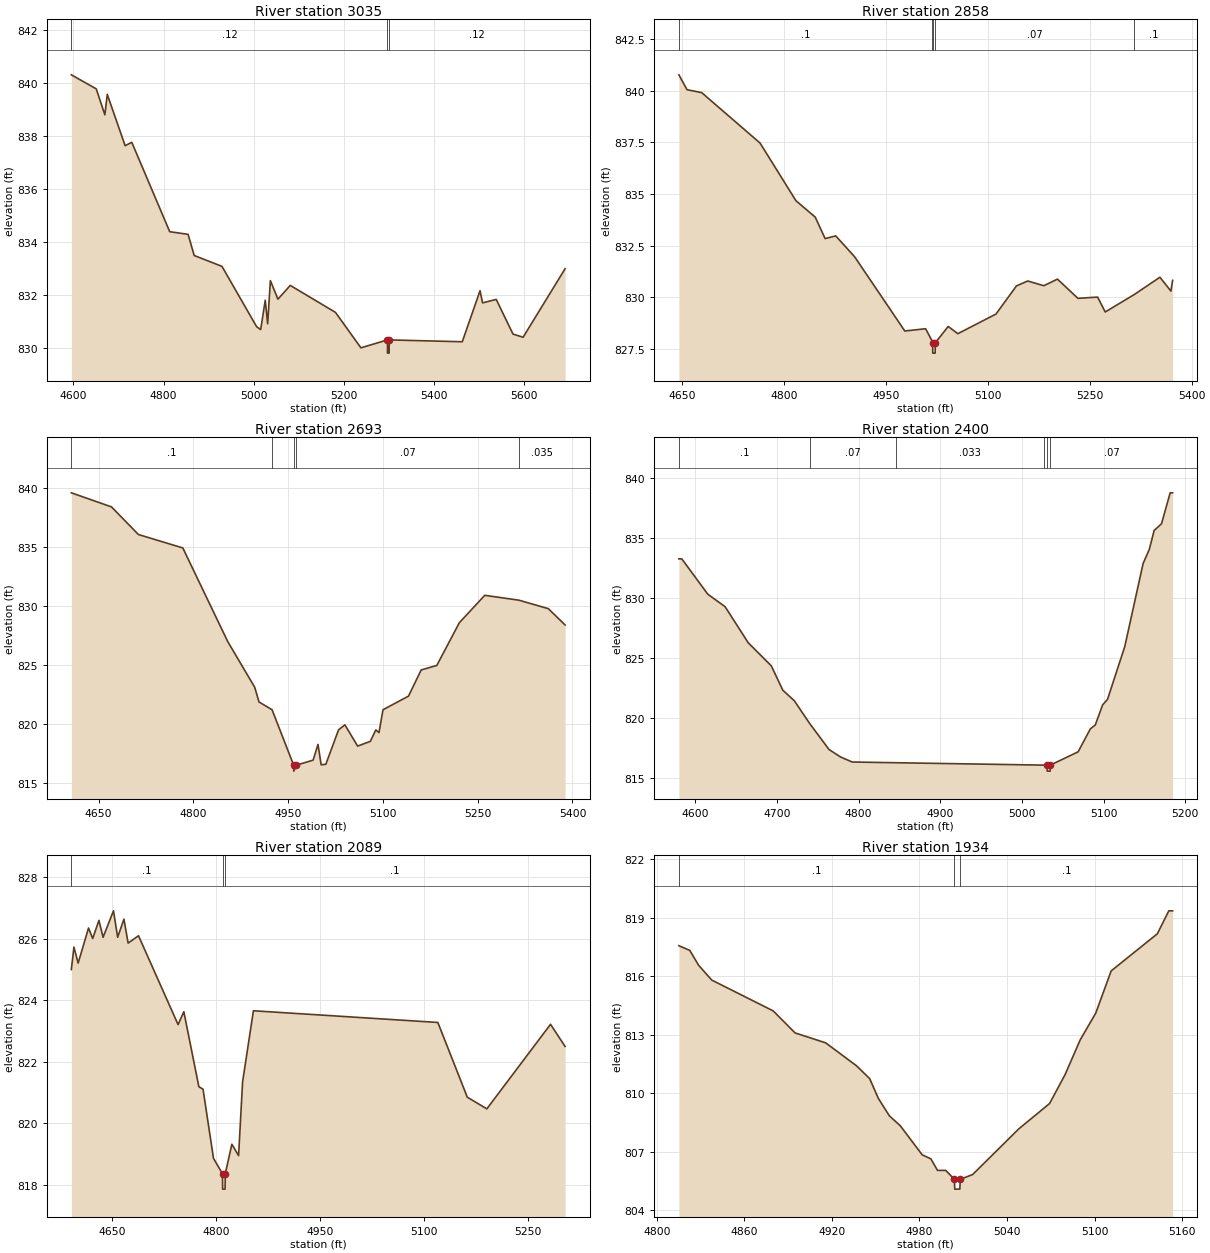
Type RM Length L Ch R = 1,3035,177,177,177
BEGIN DESCRIPTION:
Dry Comal Creek Tributary 33 5.0
END DESCRIPTION:
XS GIS Cut Line= 3
      2197811.72     13787136.10      2197978.81     13786708.62
      2197407.91     13786428.27
#Sta/Elev= 30
  4595.5  840.31  4650.7  839.78  4669.8  838.80  4675.2  839.57  4714.8  837.63
  4729.5  837.76  4813.7  834.38  4854.4  834.28  4868.0  833.48  4929.5  833.07
  5006.4  830.79  5015.4  830.68  5025.5  831.79  5030.9  830.90  5036.9  832.53
  5053.7  831.83  5081.0  832.35  5181.3  831.33  5237.7  829.99  5296.5  830.29
  5296.7  829.79  5300.2  829.79  5300.5  830.29  5462.5  830.22  5501.9  832.15
  5507.5  831.69  5537.8  831.82  5575.0  830.51  5597.4  830.39  5690.5  832.98
#Mann=3,-1,0
  4595.5    0.12       0  5296.5    0.05       0  5300.5    0.12       0
Bank Sta=5296.5,5300.5
Exp/Cntr=0.3,0.1

Type RM Length L Ch R = 1,2858,165,165,165
BEGIN DESCRIPTION:
X19038
END DESCRIPTION:
XS GIS Cut Line= 3
      2197922.39     13787157.83      2198117.70     13786825.80
      2198150.13     13786486.36
#Sta/Elev= 30
  4645.8  840.76  4657.8  840.04  4679.3  839.90  4765.2  837.46  4818.0  834.67
  4846.3  833.88  4860.9  832.84  4876.5  832.97  4904.3  831.96  4978.1  828.37
  5008.7  828.48  5018.0  827.90  5019.0  827.80  5019.2  827.30  5022.7  827.30
  5023.0  827.80  5041.9  828.59  5056.1  828.24  5112.2  829.19  5142.3  830.55
  5158.9  830.79  5182.5  830.56  5202.6  830.88  5232.7  829.95  5261.7  830.01
  5272.9  829.29  5315.4  830.13  5353.3  830.97  5369.5  830.30  5372.0  830.82
#Mann=5,-1,0
  4645.8     0.1       0  5018.0    0.07       0  5019.0    0.05       0
  5023.0    0.07       0  5315.4     0.1       0
Bank Sta=5019,5023
Exp/Cntr=0.3,0.1

Type RM Length L Ch R = 1,2693,293,293,293
BEGIN DESCRIPTION:
X19037
END DESCRIPTION:
XS GIS Cut Line= 3
      2198017.86     13787177.39      2198256.59     13786906.10
      2198302.01     13786488.64
#Sta/Elev= 30
  4607.0  839.59  4670.5  838.40  4713.1  836.06  4783.4  834.92  4854.5  826.99
  4897.2  823.12  4903.9  821.88  4924.6  821.22  4958.8  816.52  4959.0  816.02
  4962.8  816.52  4989.6  816.95  4997.3  818.28  5002.3  816.56  5009.7  816.60
  5029.8  819.51  5039.9  819.94  5060.0  818.14  5080.1  818.54  5088.8  819.51
  5093.8  819.28  5100.2  821.22  5140.5  822.37  5160.6  824.59  5185.3  824.97
  5221.0  828.59  5261.2  830.91  5315.0  830.50  5361.8  829.78  5388.3  828.40
#Mann=5,-1,0
  4607.0     0.1       0  4924.6    0.07       0  4958.8    0.05       0
  4962.8    0.07       0  5315.0   0.035       0
Bank Sta=4958.8,4962.8
Exp/Cntr=0.3,0.1

Type RM Length L Ch R = 1,2400,311,311,311
BEGIN DESCRIPTION:
Dry Comal Creek Tributary 33 4.0
END DESCRIPTION:
XS GIS Cut Line= 3
      2198174.99     13787125.01      2198475.00     13786825.00
      2198575.02     13786674.97
#Sta/Elev= 30
  4579.9  833.27  4583.5  833.27  4615.3  830.32  4636.5  829.28  4664.8  826.27
  4693.1  824.34  4707.2  822.31  4721.3  821.43  4740.1  819.53  4763.8  817.36
  4777.9  816.74  4792.1  816.32  4846.2  816.26  5027.6  816.06  5030.7  816.06
  5031.0  815.56  5034.5  815.56  5034.7  816.06  5068.8  817.17  5083.8  819.09
  5089.8  819.41  5098.8  821.09  5104.8  821.55  5125.9  825.95  5148.4  832.89
  5155.9  834.05  5161.9  835.64  5170.9  836.20  5181.5  838.78  5184.5  838.78
#Mann=6,-1,0
  4579.9     0.1       0  4740.1    0.07       0  4846.2   0.033       0
  5027.6    0.07       0  5030.7   0.033       0  5034.7    0.07       0
Bank Sta=5030.7,5034.7
Exp/Cntr=0.3,0.1

Type RM Length L Ch R = 1,2089,155,155,155
BEGIN DESCRIPTION:
X19036
END DESCRIPTION:
XS GIS Cut Line= 4
      2198425.87     13787390.03      2198556.07     13787194.73
      2198645.04     13787047.16      2198864.19     13786834.52
#Sta/Elev= 30
  4591.6  825.00  4595.3  825.73  4601.4  825.21  4616.4  826.35  4622.4  826.01
  4631.4  826.60  4637.4  826.05  4652.4  826.91  4658.4  826.05  4667.5  826.64
  4673.5  825.86  4688.5  826.10  4745.6  823.21  4753.9  823.63  4775.6  821.19
  4781.6  821.11  4796.7  818.86  4809.7  818.36  4809.9  817.86  4813.4  817.86
  4813.7  818.36  4823.2  819.32  4832.9  818.95  4838.7  821.35  4854.3  823.66
  5120.4  823.28  5162.9  820.85  5191.1  820.47  5283.0  823.22  5304.0  822.50
#Mann=3,-1,0
  4591.6     0.1       0  4809.7    0.05       0  4813.7     0.1       0
Bank Sta=4809.7,4813.7
Exp/Cntr=0.3,0.1

Type RM Length L Ch R = 1,1934,125,125,125
BEGIN DESCRIPTION:
Dry Comal Creek Tributary 33 3.0
END DESCRIPTION:
XS GIS Cut Line= 3
      2198625.04     13787224.98      2198775.00     13787125.00
      2198824.99     13786975.04
#Sta/Elev= 30
  4815.2  817.57  4822.7  817.33  4828.7  816.57  4837.7  815.81  4879.8  814.23
  4894.8  813.10  4915.8  812.59  4936.8  811.42  4945.9  810.76  4951.9  809.74
  4959.4  808.85  4966.9  808.34  4981.9  806.85  4987.9  806.64  4992.4  806.05
  4998.1  806.05  5004.0  805.59  5004.2  805.09  5007.7  805.09  5008.0  805.59
  5016.5  805.84  5048.1  808.18  5069.2  809.48  5079.8  810.96  5090.3  812.76
  5100.8  814.11  5111.4  816.28  5143.0  818.18  5150.9  819.36  5153.5  819.36
#Mann=3,-1,0
  4815.2     0.1       0  5004.0    0.05       0  5008.0     0.1       0
Bank Sta=5004,5008
Exp/Cntr=0.3,0.1

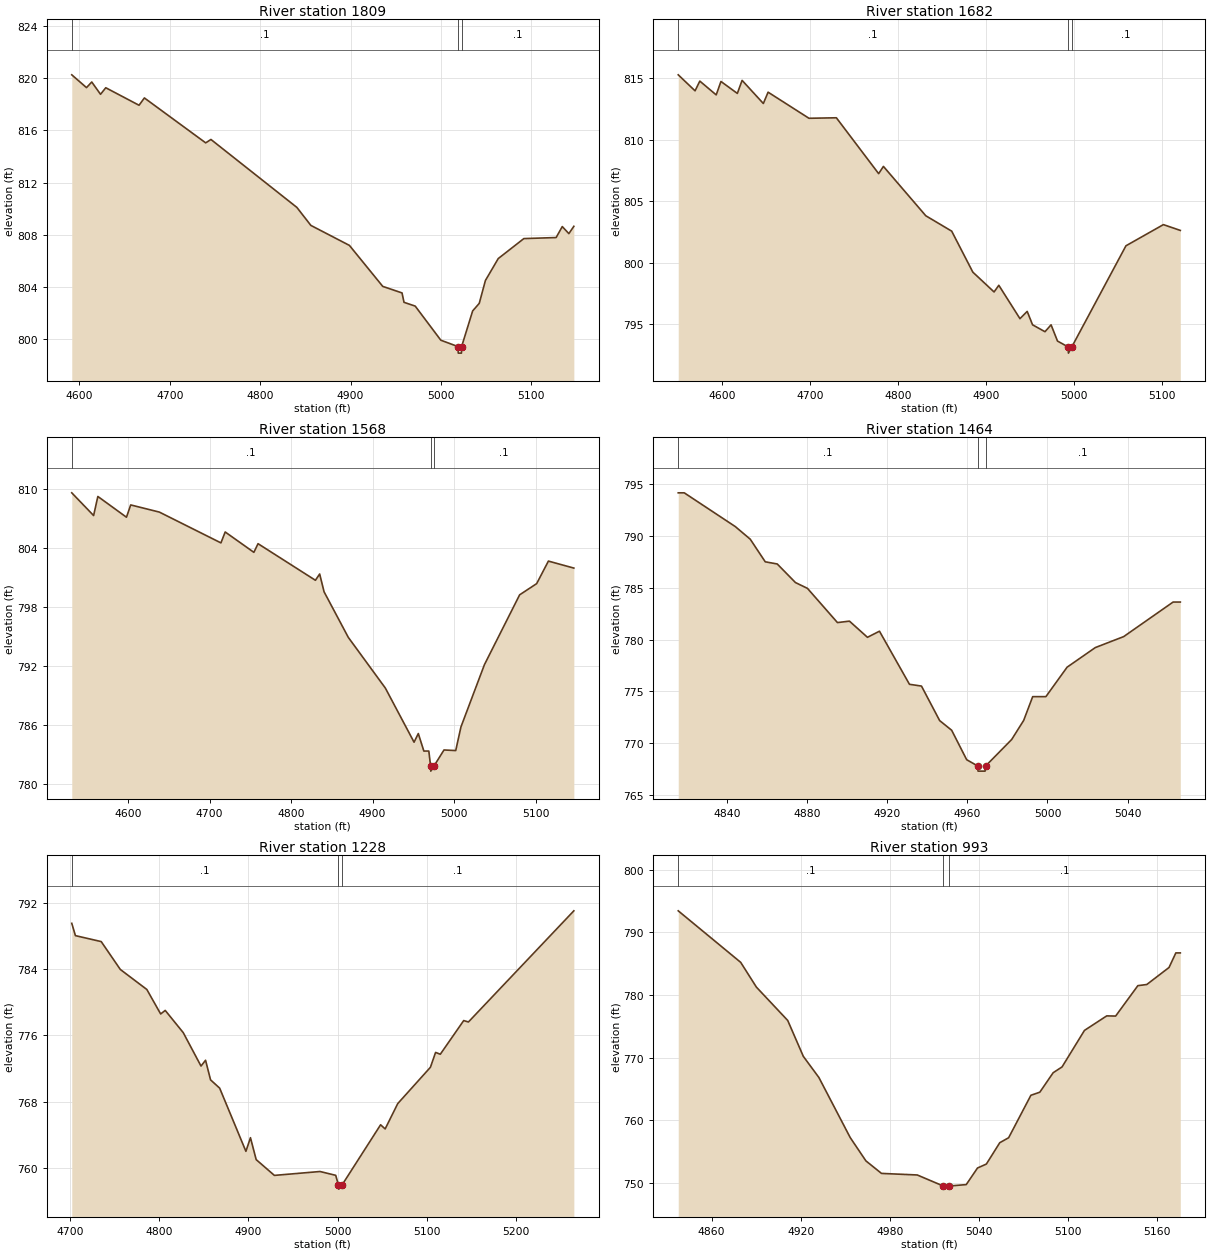
Type RM Length L Ch R = 1,1809,127,127,127
BEGIN DESCRIPTION:
X19035
END DESCRIPTION:
XS GIS Cut Line= 3
      2198536.55     13787398.71      2198851.21     13787207.75
      2198987.79     13787079.84
#Sta/Elev= 30
  4591.7  820.26  4608.0  819.28  4613.8  819.71  4623.5  818.77  4629.3  819.27
  4666.1  817.93  4672.0  818.49  4739.8  815.05  4745.6  815.31  4840.6  810.11
  4856.1  808.73  4898.7  807.20  4935.6  804.06  4956.9  803.56  4959.1  802.84
  4971.5  802.55  4999.8  799.94  5018.8  799.45  5019.1  798.95  5022.6  798.95
  5022.8  799.45  5035.0  802.18  5042.3  802.76  5049.1  804.51  5063.3  806.19
  5091.6  807.72  5127.3  807.80  5134.1  808.64  5141.4  808.10  5146.9  808.66
#Mann=3,-1,0
  4591.7     0.1       0  5018.8    0.05       0  5022.8     0.1       0
Bank Sta=5018.8,5022.8
Exp/Cntr=0.3,0.1

Type RM Length L Ch R = 1,1682,114,114,114
BEGIN DESCRIPTION:
X19034
END DESCRIPTION:
XS GIS Cut Line= 3
      2198562.58     13787457.32      2198929.33     13787307.58
      2199056.43     13787189.10
#Sta/Elev= 30
  4550.6  815.26  4569.7  813.96  4575.1  814.75  4593.7  813.63  4599.1  814.72
  4617.7  813.75  4623.1  814.81  4647.2  812.93  4652.6  813.85  4699.0  811.73
  4730.1  811.77  4778.1  807.23  4783.5  807.82  4831.6  803.81  4861.0  802.56
  4885.0  799.23  4909.1  797.62  4914.5  798.16  4938.5  795.45  4946.7  796.04
  4952.8  794.95  4966.9  794.39  4973.8  794.95  4981.1  793.63  4993.3  793.15
  4993.5  792.65  4997.3  793.15  5058.8  801.37  5101.3  803.09  5120.5  802.62
#Mann=3,-1,0
  4550.6     0.1       0  4993.3    0.05       0  4997.3     0.1       0
Bank Sta=4993.3,4997.3
Exp/Cntr=0.3,0.1

Type RM Length L Ch R = 1,1568,104,104,104
BEGIN DESCRIPTION:
X19033
END DESCRIPTION:
XS GIS Cut Line= 3
      2198575.62     13787507.22      2198996.60     13787396.55
      2199109.43     13787255.51
#Sta/Elev= 30
  4531.0  809.62  4557.8  807.31  4563.0  809.25  4598.1  807.14  4603.3  808.39
  4638.5  807.66  4714.0  804.53  4719.2  805.64  4754.4  803.57  4759.5  804.45
  4829.9  800.73  4835.1  801.37  4840.5  799.56  4870.2  794.93  4915.7  789.77
  4950.9  784.27  4956.1  785.15  4962.9  783.37  4969.0  783.37  4971.2  781.83
  4971.4  781.33  4975.2  781.83  4987.6  783.48  5002.0  783.42  5008.4  785.82
  5037.2  792.15  5080.4  799.25  5101.3  800.39  5115.7  802.68  5146.9  801.97
#Mann=3,-1,0
  4531.0     0.1       0  4971.2    0.05       0  4975.2     0.1       0
Bank Sta=4971.2,4975.2
Exp/Cntr=0.3,0.1

Type RM Length L Ch R = 1,1464,236,236,236
BEGIN DESCRIPTION:
Dry Comal Creek Tributary 33 2.0
END DESCRIPTION:
XS GIS Cut Line= 3
      2198925.02     13787624.97      2199025.00     13787475.00
      2199075.04     13787424.96
#Sta/Elev= 30
  4815.4  794.15  4818.4  794.15  4843.9  790.90  4851.4  789.68  4858.9  787.50
  4864.9  787.29  4874.0  785.50  4880.0  784.94  4895.0  781.64  4901.0  781.78
  4910.0  780.22  4916.0  780.81  4931.0  775.69  4937.0  775.52  4946.1  772.19
  4952.1  771.26  4959.6  768.42  4965.1  767.82  4965.3  767.32  4968.8  767.32
  4969.1  767.82  4982.1  770.37  4988.1  772.21  4992.6  774.50  4999.2  774.50
  5009.8  777.34  5023.9  779.23  5038.1  780.29  5062.8  783.62  5066.4  783.62
#Mann=3,-1,0
  4815.4     0.1       0  4965.1    0.05       0  4969.1     0.1       0
Bank Sta=4965.1,4969.1
Exp/Cntr=0.3,0.1

Type RM Length L Ch R = 1,1228,235,235,235
BEGIN DESCRIPTION:
X19032
END DESCRIPTION:
XS GIS Cut Line= 3
      2199139.84     13787917.34      2199213.62     13787559.31
      2199150.69     13787372.68
#Sta/Elev= 30
  4702.1  789.56  4706.2  788.07  4735.1  787.35  4756.5  783.98  4786.2  781.56
  4801.7  778.60  4806.8  779.03  4827.0  776.34  4846.9  772.30  4852.0  773.00
  4857.6  770.63  4867.8  769.63  4897.2  761.99  4902.3  763.64  4908.7  760.99
  4929.1  759.08  4980.2  759.55  4997.8  759.09  5000.9  757.92  5001.2  757.42
  5004.9  757.92  5048.1  765.20  5053.2  764.70  5067.3  767.76  5103.9  772.15
  5109.7  773.95  5115.0  773.73  5141.2  777.80  5146.5  777.63  5264.6  791.07
#Mann=3,-1,0
  4702.1     0.1       0  5000.9    0.05       0  5004.9     0.1       0
Bank Sta=5000.9,5004.9
Exp/Cntr=0.3,0.1

Type RM Length L Ch R = 1,993,457,457,457
BEGIN DESCRIPTION:
Dry Comal Creek Tributary 33 1.0
END DESCRIPTION:
XS GIS Cut Line= 3
      2199524.97     13787524.99      2199375.00     13787475.00
      2199224.97     13787374.98
#Sta/Elev= 30
  4837.5  793.46  4879.6  785.23  4890.2  781.27  4911.3  775.95  4921.8  770.22
  4932.3  766.84  4953.4  757.25  4964.0  753.52  4974.5  751.52  4998.6  751.27
  5016.1  749.51  5016.4  749.01  5020.1  749.51  5031.6  749.73  5039.2  752.38
  5045.2  753.02  5054.2  756.42  5060.2  757.22  5075.2  764.00  5081.2  764.49
  5090.2  767.60  5096.2  768.53  5111.3  774.36  5126.3  776.68  5132.3  776.65
  5147.3  781.51  5153.3  781.69  5168.3  784.41  5172.9  786.74  5175.9  786.74
#Mann=3,-1,0
  4837.5     0.1       0  5016.1    0.05       0  5020.1     0.1       0
Bank Sta=5016.1,5020.1
Exp/Cntr=0.3,0.1

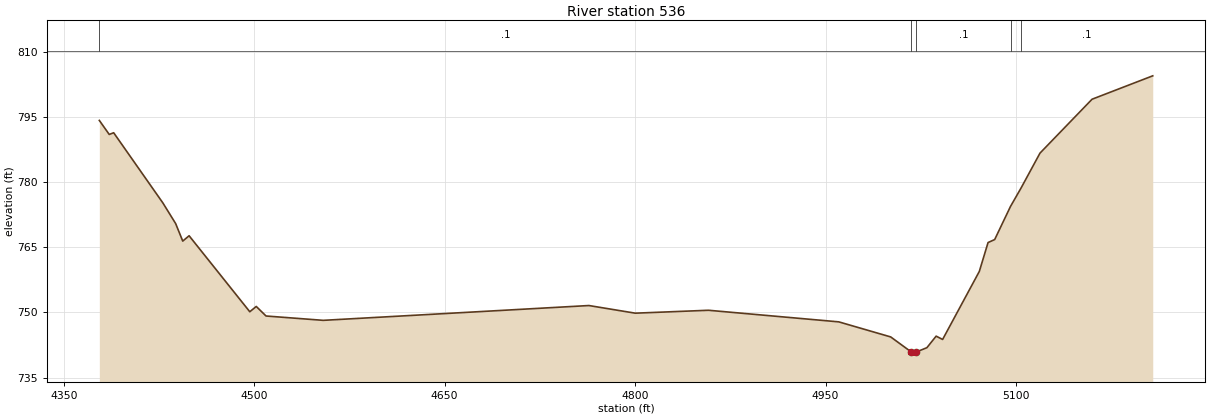
Type RM Length L Ch R = 1,536,0,0,0
BEGIN DESCRIPTION:
X19031
END DESCRIPTION:
XS GIS Cut Line= 4
      2199602.07     13787544.11      2199545.65     13787240.30
      2199328.64     13787103.58      2199072.58     13787038.48
#Sta/Elev= 30
  4378.0  794.23  4385.8  791.00  4389.3  791.39  4428.0  775.25  4438.1  770.48
  4443.7  766.44  4448.7  767.67  4496.5  750.17  4501.6  751.39  4509.3  749.19
  4554.4  748.19  4763.6  751.60  4800.1  749.84  4857.8  750.51  4960.4  747.84
  5001.3  744.37  5017.5  740.91  5017.7  740.41  5021.5  740.91  5029.8  741.89
  5037.1  744.55  5042.2  743.79  5071.1  759.45  5078.0  766.11  5083.2  766.79
  5095.7  774.44  5104.0  778.67  5118.9  786.70  5159.9  799.11  5207.7  804.50
#Mann=5,-1,0
  4378.0     0.1       0  5017.5    0.05       0  5021.5     0.1       0
  5095.7     0.1       0  5104.0     0.1       0
Bank Sta=5017.5,5021.5
Exp/Cntr=0.3,0.1

Chan Stop Cuts=-1