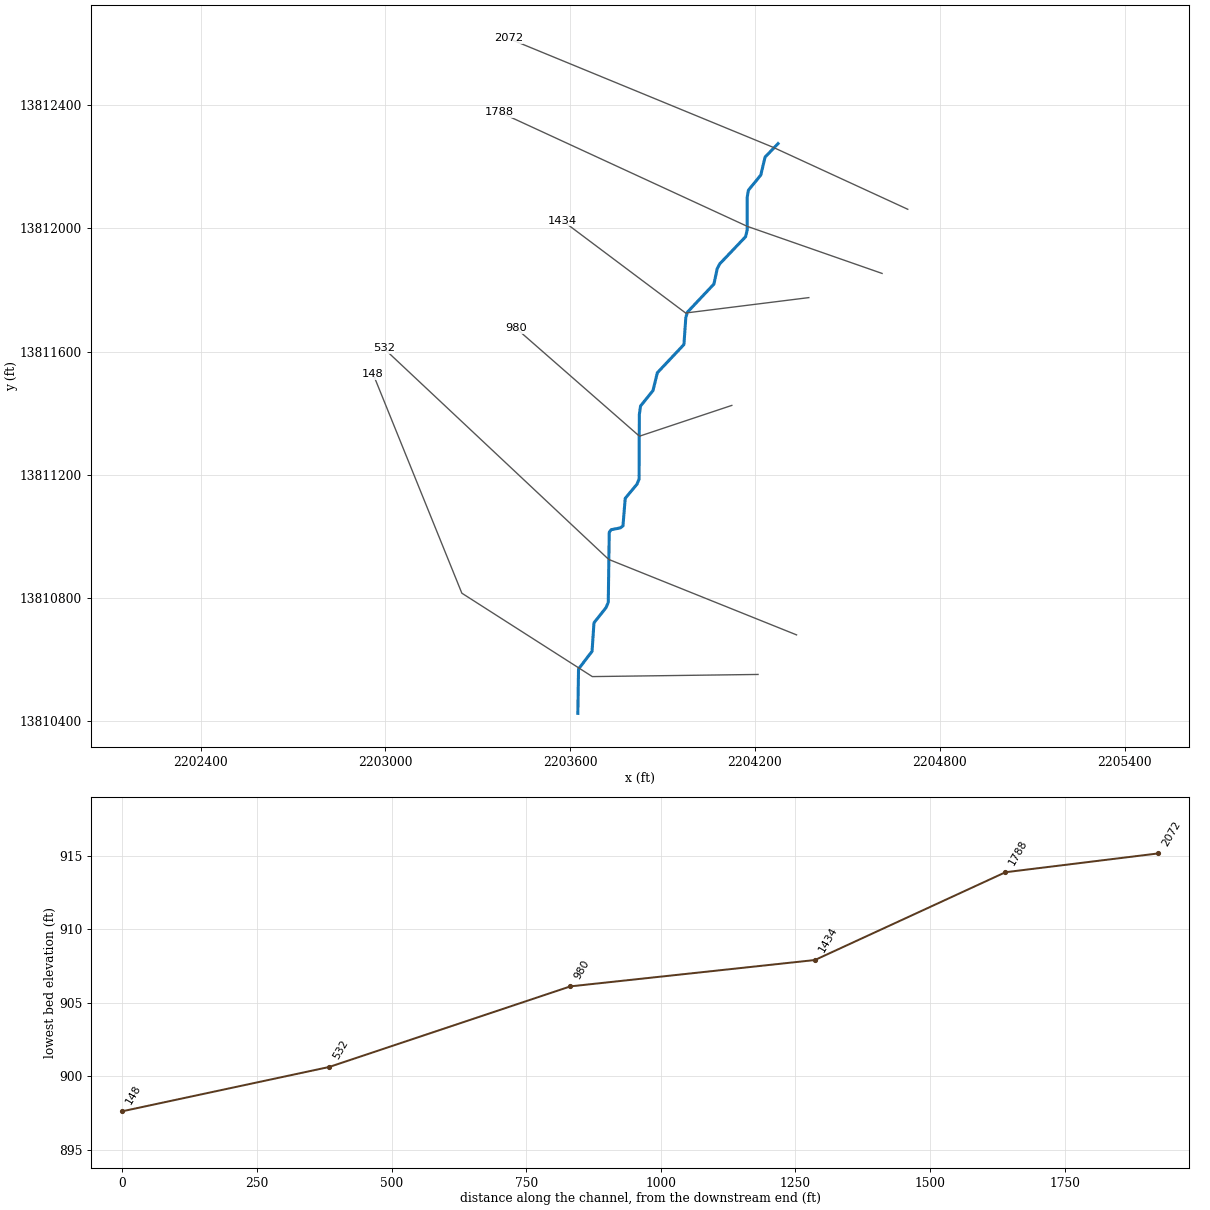
--- Dry Comal Creek Tributary 37.prj (project) ---

Proj Title=Dry Comal Creek Tributary 37 Base Level Engineering
Current Plan=p01
Default Exp/Contr=0.3,0.1
English Units
Geom File=g01
Flow File=f01
Plan File=p01
BEGIN DESCRIPTION:
Dry Comal Creek Tributary 37
END DESCRIPTION:

--- Dry Comal Creek Tributary 37.p01 (plan) ---

Plan Title=Multiple Run
Short Identifier=Multiple
Geom File=g01
Flow File=f01
Subcritical Flow
K Sum by GR= 0
Std Step Tol= 0.01
Critical Tol= 0.01
Num of Std Step Trials= 20
Max Error Tol= 0.3
Flow Tol Ratio= 0.001
Split Flow NTrial= 30
Split Flow Tol= 0.02
Split Flow Ratio= 0.02
Log Output Level= 0
Friction Slope Method= 1
Unsteady Friction Slope Method= 2
Unsteady Bridges Friction Slope Method= 1
Parabolic Critical Depth
Global Vel Dist=  1 , 1 , 1
Global Log Level= 0
CheckData=True
Encroach Param= -1, 0, 0, 0
BEGIN DESCRIPTION:
Multiple Run
END DESCRIPTION:

--- Dry Comal Creek Tributary 37.f01 (steady flow) ---

Flow Title=Multiple
Number of Profiles=7
Profile Names=10-year,25-year,50-year,1pct_min,100-year,1pct_plu,500-year
River Rch & RM= Dry Comal Creek ,Reach-1,2072
    1269    2162    3015    2035    4061    8102    7292
Boundary for River Rch & Prof#=Dry Comal Creek ,Reach-1,1
Up Type=0
Dn Type=3
Dn Slope=0.005
Boundary for River Rch & Prof#=Dry Comal Creek ,Reach-1,2
Up Type=0
Dn Type=3
Dn Slope=0.005
Boundary for River Rch & Prof#=Dry Comal Creek ,Reach-1,3
Up Type=0
Dn Type=3
Dn Slope=0.005
Boundary for River Rch & Prof#=Dry Comal Creek ,Reach-1,4
Up Type=0
Dn Type=3
Dn Slope=0.005
Boundary for River Rch & Prof#=Dry Comal Creek ,Reach-1,5
Up Type=0
Dn Type=3
Dn Slope=0.005
Boundary for River Rch & Prof#=Dry Comal Creek ,Reach-1,6
Up Type=0
Dn Type=3
Dn Slope=0.005
Boundary for River Rch & Prof#=Dry Comal Creek ,Reach-1,7
Up Type=0
Dn Type=3
Dn Slope=0.005

--- Dry Comal Creek Tributary 37.g01 (geometry) ---

Geom Title=Existing Conditions

River Reach=Dry Comal Creek ,Reach-1
Reach XY= 30
      2204275.00     13812275.00      2204232.91     13812231.15
      2204218.97     13812172.78      2204178.75     13812123.45
      2204174.81     13812100.08      2204175.02     13811994.99
      2204169.52     13811972.56      2204085.80     13811884.67
      2204077.54     13811868.95      2204066.82     13811818.96
      2203980.54     13811727.42      2203975.53     13811709.78
      2203969.46     13811622.58      2203883.16     13811531.05
      2203868.86     13811472.83      2203828.75     13811423.45
      2203824.64     13811395.15      2203823.78     13811185.50
      2203816.86     13811168.94      2203778.88     13811123.33
      2203771.44     13811033.50      2203762.76     13811027.21
      2203733.57     13811021.42      2203726.96     13811013.03
      2203723.78     13810785.50      2203716.86     13810768.94
      2203677.36     13810719.02      2203671.15     13810626.60
      2203627.22     13810569.08      2203625.00     13810425.00

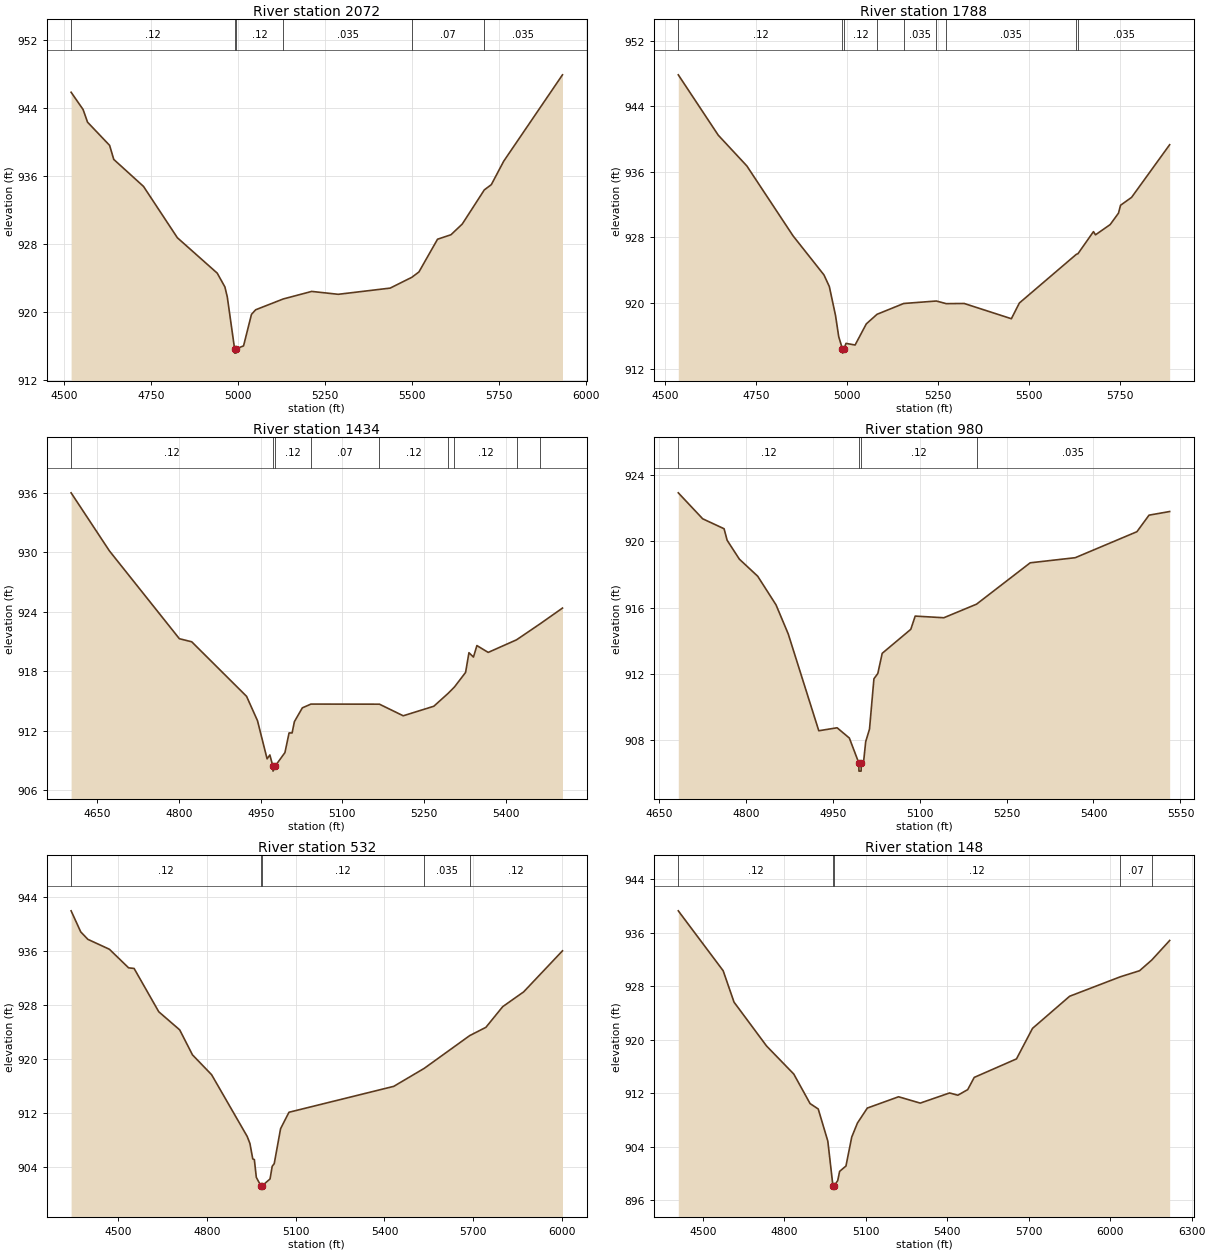
Type RM Length L Ch R = 1,2072,284,284,284
BEGIN DESCRIPTION:
X19040
END DESCRIPTION:
XS GIS Cut Line= 3
      2204696.25     13812061.82      2204258.77     13812263.19
      2203398.86     13812616.87
#Sta/Elev= 30
  4521.3  945.85  4555.7  943.82  4568.5  942.33  4631.9  939.60  4643.8  937.95
  4729.3  934.77  4826.6  928.73  4941.0  924.57  4963.0  922.95  4969.9  921.78
  4990.9  915.66  4991.2  915.16  4994.7  915.16  4994.9  915.66  5016.6  916.01
  5039.4  919.72  5051.4  920.26  5130.5  921.53  5212.4  922.42  5288.6  922.08
  5437.8  922.81  5500.0  924.08  5520.4  924.71  5573.8  928.56  5612.5  929.09
  5644.9  930.35  5708.3  934.37  5728.3  934.98  5763.9  937.74  5932.7  947.90
#Mann=6,-1,0
  4521.3    0.12       0  4990.9    0.05       0  4994.9    0.12       0
  5130.5   0.035       0  5500.0    0.07       0  5708.3   0.035       0
Bank Sta=4990.9,4994.9
Exp/Cntr=0.3,0.1

Type RM Length L Ch R = 1,1788,354,354,354
BEGIN DESCRIPTION:
Dry Comal Creek Tributary 37 4.0
END DESCRIPTION:
XS GIS Cut Line= 3
      2204612.90     13811853.49      2204175.43     13812006.25
      2203369.94     13812377.75
#Sta/Elev= 30
  4536.6  947.85  4646.5  940.48  4725.0  936.73  4852.1  928.19  4936.9  923.43
  4951.7  922.01  4968.7  918.48  4977.5  915.89  4987.8  914.38  4988.1  913.88
  4991.8  914.38  4997.6  915.07  5022.5  914.87  5053.3  917.45  5082.8  918.62
  5156.2  919.94  5245.9  920.24  5272.9  919.92  5322.3  919.94  5452.0  918.08
  5474.0  920.00  5630.8  925.95  5634.9  926.01  5677.6  928.71  5683.2  928.32
  5723.5  929.57  5746.4  930.97  5752.0  931.93  5782.3  932.89  5887.0  939.32
#Mann=9,-1,0
  4536.6    0.12       0  4987.8    0.05       0  4991.8    0.12       0
  5082.8    0.07       0  5156.2   0.035       0  5245.9    0.07       0
  5272.9   0.035       0  5630.8    0.07       0  5634.9   0.035       0
Bank Sta=4987.8,4991.8
Exp/Cntr=0.3,0.1

Type RM Length L Ch R = 1,1434,454,454,454
BEGIN DESCRIPTION:
Dry Comal Creek Tributary 37 3.0
END DESCRIPTION:
XS GIS Cut Line= 3
      2204374.96     13811775.00      2203975.00     13811725.00
      2203574.98     13812025.01
#Sta/Elev= 30
  4601.6  935.97  4672.1  930.11  4800.6  921.26  4823.3  920.95  4924.1  915.45
  4944.2  912.99  4961.8  909.15  4966.9  909.54  4972.4  908.41  4972.7  907.91
  4976.5  908.41  4994.6  909.78  5002.2  911.76  5007.8  911.76  5012.0  912.90
  5026.6  914.29  5042.4  914.67  5168.3  914.66  5212.0  913.49  5268.2  914.45
  5294.3  915.74  5306.1  916.39  5326.6  917.86  5332.8  919.85  5341.1  919.41
  5347.4  920.57  5368.2  919.88  5420.3  921.15  5463.8  922.77  5504.7  924.35
#Mann=9,-1,0
  4601.6    0.12       0  4972.4    0.05       0  4976.5    0.12       0
  5042.4    0.07       0  5168.3    0.12       0  5294.3   0.035       0
  5306.1    0.12       0  5420.3   0.035       0  5463.8    0.12       0
Bank Sta=4972.4,4976.5
Exp/Cntr=0.3,0.1

Type RM Length L Ch R = 1,980,448,448,448
BEGIN DESCRIPTION:
Dry Comal Creek Tributary 37 2.0
END DESCRIPTION:
XS GIS Cut Line= 3
      2204124.96     13811424.99      2203825.00     13811325.00
      2203424.99     13811675.01
#Sta/Elev= 30
  4683.7  922.94  4725.8  921.37  4762.7  920.77  4768.0  920.07  4789.1  918.93
  4820.7  917.90  4852.3  916.17  4873.4  914.41  4926.1  908.56  4957.7  908.74
  4978.8  908.12  4995.1  906.62  4995.4  906.12  4999.1  906.12  4999.3  906.62
  5003.2  906.62  5007.0  907.90  5013.6  908.66  5021.2  911.70  5027.9  912.02
  5035.5  913.24  5084.8  914.69  5092.4  915.49  5141.8  915.39  5198.2  916.21
  5290.8  918.71  5368.6  919.02  5474.9  920.59  5495.8  921.59  5531.4  921.81
#Mann=4,-1,0
  4683.7    0.12       0  4995.1    0.05       0  4999.3    0.12       0
  5198.2   0.035       0
Bank Sta=4995.1,4999.3
Exp/Cntr=0.3,0.1

Type RM Length L Ch R = 1,532,384,384,384
BEGIN DESCRIPTION:
Dry Comal Creek Tributary 37 1.0
END DESCRIPTION:
XS GIS Cut Line= 3
      2204335.15     13810679.86      2203725.00     13810925.00
      2202995.09     13811610.22
#Sta/Elev= 30
  4342.3  941.99  4374.8  938.86  4399.0  937.75  4471.6  936.28  4536.4  933.52
  4554.9  933.43  4638.3  926.99  4708.9  924.30  4752.0  920.59  4816.6  917.64
  4936.7  908.47  4946.0  907.41  4955.5  905.13  4960.9  905.03  4967.5  902.39
  4982.8  901.14  4983.1  900.64  4987.4  901.14  5013.8  902.15  5021.1  904.03
  5028.0  904.43  5049.4  909.62  5077.7  912.06  5431.4  915.91  5534.5  918.59
  5687.8  923.45  5742.5  924.68  5799.2  927.75  5870.0  929.95  6001.0  936.05
#Mann=5,-1,0
  4342.3    0.12       0  4982.8    0.05       0  4987.4    0.12       0
  5534.5   0.035       0  5687.8    0.12       0
Bank Sta=4982.8,4987.4
Exp/Cntr=0.3,0.1

Type RM Length L Ch R = 1,148,0,0,0
BEGIN DESCRIPTION:
X19039
END DESCRIPTION:
XS GIS Cut Line= 4
      2204210.16     13810551.39      2203671.96     13810544.44
      2203248.35     13810815.28      2202960.14     13811527.12
#Sta/Elev= 30
  4410.0  939.30  4575.2  930.33  4615.2  925.63  4735.2  919.05  4835.2  914.86
  4895.2  910.44  4925.2  909.63  4960.5  904.82  4979.3  898.13  4979.7  897.63
  4983.9  898.13  4996.9  898.91  5004.0  900.29  5027.3  901.09  5048.5  905.42
  5069.6  907.53  5106.0  909.77  5221.0  911.46  5300.7  910.51  5408.8  912.03
  5439.2  911.69  5475.5  912.53  5499.6  914.36  5655.1  917.13  5714.1  921.70
  5850.8  926.51  6037.1  929.42  6108.1  930.33  6153.3  931.94  6219.0  934.86
#Mann=5,-1,0
  4410.0    0.12       0  4979.3    0.05       0  4983.9    0.12       0
  6037.1    0.07       0  6153.3    0.12       0
Bank Sta=4979.3,4983.9
Exp/Cntr=0.3,0.1

Chan Stop Cuts=-1