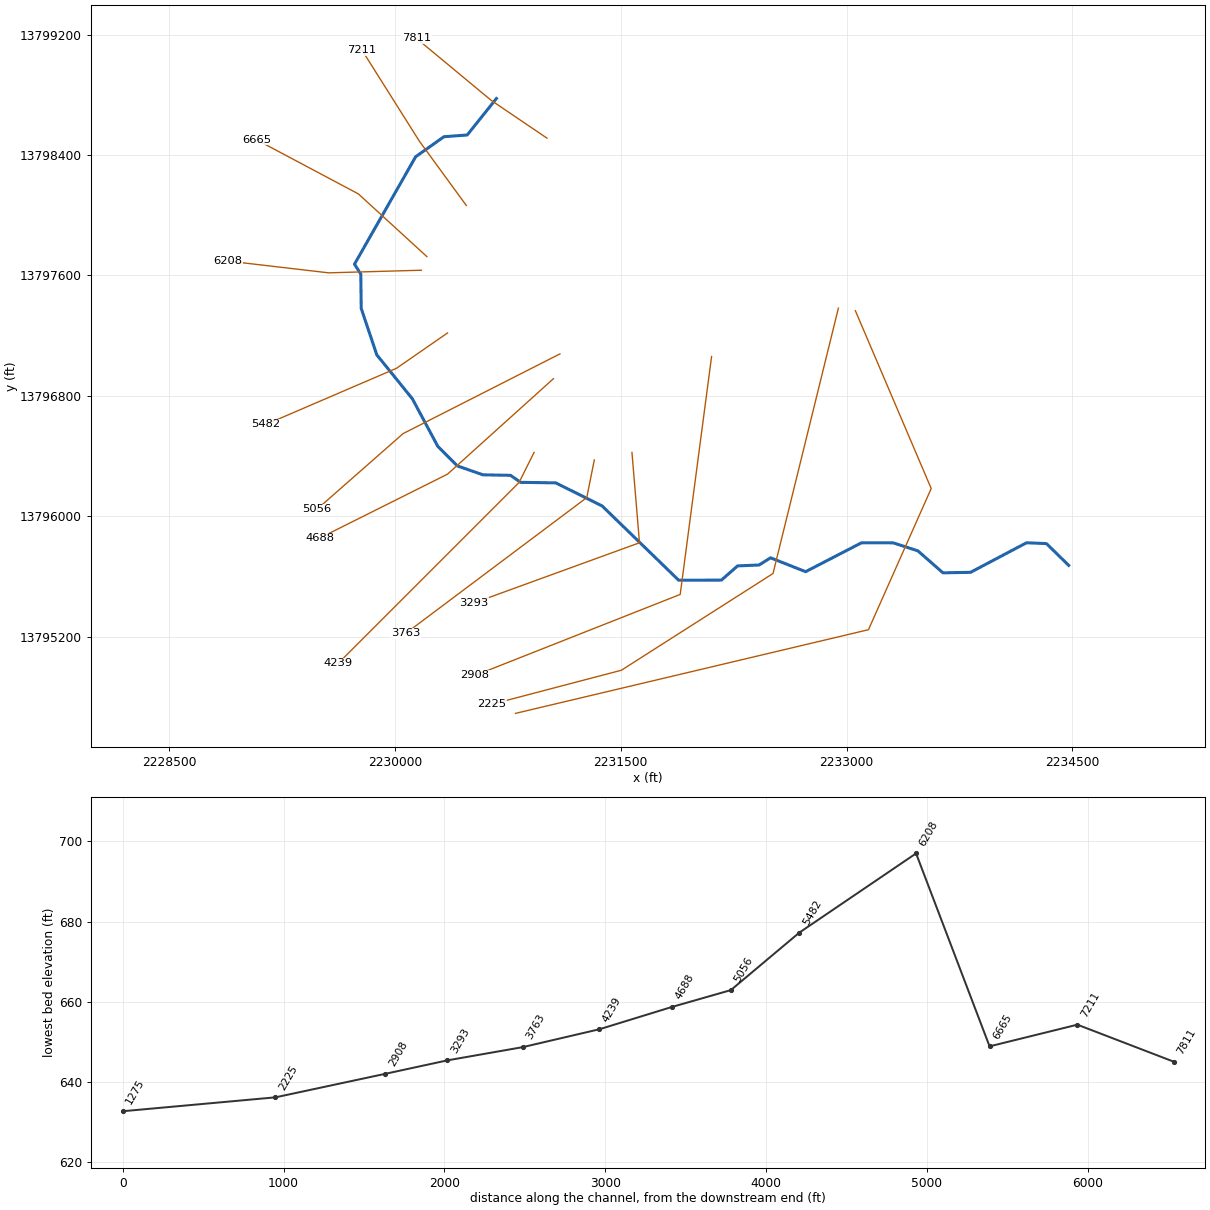
--- Dry Comal Creek Tributary 9.prj (project) ---

Proj Title=Dry Comal Creek Tributary 9 Base Level Engineering
Current Plan=p01
Default Exp/Contr=0.3,0.1
English Units
Geom File=g01
Flow File=f01
Plan File=p01
BEGIN DESCRIPTION:
Dry Comal Creek Tributary 9
END DESCRIPTION:

--- Dry Comal Creek Tributary 9.p01 (plan) ---

Plan Title=Multiple Run
Short Identifier=Multiple
Geom File=g01
Flow File=f01
Subcritical Flow
K Sum by GR= 0
Std Step Tol= 0.01
Critical Tol= 0.01
Num of Std Step Trials= 20
Max Error Tol= 0.3
Flow Tol Ratio= 0.001
Split Flow NTrial= 30
Split Flow Tol= 0.02
Split Flow Ratio= 0.02
Log Output Level= 0
Friction Slope Method= 1
Unsteady Friction Slope Method= 2
Unsteady Bridges Friction Slope Method= 1
Parabolic Critical Depth
Global Vel Dist=  1 , 1 , 1
Global Log Level= 0
CheckData=True
Encroach Param= -1, 0, 0, 0
BEGIN DESCRIPTION:
Multiple Run
END DESCRIPTION:

--- Dry Comal Creek Tributary 9.f01 (steady flow) ---

Flow Title=Multiple
Number of Profiles=7
Profile Names=10-year,25-year,50-year,1pct_min,100-year,1pct_plu,500-year
River Rch & RM= Dry Comal Creek ,Reach-1,7811
    1127    1910    2655    1788    3567    7118    6373
River Rch & RM= Dry Comal Creek ,Reach-1,6208
    1552    2671    3750    2547    5081   10139    9239
River Rch & RM= Dry Comal Creek ,Reach-1,2225
    2028    3534    5002    3420    6824   13617   12584
Boundary for River Rch & Prof#=Dry Comal Creek ,Reach-1,1
Up Type=0
Dn Type=3
Dn Slope=0.005
Boundary for River Rch & Prof#=Dry Comal Creek ,Reach-1,2
Up Type=0
Dn Type=3
Dn Slope=0.005
Boundary for River Rch & Prof#=Dry Comal Creek ,Reach-1,3
Up Type=0
Dn Type=3
Dn Slope=0.005
Boundary for River Rch & Prof#=Dry Comal Creek ,Reach-1,4
Up Type=0
Dn Type=3
Dn Slope=0.005
Boundary for River Rch & Prof#=Dry Comal Creek ,Reach-1,5
Up Type=0
Dn Type=3
Dn Slope=0.005
Boundary for River Rch & Prof#=Dry Comal Creek ,Reach-1,6
Up Type=0
Dn Type=3
Dn Slope=0.005
Boundary for River Rch & Prof#=Dry Comal Creek ,Reach-1,7
Up Type=0
Dn Type=3
Dn Slope=0.005

--- Dry Comal Creek Tributary 9.g01 (geometry) ---

Geom Title=Existing Conditions

River Reach=Dry Comal Creek ,Reach-1
Reach XY= 30
      2230675.00     13798775.00      2230481.21     13798532.81
      2230326.56     13798521.24      2230138.61     13798388.24
      2229732.53     13797675.01      2229774.34     13797609.84
      2229777.26     13797380.94      2229880.84     13797072.71
      2230116.86     13796781.06      2230285.78     13796465.32
      2230415.21     13796335.52      2230585.50     13796276.22
      2230769.06     13796272.74      2230835.50     13796226.22
      2231069.07     13796222.76      2231377.30     13796069.17
      2231885.43     13795576.05      2232169.14     13795577.07
      2232276.47     13795671.44      2232419.06     13795677.27
      2232495.10     13795725.10      2232728.31     13795633.02
      2233099.91     13795825.21      2233309.78     13795824.48
      2233473.50     13795771.39      2233640.16     13795625.38
      2233823.45     13795628.75      2234195.03     13795824.96
      2234327.45     13795819.55      2234475.00     13795675.00

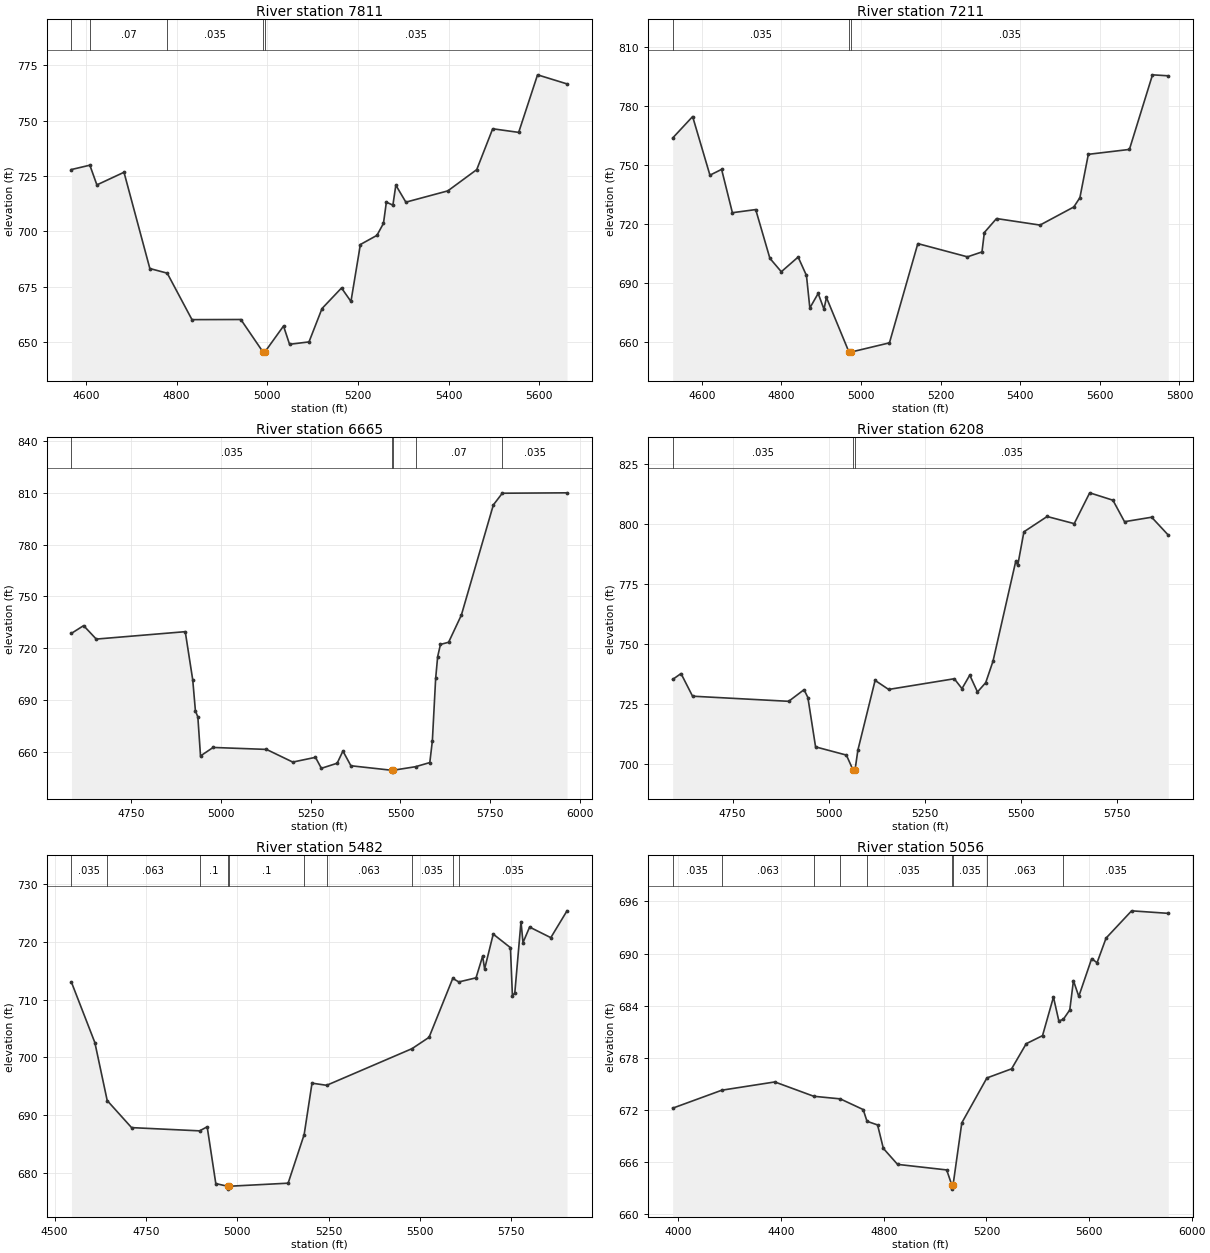
Type RM Length L Ch R = 1,7811,600,600,600
BEGIN DESCRIPTION:
X19050
END DESCRIPTION:
XS GIS Cut Line= 3
      2231011.03     13798511.64      2230640.99     13798762.19
      2230143.76     13799174.62
#Sta/Elev= 30
  4568.3  727.89  4608.9  729.85  4624.4  720.95  4684.2  726.65  4741.2  683.20
  4779.5  681.11  4834.1  660.13  4941.9  660.19  4990.8  645.51  4991.1  645.01
  4994.8  645.51  5036.0  657.25  5049.3  648.99  5092.2  650.08  5120.9  665.15
  5163.9  674.42  5184.7  668.33  5205.5  694.04  5242.0  698.17  5256.4  703.59
  5262.8  713.16  5277.2  711.81  5283.7  720.83  5305.8  713.16  5398.3  718.25
  5462.1  727.85  5497.3  746.29  5554.6  744.66  5596.2  770.64  5661.2  766.54
#Mann=5,-1,0
  4568.3   0.035       0  4608.9    0.07       0  4779.5   0.035       0
  4990.8   0.035       0  4994.8   0.035       0
Bank Sta=4990.8,4994.8
Exp/Cntr=0.3,0.1

Type RM Length L Ch R = 1,7211,546,546,546
BEGIN DESCRIPTION:
X19049
END DESCRIPTION:
XS GIS Cut Line= 3
      2230475.23     13798064.53      2230163.02     13798492.37
      2229781.41     13799097.55
#Sta/Elev= 30
  4526.7  763.70  4576.8  774.60  4620.3  744.78  4649.6  747.74  4676.7  725.69
  4735.3  727.28  4770.9  702.50  4799.6  695.66  4841.9  703.14  4862.8  693.75
  4871.3  677.23  4892.2  684.62  4906.8  676.62  4913.0  682.56  4969.7  654.76
  4969.9  654.26  4973.8  654.76  5071.3  659.49  5142.6  709.97  5267.3  703.24
  5303.8  705.74  5309.7  715.61  5340.3  722.72  5449.6  719.40  5534.5  728.61
  5549.8  733.34  5571.0  755.39  5674.2  757.88  5732.2  795.83  5771.8  795.33
#Mann=3,-1,0
  4526.7   0.035       0  4969.7   0.035       0  4973.8   0.035       0
Bank Sta=4969.7,4973.8
Exp/Cntr=0.3,0.1

Type RM Length L Ch R = 1,6665,457,457,457
BEGIN DESCRIPTION:
X19048
END DESCRIPTION:
XS GIS Cut Line= 3
      2230213.10     13797725.34      2229758.29     13798141.60
      2229083.77     13798500.06
#Sta/Elev= 30
  4583.6  728.62  4617.5  733.09  4652.7  725.30  4900.6  729.59  4921.5  701.62
  4928.9  683.74  4935.7  680.19  4943.1  657.64  4978.3  662.56  5126.9  661.42
  5200.1  654.09  5263.4  656.84  5279.7  650.48  5323.7  653.42  5339.8  660.48
  5362.0  651.96  5475.5  649.35  5475.7  648.85  5479.6  649.35  5542.1  651.41
  5581.8  653.81  5588.9  666.35  5598.1  702.52  5603.7  715.18  5611.5  722.21
  5634.2  723.47  5669.7  739.19  5758.8  802.97  5783.7  809.75  5964.0  809.98
#Mann=5,-1,0
  4583.6   0.035       0  5475.5   0.035       0  5479.6   0.035       0
  5542.1    0.07       0  5783.7   0.035       0
Bank Sta=5475.5,5479.6
Exp/Cntr=0.3,0.1

Type RM Length L Ch R = 1,6208,726,726,726
BEGIN DESCRIPTION:
X19047
END DESCRIPTION:
XS GIS Cut Line= 3
      2230176.67     13797634.82      2229560.36     13797617.46
      2228891.97     13797695.59
#Sta/Elev= 30
  4594.2  735.16  4615.9  737.60  4645.9  728.18  4896.0  726.05  4936.0  730.89
  4946.0  727.62  4966.0  707.09  5046.1  703.68  5063.5  697.50  5063.9  697.00
  5068.7  697.50  5076.1  705.75  5120.9  734.75  5156.1  730.99  5326.9  735.44
  5347.0  731.33  5367.2  736.94  5387.3  729.94  5408.7  733.81  5427.6  742.70
  5487.0  784.42  5492.0  782.61  5508.1  796.58  5568.5  802.95  5639.0  799.98
  5679.3  812.80  5739.7  809.73  5769.9  800.79  5840.5  802.65  5883.7  795.22
#Mann=3,-1,0
  4594.2   0.035       0  5063.5   0.035       0  5068.7   0.035       0
Bank Sta=5063.5,5068.7
Exp/Cntr=0.3,0.1

Type RM Length L Ch R = 1,5482,426,426,426
BEGIN DESCRIPTION:
X19046
END DESCRIPTION:
XS GIS Cut Line= 3
      2230350.30     13797218.16      2230011.75     13796983.78
      2229143.67     13796610.51
#Sta/Elev= 30
  4545.9  713.02  4610.0  702.58  4643.8  692.55  4710.5  687.87  4896.8  687.31
  4917.5  688.01  4941.1  678.19  4973.3  677.73  4973.7  677.23  4978.5  677.73
  5139.1  678.26  5183.0  686.67  5204.5  695.56  5244.6  695.19  5478.3  701.53
  5524.9  703.49  5589.8  713.68  5606.5  713.07  5653.5  713.78  5671.6  717.53
  5677.0  715.32  5700.6  721.34  5747.7  719.00  5753.1  710.70  5759.6  711.13
  5776.6  723.49  5782.1  719.88  5800.2  722.56  5858.2  720.73  5902.6  725.37
#Mann=10,-1,0
  4545.9   0.035       0  4643.8   0.063       0  4896.8     0.1       0
  4973.3    0.05       0  4978.5     0.1       0  5183.0   0.035       0
  5244.6   0.063       0  5478.3   0.035       0  5589.8   0.063       0
  5606.5   0.035       0
Bank Sta=4973.3,4978.5
Exp/Cntr=0.3,0.1

Type RM Length L Ch R = 1,5056,368,368,368
BEGIN DESCRIPTION:
X19045
END DESCRIPTION:
XS GIS Cut Line= 3
      2231096.84     13797079.28      2230055.15     13796549.75
      2229482.20     13796046.25
#Sta/Elev= 30
  3977.5  672.20  4169.1  674.27  4375.5  675.22  4527.3  673.57  4630.6  673.27
  4719.9  672.04  4734.8  670.69  4776.0  670.27  4798.5  667.57  4853.8  665.73
  5045.3  665.09  5065.0  663.38  5065.4  662.88  5070.3  663.38  5104.2  670.51
  5202.0  675.68  5298.3  676.73  5355.2  679.62  5418.8  680.55  5461.4  684.99
  5482.3  682.25  5499.6  682.42  5525.0  683.51  5539.3  686.88  5560.1  685.07
  5610.4  689.42  5631.3  688.94  5666.4  691.78  5766.0  694.92  5908.8  694.63
#Mann=9,-1,0
  3977.5   0.035       0  4169.1   0.063       0  4527.3   0.035       0
  4630.6   0.063       0  4734.8   0.035       0  5065.0   0.035       0
  5070.3   0.035       0  5202.0   0.063       0  5499.6   0.035       0
Bank Sta=5065,5070.3
Exp/Cntr=0.3,0.1

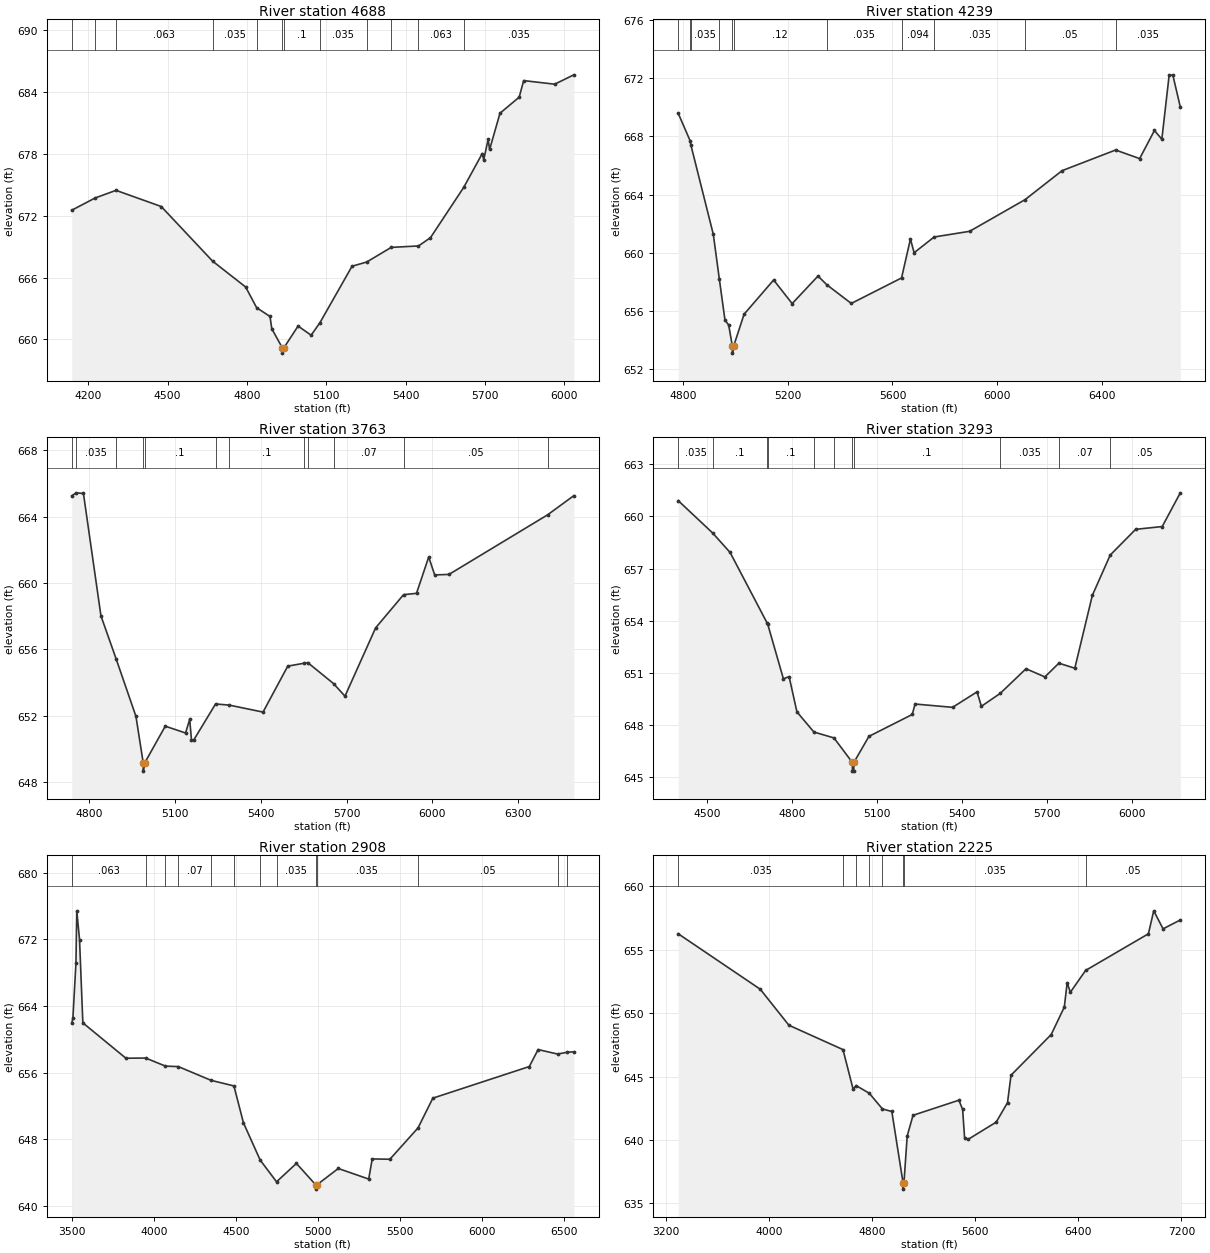
Type RM Length L Ch R = 1,4688,449,449,449
BEGIN DESCRIPTION:
X19044
END DESCRIPTION:
XS GIS Cut Line= 3
      2231053.42     13796914.34      2230350.29     13796280.66
      2229499.82     13795855.42
#Sta/Elev= 30
  4138.0  672.54  4226.3  673.73  4305.2  674.47  4476.1  672.90  4670.4  667.59
  4795.2  665.08  4836.7  663.07  4887.2  662.22  4893.9  661.03  4933.9  659.16
  4934.3  658.66  4939.2  659.16  4993.3  661.29  5042.6  660.40  5076.0  661.62
  5197.2  667.10  5252.7  667.51  5345.2  668.93  5448.3  669.07  5493.5  669.87
  5619.3  674.76  5689.2  678.04  5694.8  677.43  5711.5  679.42  5717.1  678.44
  5756.3  681.96  5828.9  683.52  5845.7  685.13  5963.1  684.78  6035.4  685.69
#Mann=12,-1,0
  4138.0   0.035       0  4226.3   0.094       0  4305.2   0.063       0
  4670.4   0.035       0  4836.7     0.1       0  4933.9    0.05       0
  4939.2     0.1       0  5076.0   0.035       0  5252.7   0.063       0
  5345.2   0.094       0  5448.3   0.063       0  5619.3   0.035       0
Bank Sta=4933.9,4939.2
Exp/Cntr=0.3,0.1

Type RM Length L Ch R = 1,4239,476,476,476
BEGIN DESCRIPTION:
Dry Comal Creek Tributary 9 3.0
END DESCRIPTION:
XS GIS Cut Line= 3
      2230925.01     13796425.01      2230825.00     13796225.00
      2229624.98     13795024.98
#Sta/Elev= 30
  4780.5  669.58  4825.8  667.70  4828.5  667.43  4914.7  661.27  4937.5  658.23
  4959.4  655.38  4973.4  655.05  4987.4  653.62  4987.9  653.12  4992.8  653.62
  5032.4  655.79  5145.5  658.14  5216.3  656.52  5315.2  658.41  5349.0  657.81
  5442.5  656.53  5634.8  658.28  5668.8  660.95  5682.9  660.01  5759.4  661.09
  5895.1  661.48  6107.0  663.65  6248.6  665.64  6453.7  667.06  6545.6  666.47
  6602.2  668.40  6630.5  667.80  6658.7  672.22  6672.9  672.18  6701.2  670.01
#Mann=11,-1,0
  4780.5   0.094       0  4825.8   0.063       0  4828.5   0.035       0
  4937.5    0.12       0  4987.4    0.05       0  4992.8    0.12       0
  5349.0   0.035       0  5634.8   0.094       0  5759.4   0.035       0
  6107.0    0.05       0  6453.7   0.035       0
Bank Sta=4987.4,4992.8
Exp/Cntr=0.3,0.1

Type RM Length L Ch R = 1,3763,470,470,470
BEGIN DESCRIPTION:
Dry Comal Creek Tributary 9 2.0
END DESCRIPTION:
XS GIS Cut Line= 3
      2231325.00     13796375.00      2231275.00     13796125.00
      2230074.96     13795224.97
#Sta/Elev= 30
  4739.6  665.26  4755.1  665.44  4780.4  665.40  4841.6  658.02  4894.2  655.45
  4964.0  651.96  4989.3  649.16  4989.7  648.66  4994.7  649.16  5066.4  651.37
  5137.3  650.96  5151.8  651.78  5158.1  650.53  5166.4  650.55  5242.2  652.71
  5290.3  652.64  5408.1  652.22  5494.6  654.99  5549.9  655.16  5564.7  655.20
  5654.5  653.94  5694.6  653.18  5801.8  657.30  5899.4  659.30  5944.6  659.38
  5987.3  661.57  6008.1  660.49  6058.1  660.52  6402.6  664.11  6494.6  665.27
#Mann=12,-1,0
  4739.6   0.063       0  4755.1   0.035       0  4894.2     0.1       0
  4989.3    0.05       0  4994.7     0.1       0  5242.2    0.12       0
  5290.3     0.1       0  5549.9    0.07       0  5564.7   0.035       0
  5654.5    0.07       0  5899.4    0.05       0  6402.6   0.035       0
Bank Sta=4989.3,4994.7
Exp/Cntr=0.3,0.1

Type RM Length L Ch R = 1,3293,385,385,385
BEGIN DESCRIPTION:
Dry Comal Creek Tributary 9 1.0
END DESCRIPTION:
XS GIS Cut Line= 3
      2231575.00     13796425.01      2231625.00     13795825.00
      2230524.97     13795424.99
#Sta/Elev= 30
  4397.9  660.91  4519.4  659.05  4581.0  657.93  4712.4  653.85  4713.9  653.80
  4769.2  650.66  4789.3  650.79  4816.9  648.76  4876.8  647.60  4947.8  647.26
  5012.6  645.85  5013.0  645.35  5017.6  645.35  5018.0  645.85  5071.2  647.35
  5224.1  648.61  5234.1  649.21  5366.4  649.02  5452.9  649.91  5468.2  649.08
  5534.5  649.82  5625.8  651.24  5692.3  650.77  5741.8  651.56  5798.0  651.27
  5859.9  655.46  5923.0  657.78  6012.8  659.26  6106.6  659.42  6170.5  661.36
#Mann=11,-1,0
  4397.9   0.035       0  4519.4     0.1       0  4712.4    0.07       0
  4713.9     0.1       0  4876.8   0.035       0  4947.8     0.1       0
  5012.6    0.05       0  5018.0     0.1       0  5534.5   0.035       0
  5741.8    0.07       0  5923.0    0.05       0
Bank Sta=5012.6,5018
Exp/Cntr=0.3,0.1

Type RM Length L Ch R = 1,2908,683,683,683
BEGIN DESCRIPTION:
X19043
END DESCRIPTION:
XS GIS Cut Line= 3
      2232103.76     13797061.88      2231895.43     13795482.05
      2230532.56     13794943.84
#Sta/Elev= 30
  3499.8  661.94  3506.7  662.56  3525.2  669.14  3530.3  675.44  3547.1  671.98
  3567.3  661.98  3829.5  657.73  3950.1  657.75  4070.8  656.78  4149.4  656.72
  4348.7  655.07  4487.6  654.40  4545.7  649.97  4647.7  645.49  4747.4  642.88
  4868.4  645.09  4986.8  642.50  4987.2  642.00  4992.2  642.50  5123.4  644.48
  5308.8  643.21  5330.3  645.63  5437.8  645.59  5609.4  649.36  5699.5  652.93
  6287.2  656.73  6340.9  658.77  6459.4  658.23  6519.3  658.45  6558.6  658.50
#Mann=13,-1,0
  3499.8   0.063       0  3950.1    0.07       0  4070.8   0.035       0
  4149.4    0.07       0  4348.7   0.063       0  4487.6   0.094       0
  4647.7   0.063       0  4747.4   0.035       0  4986.8   0.035       0
  4992.2   0.035       0  5609.4    0.05       0  6459.4   0.035       0
  6519.3    0.05       0
Bank Sta=4986.8,4992.2
Exp/Cntr=0.3,0.1

Type RM Length L Ch R = 1,2225,950,950,950
BEGIN DESCRIPTION:
X19042
END DESCRIPTION:
XS GIS Cut Line= 4
      2232945.78     13797383.09      2232511.75     13795620.93
      2231504.81     13794978.57      2230645.46     13794752.89
#Sta/Elev= 30
  3293.1  656.26  3929.7  651.89  4152.3  649.05  4572.1  647.13  4650.4  644.02
  4674.3  644.29  4776.0  643.69  4878.5  642.45  4951.2  642.25  5038.4  636.63
  5038.9  636.13  5045.4  636.63  5070.6  640.32  5115.9  641.95  5471.8  643.14
  5500.8  642.42  5516.0  640.19  5543.1  640.05  5761.4  641.41  5849.4  642.95
  5876.5  645.11  6188.7  648.32  6290.2  650.48  6312.5  652.40  6337.2  651.65
  6455.6  653.37  6943.1  656.26  6984.5  658.07  7056.9  656.65  7190.8  657.35
#Mann=8,-1,0
  3293.1   0.035       0  4572.1   0.063       0  4674.3   0.094       0
  4776.0   0.063       0  4878.5   0.035       0  5038.4   0.035       0
  5045.4   0.035       0  6455.6    0.05       0
Bank Sta=5038.4,5045.4
Exp/Cntr=0.3,0.1

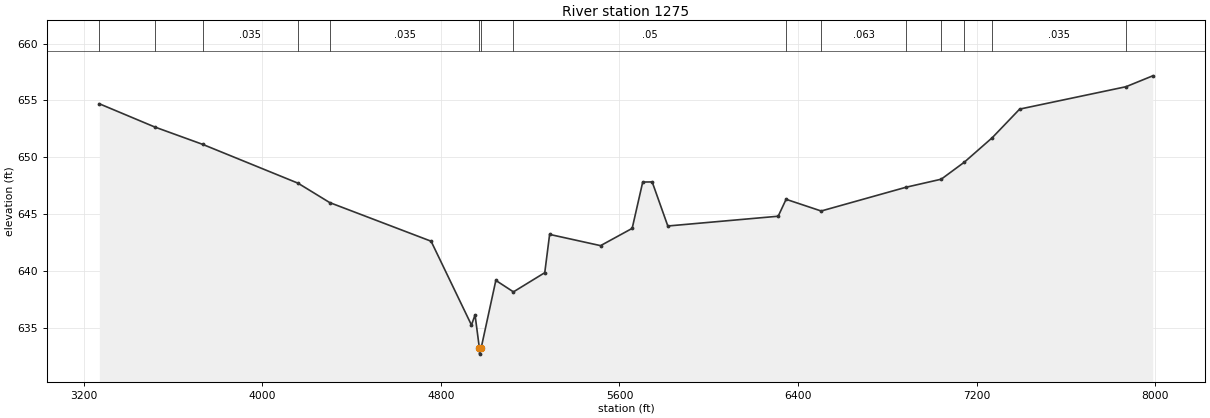
Type RM Length L Ch R = 1,1275,0,0,0
BEGIN DESCRIPTION:
X19041
END DESCRIPTION:
XS GIS Cut Line= 4
      2233058.61     13797365.76      2233562.10     13796185.17
      2233145.43     13795247.67      2230801.66     13794692.11
#Sta/Elev= 30
  3270.3  654.70  3519.2  652.65  3732.6  651.13  4160.0  647.71  4302.2  646.00
  4756.2  642.60  4937.0  635.22  4953.1  636.11  4972.7  633.16  4973.2  632.66
  4980.0  633.16  5046.2  639.15  5125.0  638.14  5265.3  639.83  5287.1  643.20
  5515.3  642.21  5656.8  643.73  5704.1  647.81  5746.4  647.82  5816.5  643.94
  6310.8  644.80  6346.2  646.29  6503.4  645.26  6883.1  647.35  7041.1  648.06
  7144.6  649.56  7269.4  651.71  7392.3  654.23  7868.4  656.20  7988.4  657.16
#Mann=15,-1,0
  3270.3   0.035       0  3519.2    0.07       0  3732.6   0.035       0
  4160.0   0.063       0  4302.2   0.035       0  4972.7   0.035       0
  4980.0   0.035       0  5125.0    0.05       0  6346.2   0.035       0
  6503.4   0.063       0  6883.1   0.094       0  7041.1   0.035       0
  7144.6   0.094       0  7269.4   0.035       0  7868.4    0.05       0
Bank Sta=4972.7,4980
Exp/Cntr=0.3,0.1

Chan Stop Cuts=-1