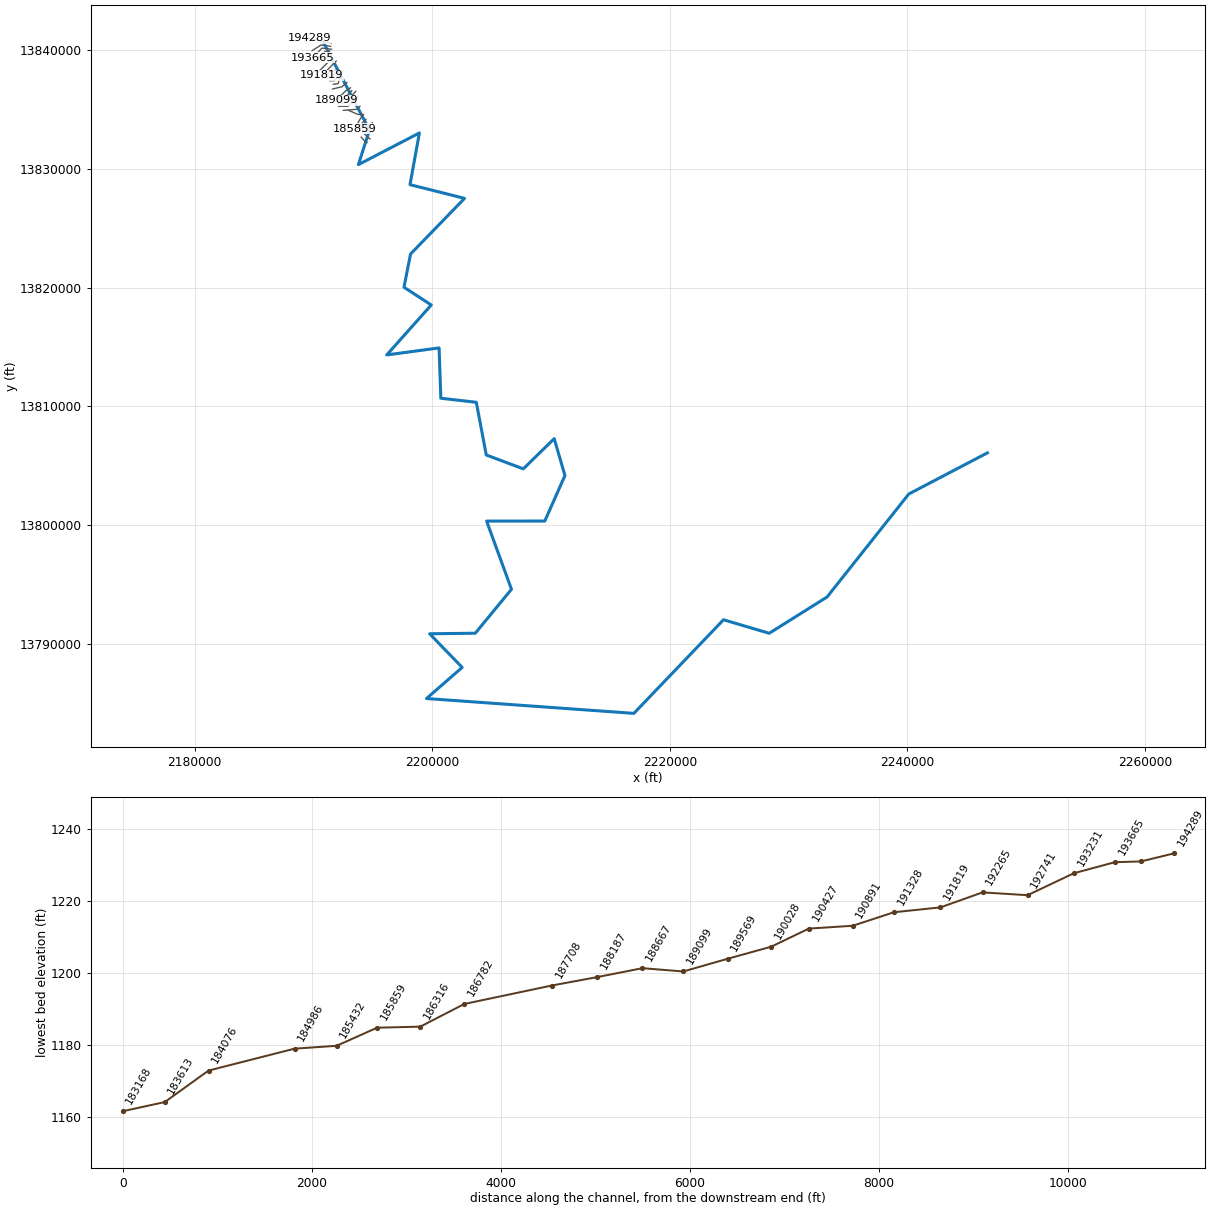
--- Dry Comal Creek.prj (project) ---

Proj Title=Dry Comal Creek Base Level Engineering
Current Plan=p01
Default Exp/Contr=0.3,0.1
English Units
Geom File=g01
Flow File=f01
Plan File=p01
Y Axis Title=Elevation
X Axis Title(PF)=Main Channel Distance
X Axis Title(XS)=Station
BEGIN DESCRIPTION:
Dry Comal Creek
END DESCRIPTION:
DSS Export Rating Curves= 0
DSS Export Rating Curve Sorted= 0
DSS Export Volume Flow Curves= 0
DXF OffsetX= 0
DXF OffsetY= 0
DXF ScaleX= 1
DXF ScaleY= 10

--- Dry Comal Creek.p01 (plan) ---

Plan Title=Multiple Run
Short Identifier=Multiple
Geom File=g01
Flow File=f01
Subcritical Flow
K Sum by GR= 0
Std Step Tol= 0.01
Critical Tol= 0.01
Num of Std Step Trials= 20
Max Error Tol= 0.3
Flow Tol Ratio= 0.001
Split Flow NTrial= 30
Split Flow Tol= 0.02
Split Flow Ratio= 0.02
Log Output Level= 0
Friction Slope Method= 1
Unsteady Friction Slope Method= 2
Unsteady Bridges Friction Slope Method= 1
Parabolic Critical Depth
Global Vel Dist=  1 , 1 , 1
Global Log Level= 0
CheckData=True
Encroach Param= -1, 0, 0, 0
BEGIN DESCRIPTION:
Multiple Run
END DESCRIPTION:

--- Dry Comal Creek.f01 (steady flow) ---

Flow Title=Multiple
Program Version=4.10
Number of Profiles= 7
Profile Names=10-year,25-year,50-year,1pct_min,100-year,1pct_plu,500-year
River Rch & RM=Dry Comal Creek,Reach-1         ,194289
     874    1457    2003    1335    2663    5313    4655
River Rch & RM=Dry Comal Creek,Reach-1         ,193941
    1310    2218    3079    2067    4124    8229    7325
River Rch & RM=Dry Comal Creek,Reach-1         ,189569
    1468    2486    3449    2312    4613    9204    8171
River Rch & RM=Dry Comal Creek,Reach-1         ,184986
    1537    2604    3615    2424    4836    9649    8571
River Rch & RM=Dry Comal Creek,Reach-1         ,181828
    1802    3078    4294    2892    5771   11514   10323
River Rch & RM=Dry Comal Creek,Reach-1         ,180477
    2050    3507    4898    3299    6583   13134   11780
River Rch & RM=Dry Comal Creek,Reach-1         ,171409
    2713    4691    6599    4473    8925   17809   16176
River Rch & RM=Dry Comal Creek,Reach-1         ,161807
    2877    4987    7027    4770    9517   18989   17298
River Rch & RM=Dry Comal Creek,Reach-1         ,161348
    3040    5279    7447    5060   10096   20143   18386
River Rch & RM=Dry Comal Creek,Reach-1         ,159997
    3274    5695    8044    5471   10916   21780   19917
River Rch & RM=Dry Comal Creek,Reach-1         ,156020
    3317    5763    8132    5525   11024   21996   20072
River Rch & RM=Dry Comal Creek,Reach-1         ,148169
    3728    6505    9207    6272   12514   24969   22907
River Rch & RM=Dry Comal Creek,Reach-1         ,145467
    3834    6706    9507    6487   12944   25826   23771
River Rch & RM=Dry Comal Creek,Reach-1         ,143284
    3842    6715    9516    6490   12950   25838   23761
River Rch & RM=Dry Comal Creek,Reach-1         ,139594
    4346    7630   10844    7415   14795   29520   27286
River Rch & RM=Dry Comal Creek,Reach-1         ,136613
    4494    7893   11220    7674   15311   30550   28248
River Rch & RM=Dry Comal Creek,Reach-1         ,132191
    4577    8043   11438    7825   15612   31150   28816
River Rch & RM=Dry Comal Creek,Reach-1         ,127496
    4655    8180   11633    7957   15877   31679   29303
River Rch & RM=Dry Comal Creek,Reach-1         ,122276
    4962    8736   12439    8518   16996   33912   31436
River Rch & RM=Dry Comal Creek,Reach-1         ,120094
    5167    9113   12992    8908   17774   35463   32953
River Rch & RM=Dry Comal Creek,Reach-1         ,116751
    5349    9444   13474    9244   18444   36800   34235
River Rch & RM=Dry Comal Creek,Reach-1         ,110780
    5421    9567   13645    9358   18672   37255   34633
River Rch & RM=Dry Comal Creek,Reach-1         ,108254
    7059   12563   18023   12425   24792   49466   46463
River Rch & RM=Dry Comal Creek,Reach-1         ,102149
    7115   12651   18137   12496   24933   49747   46661
River Rch & RM=Dry Comal Creek,Reach-1         ,97239
    6956   12386   17770   12250   24443   48770   45819
River Rch & RM=Dry Comal Creek,Reach-1         ,92346
    7068   12584   18054   12445   24830   49543   46534
River Rch & RM=Dry Comal Creek,Reach-1         ,86259
    3248    5618    7901    5347   10669   21287   19282
River Rch & RM=Dry Comal Creek,Reach-1         ,79003
    3193    5513    7744    5234   10443   20837   18825
River Rch & RM=Dry Comal Creek,Reach-1         ,70499
    3235    5590    7856    5312   10599   21148   19125
River Rch & RM=Dry Comal Creek,Reach-1         ,67505
    3256    5627    7908    5347   10669   21288   19250
River Rch & RM=Dry Comal Creek,Reach-1         ,66252
    5848   10320   14714   10081   20114   40133   37247
River Rch & RM=Dry Comal Creek,Reach-1         ,62723
    6230   11015   15726   10787   21523   42945   39951
River Rch & RM=Dry Comal Creek,Reach-1         ,57022
    6463   11447   16364   11240   22426   44745   41733
River Rch & RM=Dry Comal Creek,Reach-1         ,52927
    8019   14293   20523   14153   28238   56343   52961
River Rch & RM=Dry Comal Creek,Reach-1         ,47618
    8327   14880   21403   14787   29503   58866   55533
River Rch & RM=Dry Comal Creek,Reach-1         ,46270
    8557   15280   21968   15168   30263   60383   56890
River Rch & RM=Dry Comal Creek,Reach-1         ,45337
    8940   15972   22973   15866   31656   63163   59541
River Rch & RM=Dry Comal Creek,Reach-1         ,38024
    8993   16066   23105   15956   31836   63521   59867
River Rch & RM=Dry Comal Creek,Reach-1         ,37208
    9800   17537   25253   17458   34833   69500   65636
River Rch & RM=Dry Comal Creek,Reach-1         ,29019
    9998   17904   25793   17839   35593   71017   67124
River Rch & RM=Dry Comal Creek,Reach-1         ,26414
   10773   19251   27701   19134   38178   76175   71782
River Rch & RM=Dry Comal Creek,Reach-1         ,23691
   11047   19744   28415   19629   39166   78146   73652
River Rch & RM=Dry Comal Creek,Reach-1         ,19865
   11458   20489   29498   20384   40671   81150   76524
River Rch & RM=Dry Comal Creek,Reach-1         ,16639
   11560   20675   29769   20573   41049   81903   77252
River Rch & RM=Dry Comal Creek,Reach-1         ,15456
   11585   20708   29805   20589   41081   81967   77245
River Rch & RM=Dry Comal Creek,Reach-1         ,13346
   11670   20858   30020   20737   41375   82554   77788
River Rch & RM=Dry Comal Creek,Reach-1         ,12223
   11710   20918   30095   20781   41463   82730   77891
River Rch & RM=Dry Comal Creek,Reach-1         ,8151
   11735   20949   30127   20792   41486   82776   77859
River Rch & RM=Dry Comal Creek,Reach-1         ,4731
   11750   20975   30162   20815   41532   82867   77932
Boundary for River Rch & Prof#=Dry Comal Creek,Reach-1         , 1
Up Type= 0
Dn Type= 3
Dn Slope=0.005
Boundary for River Rch & Prof#=Dry Comal Creek,Reach-1         , 2
Up Type= 0
Dn Type= 3
Dn Slope=0.005
Boundary for River Rch & Prof#=Dry Comal Creek,Reach-1         , 3
Up Type= 0
Dn Type= 3
Dn Slope=0.005
Boundary for River Rch & Prof#=Dry Comal Creek,Reach-1         , 4
Up Type= 0
Dn Type= 3
Dn Slope=0.005
Boundary for River Rch & Prof#=Dry Comal Creek,Reach-1         , 5
Up Type= 0
Dn Type= 3
Dn Slope=0.005
Boundary for River Rch & Prof#=Dry Comal Creek,Reach-1         , 6
Up Type= 0
Dn Type= 3
Dn Slope=0.005
Boundary for River Rch & Prof#=Dry Comal Creek,Reach-1         , 7
Up Type= 0
Dn Type= 3
Dn Slope=0.005
DSS Import GetInterval= 0
DSS Import GetPeak= 0
DSS Import FillOption= 0

--- Dry Comal Creek.g01 (geometry) ---

Geom Title=Existing Conditions
Program Version=4.10

River Reach=Dry Comal Creek ,Reach-1
Reach XY= 30
        2190775.       13840775.      2194722.94     13833269.15
      2193791.63     13830358.29        2198925.       13833025.
      2198133.14     13828668.94      2202723.94     13827514.56
      2198178.75     13822823.45      2197628.39     13820026.41
      2199922.76     13818530.93        2196175.       13814325.
      2200581.06     13814916.86      2200728.67     13810676.58
      2203714.28      13810334.7      2204551.03     13805898.17
      2207669.14     13804727.07      2210269.22     13807273.11
       2211173.8      13804164.5      2209477.29     13800330.84
      2204580.46     13800327.45      2206672.76     13794580.93
       2203627.3     13790880.83      2199785.07       13790835.
      2202525.21     13787999.91      2199522.57     13785380.52
      2216973.52     13784128.56       2224515.2     13792014.53
      2228364.56     13790876.05       2233231.5     13793932.72
      2240107.86     13802608.72        2246725.       13806075.

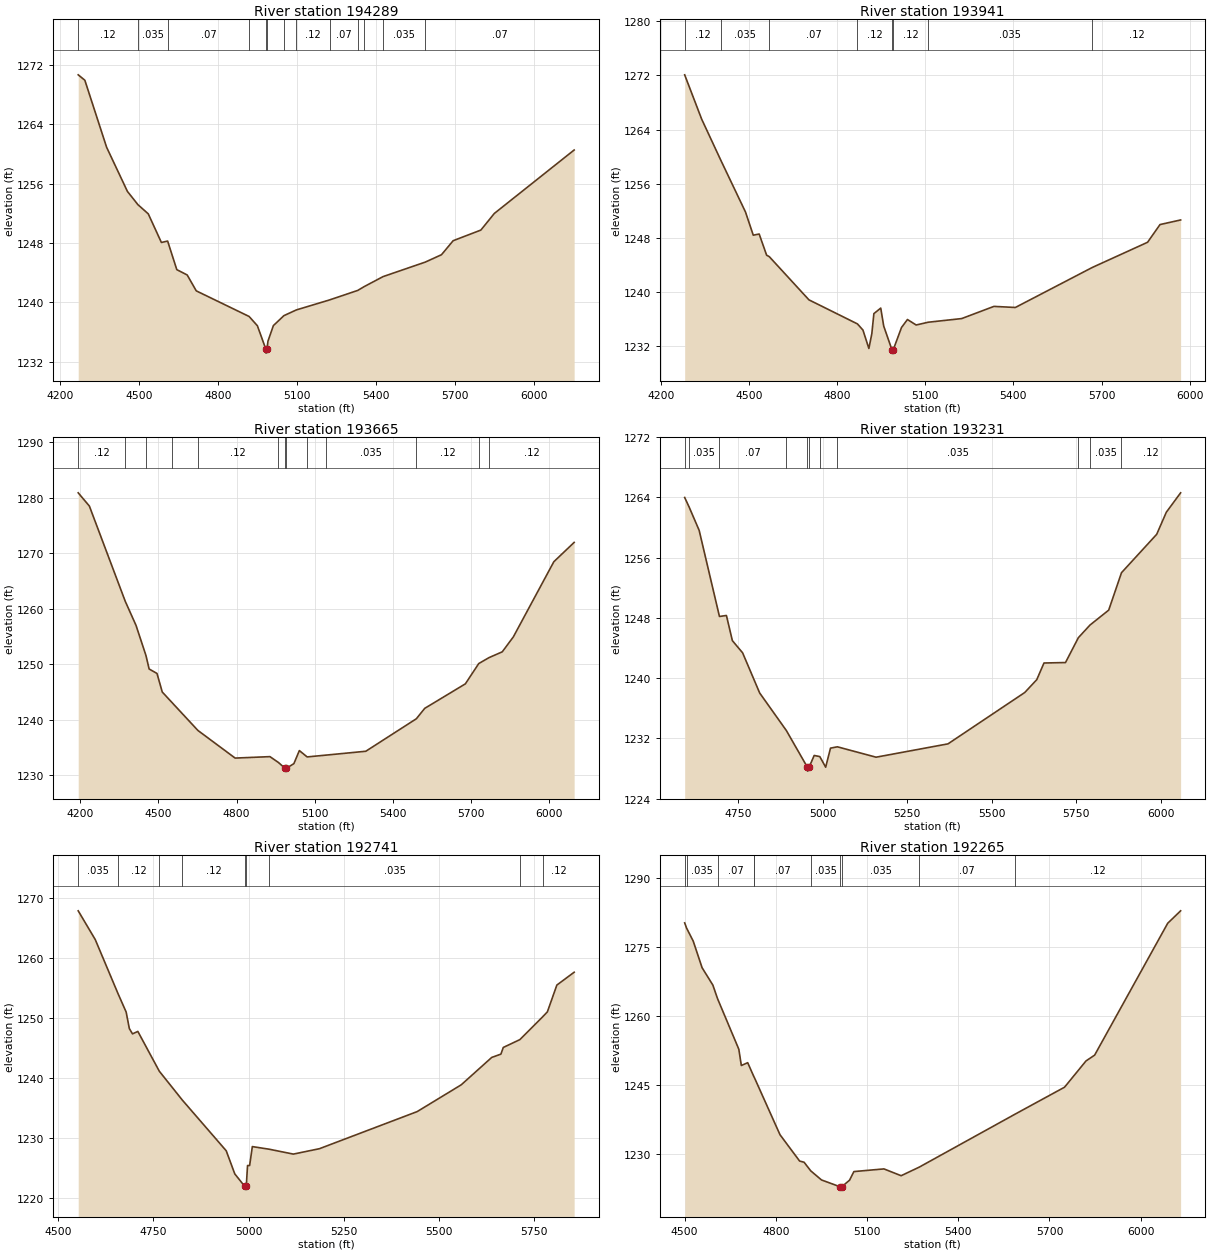
Type RM Length L Ch R = 1 ,194289  ,348,348,348
BEGIN DESCRIPTION:
Dry Comal Creek 275.0
END DESCRIPTION:
XS GIS Cut Line= 3
      2191479.28     13840560.05      2190775.89     13840754.22
      2189648.77     13840995.74
#Sta/Elev= 30
  4269.4 1270.67  4294.6 1269.94  4377.2 1260.91  4456.2 1254.96  4496.2 1253.17
  4535.3 1251.94  4585.1 1248.08  4608.8 1248.27  4643.6 1244.42  4683.1  1243.7
  4717.5 1241.56    4918 1238.11  4949.5 1236.86  4981.9 1233.67  4982.1 1233.17
  4985.9 1233.67  4989.6 1234.78  5010.2 1236.88  5050.1 1238.22  5097.3 1238.99
  5223.5 1240.34  5330.4 1241.62  5355.3 1242.14  5426.4 1243.48  5587.1 1245.44
  5648.3 1246.43  5692.6 1248.32  5797.7 1249.75  5848.8 1251.99  6151.8 1260.54
#Mann= 13 ,-1 , 0
  4269.4     .12       0  4496.2    .035       0  4608.8     .07       0
    4918     .12       0  4981.9     .05       0  4985.9     .12       0
  5050.1    .035       0  5097.3     .12       0  5223.5     .07       0
  5330.4    .035       0  5355.3     .07       0  5426.4    .035       0
  5587.1     .07       0
Bank Sta=4981.9,4985.9
XS Rating Curve= 0 ,0
Exp/Cntr=0.3,0.1

Type RM Length L Ch R = 1 ,193941  ,276,276,276
BEGIN DESCRIPTION:
X18976
END DESCRIPTION:
XS GIS Cut Line= 3
      2191446.28     13840321.95      2190647.67     13840431.85
      2189900.34     13839962.93
#Sta/Elev= 30
  4280.8 1272.09  4338.7 1265.53  4404.7 1259.38  4487.8 1251.81  4514.3 1248.38
  4534.4 1248.55  4559.8 1245.42  4568.9  1245.2  4703.8 1238.82    4869 1235.26
  4887.7 1234.35  4907.9 1231.63    4918 1233.83  4924.9 1236.78  4948.3  1237.6
  4958.4 1234.94  4986.4 1231.44  4986.7 1230.94  4990.9 1231.44    5019 1234.73
  5039.2 1235.91  5068.9  1235.1    5110 1235.51    5224 1236.05  5333.6 1237.85
  5406.6 1237.69  5668.2  1243.6  5856.7 1247.33  5899.1 1249.95  5969.2 1250.63
#Mann= 8 ,-1 , 0
  4280.8     .12       0  4404.7    .035       0  4568.9     .07       0
    4869     .12       0  4986.4     .05       0  4990.9     .12       0
    5110    .035       0  5668.2     .12       0
Bank Sta=4986.4,4990.9
XS Rating Curve= 0 ,0
Exp/Cntr=0.3,0.1

Type RM Length L Ch R = 1 ,193665  ,434,434,434
BEGIN DESCRIPTION:
Dry Comal Creek 274.0
END DESCRIPTION:
XS GIS Cut Line= 3
      2191524.98       13840075.        2190725.       13840175.
      2189974.99     13839374.99
#Sta/Elev= 30
  4192.6 1280.86  4235.4 1278.48  4373.1 1261.32  4414.3    1257  4452.5 1251.56
  4464.7 1249.13  4494.9 1248.32  4515.1 1244.98  4552.2  1243.1  4651.8 1238.06
  4794.7 1233.08  4928.3 1233.34    4961 1232.28  4986.5 1231.23  4986.8 1230.73
    4991 1231.23  5020.1 1232.08  5041.1 1234.43    5071 1233.29  5144.8 1233.62
    5296 1234.31  5489.9 1240.16  5522.2 1242.04    5678 1246.45  5729.4 1250.11
    5769 1251.18  5819.6 1252.22  5862.1 1254.91  6017.5 1268.45  6095.4 1271.93
#Mann= 13 ,-1 , 0
  4192.6     .12       0  4373.1    .035       0  4452.5     .07       0
  4552.2    .035       0  4651.8     .12       0    4961    .035       0
  4986.5    .035       0    4991    .035       0    5071     .07       0
  5144.8    .035       0  5489.9     .12       0  5729.4     .07       0
    5769     .12       0
Bank Sta=4986.5,4991
XS Rating Curve= 0 ,0
Exp/Cntr=0.3,0.1

Type RM Length L Ch R = 1 ,193231  ,490,490,490
BEGIN DESCRIPTION:
Dry Comal Creek 273.0
END DESCRIPTION:
XS GIS Cut Line= 3
      2191374.96     13839924.99        2190975.       13839875.
      2190174.99     13839174.99
#Sta/Elev= 30
    4592    1264  4605.1 1262.74  4634.8 1259.64  4694.8  1248.2  4715.4 1248.33
    4733 1244.99  4763.3 1243.37  4813.7 1238.04  4892.6 1233.05    4955 1228.16
  4955.3 1227.66  4959.6 1228.16  4974.9 1229.74  4991.5 1229.59  5008.8 1228.18
  5023.1 1230.71  5043.4 1230.89  5157.8 1229.51  5370.4 1231.28  5597.3  1238.1
  5632.9 1239.81  5654.2 1242.02  5717.8 1242.08  5755.8 1245.38  5790.2 1247.06
  5845.5 1249.04  5883.3 1254.01  5987.4 1259.11  6015.8 1262.04  6058.1 1264.62
#Mann= 11 ,-1 , 0
    4592     .12       0  4605.1    .035       0  4694.8     .07       0
  4892.6    .035       0    4955     .05       0  4959.6    .035       0
  4991.5     .07       0  5043.4    .035       0  5755.8     .07       0
  5790.2    .035       0  5883.3     .12       0
Bank Sta=4955,4959.6
XS Rating Curve= 0 ,0
Exp/Cntr=0.3,0.1

Type RM Length L Ch R = 1 ,192741  ,476,476,476
BEGIN DESCRIPTION:
Dry Comal Creek 272.0
END DESCRIPTION:
XS GIS Cut Line= 3
      2191474.99       13839625.        2191075.       13839425.
      2190275.01       13839125.
#Sta/Elev= 30
  4552.7 1267.87  4597.4 1263.09  4657.1  1254.1  4678.5 1251.03  4686.9 1248.27
  4695.2 1247.39  4709.2  1247.8  4765.6 1241.17    4826 1236.37  4941.2 1227.93
  4963.6 1224.09  4989.2 1222.05  4989.5 1221.55  4993.8 1222.05  4997.1 1225.48
  5002.6 1225.48  5009.7 1228.63  5054.1 1228.19  5117.4 1227.38  5185.9 1228.28
  5442.2 1234.45  5557.9 1238.91    5638 1243.47  5662.1 1244.02  5668.3 1245.13
  5711.7 1246.43  5772.1 1250.26    5784 1251.05  5808.9 1255.51  5854.3 1257.65
#Mann= 9 ,-1 , 0
  4552.7    .035       0  4657.1     .12       0  4765.6    .035       0
    4826     .12       0  4989.2     .05       0  4993.8     .12       0
  5054.1    .035       0  5711.7     .07       0  5772.1     .12       0
Bank Sta=4989.2,4993.8
XS Rating Curve= 0 ,0
Exp/Cntr=0.3,0.1

Type RM Length L Ch R = 1 ,192265  ,446,446,446
BEGIN DESCRIPTION:
Dry Comal Creek 271.0
END DESCRIPTION:
XS GIS Cut Line= 3
      2191674.99     13839324.99        2191275.       13839025.
      2190474.97     13838224.97
#Sta/Elev= 30
    4500 1280.28  4506.1 1279.17  4528.1 1276.31  4557.3 1270.52  4592.7 1266.74
  4608.4 1263.74  4678.1 1252.78  4686.4 1249.23  4707.3 1249.85  4727.9 1246.77
  4728.8 1246.68  4813.5 1234.18  4878.1 1228.44  4892.7 1228.19  4914.7 1226.31
    4950 1224.33  5011.7 1222.83  5012.1 1222.33  5016.5 1222.83  5042.4 1224.28
  5056.6 1226.15  5155.5 1226.73  5212.1 1225.25  5271.7 1227.12  5585.6  1238.6
  5749.5 1244.51  5820.2 1250.23  5848.5 1251.49  6088.9 1280.19  6131.4  1282.9
#Mann= 10 ,-1 , 0
    4500     .12       0  4506.1    .035       0  4608.4     .07       0
  4727.9    .035       0  4728.8     .07       0  4914.7    .035       0
  5011.7    .035       0  5016.5    .035       0  5271.7     .07       0
  5585.6     .12       0
Bank Sta=5011.7,5016.5
XS Rating Curve= 0 ,0
Exp/Cntr=0.3,0.1

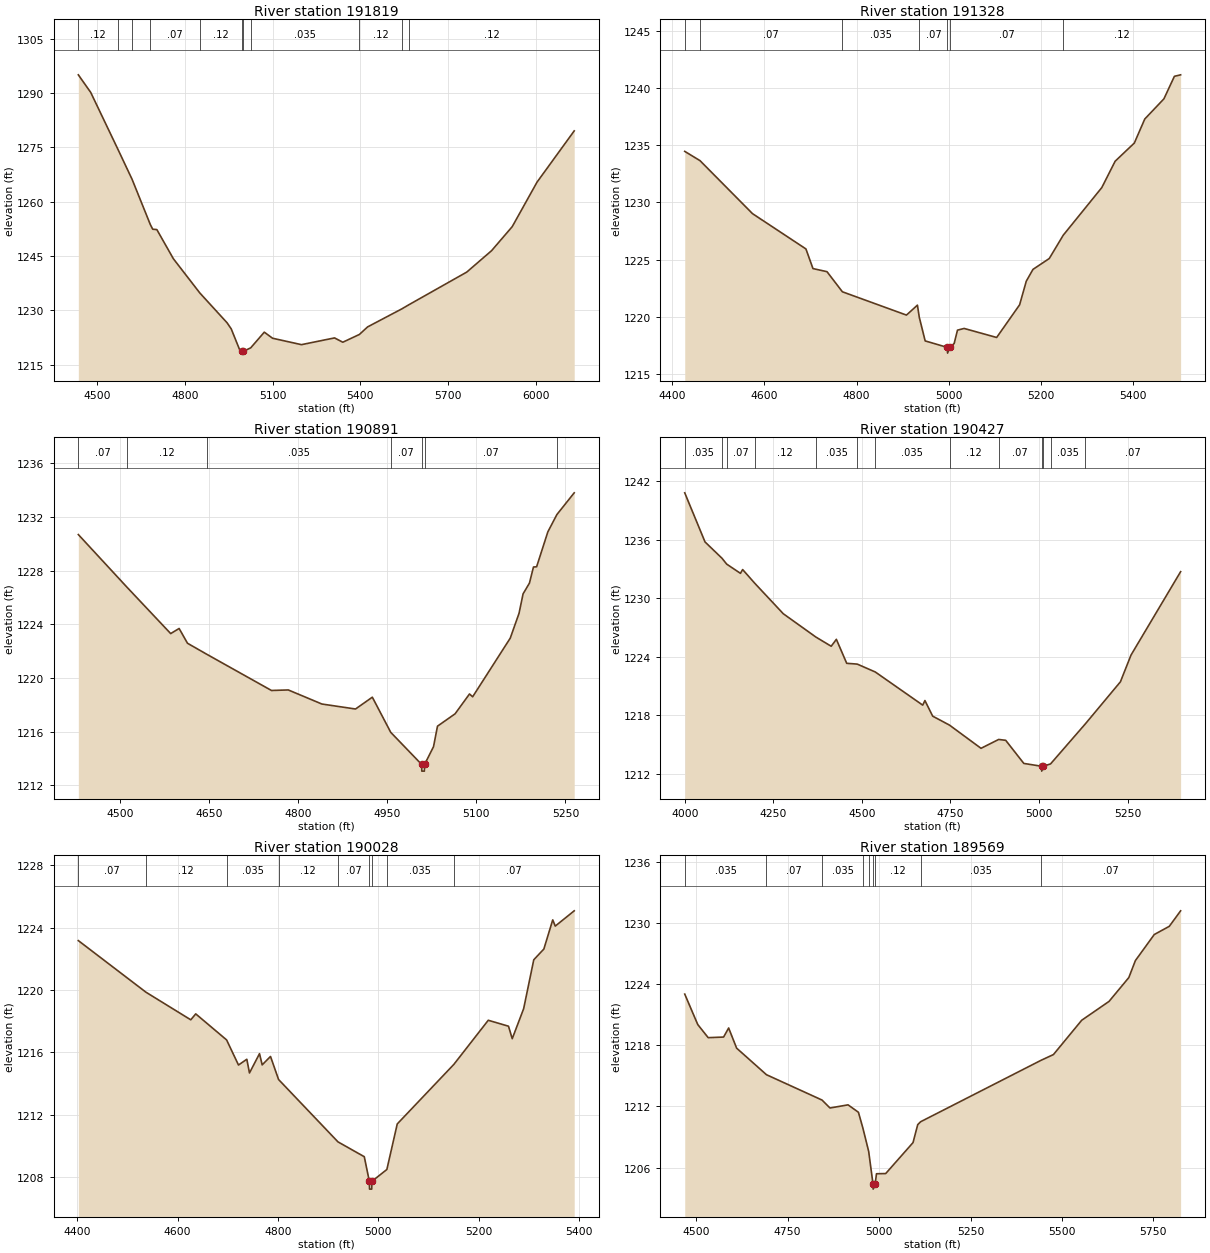
Type RM Length L Ch R = 1 ,191819  ,491,491,491
BEGIN DESCRIPTION:
Dry Comal Creek 270.0
END DESCRIPTION:
XS GIS Cut Line= 3
      2191924.98     13839074.98        2191525.       13838675.
      2190725.02     13837875.02
#Sta/Elev= 30
  4434.8 1295.01  4477.2 1290.15  4571.2 1274.29  4618.9 1266.13    4681  1253.7
  4689.3 1252.38  4703.5 1252.27    4760 1244.23  4850.7 1234.76  4943.9 1226.53
    4958 1224.86  4986.3  1219.2  4994.5 1218.66  4994.9 1218.16  4999.3 1218.66
  5024.6 1219.61  5071.2 1223.95  5099.5 1222.27  5198.4  1220.5  5311.6 1222.36
  5339.9 1221.17  5396.7 1223.32  5424.7  1225.4  5541.9 1230.38  5565.6  1231.5
  5764.1 1240.54    5849 1246.45  5919.7 1253.09  6004.5 1265.37  6131.8 1279.53
#Mann= 11 ,-1 , 0
  4434.8     .12       0  4571.2    .035       0  4618.9     .12       0
    4681     .07       0  4850.7     .12       0  4994.5     .05       0
  4999.3     .12       0  5024.6    .035       0  5396.7     .12       0
  5541.9     .07       0  5565.6     .12       0
Bank Sta=4994.5,4999.3
XS Rating Curve= 0 ,0
Exp/Cntr=0.3,0.1

Type RM Length L Ch R = 1 ,191328  ,437,437,437
BEGIN DESCRIPTION:
Dry Comal Creek 269.0
END DESCRIPTION:
XS GIS Cut Line= 3
      2192039.31     13838323.71      2191462.94     13838226.49
      2191075.03     13837925.02
#Sta/Elev= 30
  4427.3 1234.47  4460.4 1233.66  4574.3 1229.02  4690.2 1225.93  4705.5 1224.21
  4735.9 1223.94  4769.3 1222.18  4908.3 1220.14  4932.1 1221.01  4936.2 1219.94
  4948.9 1217.88  4997.1 1217.31  4997.5 1216.81  5002.1 1217.31  5011.8 1217.65
    5019 1218.82  5033.4 1218.97    5104 1218.18  5153.8 1221.04  5168.3 1223.11
  5182.8 1224.14  5218.1 1225.09  5248.4 1227.13  5332.1  1231.3  5361.1 1233.61
  5402.7  1235.2  5425.3  1237.3  5466.9 1239.07  5489.6 1241.04  5503.1 1241.17
#Mann= 7 ,-1 , 0
  4427.3    .035       0  4460.4     .07       0  4769.3    .035       0
  4936.2     .07       0  4997.1     .05       0  5002.1     .07       0
  5248.4     .12       0
Bank Sta=4997.1,5002.1
XS Rating Curve= 0 ,0
Exp/Cntr=0.3,0.1

Type RM Length L Ch R = 1 ,190891  ,464,464,464
BEGIN DESCRIPTION:
Dry Comal Creek 268.0
END DESCRIPTION:
XS GIS Cut Line= 3
      2191974.98     13838224.98        2191575.       13837825.
      2191325.02     13837725.01
#Sta/Elev= 30
  4429.8 1230.68    4511 1226.79  4585.3  1223.3  4599.5 1223.68  4613.6 1222.58
  4647.2 1221.73    4755 1219.06  4783.3  1219.1  4839.9 1218.05  4896.5 1217.68
  4924.8 1218.56  4955.8 1215.94  5007.8 1213.55  5008.1 1213.05  5012.4 1213.05
  5012.8 1213.55  5027.8 1214.87  5034.5  1216.4  5064.1 1217.32  5088.4  1218.8
  5093.7 1218.59    5157 1222.96  5171.8 1224.81  5178.6 1226.26  5189.3 1227.06
  5196.1 1228.26  5201.4 1228.28  5220.3 1230.88  5235.5 1232.17  5264.7 1233.79
#Mann= 7 ,-1 , 0
  4429.8     .07       0    4511     .12       0  4647.2    .035       0
  4955.8     .07       0  5007.8     .05       0  5012.8     .07       0
  5235.5     .12       0
Bank Sta=5007.8,5012.8
XS Rating Curve= 0 ,0
Exp/Cntr=0.3,0.1

Type RM Length L Ch R = 1 ,190427  ,399,399,399
BEGIN DESCRIPTION:
Dry Comal Creek 267.0
END DESCRIPTION:
XS GIS Cut Line= 3
        2192375.       13838225.        2191775.       13837425.
        2191375.       13837425.
#Sta/Elev= 30
  3999.7 1240.81    4057 1235.77  4105.1 1234.09    4118  1233.5    4157 1232.55
  4163.2 1232.94  4197.2 1231.54  4277.8 1228.41  4369.7 1226.02  4413.2 1225.07
  4427.8 1225.78    4457 1223.32  4486.7 1223.24  4537.7 1222.43  4671.6 1219.03
  4677.8  1219.5  4699.7  1217.9  4747.2 1216.98  4836.2  1214.6  4886.1 1215.51
  4905.9 1215.42    4957 1213.05  5007.1 1212.76  5007.5 1212.26  5012.2 1212.76
  5032.5    1213    5131 1217.12  5229.7 1221.42  5259.7 1224.17  5399.7 1232.72
#Mann= 13 ,-1 , 0
  3999.7    .035       0  4105.1     .12       0    4118     .07       0
  4197.2     .12       0  4369.7    .035       0  4486.7     .07       0
  4537.7    .035       0  4747.2     .12       0  4886.1     .07       0
  5007.1     .05       0  5012.2     .07       0  5032.5    .035       0
    5131     .07       0
Bank Sta=5007.1,5012.2
XS Rating Curve= 0 ,0
Exp/Cntr=0.3,0.1

Type RM Length L Ch R = 1 ,190028  ,459,459,459
BEGIN DESCRIPTION:
Dry Comal Creek 266.0
END DESCRIPTION:
XS GIS Cut Line= 3
      2192274.98     13837724.96        2192075.       13837175.
        2191675.       13837125.
#Sta/Elev= 30
  4402.3 1223.16  4537.1 1219.85  4626.4 1218.08  4636.3 1218.46  4697.8 1216.79
  4721.5 1215.18  4738.1 1215.55  4743.4 1214.67  4763.4 1215.91  4768.7 1215.19
  4785.3 1215.73  4801.4 1214.25  4919.8 1210.25  4972.2  1209.3  4982.3 1207.72
  4982.7 1207.22    4987 1207.22  4987.4 1207.72  5017.2 1208.48  5037.9  1211.4
  5150.7 1215.22  5219.3 1218.05  5259.6 1217.67  5267.1 1216.87  5289.8 1218.79
    5310 1221.93  5330.1 1222.62  5347.8 1224.49  5352.8 1224.09  5390.6 1225.07
#Mann= 9 ,-1 , 0
  4402.3     .07       0  4537.1     .12       0  4697.8    .035       0
  4801.4     .12       0  4919.8     .07       0  4982.3     .05       0
  4987.4     .07       0  5017.2    .035       0  5150.7     .07       0
Bank Sta=4982.3,4987.4
XS Rating Curve= 0 ,0
Exp/Cntr=0.3,0.1

Type RM Length L Ch R = 1 ,189569  ,470,470,470
BEGIN DESCRIPTION:
Dry Comal Creek 265.0
END DESCRIPTION:
XS GIS Cut Line= 3
      2192825.01     13837275.01        2192425.       13836925.
      2191625.04     13836725.01
#Sta/Elev= 30
  4468.5 1223.04  4504.1 1220.05  4532.6 1218.76  4574.8 1218.82  4588.6 1219.71
  4610.4 1217.73    4692 1215.12    4844 1212.63  4865.7 1211.85  4915.1 1212.16
  4943.5 1211.43  4955.6 1209.89  4971.5 1207.59  4983.4 1204.38  4983.8 1203.88
  4989.2 1204.38  4992.9 1205.39  5018.1 1205.41  5092.8 1208.45  5105.7 1210.22
  5113.6  1210.5  5442.6 1216.53  5476.8  1217.1  5554.1 1220.47  5628.8 1222.32
  5682.9 1224.66  5700.9 1226.33  5752.5 1228.89  5793.7  1229.7  5824.6 1231.22
#Mann= 9 ,-1 , 0
  4468.5    .035       0    4692     .07       0    4844    .035       0
  4955.6     .07       0  4971.5     .12       0  4983.4     .05       0
  4989.2     .12       0  5113.6    .035       0  5442.6     .07       0
Bank Sta=4983.4,4989.2
XS Rating Curve= 0 ,0
Exp/Cntr=0.3,0.1

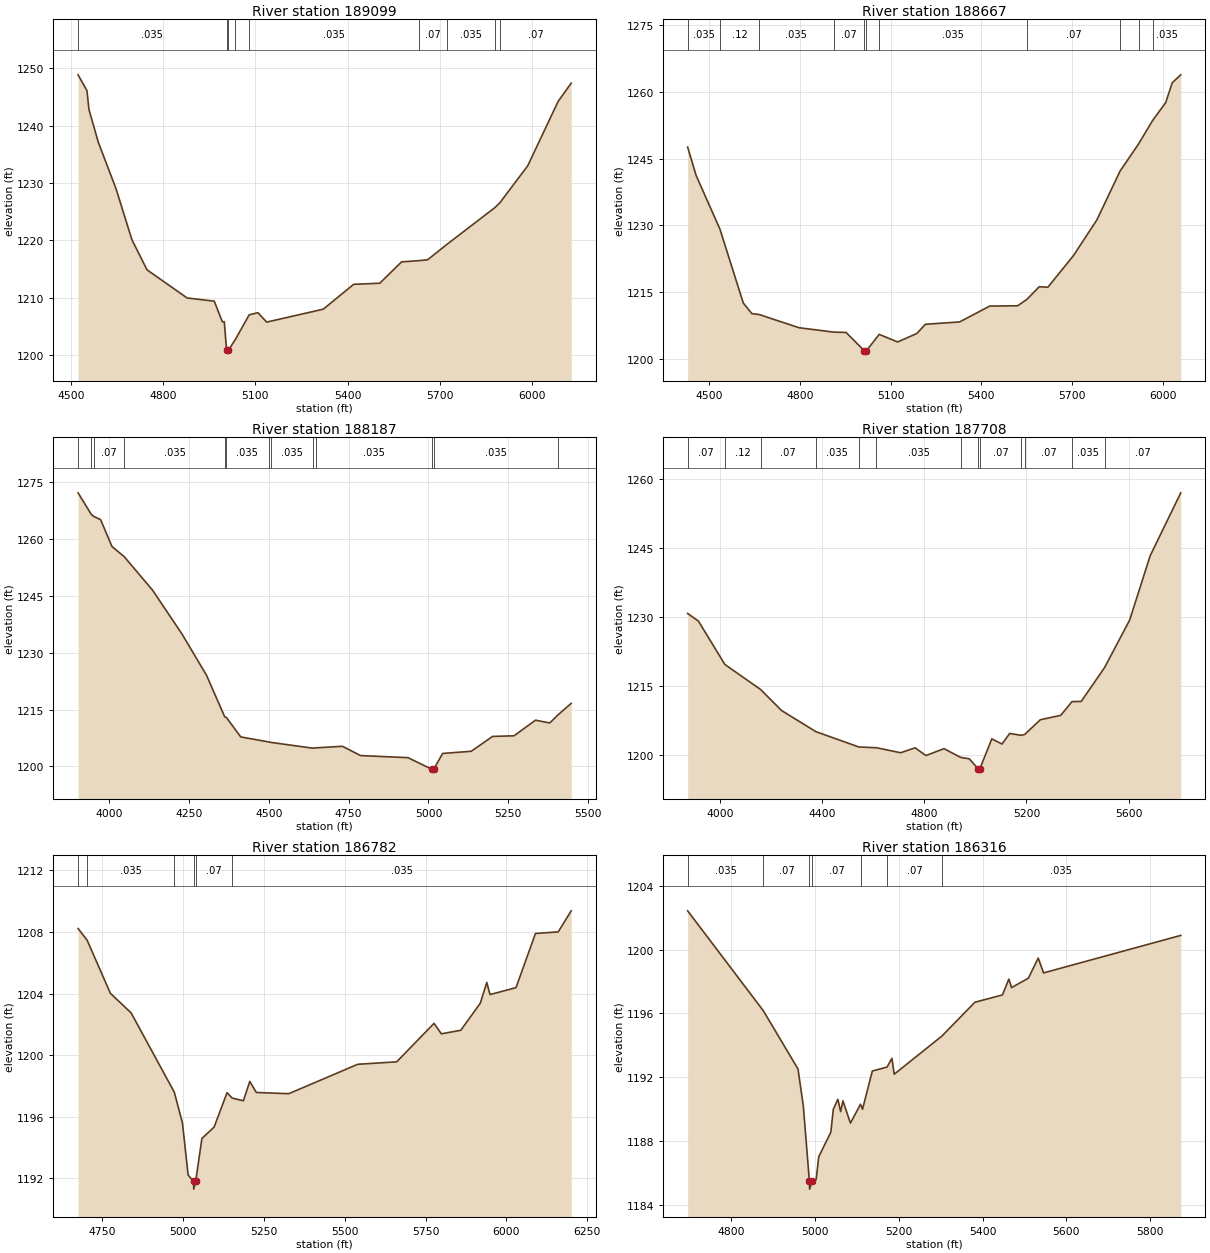
Type RM Length L Ch R = 1 ,189099  ,432,432,432
BEGIN DESCRIPTION:
Dry Comal Creek 264.0
END DESCRIPTION:
XS GIS Cut Line= 3
      2193125.02     13836825.02        2192725.       13836575.
        2191925.       13835775.
#Sta/Elev= 30
    4524 1248.87  4552.9 1246.11  4559.4 1242.82  4589.5 1237.16  4647.3 1229.02
  4699.1 1220.11  4748.1 1214.87  4878.4 1209.96  4966.8  1209.4  4992.8 1205.82
  4999.3 1205.82  5006.9 1200.84  5007.4 1200.34  5012.8 1200.84  5035.4 1202.73
  5080.3 1207.02  5108.9 1207.39  5137.1 1205.75    5321    1208    5420 1212.34
  5504.8 1212.53  5575.6 1216.25  5633.3 1216.47  5660.4 1216.62  5722.3 1219.27
  5878.9 1225.71  5895.4 1226.57  5985.7    1233  6084.7 1244.24  6127.1 1247.42
#Mann= 9 ,-1 , 0
    4524    .035       0  5006.9    .035       0  5012.8    .035       0
  5035.4     .07       0  5080.3    .035       0  5633.3     .07       0
  5722.3    .035       0  5878.9     .12       0  5895.4     .07       0
Bank Sta=5006.9,5012.8
XS Rating Curve= 0 ,0
Exp/Cntr=0.3,0.1

Type RM Length L Ch R = 1 ,188667  ,480,480,480
BEGIN DESCRIPTION:
Dry Comal Creek 263.0
END DESCRIPTION:
XS GIS Cut Line= 3
      2193225.01     13836575.01        2192825.       13836175.
      2192025.01     13835475.01
#Sta/Elev= 30
  4429.9 1247.61  4458.2 1241.19  4536.7 1229.13  4613.8 1212.51    4642 1210.14
  4665.9 1209.94  4797.6 1206.97  4912.1 1205.98  4953.2 1205.91  5013.9 1201.75
  5014.4 1201.25    5020 1201.75  5062.7 1205.47  5123.3 1203.76  5186.8 1205.66
  5215.3 1207.74  5328.3 1208.27  5427.9 1211.84    5520  1211.9  5550.5 1213.35
  5591.2 1216.19  5619.6 1216.07  5704.1 1223.18  5781.9 1231.27  5857.9 1242.18
  5919.2 1248.32  5965.8 1253.61  6008.8 1257.61  6030.6  1262.1  6058.6 1263.87
#Mann= 11 ,-1 , 0
  4429.9    .035       0  4536.7     .12       0  4665.9    .035       0
  4912.1     .07       0  5013.9     .05       0    5020     .07       0
  5062.7    .035       0  5550.5     .07       0  5857.9    .035       0
  5919.2     .07       0  5965.8    .035       0
Bank Sta=5013.9,5020
XS Rating Curve= 0 ,0
Exp/Cntr=0.3,0.1

Type RM Length L Ch R = 1 ,188187  ,479,479,479
BEGIN DESCRIPTION:
Dry Comal Creek 262.0
END DESCRIPTION:
XS GIS Cut Line= 3
      2193574.99     13836524.99        2192825.       13835725.
      2192424.99     13835524.99
#Sta/Elev= 30
  3903.1 1272.13  3944.1 1266.49  3951.6 1265.94  3973.7 1265.05  4009.3 1257.97
  4047.6  1255.3  4136.3 1246.47  4228.6 1234.89  4305.2 1224.05  4362.4 1213.04
  4367.3 1212.94  4412.3 1207.79  4499.3 1206.47  4506.9 1206.34  4638.1 1204.82
  4646.4  1204.9  4730.8 1205.32  4787.4 1202.87  4935.9 1202.32  5010.6 1199.27
  5011.1 1198.77  5016.8 1199.27  5044.4 1203.43  5133.8    1204  5200.9 1207.92
    5268 1208.08  5335.1  1212.2  5379.8 1211.47  5406.6 1213.67  5446.9 1216.64
#Mann= 13 ,-1 , 0
  3903.1     .07       0  3944.1    .035       0  3951.6     .07       0
  4047.6    .035       0  4362.4     .07       0  4367.3    .035       0
  4499.3     .07       0  4506.9    .035       0  4638.1     .07       0
  4646.4    .035       0  5010.6    .035       0  5016.8    .035       0
  5406.6     .07       0
Bank Sta=5010.6,5016.8
XS Rating Curve= 0 ,0
Exp/Cntr=0.3,0.1

Type RM Length L Ch R = 1 ,187708  ,926,926,926
BEGIN DESCRIPTION:
Dry Comal Creek 261.0
END DESCRIPTION:
XS GIS Cut Line= 3
      2193724.99     13836074.99        2192925.       13835275.
      2192124.95       13835275.
#Sta/Elev= 30
  3872.9 1230.74  3915.3 1229.07  4018.7 1219.64  4158.6  1214.2  4240.6 1209.63
  4374.8 1205.03  4543.8 1201.68  4612.5 1201.52  4707.3 1200.43  4763.8  1201.5
  4806.3 1199.82    4877 1201.32  4941.9 1199.42    4976 1199.11  5011.1 1196.93
  5011.6 1196.43  5017.4 1196.93  5064.3 1203.45  5104.3 1202.33  5134.3 1204.63
  5178.9 1204.22  5193.1 1204.41  5254.3 1207.61  5334.3 1208.57  5378.3 1211.56
  5414.3 1211.59  5505.9 1218.96  5604.3 1229.32  5684.3 1243.27  5804.3 1256.99
#Mann= 13 ,-1 , 0
  3872.9     .07       0  4018.7     .12       0  4158.6     .07       0
  4374.8    .035       0  4543.8     .07       0  4612.5    .035       0
  4941.9     .07       0  5011.1     .05       0  5017.4     .07       0
  5178.9    .035       0  5193.1     .07       0  5378.3    .035       0
  5505.9     .07       0
Bank Sta=5011.1,5017.4
XS Rating Curve= 0 ,0
Exp/Cntr=0.3,0.1

Type RM Length L Ch R = 1 ,186782  ,466,466,466
BEGIN DESCRIPTION:
Dry Comal Creek 260.0
END DESCRIPTION:
XS GIS Cut Line= 3
      2193924.98     13835274.98        2193725.       13835025.
      2192524.98       13834925.
#Sta/Elev= 30
  4675.7 1208.23  4703.5 1207.48  4775.7 1204.02  4839.7 1202.75  4973.1  1197.6
  4998.3  1195.6  5015.9 1192.22  5032.7  1191.8  5033.2  1191.3  5039.2  1191.8
  5058.5 1194.59  5096.2 1195.33  5136.3 1197.57  5151.8 1197.22  5186.5 1197.04
  5206.6  1198.3  5226.6 1197.58    5327  1197.5  5540.2 1199.41  5660.6 1199.57
    5776 1202.07  5798.6 1201.39  5858.8 1201.62    5919 1203.38  5939.1 1204.73
  5949.1 1203.94  6029.4 1204.39  6089.6 1207.91  6159.8 1208.01    6200 1209.38
#Mann= 6 ,-1 , 0
  4675.7     .07       0  4703.5    .035       0  4973.1     .07       0
  5032.7     .05       0  5039.2     .07       0  5151.8    .035       0
Bank Sta=5032.7,5039.2
XS Rating Curve= 0 ,0
Exp/Cntr=0.3,0.1

Type RM Length L Ch R = 1 ,186316  ,457,457,457
BEGIN DESCRIPTION:
Dry Comal Creek 259.0
END DESCRIPTION:
XS GIS Cut Line= 3
      2194074.95     13834624.99        2193775.       13834575.
        2192975.       13834925.
#Sta/Elev= 30
  4695.9 1202.43  4876.6 1196.17  4959.4 1192.52  4972.1  1190.2  4986.6 1185.49
  4987.1 1184.99  4993.2 1185.49  5002.7 1185.59    5009 1187.02  5037.8 1188.56
  5043.7 1189.99  5054.6 1190.62  5061.2 1189.85  5066.7 1190.52  5084.6 1189.13
  5108.7 1190.31  5113.4 1189.99  5136.8 1192.39  5172.1 1192.64  5183.6 1193.19
  5189.1 1192.19  5303.3 1194.59  5381.6  1196.7  5447.5 1197.16  5462.7 1198.15
  5469.3 1197.62  5509.5 1198.21  5532.9 1199.47  5545.7 1198.54  5873.2 1200.89
#Mann= 7 ,-1 , 0
  4695.9    .035       0  4876.6     .07       0  4986.6     .05       0
  4993.2     .07       0  5108.7    .035       0  5172.1     .07       0
  5303.3    .035       0
Bank Sta=4986.6,4993.2
XS Rating Curve= 0 ,0
Exp/Cntr=0.3,0.1

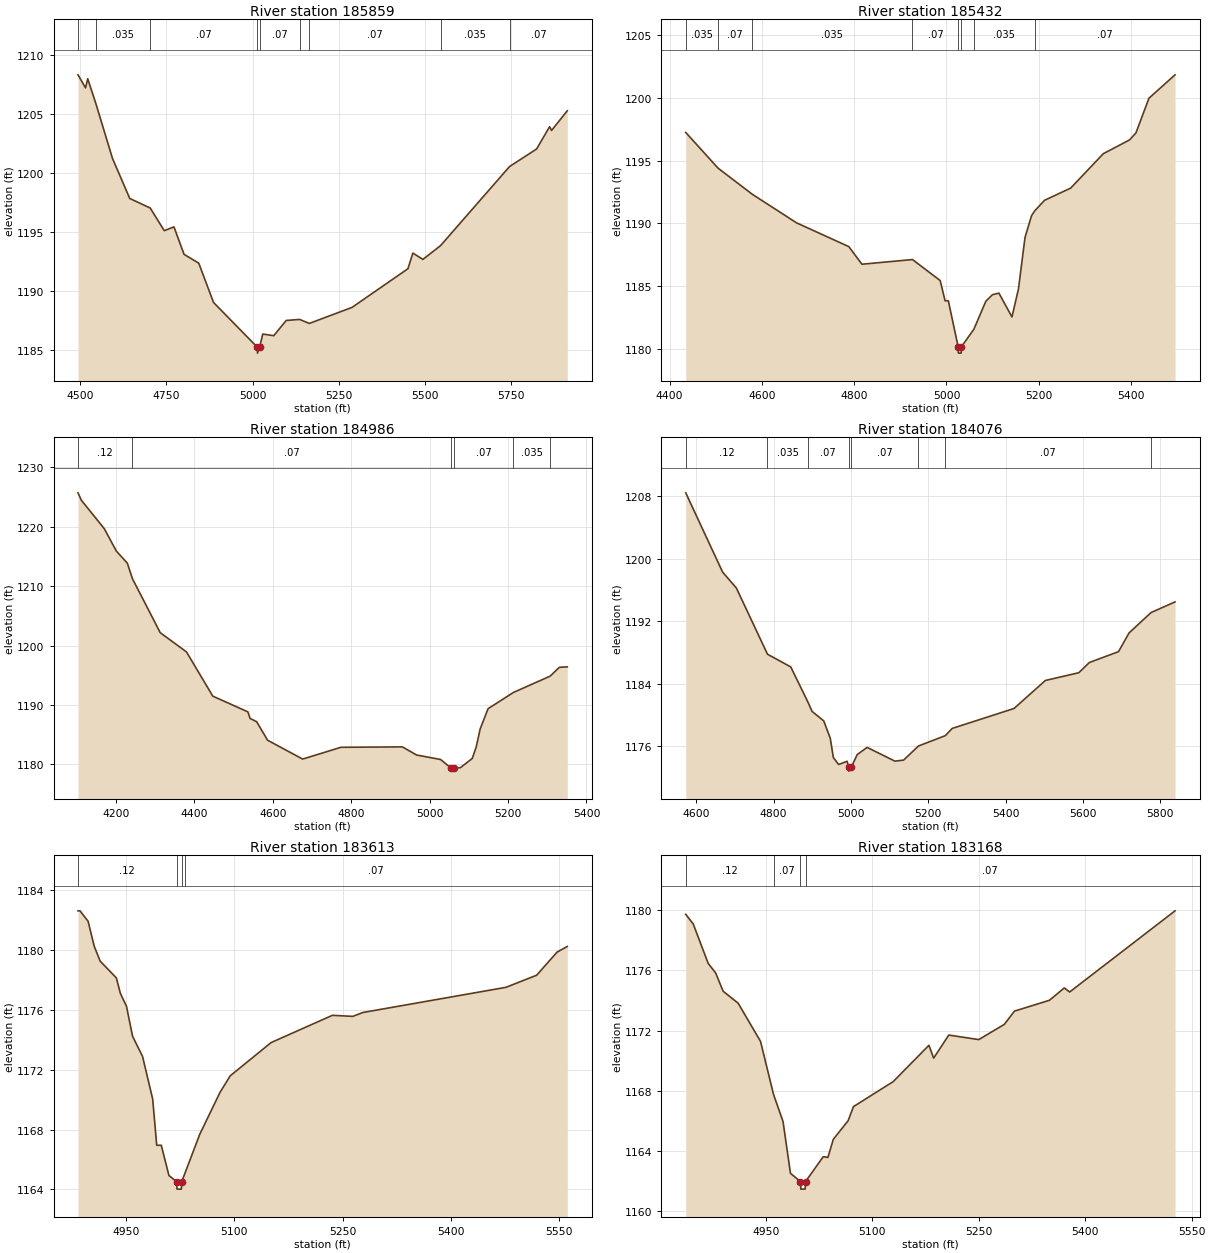
Type RM Length L Ch R = 1 ,185859  ,427,427,427
BEGIN DESCRIPTION:
Dry Comal Creek 258.0
END DESCRIPTION:
XS GIS Cut Line= 3
      2194225.01     13834575.02        2193925.       13834175.
        2193475.       13833375.
#Sta/Elev= 30
  4494.2 1208.31  4516.1  1207.2  4522.3 1207.98  4545.7  1205.9  4594.2 1201.21
  4644.2 1197.82  4703.5 1197.01  4744.2 1195.09  4772.3 1195.41  4801.5 1193.08
  4844.2 1192.33  4886.9    1189  5013.9  1185.2  5014.4  1184.7  5020.5  1185.2
  5029.6 1186.32  5061.5 1186.18  5097.5 1187.47  5136.4 1187.56  5164.5 1187.22
  5288.4 1188.58  5450.3 1191.86  5464.6 1193.19  5493.6 1192.65  5544.8 1193.82
  5744.8 1200.53  5823.2 1202.02  5860.8 1203.91  5866.5 1203.59  5912.1 1205.26
#Mann= 9 ,-1 , 0
  4494.2     .07       0  4545.7    .035       0  4703.5     .07       0
  5013.9     .05       0  5020.5     .07       0  5136.4    .035       0
  5164.5     .07       0  5544.8    .035       0  5744.8     .07       0
Bank Sta=5013.9,5020.5
XS Rating Curve= 0 ,0
Exp/Cntr=0.3,0.1

Type RM Length L Ch R = 1 ,185432  ,446,446,446
BEGIN DESCRIPTION:
Dry Comal Creek 257.0
END DESCRIPTION:
XS GIS Cut Line= 3
      2194424.99     13834174.99        2194025.       13833775.
      2193675.03     13833425.03
#Sta/Elev= 30
  4434.9 1197.24  4504.9  1194.4  4579.1 1192.32  4675.3 1190.04  4788.4 1188.15
  4816.7 1186.75  4926.4 1187.12  4986.4 1185.45    4997 1183.84  5004.1 1183.84
  5025.4 1180.17  5025.9 1179.67  5031.8 1179.67  5032.3 1180.17  5059.4 1181.57
  5085.4  1183.8  5099.6 1184.32  5113.7 1184.45    5142 1182.55  5156.1 1184.78
  5170.3 1188.88  5184.4 1190.61  5191.8 1191.02  5212.7 1191.84  5269.3 1192.81
    5340 1195.55  5396.6 1196.64  5410.7  1197.2    5439 1199.97  5495.5 1201.83
#Mann= 8 ,-1 , 0
  4434.9    .035       0  4504.9     .07       0  4579.1    .035       0
  4926.4     .07       0  5025.4     .05       0  5032.3     .07       0
  5059.4    .035       0  5191.8     .07       0
Bank Sta=5025.4,5032.3
XS Rating Curve= 0 ,0
Exp/Cntr=0.3,0.1

Type RM Length L Ch R = 1 ,184986  ,910,910,910
BEGIN DESCRIPTION:
Dry Comal Creek 256.0
END DESCRIPTION:
XS GIS Cut Line= 3
      2194975.02     13833875.01        2194175.       13833475.
      2193825.01       13833425.
#Sta/Elev= 30
  4103.1  1225.7  4111.5 1224.47  4170.2 1219.66    4201 1215.89  4228.9 1213.87
  4241.9 1211.26  4312.8 1202.17  4379.8 1198.93  4446.9 1191.49  4536.4 1188.84
    4542 1187.74  4558.7 1187.19  4586.7 1184.07  4676.1  1180.9  4773.9 1182.88
  4930.5 1182.95  4966.8 1181.58  5027.9 1180.83  5054.7 1179.37  5055.2 1178.87
  5061.6 1179.37  5078.4 1179.45  5108.7    1181  5118.8 1182.94  5128.9 1185.97
  5149.1 1189.38  5213.8 1192.11  5307.3 1194.85  5330.9 1196.34  5351.1 1196.42
#Mann= 6 ,-1 , 0
  4103.1     .12       0  4241.9     .07       0  5054.7     .05       0
  5061.6     .07       0  5213.8    .035       0  5307.3     .07       0
Bank Sta=5054.7,5061.6
XS Rating Curve= 0 ,0
Exp/Cntr=0.3,0.1

Type RM Length L Ch R = 1 ,184076  ,463,463,463
BEGIN DESCRIPTION:
Dry Comal Creek 255.0
END DESCRIPTION:
XS GIS Cut Line= 3
      2195125.02     13833175.01        2194725.       13833025.
      2193924.98     13833275.01
#Sta/Elev= 30
  4572.8 1208.42  4668.1 1198.27  4703.7 1196.23  4784.2 1187.75  4844.3 1186.13
  4888.3 1181.67  4899.5 1180.43  4929.7 1179.21  4946.6 1176.98  4954.6 1174.51
    4968 1173.63  4990.2 1174.04  4993.9 1173.28  4994.4 1172.78  5000.9 1173.28
  5016.3  1174.9  5041.9 1175.82  5113.7 1174.06  5136.2 1174.19  5174.7    1176
    5244 1177.32  5261.9 1178.25  5421.7  1180.8  5502.9 1184.39  5589.3 1185.38
  5616.6 1186.69    5692 1188.08  5719.3 1190.48  5776.2 1193.09  5838.2 1194.45
#Mann= 8 ,-1 , 0
  4572.8     .12       0  4784.2    .035       0  4888.3     .07       0
  4993.9     .05       0  5000.9     .07       0  5174.7     .12       0
    5244     .07       0  5776.2    .035       0
Bank Sta=4993.9,5000.9
XS Rating Curve= 0 ,0
Exp/Cntr=0.3,0.1

Type RM Length L Ch R = 1 ,183613  ,445,445,445
BEGIN DESCRIPTION:
Dry Comal Creek 254.0
END DESCRIPTION:
XS GIS Cut Line= 3
      2194774.99       13832525.        2194675.       13832575.
      2194274.99     13832975.01
#Sta/Elev= 30
  4883.7 1182.61  4886.5 1182.61  4897.7 1181.91  4906.1 1180.25  4914.4 1179.25
  4936.8 1178.13  4942.4 1177.09  4950.8 1176.24  4959.2 1174.24  4973.1 1172.88
  4987.1 1170.04  4992.7 1166.95    4999 1166.95  5009.6 1164.93  5020.3 1164.52
  5020.8 1164.02  5026.8 1164.02  5027.3 1164.52  5031.3 1165.02  5052.1 1167.66
  5080.3 1170.48  5094.5 1171.59  5151.1 1173.81  5235.9 1175.63  5264.2 1175.56
  5278.3 1175.82  5476.3  1177.5  5518.8 1178.31    5547 1179.85  5561.2 1180.23
#Mann= 4 ,-1 , 0
  4883.7     .12       0  5020.3     .05       0  5027.3     .12       0
  5031.3     .07       0
Bank Sta=5020.3,5027.3
XS Rating Curve= 0 ,0
Exp/Cntr=0.3,0.1

Type RM Length L Ch R = 1 ,183168  ,417,417,417
BEGIN DESCRIPTION:
Dry Comal Creek 253.0
END DESCRIPTION:
XS GIS Cut Line= 3
      2194525.02     13832224.99        2194375.       13832275.
      2194025.03     13832674.97
#Sta/Elev= 30
    4837 1179.72  4847.6 1179.07  4868.6 1176.46  4879.2 1175.82  4889.7 1174.61
  4910.8 1173.82  4942.4 1171.28  4960.7 1167.76  4974.1 1165.96  4984.6 1162.52
  4998.7 1161.97  4999.2 1161.47  5005.3 1161.47  5005.8 1161.97  5030.7 1163.62
  5037.4 1163.58    5045 1164.78  5065.8 1166.01  5073.4 1166.95  5129.4 1168.61
  5179.7 1171.02  5186.4 1170.17  5207.7  1171.7    5250  1171.4    5286 1172.41
  5300.3 1173.29  5349.6 1174.01  5370.5 1174.83  5378.1 1174.56  5526.6 1179.95
#Mann= 4 ,-1 , 0
    4837     .12       0  4960.7     .07       0  4998.7     .05       0
  5005.8     .07       0
Bank Sta=4998.7,5005.8
XS Rating Curve= 0 ,0
Exp/Cntr=0.3,0.1