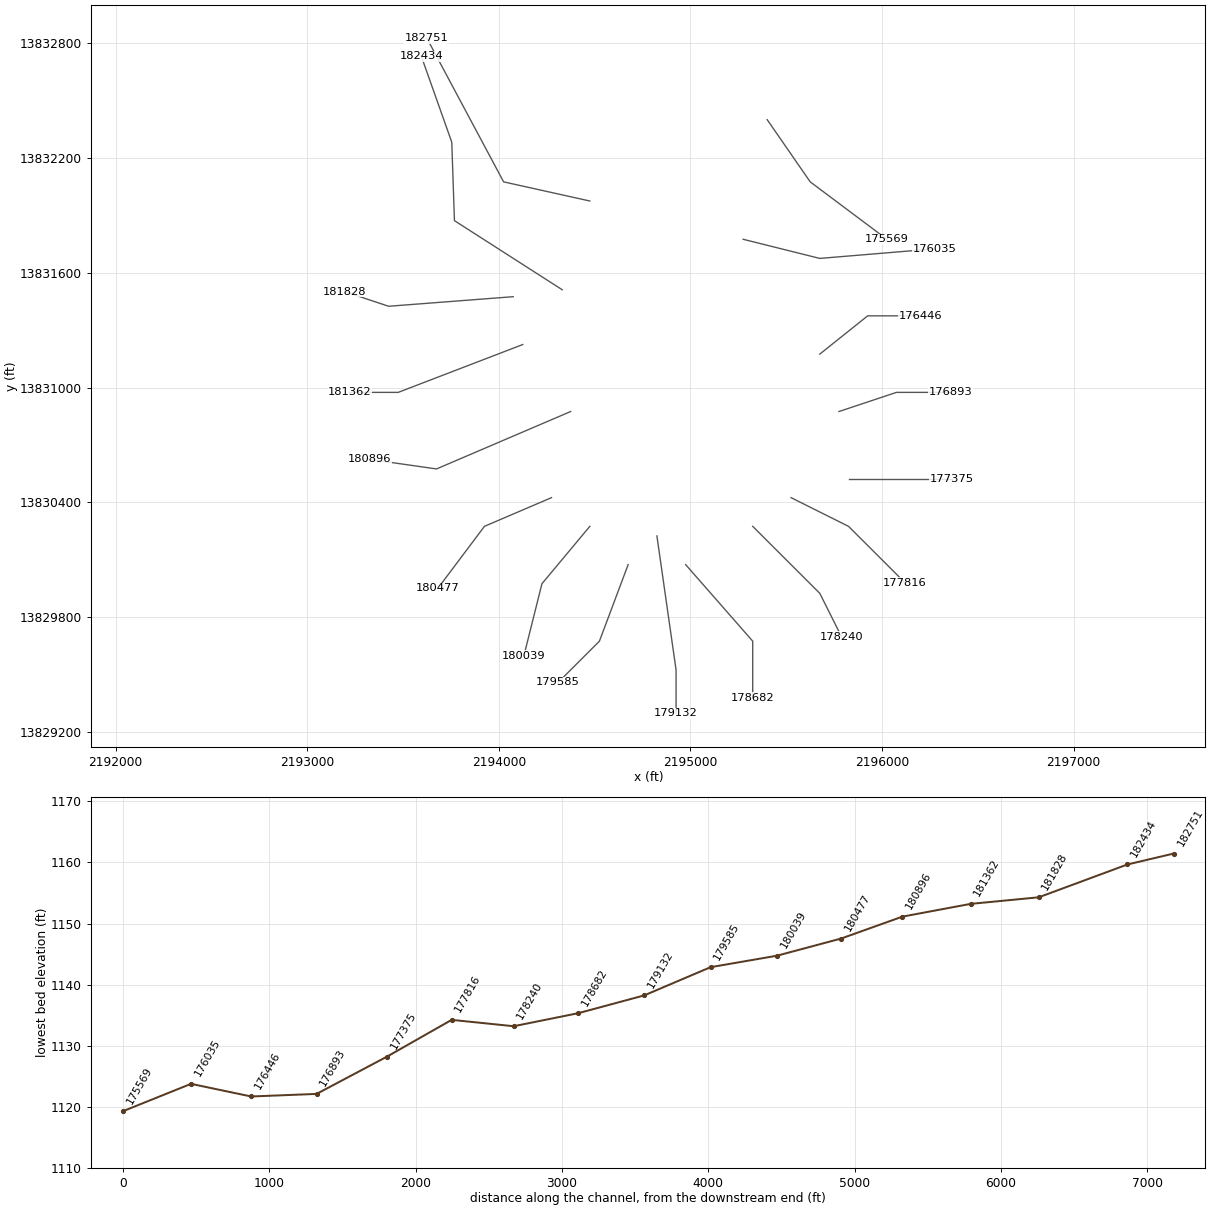
HEC-RAS study Dry Comal Creek.prj: Dry Comal Creek Base Level Engineering

--- Dry Comal Creek.g01 (geometry) --- (continued)

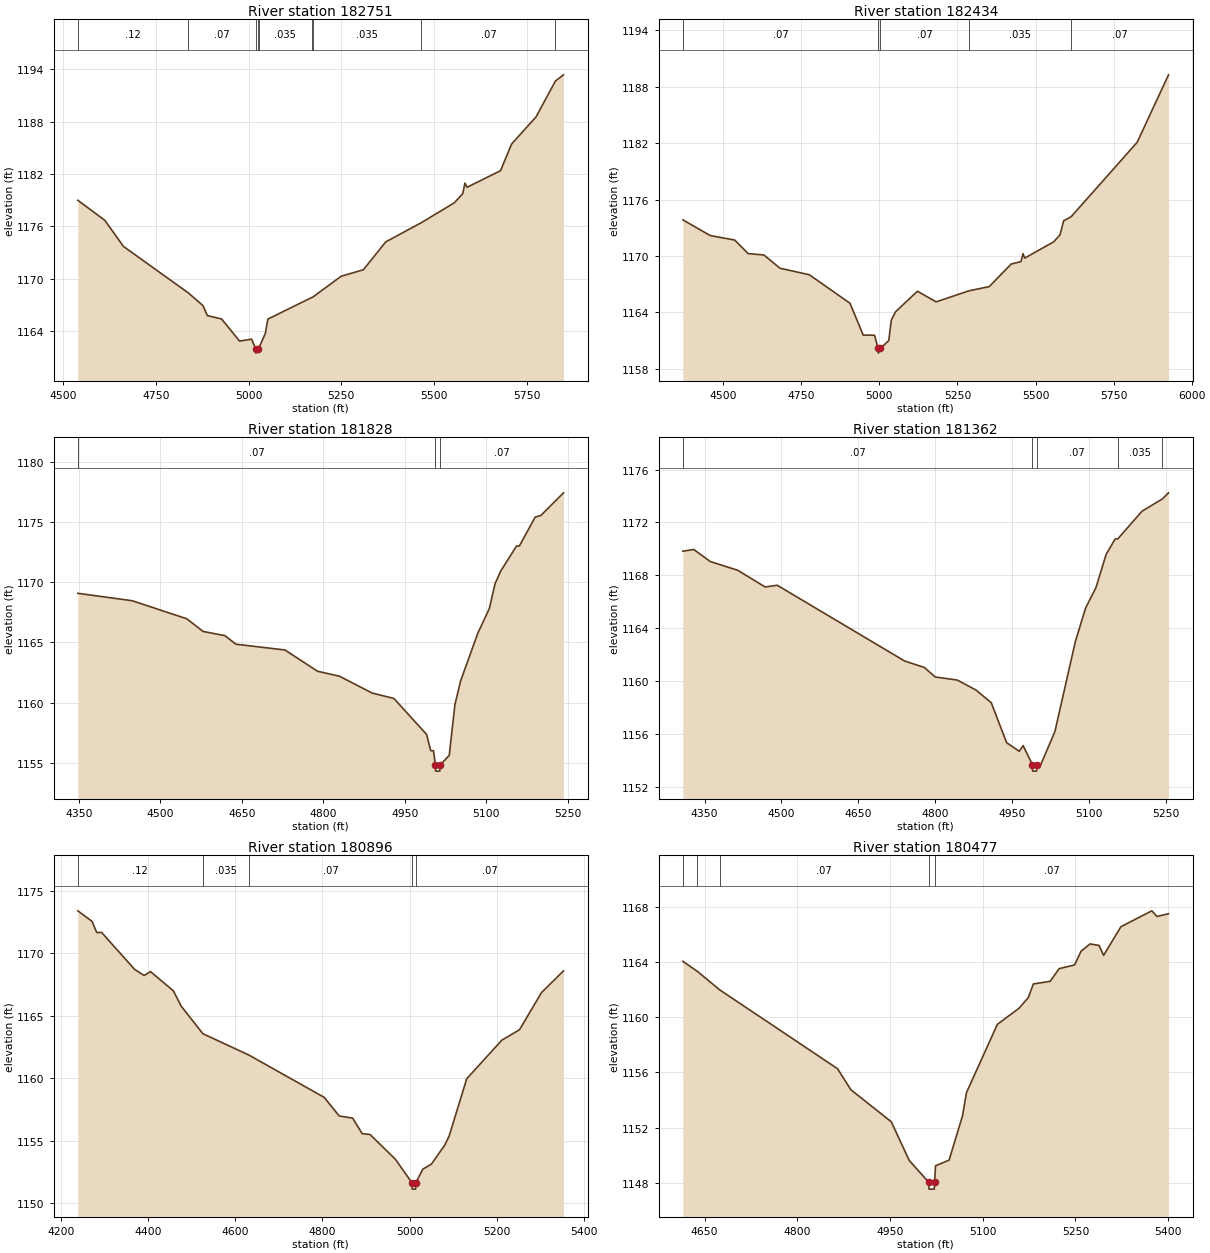
Type RM Length L Ch R = 1 ,182751  ,317,317,317
BEGIN DESCRIPTION:
Dry Comal Creek 252.0
END DESCRIPTION:
XS GIS Cut Line= 3
      2194474.99       13831975.        2194025.       13832075.
      2193624.99     13832825.03
#Sta/Elev= 30
  4538.8 1178.99  4611.8 1176.69  4661.7 1173.71  4836.6 1168.39  4876.8 1166.91
  4888.4 1165.77  4926.8 1165.39  4975.4 1162.85  5007.9 1163.07  5018.9 1161.97
  5019.4 1161.47    5026 1161.97  5027.5 1162.06  5045.1 1163.74  5051.8 1165.37
  5169.9 1167.84    5173 1167.89  5249.5 1170.28  5309.7 1171.03  5369.9 1174.22
  5465.9 1176.42  5555.1  1178.7  5577.8 1179.75  5583.8 1180.96  5589.5 1180.48
  5679.8 1182.38  5709.9 1185.45  5775.8 1188.55  5828.1 1192.67  5849.8 1193.37
#Mann= 9 ,-1 , 0
  4538.8     .12       0  4836.6     .07       0  5018.9     .05       0
    5026     .07       0  5027.5    .035       0  5169.9     .07       0
    5173    .035       0  5465.9     .07       0  5828.1    .035       0
Bank Sta=5018.9,5026
XS Rating Curve= 0 ,0
Exp/Cntr=0.3,0.1

Type RM Length L Ch R = 1 ,182434  ,606,606,606
BEGIN DESCRIPTION:
X18975
END DESCRIPTION:
XS GIS Cut Line= 4
      2194331.02      13831511.2      2193768.49     13831872.32
       2193754.6     13832282.05       2193595.5      13832731.7
#Sta/Elev= 30
  4370.5 1173.85  4457.9 1172.18  4536.5  1171.7  4579.7 1170.26  4630.3 1170.11
  4681.8  1168.7  4775.6 1168.01  4905.8 1164.98  4948.1  1161.6  4984.4 1161.58
    4996 1160.18  4996.5 1159.68  5003.2 1160.18    5030 1161.02  5038.1 1163.18
  5051.6 1164.07  5121.7 1166.26  5181.7 1165.13  5286.4  1166.3  5351.8 1166.75
  5421.9 1169.15  5453.1  1169.4    5460 1170.25  5465.3 1169.78  5558.1 1171.51
  5578.3 1172.25    5590 1173.74  5614.3 1174.19  5825.5 1182.09  5925.9 1189.26
#Mann= 5 ,-1 , 0
  4370.5     .07       0    4996     .05       0  5003.2     .07       0
  5286.4    .035       0  5614.3     .07       0
Bank Sta=4996,5003.2
XS Rating Curve= 0 ,0
Exp/Cntr=0.3,0.1

Type RM Length L Ch R = 1 ,181828  ,466,466,466
BEGIN DESCRIPTION:
Dry Comal Creek 251.0
END DESCRIPTION:
XS GIS Cut Line= 4
      2194074.97       13831475.        2193425.       13831425.
        2193275.       13831475.       2193195.5      13831501.5
#Sta/Elev= 30
  4348.1 1169.08  4448.4 1168.46  4548.7 1166.96  4578.7 1165.91  4618.9 1165.56
  4638.9 1164.85  4729.2 1164.37  4789.4  1162.6  4829.5 1162.19  4889.7 1160.79
  4929.8 1160.34    4990 1157.35  4997.5    1156  5002.6    1156  5006.2  1154.8
  5006.7  1154.3  5014.3  1154.3  5014.8  1154.8  5031.6 1155.61  5042.1 1159.83
  5052.7 1161.82  5084.3 1165.77  5105.4 1167.81  5115.9 1169.87  5126.5 1170.94
  5155.5 1173.01  5160.7 1173.01  5189.7 1175.41  5200.3 1175.55  5241.9 1177.43
#Mann= 3 ,-1 , 0
  4348.1     .07       0  5006.2     .05       0  5014.8     .07       0
Bank Sta=5006.2,5014.8
XS Rating Curve= 0 ,0
Exp/Cntr=0.3,0.1

Type RM Length L Ch R = 1 ,181362  ,466,466,466
BEGIN DESCRIPTION:
Dry Comal Creek 250.0
END DESCRIPTION:
XS GIS Cut Line= 4
      2194124.99       13831225.        2193475.       13830975.
        2193325.       13830975.      2193223.21       13830975.
#Sta/Elev= 30
  4307.7 1169.83  4329.1 1169.96  4361.3 1169.05  4414.8 1168.39  4468.4 1167.13
    4492 1167.26  4740.5 1161.54  4779.1 1161.05  4800.5 1160.33  4843.4  1160.1
  4879.8 1159.35  4909.8 1158.39  4939.8 1155.37  4964.5 1154.72    4972 1155.15
  4990.1 1153.72  4990.6 1153.22  4998.3 1153.22  4998.8 1153.72  5006.6 1153.72
  5034.1 1156.21  5074.1 1163.02  5094.1 1165.55  5114.1 1167.07  5134.1 1169.59
  5151.6 1170.75  5156.8 1170.76  5204.1 1172.85  5243.9 1173.78  5255.9 1174.24
#Mann= 5 ,-1 , 0
  4307.7     .07       0  4990.1     .05       0  4998.8     .07       0
  5156.8    .035       0  5243.9     .07       0
Bank Sta=4990.1,4998.8
XS Rating Curve= 0 ,0
Exp/Cntr=0.3,0.1

Type RM Length L Ch R = 1 ,180896  ,419,419,419
BEGIN DESCRIPTION:
Dry Comal Creek 249.0
END DESCRIPTION:
XS GIS Cut Line= 3
        2194375.       13830875.        2193675.       13830575.
      2193325.03       13830625.
#Sta/Elev= 30
  4238.4 1173.39    4271 1172.55  4281.9 1171.65  4292.8 1171.67    4369  1168.7
  4390.7 1168.22  4405.2 1168.53  4457.8 1166.99  4475.9 1165.76  4525.6 1163.56
  4631.4 1161.85  4804.1 1158.47  4838.6 1156.98  4869.4 1156.81  4891.2 1155.57
  4909.3  1155.5  4967.3 1153.53  5005.7 1151.63  5006.2 1151.13  5013.9 1151.13
  5014.4 1151.63  5030.3 1152.72  5050.5 1153.14  5080.8 1154.65  5090.9 1155.37
  5131.3 1159.96  5212.1 1163.05  5252.5 1163.88    5303 1166.85  5353.5 1168.59
#Mann= 5 ,-1 , 0
  4238.4     .12       0  4525.6    .035       0  4631.4     .07       0
  5005.7     .05       0  5014.4     .07       0
Bank Sta=5005.7,5014.4
XS Rating Curve= 0 ,0
Exp/Cntr=0.3,0.1

Type RM Length L Ch R = 1 ,180477  ,438,438,438
BEGIN DESCRIPTION:
Dry Comal Creek 248.0
END DESCRIPTION:
XS GIS Cut Line= 4
      2194274.99     13830424.99        2193925.       13830275.
        2193775.       13830075.      2193681.92      13829950.9
#Sta/Elev= 30
  4614.7 1164.05  4638.3 1163.32  4674.1 1161.99  4864.9 1156.27  4886.7 1154.74
    4952 1152.42    4981 1149.62  5012.5 1148.04    5013 1147.54  5021.6 1147.54
  5022.1 1148.04  5023.6 1149.23  5045.5 1149.64  5067.3 1152.86  5073.6 1154.53
  5123.6 1159.48    5159 1160.66  5173.6 1161.42  5181.9 1162.41    5209  1162.6
  5223.6 1163.52  5248.6 1163.79    5259 1164.78  5273.6 1165.31  5288.2  1165.2
  5295.5 1164.48  5323.6 1166.56  5373.6 1167.71  5381.9  1167.3  5400.6  1167.5
#Mann= 5 ,-1 , 0
  4614.7     .07       0  4638.3    .035       0  4674.1     .07       0
  5012.5     .05       0  5022.1     .07       0
Bank Sta=5012.5,5022.1
XS Rating Curve= 0 ,0
Exp/Cntr=0.3,0.1

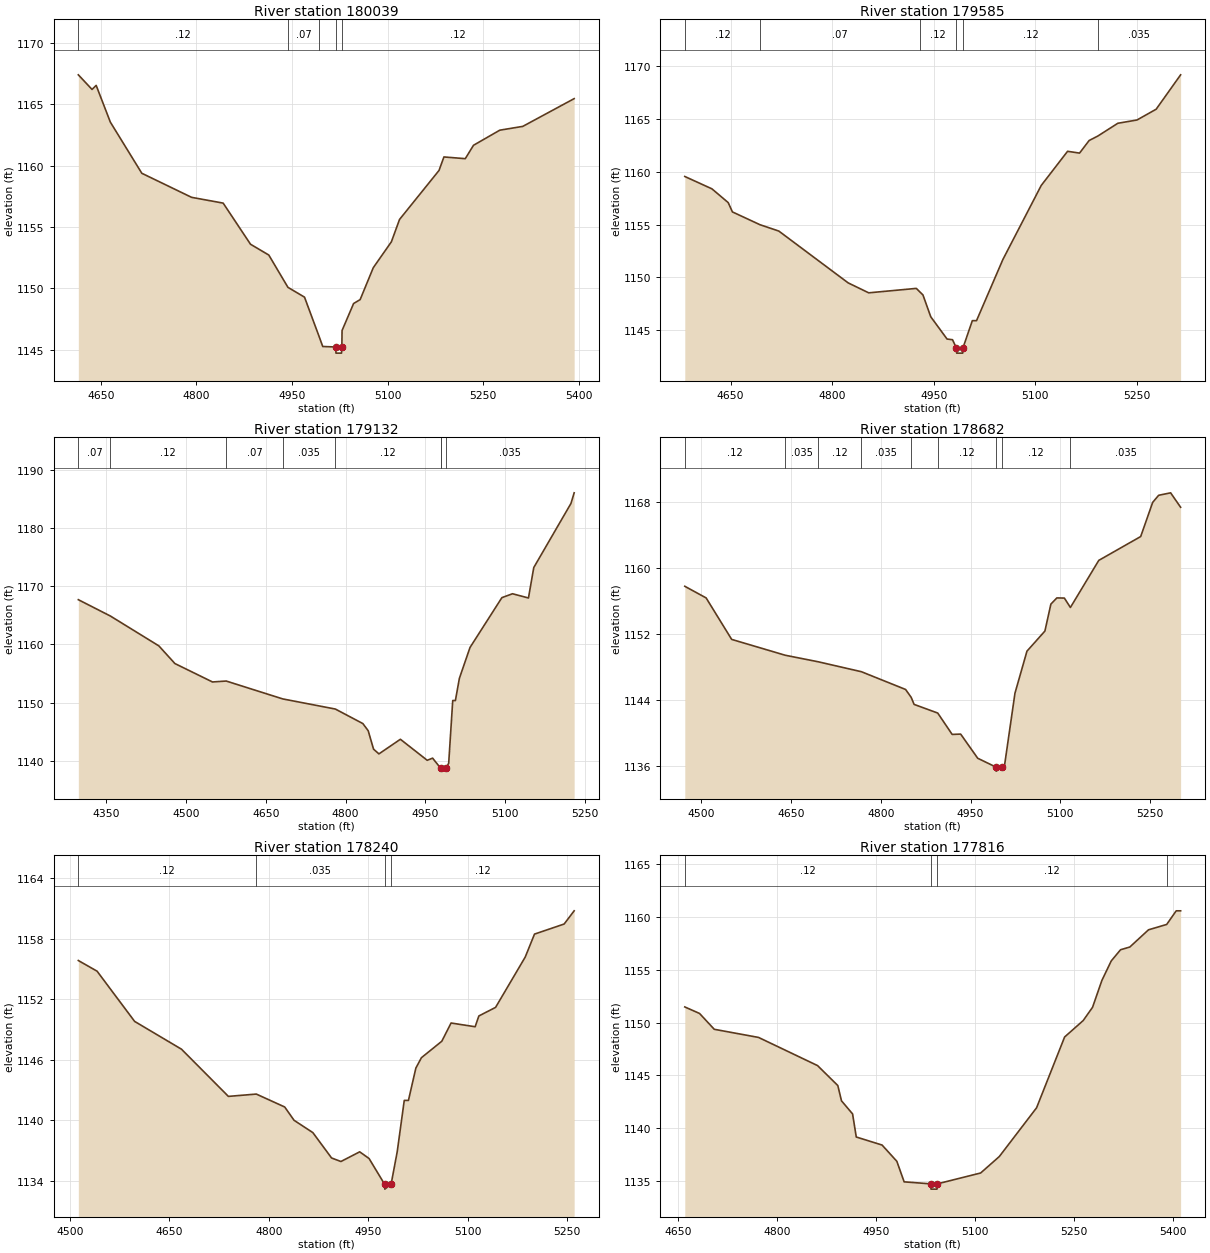
Type RM Length L Ch R = 1 ,180039  ,454,454,454
BEGIN DESCRIPTION:
Dry Comal Creek 247.0
END DESCRIPTION:
XS GIS Cut Line= 4
      2194475.02     13830275.03        2194225.       13829975.
        2194175.       13829775.      2194131.08     13829599.31
#Sta/Elev= 30
  4614.8  1167.4  4636.3 1166.21  4642.8 1166.54    4665 1163.55  4714.4 1159.38
  4792.5 1157.42    4842 1156.95  4884.9  1153.6  4913.6 1152.72  4943.6 1150.09
  4969.6 1149.29  4992.9 1146.03  4998.2 1145.27  5018.5 1145.23    5019 1144.73
  5027.7 1144.73  5028.2 1145.23  5028.5 1146.57  5046.6 1148.77  5056.9 1149.09
  5077.5 1151.69  5105.9  1153.8  5118.7 1155.62  5180.6 1159.61  5188.3 1160.71
  5221.8 1160.57  5234.7 1161.66  5275.9 1162.89    5312  1163.2  5392.6 1165.46
#Mann= 5 ,-1 , 0
  4614.8     .12       0  4943.6     .07       0  4992.9     .12       0
  5018.5     .05       0  5028.2     .12       0
Bank Sta=5018.5,5028.2
XS Rating Curve= 0 ,0
Exp/Cntr=0.3,0.1

Type RM Length L Ch R = 1 ,179585  ,453,453,453
BEGIN DESCRIPTION:
Dry Comal Creek 246.0
END DESCRIPTION:
XS GIS Cut Line= 4
        2194675.     13830075.01        2194525.       13829675.
        2194425.       13829575.      2194309.48     13829459.48
#Sta/Elev= 30
  4582.4 1159.55  4622.5 1158.38  4646.5 1157.08  4652.7  1156.2  4693.4 1154.99
  4721.2 1154.39  4823.6 1149.49  4853.9 1148.55  4924.2 1148.97  4928.9 1148.67
    4934 1148.35  4945.5 1146.29  4969.6 1144.18  4977.6 1144.12  4983.3 1143.35
  4983.8 1142.85  4992.6 1142.85  4993.1 1143.35  5006.9 1145.92  5013.1 1145.92
    5052  1151.7  5108.6  1158.7  5147.5 1161.93  5165.2 1161.76  5179.3 1162.95
  5192.1 1163.37  5221.7 1164.58    5250 1164.89  5278.3 1165.91  5314.4 1169.16
#Mann= 6 ,-1 , 0
  4582.4     .12       0  4693.4     .07       0  4928.9     .12       0
  4983.3     .05       0  4993.1     .12       0  5192.1    .035       0
Bank Sta=4983.3,4993.1
XS Rating Curve= 0 ,0
Exp/Cntr=0.3,0.1

Type RM Length L Ch R = 1 ,179132  ,450,450,450
BEGIN DESCRIPTION:
Dry Comal Creek 245.0
END DESCRIPTION:
XS GIS Cut Line= 4
        2194825.     13830225.01        2194925.       13829525.
        2194925.       13829425.        2194925.     13829299.01
#Sta/Elev= 30
  4297.1 1167.67  4357.5 1164.86  4448.6 1159.74  4478.9  1156.7  4549.6 1153.54
  4575.4  1153.7  4681.8 1150.63  4780.8 1148.89  4832.5  1146.4  4842.6 1145.17
  4852.7    1142  4862.8 1141.19  4903.2  1143.7  4953.7 1140.09  4963.8 1140.46
  4978.7 1138.76  4979.1 1138.73  4979.6 1138.23    4989 1138.73  4994.1 1139.59
  5001.7 1150.35  5006.7 1150.35  5014.2 1154.16  5034.2 1159.46  5094.2 1168.02
  5114.2 1168.69  5144.2 1167.96  5154.2 1173.19  5224.2  1184.2  5230.2 1186.02
#Mann= 8 ,-1 , 0
  4297.1     .07       0  4357.5     .12       0  4575.4     .07       0
  4681.8    .035       0  4780.8     .12       0  4978.7    .035       0
  4979.1    .035       0    4989    .035       0
Bank Sta=4979.1,4989
XS Rating Curve= 0 ,0
Exp/Cntr=0.3,0.1

Type RM Length L Ch R = 1 ,178682  ,442,442,442
BEGIN DESCRIPTION:
Dry Comal Creek 244.0
END DESCRIPTION:
XS GIS Cut Line= 4
      2194974.98     13830075.02        2195325.       13829675.
        2195325.       13829575.        2195325.     13829378.34
#Sta/Elev= 30
  4472.6 1157.73  4508.2 1156.32  4550.9 1151.29  4640.3 1149.37  4695.9 1148.57
  4767.7 1147.37  4841.4 1145.22  4850.8 1144.26  4855.6 1143.41  4895.1 1142.36
  4919.2 1139.77  4933.4 1139.81  4961.9 1136.88  4992.1 1135.82  4992.6 1135.32
    5002 1135.82  5006.6 1135.97  5024.1 1144.77  5044.1 1149.86  5074.1  1152.3
  5084.1 1155.57  5094.1 1156.32  5106.6  1156.3  5116.7 1155.16  5164.1 1160.87
  5234.1 1163.76  5254.1  1167.9  5264.1 1168.76  5284.1 1169.06  5300.8 1167.31
#Mann= 9 ,-1 , 0
  4472.6     .12       0  4640.3    .035       0  4695.9     .12       0
  4767.7    .035       0  4850.8     .07       0  4895.1     .12       0
  4992.1     .05       0    5002     .12       0  5116.7    .035       0
Bank Sta=4992.1,5002
XS Rating Curve= 0 ,0
Exp/Cntr=0.3,0.1

Type RM Length L Ch R = 1 ,178240  ,424,424,424
BEGIN DESCRIPTION:
Dry Comal Creek 243.0
END DESCRIPTION:
XS GIS Cut Line= 4
      2195324.97     13830275.03        2195675.       13829925.
        2195725.       13829825.        2195788.     13829698.99
#Sta/Elev= 30
  4512.9 1155.86  4541.2  1154.8  4597.8 1149.82  4668.5 1147.06  4739.2 1142.38
  4781.3 1142.61  4824.1 1141.33  4838.2 1140.01  4866.5 1138.79  4894.8 1136.27
  4908.9 1135.92  4937.2 1136.88  4951.3 1136.22  4974.6 1133.68  4975.1 1133.18
  4984.6 1133.68  4993.8  1136.9  5004.4 1141.98  5010.7 1141.98  5021.9 1145.19
  5030.3 1146.22    5061 1147.85    5075 1149.66  5111.3 1149.29  5116.9 1150.36
  5142.1 1151.21  5186.8  1156.2  5200.8 1158.48  5245.5 1159.48  5260.6 1160.79
#Mann= 4 ,-1 , 0
  4512.9     .12       0  4781.3    .035       0  4974.6     .05       0
  4984.6     .12       0
Bank Sta=4974.6,4984.6
XS Rating Curve= 0 ,0
Exp/Cntr=0.3,0.1

Type RM Length L Ch R = 1 ,177816  ,441,441,441
BEGIN DESCRIPTION:
Dry Comal Creek 242.0
END DESCRIPTION:
XS GIS Cut Line= 4
      2195524.98     13830425.01        2195825.       13830275.
        2196075.       13830025.      2196119.41     13829980.59
#Sta/Elev= 30
  4659.8 1151.49  4682.2 1150.87  4704.5 1149.37  4771.6  1148.6  4861.1 1145.93
  4891.8 1144.04  4897.4 1142.59  4914.2 1141.35  4919.8 1139.16  4958.9  1138.4
  4981.3 1136.86  4992.4 1134.91  5032.6 1134.72  5033.1 1134.22  5042.2 1134.22
  5042.7 1134.72  5108.4 1135.75  5136.7 1137.31  5193.2 1141.93  5235.7 1148.64
  5263.9  1150.2  5278.1 1151.46  5292.2    1154  5306.4 1155.85  5320.5 1156.91
  5334.6 1157.17  5362.9  1158.8  5390.5 1159.31  5404.9  1160.6  5411.6  1160.6
#Mann= 4 ,-1 , 0
  4659.8     .12       0  5032.6     .05       0  5042.7     .12       0
  5390.5     .07       0
Bank Sta=5032.6,5042.7
XS Rating Curve= 0 ,0
Exp/Cntr=0.3,0.1

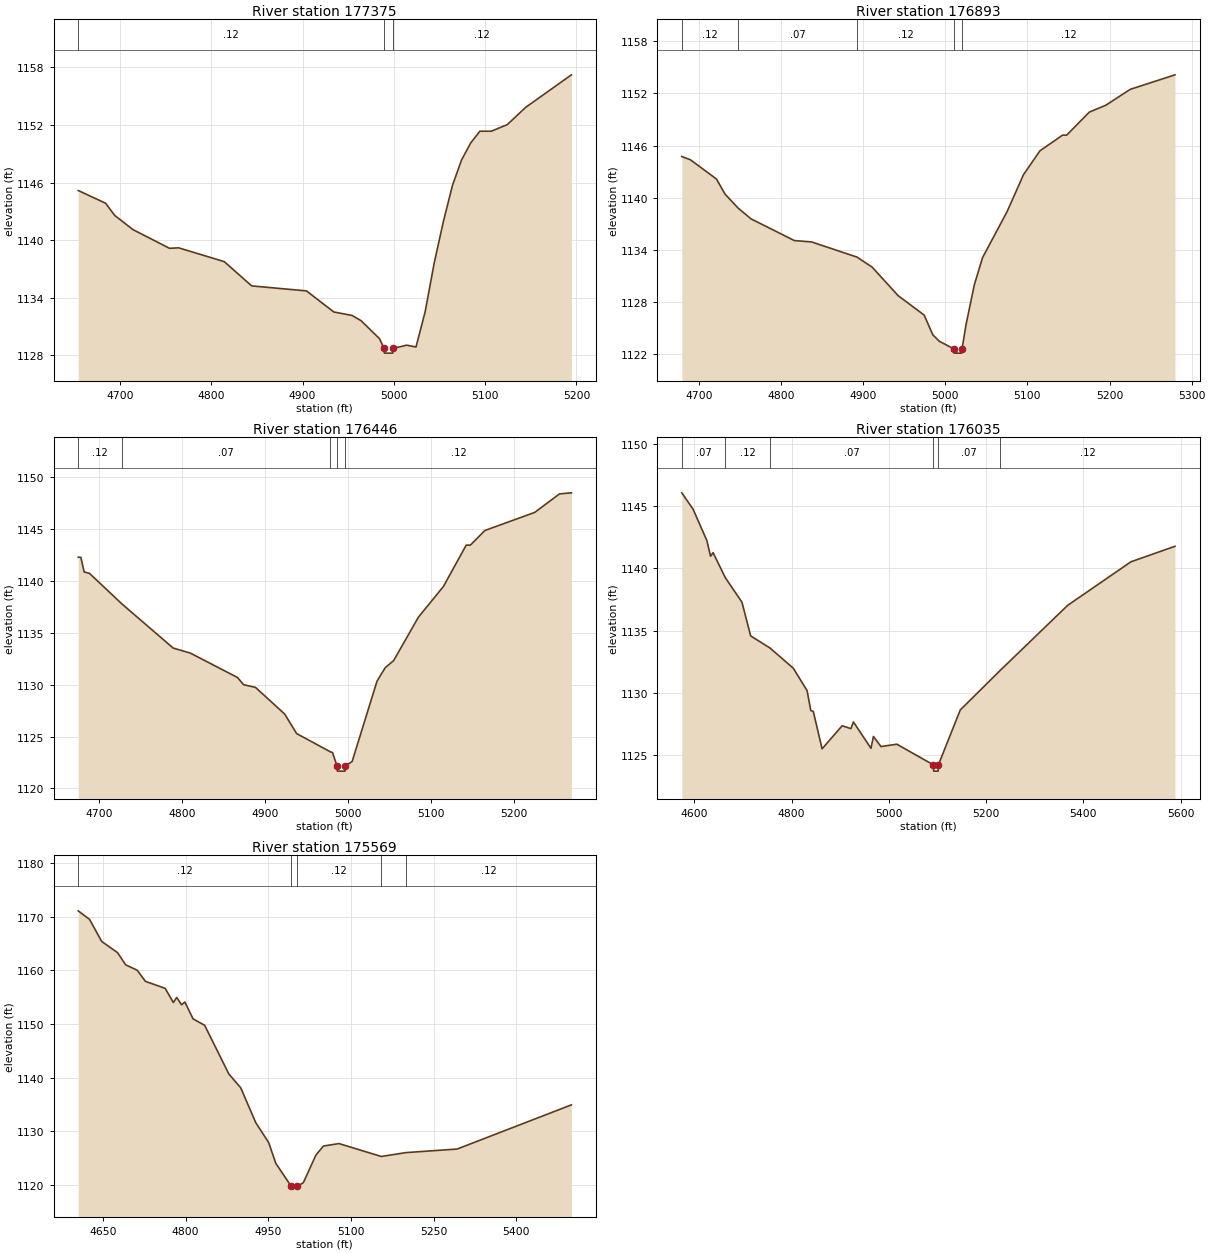
Type RM Length L Ch R = 1 ,177375  ,482,482,482
BEGIN DESCRIPTION:
Dry Comal Creek 241.0
END DESCRIPTION:
XS GIS Cut Line= 4
      2195825.05       13830525.        2196175.       13830525.
        2196275.       13830525.      2196365.25       13830525.
#Sta/Elev= 30
  4654.3 1145.17  4684.3 1143.84  4694.3 1142.57  4714.3 1141.09  4754.3 1139.14
  4764.3 1139.19  4814.3 1137.75  4844.3 1135.22  4904.3  1134.7  4934.3  1132.5
  4954.3 1132.14  4964.3 1131.58  4984.3 1129.72  4989.2 1128.71  4989.7 1128.21
  4998.8 1128.21  4999.3 1128.71  5014.3 1129.04  5024.3 1128.85  5034.3 1132.52
  5044.3 1137.64  5054.3 1141.94  5064.3 1145.72  5074.3 1148.38  5084.3 1150.14
  5094.3 1151.35  5106.8 1151.35  5124.3 1152.04  5144.3 1153.83  5194.5 1157.23
#Mann= 3 ,-1 , 0
  4654.3     .12       0  4989.2     .05       0  4999.3     .12       0
Bank Sta=4989.2,4999.3
XS Rating Curve= 0 ,0
Exp/Cntr=0.3,0.1

Type RM Length L Ch R = 1 ,176893  ,447,447,447
BEGIN DESCRIPTION:
Dry Comal Creek 240.0
END DESCRIPTION:
XS GIS Cut Line= 4
      2195774.98     13830874.99        2196075.       13830975.
        2196225.       13830975.      2196359.35       13830975.
#Sta/Elev= 30
  4679.1 1144.74  4689.7 1144.36  4721.3 1142.15  4731.8 1140.41  4747.7  1138.8
  4763.4 1137.56  4816.1 1135.06  4837.2  1134.9  4892.5 1133.15    4911 1131.99
  4942.6 1128.71  4974.3 1126.47  4984.8  1124.2  4992.7 1123.46  5010.3 1122.59
  5010.8 1122.09  5019.9 1122.09  5020.4 1122.59  5025.3 1125.39  5035.3 1129.94
  5045.3 1133.08  5075.3  1138.4  5095.3 1142.66  5115.3  1145.4  5142.8  1147.2
  5147.8  1147.2  5175.3 1149.85  5195.3 1150.64  5225.3 1152.48  5279.7 1154.15
#Mann= 5 ,-1 , 0
  4679.1     .12       0  4747.7     .07       0  4892.5     .12       0
  5010.3     .05       0  5020.4     .12       0
Bank Sta=5010.3,5020.4
XS Rating Curve= 0 ,0
Exp/Cntr=0.3,0.1

Type RM Length L Ch R = 1 ,176446  ,411,411,411
BEGIN DESCRIPTION:
Dry Comal Creek 239.0
END DESCRIPTION:
XS GIS Cut Line= 4
      2195674.99       13831175.        2195925.       13831375.
        2196075.       13831375.      2196199.34       13831375.
#Sta/Elev= 30
  4674.8 1142.28    4678 1142.28    4682 1140.86  4688.4 1140.73  4727.4 1137.79
  4789.3 1133.53  4810.1 1133.04  4866.9 1130.69  4874.1    1130  4888.5 1129.74
  4923.7 1127.17  4938.1 1125.29  4978.8 1123.53  4981.4 1123.46  4986.7 1122.17
  4987.2 1121.67  4996.4 1121.67  4996.9 1122.17    5005  1122.6    5035 1130.34
    5045 1131.65    5055 1132.32    5085 1136.52    5115 1139.46  5142.5 1143.45
  5147.5 1143.45    5165 1144.86    5225  1146.6    5255 1148.39  5269.3 1148.49
#Mann= 5 ,-1 , 0
  4674.8     .12       0  4727.4     .07       0  4978.8     .12       0
  4986.7     .05       0  4996.9     .12       0
Bank Sta=4986.7,4996.9
XS Rating Curve= 0 ,0
Exp/Cntr=0.3,0.1

Type RM Length L Ch R = 1 ,176035  ,466,466,466
BEGIN DESCRIPTION:
Dry Comal Creek 238.0
END DESCRIPTION:
XS GIS Cut Line= 3
      2195275.03     13831774.99        2195675.       13831675.
      2196275.04       13831725.
#Sta/Elev= 30
  4574.2 1146.07  4597.4 1144.76  4625.7 1142.25  4633.4 1140.98  4638.6 1141.27
  4663.6 1139.27  4697.9  1137.3  4715.9 1134.59  4755.6 1133.62  4803.5    1132
  4831.9  1130.2  4839.6  1128.6  4844.7 1128.53  4862.8 1125.53    4904 1127.38
  4922.1 1127.15  4927.2 1127.69  4963.3 1125.57  4968.4 1126.52  4983.9 1125.71
  5016.6  1125.9  5091.8 1124.24  5092.3 1123.74  5101.5 1123.74    5102 1124.24
    5147 1128.65  5228.6  1131.8  5367.8 1137.04  5498.2 1140.54  5588.6 1141.78
#Mann= 6 ,-1 , 0
  4574.2     .07       0  4663.6     .12       0  4755.6     .07       0
  5091.8     .05       0    5102     .07       0  5228.6     .12       0
Bank Sta=5091.8,5102
XS Rating Curve= 0 ,0
Exp/Cntr=0.3,0.1

Type RM Length L Ch R = 1 ,175569  ,446,446,446
BEGIN DESCRIPTION:
Dry Comal Creek 237.0
END DESCRIPTION:
XS GIS Cut Line= 3
      2195400.46     13832400.07        2195625.       13832075.
      2196025.01     13831774.99
#Sta/Elev= 30
    4605  1171.1  4625.6 1169.51  4647.6  1165.4  4676.3 1163.32  4691.2 1161.04
  4712.1 1160.03    4727 1157.96  4762.8 1156.66  4777.7 1154.02  4783.8 1154.96
  4792.6  1153.6  4798.6 1154.11  4813.5 1150.97  4834.5 1149.77  4878.5 1140.69
    4900 1138.12  4927.2 1131.64  4950.7 1127.93  4963.6 1124.06  4991.8 1119.75
  4992.3 1119.25  5002.2 1119.75  5013.6 1120.45  5036.5 1125.61  5050.1 1127.28
  5078.2 1127.74  5155.1 1125.33  5199.4 1126.05  5292.8 1126.72  5500.1 1134.95
#Mann= 5 ,-1 , 0
    4605     .12       0  4991.8     .05       0  5002.2     .12       0
  5155.1     .07       0  5199.4     .12       0
Bank Sta=4991.8,5002.2
XS Rating Curve= 0 ,0
Exp/Cntr=0.3,0.1