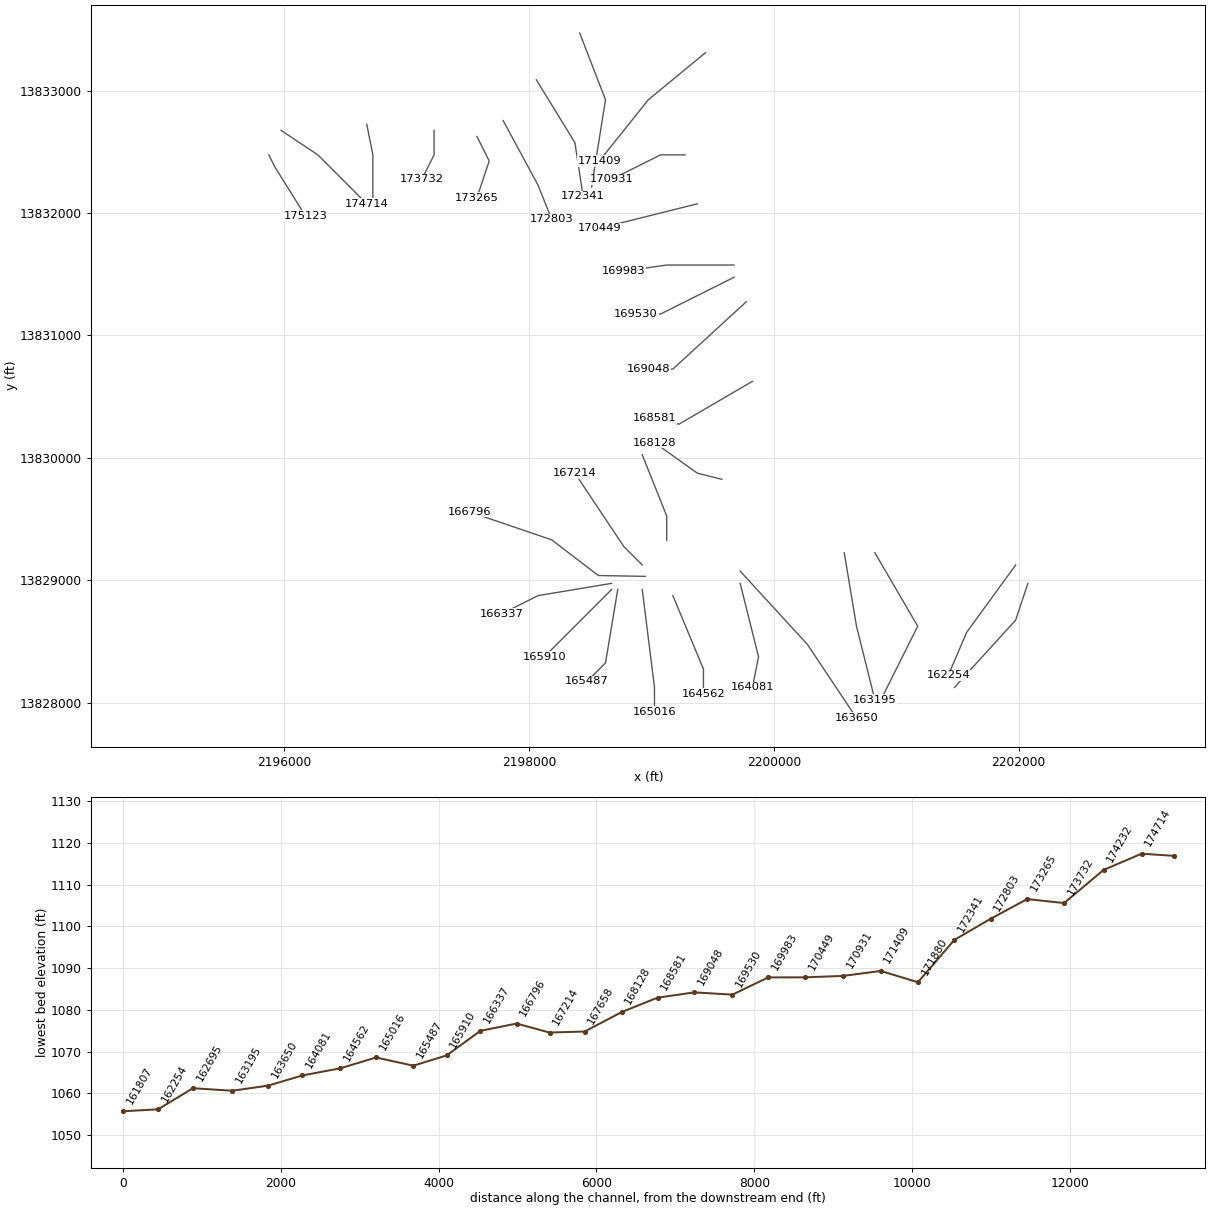
HEC-RAS study Dry Comal Creek.prj: Dry Comal Creek Base Level Engineering

--- Dry Comal Creek.g01 (geometry) --- (continued)

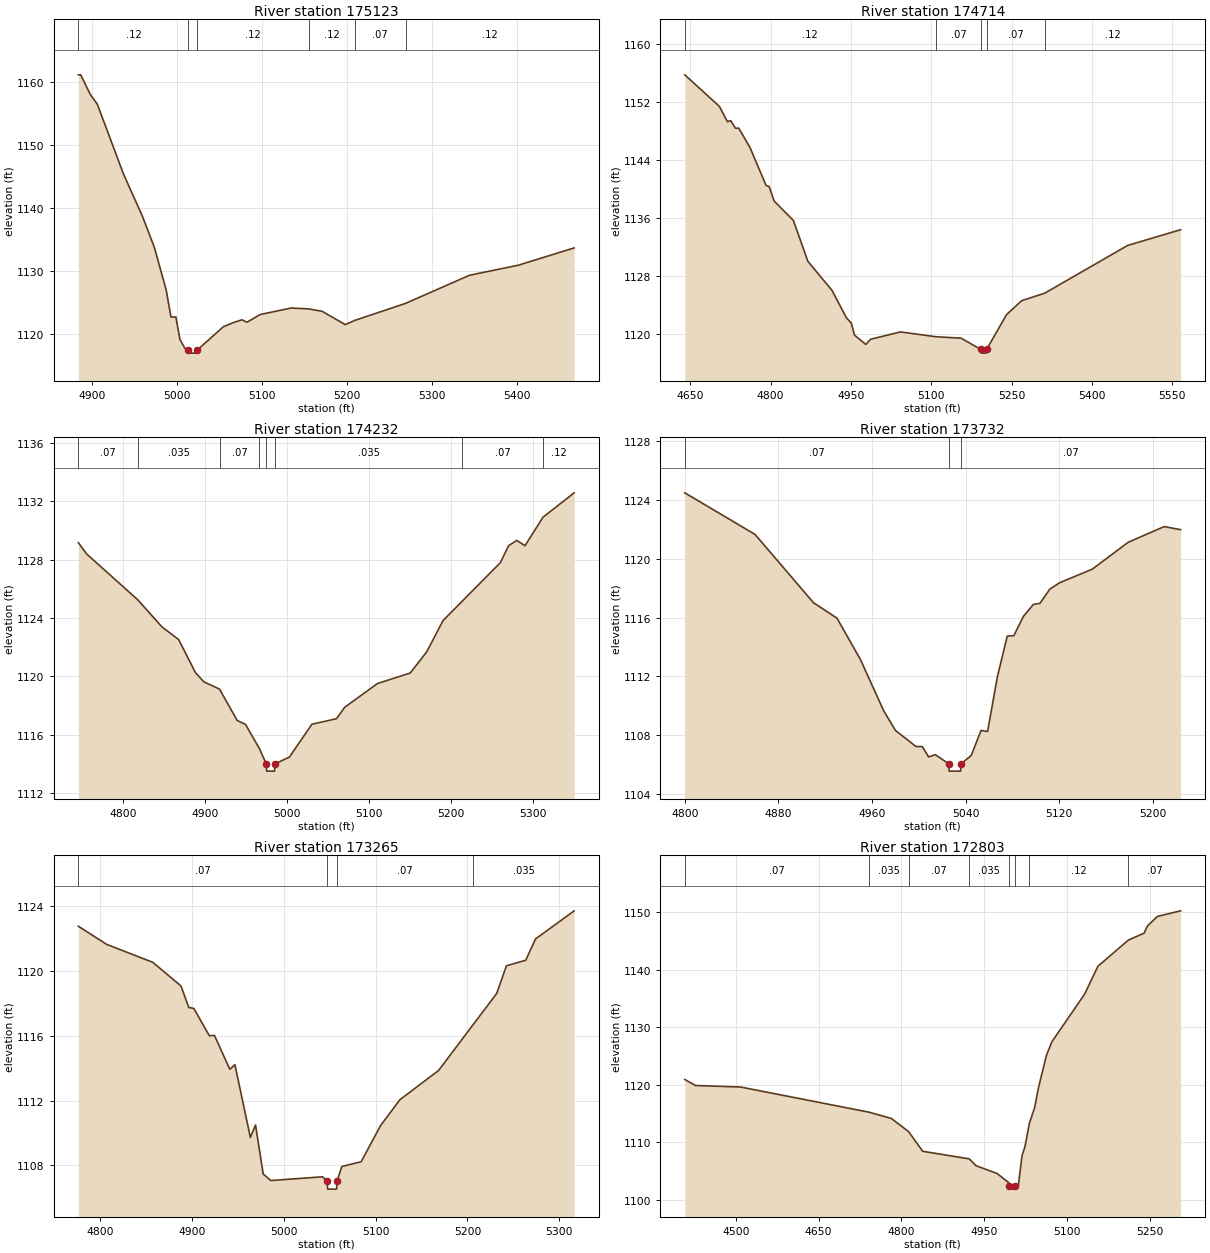
Type RM Length L Ch R = 1 ,175123  ,409,409,409
BEGIN DESCRIPTION:
Dry Comal Creek 236.0
END DESCRIPTION:
XS GIS Cut Line= 3
      2195874.99     13832475.02        2195925.       13832375.
      2196174.98     13831975.03
#Sta/Elev= 30
  4883.8 1161.13  4886.6 1161.13  4897.8 1158.04  4906.2 1156.44  4936.9 1145.37
  4959.3 1138.62  4973.3 1133.68  4987.2 1126.91  4992.8 1122.62  4998.6 1122.62
  5003.3 1119.08  5009.2 1117.64  5013.4 1117.38  5013.9 1116.88  5023.3 1116.88
  5023.8 1117.38  5054.6 1121.09    5067 1121.77  5076.4 1122.18  5082.3 1121.79
  5097.6 1123.01  5134.2 1124.05    5155 1123.91  5170.7 1123.53  5197.9 1121.42
  5209.1 1122.08  5268.9 1124.79  5344.1 1129.26  5401.9 1130.87  5467.3 1133.61
#Mann= 6 ,-1 , 0
  4883.8     .12       0  5013.4     .05       0  5023.8     .12       0
    5155     .12       0  5209.1     .07       0  5268.9     .12       0
Bank Sta=5013.4,5023.8
XS Rating Curve= 0 ,0
Exp/Cntr=0.3,0.1

Type RM Length L Ch R = 1 ,174714  ,482,482,482
BEGIN DESCRIPTION:
Dry Comal Creek 235.0
END DESCRIPTION:
XS GIS Cut Line= 3
      2195974.96     13832675.03        2196275.       13832475.
      2196675.01     13832074.99
#Sta/Elev= 30
  4639.6 1155.74  4704.2 1151.39  4719.3 1149.28  4725.3 1149.44  4734.3 1148.38
  4740.3  1148.4  4761.3 1145.75  4791.4 1140.51  4797.4 1140.33  4806.4 1138.37
  4842.5 1135.68  4869.5 1130.06  4914.6 1126.06  4941.6 1122.27  4950.6 1121.56
  4956.6 1119.89  4977.7 1118.61  4986.7 1119.32  5042.6 1120.33  5108.5 1119.67
  5155.8 1119.47  5192.9 1117.91  5193.4 1117.41  5202.9 1117.41  5203.4 1117.91
  5240.6  1122.7  5268.9 1124.63  5312.1 1125.67  5466.9 1132.24  5565.9 1134.41
#Mann= 5 ,-1 , 0
  4639.6     .12       0  5108.5     .07       0  5192.9     .05       0
  5203.4     .07       0  5312.1     .12       0
Bank Sta=5192.9,5203.4
XS Rating Curve= 0 ,0
Exp/Cntr=0.3,0.1

Type RM Length L Ch R = 1 ,174232  ,500,500,500
BEGIN DESCRIPTION:
Dry Comal Creek 234.0
END DESCRIPTION:
XS GIS Cut Line= 3
      2196674.99     13832725.04        2196725.       13832475.
        2196725.     13832124.99
#Sta/Elev= 30
  4745.1 1129.16  4755.3 1128.38  4817.7 1125.24  4847.1 1123.39  4867.5 1122.52
  4887.9 1120.27  4898.1 1119.63  4917.4 1119.13  4938.9 1116.98  4949.1 1116.71
  4965.8 1115.08  4974.4 1114.01  4974.9 1113.51  4984.5 1113.51    4985 1114.01
  5002.6 1114.47  5030.1 1116.72  5060.1  1117.1  5070.1 1117.88  5110.1 1119.51
  5150.1 1120.23  5170.1 1121.67  5190.1 1123.82  5213.7 1125.16  5260.1 1127.79
  5270.1 1128.95  5280.1 1129.31  5290.1 1128.95  5312.1  1130.9  5350.1 1132.57
#Mann= 8 ,-1 , 0
  4745.1     .07       0  4817.7    .035       0  4917.4     .07       0
  4965.8    .035       0  4974.4    .035       0    4985    .035       0
  5213.7     .07       0  5312.1     .12       0
Bank Sta=4974.4,4985
XS Rating Curve= 0 ,0
Exp/Cntr=0.3,0.1

Type RM Length L Ch R = 1 ,173732  ,467,467,467
BEGIN DESCRIPTION:
Dry Comal Creek 233.0
END DESCRIPTION:
XS GIS Cut Line= 3
        2197225.     13832675.01        2197225.       13832475.
      2197125.01     13832275.01
#Sta/Elev= 30
    4800 1124.46    4860 1121.64    4910    1117    4930 1115.96    4950 1113.16
    4970 1109.66    4980 1108.34  4997.5 1107.25  5002.8 1107.25  5008.4 1106.54
    5014  1106.7  5025.4 1106.08  5025.9 1105.58  5035.6 1105.58  5036.1 1106.08
  5044.7 1106.64  5053.1 1108.34  5058.7 1108.27  5067.1    1112  5075.5 1114.74
  5081.1 1114.77  5089.4 1116.09  5097.8 1116.89  5103.4 1116.96  5111.8 1117.92
  5120.2 1118.36  5148.1 1119.28  5178.9 1121.11  5209.6 1122.17  5223.6 1121.96
#Mann= 3 ,-1 , 0
    4800     .07       0  5025.4     .05       0  5036.1     .07       0
Bank Sta=5025.4,5036.1
XS Rating Curve= 0 ,0
Exp/Cntr=0.3,0.1

Type RM Length L Ch R = 1 ,173265  ,462,462,462
BEGIN DESCRIPTION:
Dry Comal Creek 232.0
END DESCRIPTION:
XS GIS Cut Line= 3
      2197574.99     13832625.01        2197675.       13832425.
      2197575.01     13832125.04
#Sta/Elev= 30
  4776.4 1122.77  4807.2 1121.65  4857.5 1120.54  4888.2 1119.08  4896.6 1117.76
  4902.2 1117.69    4919 1116.01  4924.6 1116.03  4941.3 1113.94  4946.9 1114.22
  4963.7 1109.73  4969.3  1110.5  4977.7 1107.47    4986 1107.07  5042.2  1107.3
  5047.3 1107.04  5047.8 1106.54  5057.6 1106.54  5058.1 1107.04  5063.3 1107.94
  5084.3 1108.23  5105.4 1110.46  5126.5 1112.06  5168.7 1113.87  5205.9 1116.67
  5231.9 1118.62  5242.5 1120.33  5263.5 1120.67  5274.1 1121.98  5316.2 1123.72
#Mann= 4 ,-1 , 0
  4776.4     .07       0  5047.3     .05       0  5058.1     .07       0
  5205.9    .035       0
Bank Sta=5047.3,5058.1
XS Rating Curve= 0 ,0
Exp/Cntr=0.3,0.1

Type RM Length L Ch R = 1 ,172803  ,462,462,462
BEGIN DESCRIPTION:
Dry Comal Creek 231.0
END DESCRIPTION:
XS GIS Cut Line= 3
      2197789.35     13832754.23        2198075.       13832225.
      2198184.89      13831949.4
#Sta/Elev= 30
  4407.7 1120.91    4427 1119.86  4508.9 1119.59  4741.4 1115.22  4781.8 1114.13
  4812.9 1111.86  4838.6 1108.42  4922.9  1107.1  4935.3 1105.91  4973.4 1104.56
  4995.3  1102.9  4995.6 1102.34  4996.1 1101.84  5005.9 1101.84  5006.4 1102.34
  5011.8 1102.44  5018.5 1107.64  5023.9 1109.24  5031.8 1113.26  5041.4 1116.01
  5048.2 1119.43  5062.9 1125.14  5072.5 1127.44  5131.8 1135.73    5156 1140.59
  5211.1 1145.14  5239.6 1146.34  5245.9 1147.62  5263.9 1149.26  5305.8 1150.23
#Mann= 8 ,-1 , 0
  4407.7     .07       0  4741.4    .035       0  4812.9     .07       0
  4922.9    .035       0  4995.6    .035       0  5006.4    .035       0
  5031.8     .12       0  5211.1     .07       0
Bank Sta=4995.6,5006.4
XS Rating Curve= 0 ,0
Exp/Cntr=0.3,0.1

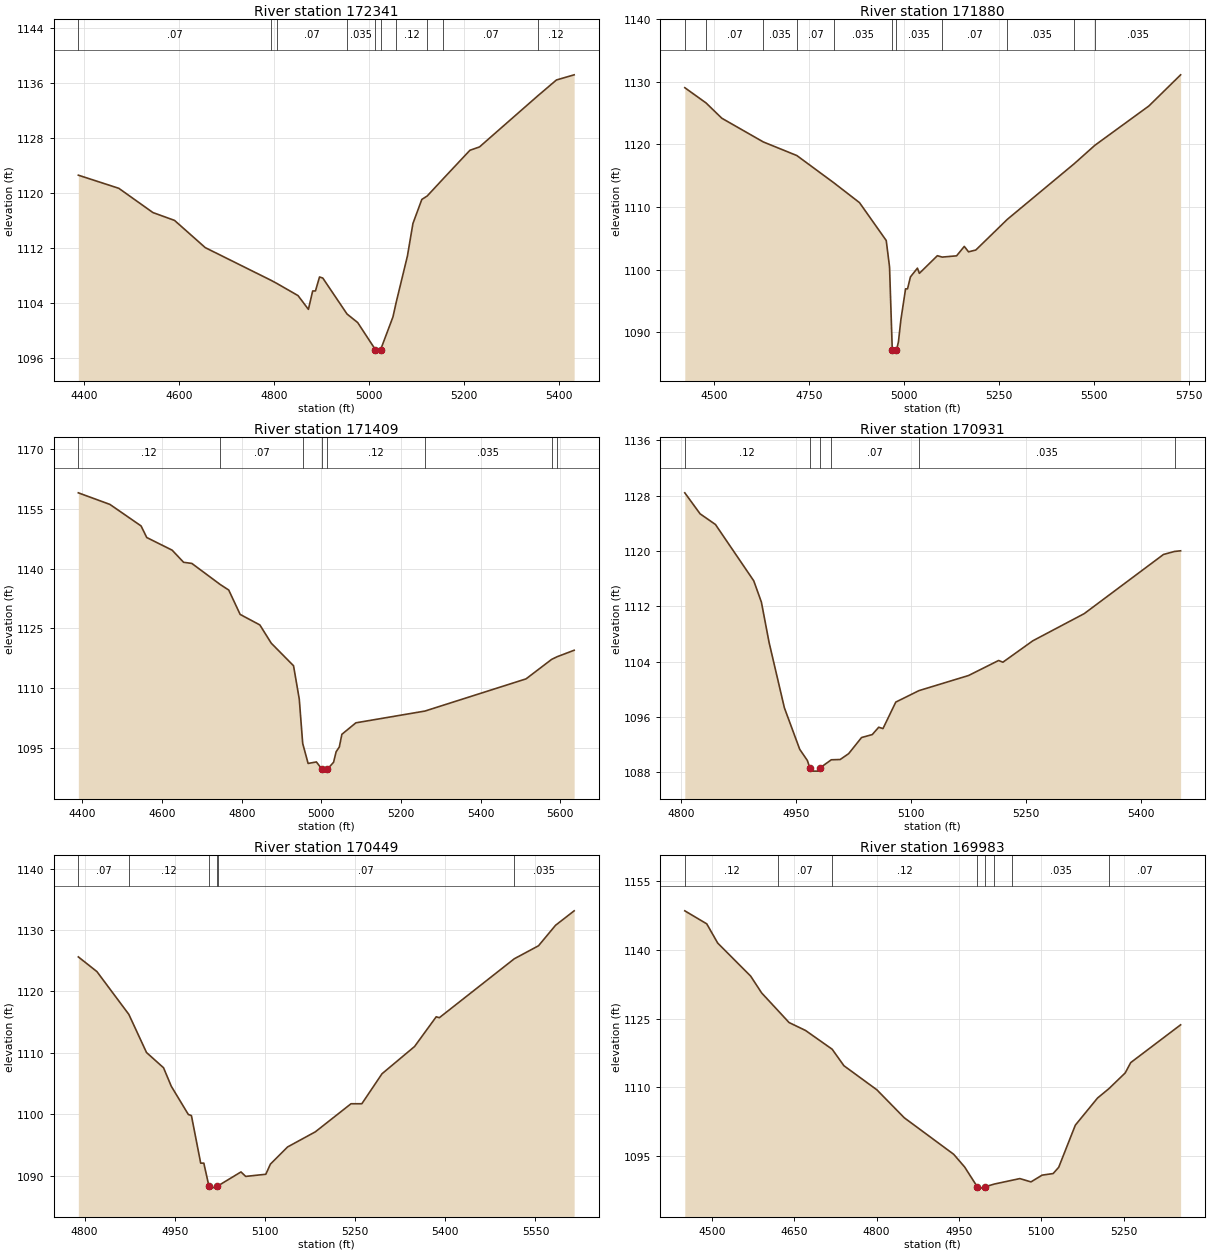
Type RM Length L Ch R = 1 ,172341  ,461,461,461
BEGIN DESCRIPTION:
Dry Comal Creek 230.0
END DESCRIPTION:
XS GIS Cut Line= 3
      2198060.18     13833087.57        2198375.       13832575.
      2198441.82     13832138.11
#Sta/Elev= 30
  4387.9 1122.64  4473.1 1120.73  4544.9  1117.2  4590.4 1116.06    4655  1112.1
  4793.6 1107.34  4805.2 1106.91  4850.3 1105.12  4872.1 1103.12  4881.1 1105.79
    4887  1105.8  4895.5 1107.83  4902.4 1107.67  4953.4 1102.44  4975.8  1101.2
  5013.2 1097.25  5013.7 1096.75  5024.1 1097.25  5050.1 1102.03    5057 1104.18
  5080.5 1110.88  5092.1 1115.61  5110.8 1119.11  5122.1 1119.61  5156.1 1122.14
    5212 1126.26  5232.2 1126.75  5354.3 1134.15  5394.1 1136.49  5431.4 1137.24
#Mann= 10 ,-1 , 0
  4387.9     .07       0  4793.6    .035       0  4805.2     .07       0
  4953.4    .035       0  5013.2    .035       0  5024.1    .035       0
    5057     .12       0  5122.1    .035       0  5156.1     .07       0
  5354.3     .12       0
Bank Sta=5013.2,5024.1
XS Rating Curve= 0 ,0
Exp/Cntr=0.3,0.1

Type RM Length L Ch R = 1 ,171880  ,471,471,471
BEGIN DESCRIPTION:
Dry Comal Creek 229.0
END DESCRIPTION:
XS GIS Cut Line= 3
      2198414.33     13833469.55        2198625.       13832925.
      2198511.54     13832212.56
#Sta/Elev= 30
  4423.5 1129.08  4479.3 1126.65  4520.9  1124.2  4630.4  1120.4  4718.5 1118.23
  4815.7 1113.88  4883.4  1110.7  4953.8 1104.64  4962.5 1100.43  4969.7 1087.13
  4970.2 1086.63  4980.8 1087.13  4985.9 1088.42  4992.4 1091.98  5004.7 1096.91
  5009.9 1096.91  5017.5 1098.82  5035.9 1100.22    5041 1099.39  5088.4 1102.21
  5101.1 1101.99    5139 1102.19  5159.3  1103.7  5170.4 1102.83  5189.6 1103.12
  5272.5 1108.02  5449.2 1116.95  5503.1 1119.87  5645.3 1126.16  5728.8 1131.14
#Mann= 11 ,-1 , 0
  4423.5    .035       0  4479.3     .07       0  4630.4    .035       0
  4718.5     .07       0  4815.7    .035       0  4969.7    .035       0
  4980.8    .035       0  5101.1     .07       0  5272.5    .035       0
  5449.2     .07       0  5503.1    .035       0
Bank Sta=4969.7,4980.8
XS Rating Curve= 0 ,0
Exp/Cntr=0.3,0.1

Type RM Length L Ch R = 1 ,171409  ,478,478,478
BEGIN DESCRIPTION:
Dry Comal Creek 228.0
END DESCRIPTION:
XS GIS Cut Line= 3
      2199442.07      13833309.8        2198975.       13832925.
      2198574.99     13832424.98
#Sta/Elev= 30
  4389.6 1158.93    4469 1156.03  4547.2 1150.65  4561.5 1147.75  4625.3 1144.59
    4654 1141.56  4674.8 1141.27  4746.5 1135.97  4767.4 1134.62  4796.1 1128.52
  4845.6 1125.89  4874.2 1121.33  4930.2 1115.68  4944.6 1107.35  4953.2 1096.26
  4966.8 1091.25  4987.6 1091.63  5001.5 1089.83    5002 1089.33  5015.3 1089.83
  5030.8 1091.55  5037.2 1094.18  5045.2 1095.37  5051.6 1098.54  5086.8 1101.41
  5260.2 1104.35  5514.2  1112.4  5578.5 1117.27  5591.8 1117.92  5635.1 1119.56
#Mann= 8 ,-1 , 0
  4389.6     .12       0  4746.5     .07       0  4953.2     .12       0
  5001.5     .05       0  5015.3     .12       0  5260.2    .035       0
  5578.5     .07       0  5591.8    .035       0
Bank Sta=5001.5,5015.3
XS Rating Curve= 0 ,0
Exp/Cntr=0.3,0.1

Type RM Length L Ch R = 1 ,170931  ,482,482,482
BEGIN DESCRIPTION:
Dry Comal Creek 227.0
END DESCRIPTION:
XS GIS Cut Line= 3
      2199274.97       13832475.        2199075.       13832475.
      2198674.99     13832274.99
#Sta/Elev= 30
  4804.6 1128.41  4824.6 1125.37  4844.6 1123.83  4894.6 1115.68  4904.6 1112.59
  4914.6 1106.77  4934.6  1097.3  4954.6  1091.3  4964.6 1089.68  4967.7 1088.64
  4968.2 1088.14    4981 1088.14  4981.5 1088.64  4995.8 1089.78  5007.4 1089.82
  5018.5 1090.67  5035.3    1093  5049.3 1093.43  5057.7 1094.49  5063.3  1094.3
    5080 1098.13  5110.3 1099.79  5175.1 1101.98  5214.2 1104.15  5219.8  1103.9
  5258.9    1107    5326 1110.93  5429.4 1119.49  5443.9 1119.93  5451.8 1120.02
#Mann= 6 ,-1 , 0
  4804.6     .12       0  4967.7     .05       0  4981.5     .12       0
  4995.8     .07       0  5110.3    .035       0  5443.9     .07       0
Bank Sta=4967.7,4981.5
XS Rating Curve= 0 ,0
Exp/Cntr=0.3,0.1

Type RM Length L Ch R = 1 ,170449  ,466,466,466
BEGIN DESCRIPTION:
Dry Comal Creek 226.0
END DESCRIPTION:
XS GIS Cut Line= 3
      2199374.97     13832074.99        2199175.       13832025.
      2198574.99       13831875.
#Sta/Elev= 30
  4789.7 1125.61  4820.6 1123.22  4873.7 1116.25  4903.1 1110.04  4931.4 1107.56
  4944.3 1104.55  4972.6 1099.96  4977.8 1099.77  4993.2 1092.03  4998.4 1092.03
  5006.9  1088.3  5007.4  1087.8  5020.8  1088.3  5022.1 1088.34  5060.2  1090.6
    5068 1089.87  5101.5 1090.22  5109.2 1091.88  5137.6 1094.66  5183.9 1097.13
  5243.2  1101.7  5261.2  1101.7  5294.7 1106.58  5348.9 1111.02  5384.9 1115.86
  5390.1 1115.71  5514.7  1125.3    5555 1127.42  5583.4 1130.76  5614.3 1133.11
#Mann= 6 ,-1 , 0
  4789.7     .07       0  4873.7     .12       0  5006.9     .05       0
  5020.8     .12       0  5022.1     .07       0  5514.7    .035       0
Bank Sta=5006.9,5020.8
XS Rating Curve= 0 ,0
Exp/Cntr=0.3,0.1

Type RM Length L Ch R = 1 ,169983  ,453,453,453
BEGIN DESCRIPTION:
Dry Comal Creek 225.0
END DESCRIPTION:
XS GIS Cut Line= 3
      2199675.04       13831575.        2199125.       13831575.
      2198774.99       13831525.
#Sta/Elev= 30
  4450.4 1148.52  4490.4 1145.68  4510.4 1141.48  4570.4 1134.28  4590.4 1130.61
  4620.5 1126.72  4640.4 1124.14  4670.4 1122.41    4719 1118.31  4740.4 1114.71
  4800.4 1109.46  4850.4 1103.35  4940.4 1095.39  4960.4 1092.61  4983.5 1088.28
    4984 1087.78  4997.4 1088.28  5014.6 1088.89  5047.3 1089.73    5061 1090.08
  5081.3 1089.36  5101.5 1090.83  5121.7 1091.18  5131.8 1092.54  5162.1 1101.74
  5202.5 1107.65  5223.4 1109.72    5253 1113.14  5263.1  1115.4    5354 1123.64
#Mann= 8 ,-1 , 0
  4450.4     .12       0  4620.5     .07       0    4719     .12       0
  4983.5     .05       0  4997.4     .12       0  5014.6     .07       0
  5047.3    .035       0  5223.4     .07       0
Bank Sta=4983.5,4997.4
XS Rating Curve= 0 ,0
Exp/Cntr=0.3,0.1

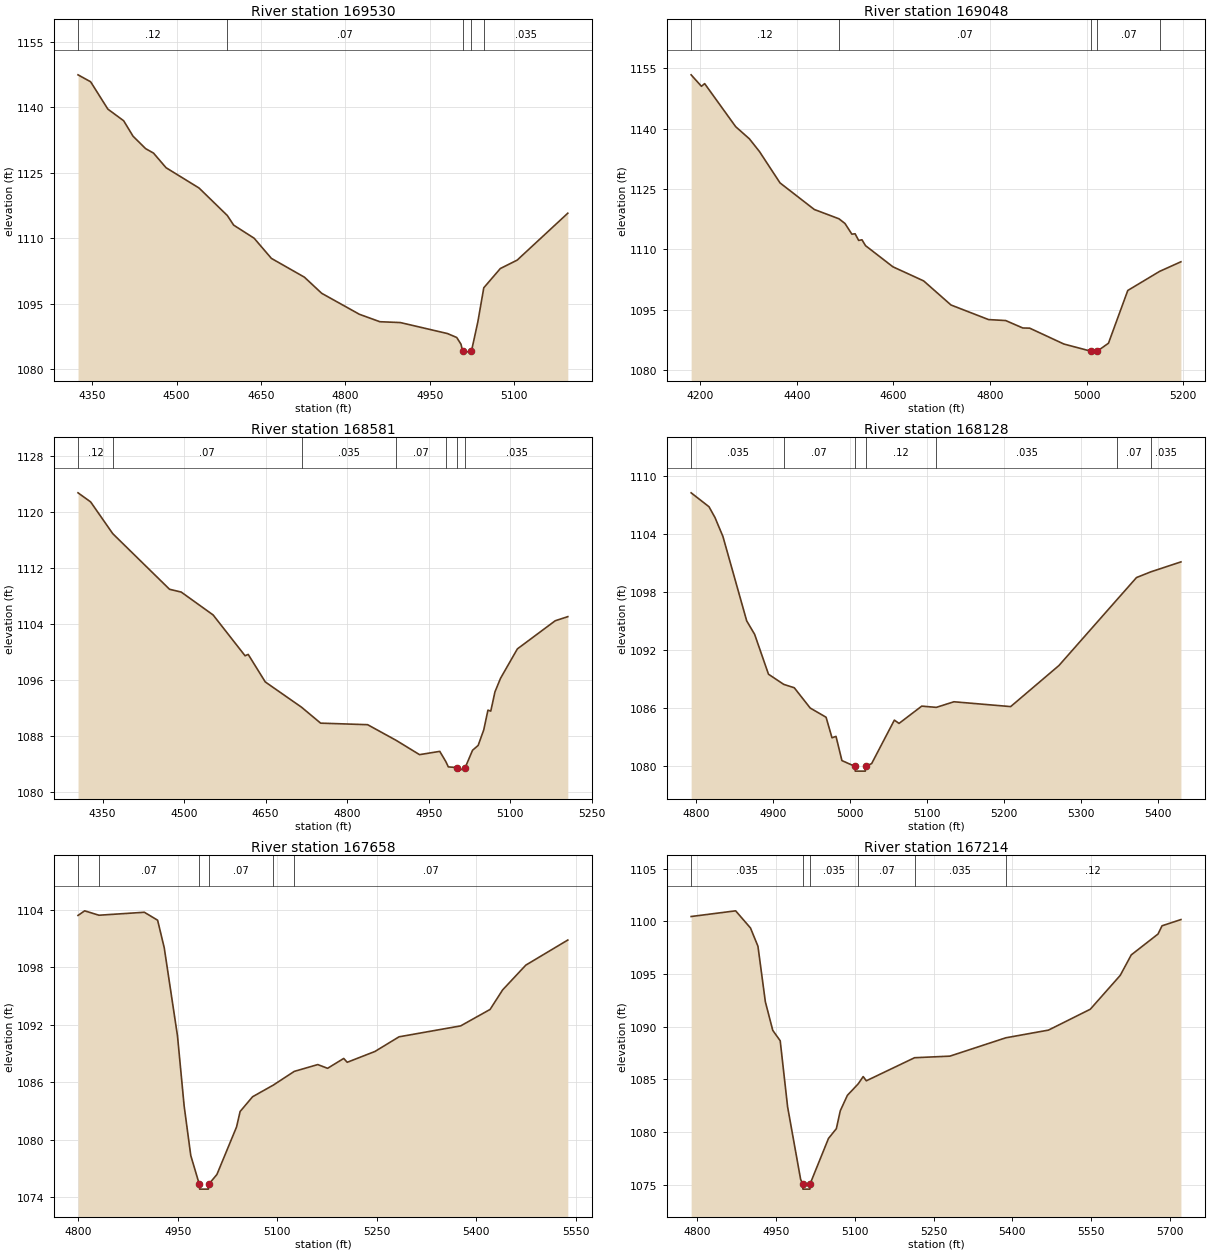
Type RM Length L Ch R = 1 ,169530  ,482,482,482
BEGIN DESCRIPTION:
Dry Comal Creek 224.0
END DESCRIPTION:
XS GIS Cut Line= 3
      2199675.01       13831475.        2199075.       13831175.
      2198875.03       13831175.
#Sta/Elev= 30
  4324.6 1147.38    4347 1145.79  4377.7 1139.52  4405.7 1136.87  4422.4 1133.33
  4444.8 1130.48  4458.8 1129.46  4481.1 1126.11  4539.8 1121.46  4590.1 1115.16
  4601.3 1112.97  4637.7 1109.97  4668.4 1105.35  4727.1 1101.05  4757.8 1097.36
  4824.9 1092.55  4861.3 1090.85  4897.6 1090.66  4981.5 1088.14  4997.9 1087.24
  5005.4 1085.72  5008.4 1084.16  5008.9 1083.66  5022.4 1084.16  5025.4 1084.89
  5035.4 1090.79    5046 1098.62  5075.4 1103.03  5105.4 1104.96  5195.4  1115.7
#Mann= 5 ,-1 , 0
  4324.6     .12       0  4590.1     .07       0  5008.4     .05       0
  5022.4     .07       0    5046    .035       0
Bank Sta=5008.4,5022.4
XS Rating Curve= 0 ,0
Exp/Cntr=0.3,0.1

Type RM Length L Ch R = 1 ,169048  ,467,467,467
BEGIN DESCRIPTION:
Dry Comal Creek 223.0
END DESCRIPTION:
XS GIS Cut Line= 3
      2199774.99     13831274.99        2199175.       13830725.
      2198975.03       13830725.
#Sta/Elev= 30
  4181.5 1153.39  4202.8 1150.54  4209.5  1151.2  4273.7  1140.5    4302 1137.49
    4323 1134.31  4365.5 1126.52  4436.5 1119.91  4487.5  1117.6    4500 1116.43
  4514.2 1113.78  4520.9 1113.87  4528.3 1112.22  4535.1 1112.38  4542.5 1110.92
  4599.2 1105.66  4662.8 1102.16  4719.5 1096.16  4797.2 1092.54  4832.6  1092.3
  4868.1 1090.45  4882.3 1090.41  4953.2 1086.46  5008.4  1084.7  5008.9  1084.2
  5022.4  1084.7  5045.4 1086.66  5085.4 1099.78  5151.2 1104.52  5195.4 1106.91
#Mann= 5 ,-1 , 0
  4181.5     .12       0  4487.5     .07       0  5008.4     .05       0
  5022.4     .07       0  5151.2    .035       0
Bank Sta=5008.4,5022.4
XS Rating Curve= 0 ,0
Exp/Cntr=0.3,0.1

Type RM Length L Ch R = 1 ,168581  ,453,453,453
BEGIN DESCRIPTION:
Dry Comal Creek 222.0
END DESCRIPTION:
XS GIS Cut Line= 3
      2199825.03     13830625.02        2199225.       13830275.
      2199025.01       13830325.
#Sta/Elev= 30
  4304.9 1122.78  4328.1 1121.48  4368.8 1116.93  4473.2 1108.97  4494.7 1108.57
  4553.4 1105.29  4612.1 1099.45  4617.9 1099.64  4649.3  1095.7    4716 1092.08
  4751.1  1089.8  4837.5 1089.58  4889.7 1087.35    4933 1085.29  4970.2 1085.76
  4981.4 1084.29  4985.9 1083.54  5002.8 1083.43  5003.3 1082.93  5016.9 1083.43
  5030.5 1085.92  5040.8 1086.61  5051.1 1088.84  5058.8 1091.66    5064 1091.52
  5071.7 1094.28    5082 1096.23  5112.9 1100.43  5182.5 1104.46  5205.7 1105.05
#Mann= 7 ,-1 , 0
  4304.9     .12       0  4368.8     .07       0    4716    .035       0
  4889.7     .07       0  4981.4    .035       0  5002.8    .035       0
  5016.9    .035       0
Bank Sta=5002.8,5016.9
XS Rating Curve= 0 ,0
Exp/Cntr=0.3,0.1

Type RM Length L Ch R = 1 ,168128  ,470,470,470
BEGIN DESCRIPTION:
Dry Comal Creek 221.0
END DESCRIPTION:
XS GIS Cut Line= 3
      2199575.05     13829824.99        2199375.       13829875.
      2199025.02     13830124.99
#Sta/Elev= 30
  4793.9  1108.3  4817.1 1106.86  4824.9 1105.74  4835.2 1103.78  4866.1 1095.04
  4876.4 1093.65  4894.4 1089.52  4914.2 1088.47  4927.9 1088.12  4948.6 1086.02
  4969.2 1085.07  4976.9 1082.94  4982.1 1083.09  4989.8 1080.58  5006.6 1079.99
  5007.1 1079.49  5020.2 1079.49  5020.7 1079.99  5028.4 1080.27  5057.9 1084.77
    5064 1084.43  5093.5 1086.22  5112.4 1086.09  5135.3 1086.67    5209 1086.17
  5271.7 1090.42  5346.9 1097.22  5372.5 1099.53  5391.1 1100.12  5430.2 1101.15
#Mann= 7 ,-1 , 0
  4793.9    .035       0  4914.2     .07       0  5006.6     .05       0
  5020.7     .12       0  5112.4    .035       0  5346.9     .07       0
  5391.1    .035       0
Bank Sta=5006.6,5020.7
XS Rating Curve= 0 ,0
Exp/Cntr=0.3,0.1

Type RM Length L Ch R = 1 ,167658  ,444,444,444
BEGIN DESCRIPTION:
Dry Comal Creek 220.0
END DESCRIPTION:
XS GIS Cut Line= 3
        2199125.     13829325.04        2199125.       13829525.
      2198924.99     13830025.02
#Sta/Elev= 30
  4799.8 1103.42  4809.8  1103.9  4831.4 1103.44  4899.8 1103.75  4919.8 1102.92
  4929.8 1100.04  4949.8 1090.82  4959.8 1083.52  4969.8 1078.34  4982.7 1075.33
  4983.2 1074.83  4996.3 1074.83  4996.8 1075.33  5009.2 1076.36  5038.8 1081.32
  5044.2 1082.94    5063 1084.48  5094.3  1085.7  5125.9 1087.13  5161.3 1087.84
  5176.1 1087.45  5200.4 1088.48  5205.7 1088.08  5247.5 1089.21  5283.8 1090.74
  5376.7 1091.88  5421.1  1093.6    5440 1095.64    5475 1098.23  5538.3 1100.85
#Mann= 6 ,-1 , 0
  4799.8    .035       0  4831.4     .07       0  4982.7     .05       0
  4996.8     .07       0  5094.3    .035       0  5125.9     .07       0
Bank Sta=4982.7,4996.8
XS Rating Curve= 0 ,0
Exp/Cntr=0.3,0.1

Type RM Length L Ch R = 1 ,167214  ,418,418,418
BEGIN DESCRIPTION:
Dry Comal Creek 219.0
END DESCRIPTION:
XS GIS Cut Line= 3
      2198924.98     13829125.02        2198775.       13829275.
      2198375.01     13829874.99
#Sta/Elev= 30
  4787.9 1100.45  4872.7 1100.99    4901 1099.36  4915.2 1097.63  4929.3 1092.36
  4943.4 1089.65  4957.6 1088.66  4971.7 1082.39  4996.5 1075.51  5000.4 1075.08
  5000.9 1074.58  5014.1 1074.58  5014.6 1075.08  5049.6 1079.39  5064.6 1080.32
  5072.1 1082.02  5085.6 1083.48  5106.2 1084.57  5115.7 1085.26  5121.7 1084.86
  5213.6 1087.05  5280.9  1087.2  5387.4 1088.94  5468.7 1089.67  5548.4 1091.65
  5605.4 1094.86  5626.5 1096.81  5677.5 1098.79  5685.1 1099.57  5721.1 1100.16
#Mann= 6 ,-1 , 0
  4787.9    .035       0  5000.4    .035       0  5014.6    .035       0
  5106.2     .07       0  5213.6    .035       0  5387.4     .12       0
Bank Sta=5000.4,5014.6
XS Rating Curve= 0 ,0
Exp/Cntr=0.3,0.1

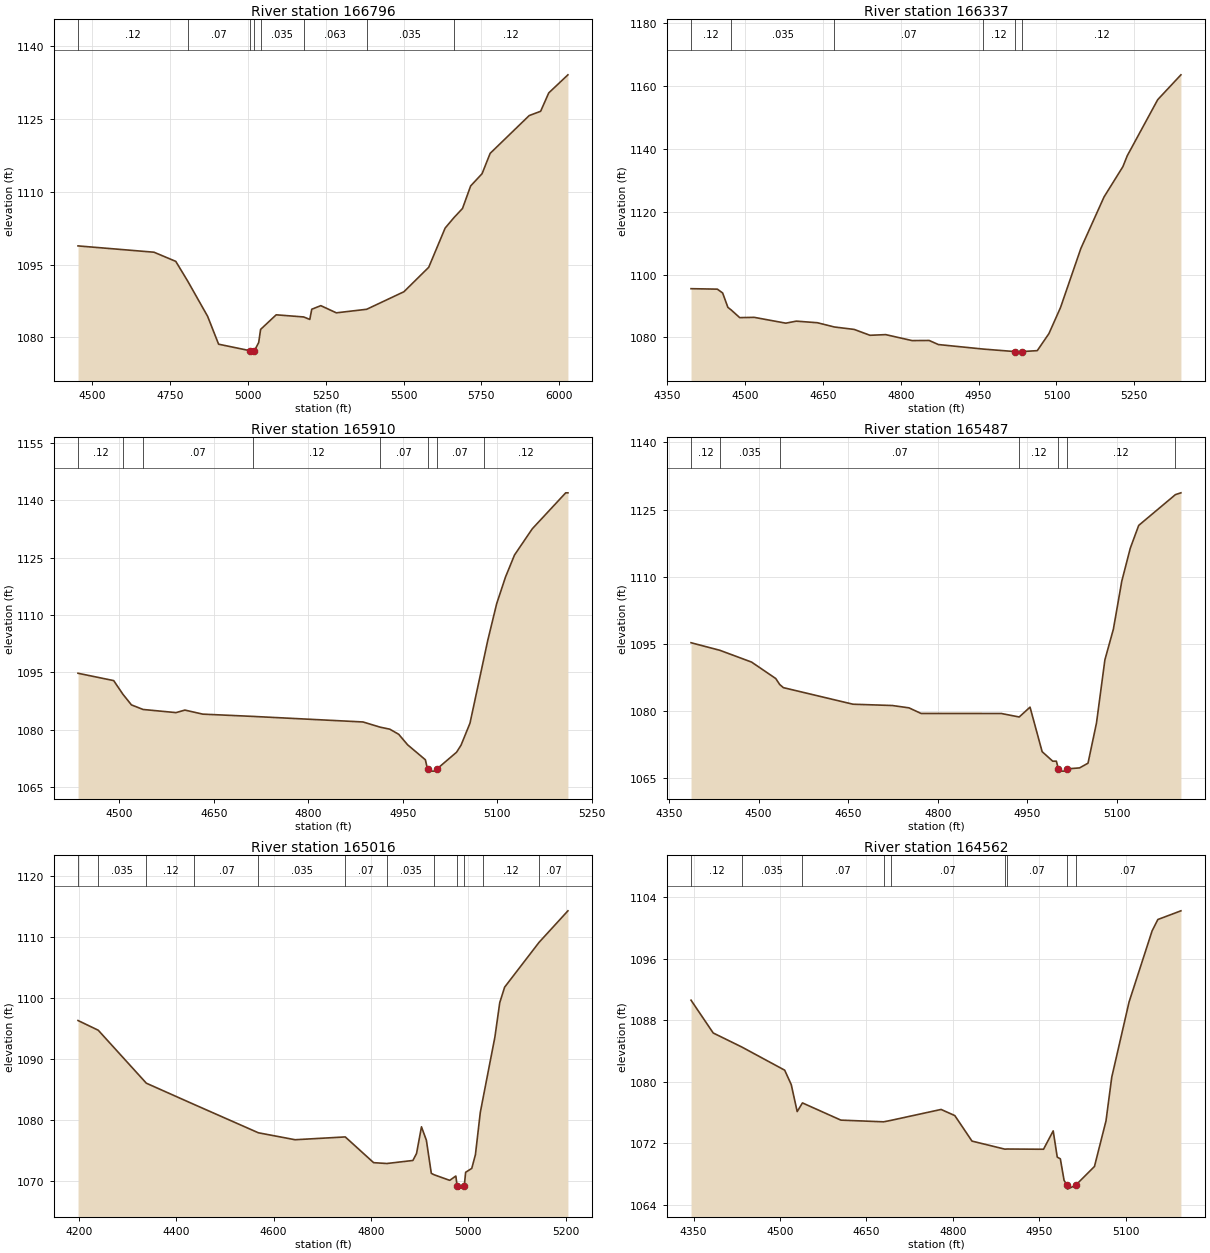
Type RM Length L Ch R = 1 ,166796  ,459,459,459
BEGIN DESCRIPTION:
X18974
END DESCRIPTION:
XS GIS Cut Line= 4
      2198949.06     13829032.05       2198567.1     13829038.99
      2198185.16     13829330.66      2197511.56     13829559.82
#Sta/Elev= 30
  4454.2 1098.84  4698.3 1097.54  4768.3 1095.65    4807 1091.54  4870.6 1084.32
  4905.9 1078.57  5006.8 1077.23  5007.3 1076.73    5021 1077.23  5034.7 1078.92
  5040.8 1081.62  5090.9 1084.63  5179.2 1084.19  5198.9 1083.68  5205.2 1085.78
  5234.3 1086.52  5284.1 1085.04  5381.6 1085.77  5501.4 1089.39    5581 1094.43
  5633.8 1102.52  5662.2 1104.68  5689.6 1106.56  5715.7  1111.2  5752.4 1113.73
  5778.5 1117.93  5903.9 1125.72  5940.6  1126.6  5966.7 1130.39  6028.3 1134.12
#Mann= 8 ,-1 , 0
  4454.2     .12       0    4807     .07       0  5006.8     .05       0
    5021     .07       0  5040.8    .035       0  5179.2    .063       0
  5381.6    .035       0  5662.2     .12       0
Bank Sta=5006.8,5021
XS Rating Curve= 0 ,0
Exp/Cntr=0.3,0.1

Type RM Length L Ch R = 1 ,166337  ,427,427,427
BEGIN DESCRIPTION:
Dry Comal Creek 218.0
END DESCRIPTION:
XS GIS Cut Line= 3
      2198675.03     13828975.01        2198075.       13828875.
      2197775.02     13828725.01
#Sta/Elev= 30
  4396.1 1095.51  4446.8 1095.36    4457 1094.14  4467.1 1089.56  4473.5 1088.73
  4489.9 1086.29  4517.8 1086.38  4578.6 1084.53  4598.9 1085.17  4639.4 1084.67
  4672.3 1083.31  4710.4 1082.54  4740.8 1080.67  4771.2 1080.88  4821.9 1078.98
  4854.9 1079.02  4872.6 1077.72  4959.1 1076.28  5019.5 1075.49    5020 1074.99
    5034 1075.49  5063.1 1075.78  5085.5  1081.2  5107.8 1089.48    5147  1108.3
  5191.7 1124.72    5228 1134.36  5236.4 1137.83  5295.1 1155.69  5339.8  1163.6
#Mann= 6 ,-1 , 0
  4396.1     .12       0  4473.5    .035       0  4672.3     .07       0
  4959.1     .12       0  5019.5     .05       0    5034     .12       0
Bank Sta=5019.5,5034
XS Rating Curve= 0 ,0
Exp/Cntr=0.3,0.1

Type RM Length L Ch R = 1 ,165910  ,423,423,423
BEGIN DESCRIPTION:
Dry Comal Creek 217.0
END DESCRIPTION:
XS GIS Cut Line= 3
        2198675.       13828925.        2198275.       13828525.
      2198125.01     13828375.01
#Sta/Elev= 30
  4434.3 1094.73  4490.9 1092.81  4505.6 1089.23  4519.1 1086.45  4537.6 1085.25
  4589.9 1084.43    4604 1085.09  4632.3 1084.03  4711.6 1083.44  4886.8 1081.98
    4914 1080.62  4929.3 1080.09  4943.4 1078.76  4957.6    1076  4985.8 1072.08
  4989.2 1069.61  4989.7 1069.11  5003.2 1069.11  5003.7 1069.61  5035.3 1074.06
  5042.4  1075.9  5056.6 1081.66  5078.6 1098.56  5084.8 1103.32    5099 1112.96
  5113.1 1119.97  5127.3 1125.69  5155.5 1132.55  5208.6 1141.97  5212.1 1141.97
#Mann= 8 ,-1 , 0
  4434.3     .12       0  4505.6    .035       0  4537.6     .07       0
  4711.6     .12       0    4914     .07       0  4989.2     .05       0
  5003.7     .07       0  5078.6     .12       0
Bank Sta=4989.2,5003.7
XS Rating Curve= 0 ,0
Exp/Cntr=0.3,0.1

Type RM Length L Ch R = 1 ,165487  ,471,471,471
BEGIN DESCRIPTION:
Dry Comal Creek 216.0
END DESCRIPTION:
XS GIS Cut Line= 3
        2198725.       13828925.        2198625.       13828325.
      2198475.01     13828175.01
#Sta/Elev= 30
  4386.9 1095.29  4435.2  1093.6  4488.3 1090.97  4528.8  1087.3  4535.4 1085.97
  4541.5 1085.27  4658.1 1081.57    4724 1081.28  4751.9 1080.76  4772.1 1079.51
  4906.5  1079.5  4936.5 1078.72  4954.6 1080.92  4974.9 1070.98  4992.6 1068.86
  4998.7 1068.86  5002.1 1067.14  5002.6 1066.64  5016.1 1066.64  5016.6 1067.14
  5037.6 1067.36  5051.7 1068.41  5065.9 1077.37    5080 1091.48  5094.2 1098.32
  5108.3 1109.05  5122.5 1116.38  5136.6 1121.47  5198.1 1128.34  5207.3 1128.74
#Mann= 7 ,-1 , 0
  4386.9     .12       0  4435.2    .035       0  4535.4     .07       0
  4936.5     .12       0  5002.1     .05       0  5016.6     .12       0
  5198.1     .07       0
Bank Sta=5002.1,5016.6
XS Rating Curve= 0 ,0
Exp/Cntr=0.3,0.1

Type RM Length L Ch R = 1 ,165016  ,454,454,454
BEGIN DESCRIPTION:
Dry Comal Creek 215.0
END DESCRIPTION:
XS GIS Cut Line= 3
        2198925.     13828924.96        2199025.       13828125.
        2199025.     13827924.99
#Sta/Elev= 30
  4198.4 1096.26  4239.9 1094.67  4338.7 1085.98  4437.5 1082.47  4568.8 1077.85
  4644.3 1076.71  4747.3 1077.17  4805.5 1072.95  4832.6 1072.81  4886.2 1073.31
  4893.7 1074.46  4903.8 1078.83  4913.9 1076.62    4924  1071.2  4929.9 1070.96
  4961.8 1070.05  4974.4 1070.76  4977.1 1069.11  4977.6 1068.61  4991.7 1069.11
  4994.5 1071.37  5007.1 1072.01  5014.6 1074.25  5024.6 1081.17  5030.1 1083.46
  5054.6 1093.54  5064.6  1099.2  5074.6 1101.73  5145.2 1109.07  5204.6 1114.25
#Mann= 12 ,-1 , 0
  4198.4     .12       0  4239.9    .035       0  4338.7     .12       0
  4437.5     .07       0  4568.8    .035       0  4747.3     .07       0
  4832.6    .035       0  4929.9     .07       0  4977.1     .05       0
  4991.7     .07       0  5030.1     .12       0  5145.2     .07       0
Bank Sta=4977.1,4991.7
XS Rating Curve= 0 ,0
Exp/Cntr=0.3,0.1

Type RM Length L Ch R = 1 ,164562  ,481,481,481
BEGIN DESCRIPTION:
Dry Comal Creek 214.0
END DESCRIPTION:
XS GIS Cut Line= 3
      2199174.99     13828875.03        2199425.       13828275.
        2199425.     13828075.03
#Sta/Elev= 30
  4345.7 1090.61  4384.2 1086.34  4433.7 1084.52  4508.2  1081.5  4519.6 1079.62
  4529.9 1076.11    4539 1077.24  4605.7    1075  4679.7 1074.78  4692.1 1074.96
  4779.6 1076.39  4803.4 1075.59  4833.2 1072.27  4890.4 1071.22  4893.8 1071.24
  4957.3 1071.21  4974.1  1073.6  4981.1 1070.19  4986.5 1069.96    4993 1067.15
  4998.4 1066.52  4998.9 1066.02    5013 1066.52  5045.7 1068.97  5065.7  1074.9
  5075.7 1080.59  5105.7 1090.37  5145.7 1099.63  5155.7 1101.11  5195.7 1102.24
#Mann= 9 ,-1 , 0
  4345.7     .12       0  4433.7    .035       0    4539     .07       0
  4679.7    .035       0  4692.1     .07       0  4890.4    .035       0
  4893.8     .07       0  4998.4     .05       0    5013     .07       0
Bank Sta=4998.4,5013
XS Rating Curve= 0 ,0
Exp/Cntr=0.3,0.1

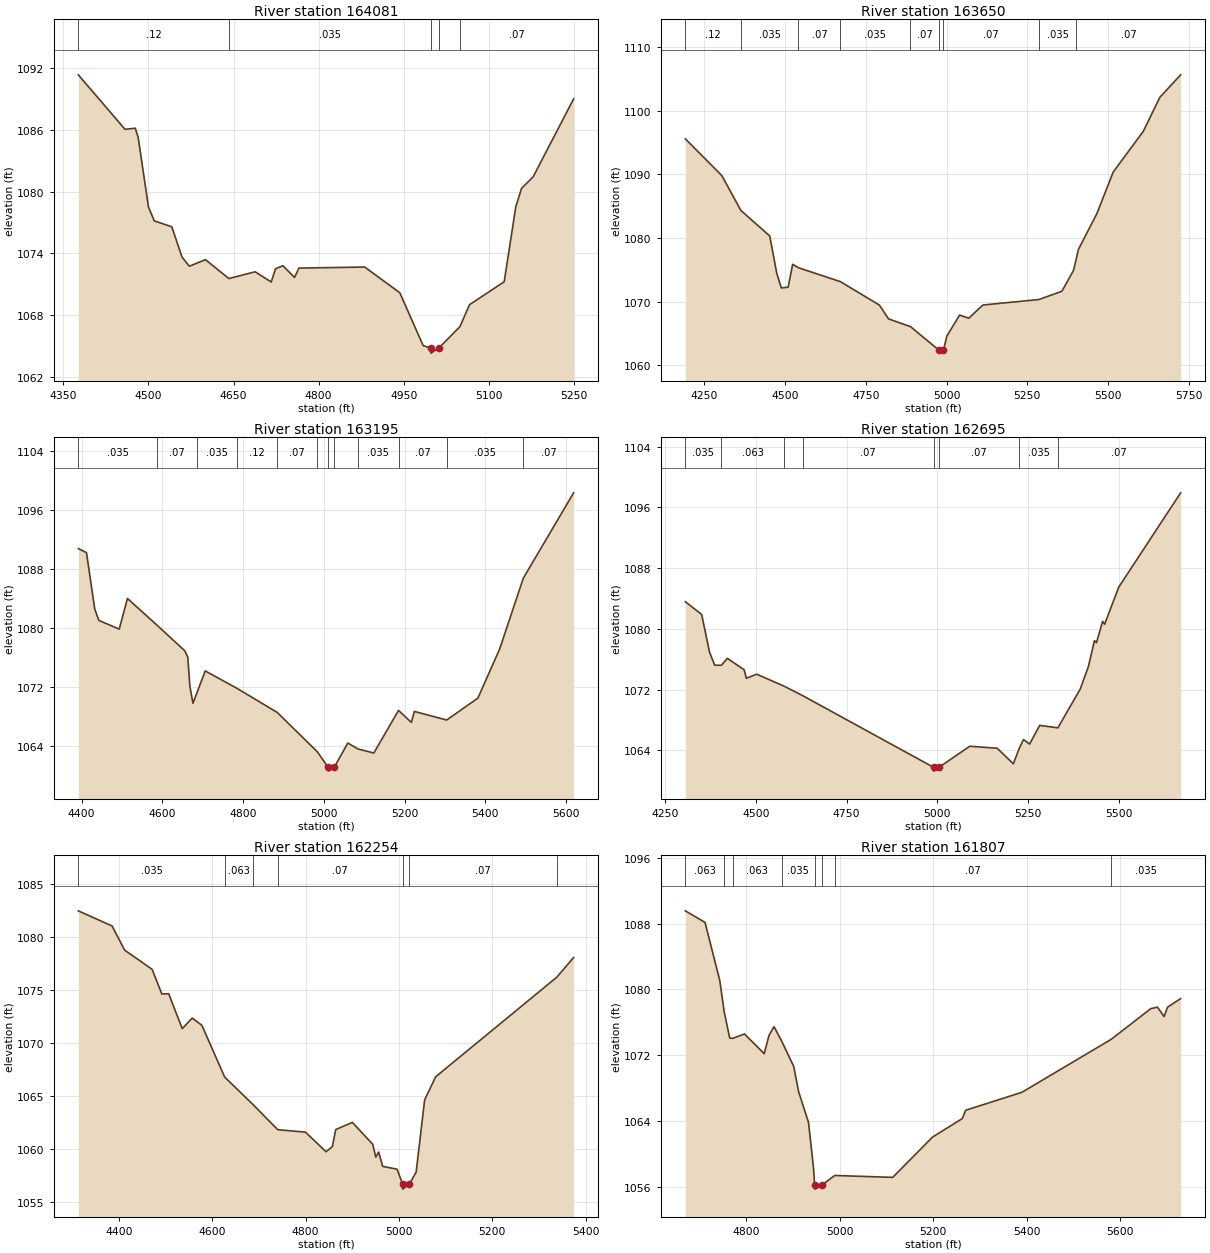
Type RM Length L Ch R = 1 ,164081  ,431,431,431
BEGIN DESCRIPTION:
Dry Comal Creek 213.0
END DESCRIPTION:
XS GIS Cut Line= 3
      2199725.01     13828974.96        2199875.       13828375.
        2199825.     13828124.98
#Sta/Elev= 30
  4376.3 1091.37  4458.7 1086.07  4476.8 1086.18  4481.9 1085.28    4500 1078.52
  4510.3 1077.17  4541.2 1076.59  4559.2 1073.65  4572.1 1072.76  4600.5  1073.4
  4641.8 1071.56  4688.1 1072.22  4716.4 1071.23  4724.1 1072.51    4737 1072.81
  4757.6 1071.67  4765.4 1072.58  4881.3 1072.68  4943.2 1070.18  4984.4 1065.04
  4997.6 1064.81  4998.1 1064.31  5012.2 1064.81  5049.3 1066.89  5066.1 1069.02
  5127.3 1071.25  5147.7 1078.53  5157.9 1080.33  5178.3 1081.45  5249.7 1089.03
#Mann= 5 ,-1 , 0
  4376.3     .12       0  4641.8    .035       0  4997.6    .035       0
  5012.2    .035       0  5049.3     .07       0
Bank Sta=4997.6,5012.2
XS Rating Curve= 0 ,0
Exp/Cntr=0.3,0.1

Type RM Length L Ch R = 1 ,163650  ,455,455,455
BEGIN DESCRIPTION:
Dry Comal Creek 212.0
END DESCRIPTION:
XS GIS Cut Line= 3
      2199725.02     13829074.98        2200275.       13828475.
      2200674.99     13827875.02
#Sta/Elev= 30
  4190.6 1095.61  4303.7 1089.82  4362.7 1084.34  4452.3 1080.31  4473.9 1074.45
  4488.1 1072.14  4509.1 1072.25  4523.2 1075.86  4541.3 1075.32  4671.2 1073.13
  4792.1 1069.44  4820.4 1067.27  4888.1 1066.06  4975.8 1062.38  4976.3 1061.88
  4990.6 1062.38  5001.1 1064.56  5040.6 1067.87  5069.1 1067.38  5112.7 1069.45
  5286.7 1070.32  5357.6 1071.62  5393.6  1074.9  5401.3 1076.52  5408.6 1078.18
  5465.7  1083.8  5516.8  1090.4  5609.9 1096.79    5661 1102.13  5725.6 1105.68
#Mann= 9 ,-1 , 0
  4190.6     .12       0  4362.7    .035       0  4541.3     .07       0
  4671.2    .035       0  4888.1     .07       0  4975.8     .05       0
  4990.6     .07       0  5286.7    .035       0  5401.3     .07       0
Bank Sta=4975.8,4990.6
XS Rating Curve= 0 ,0
Exp/Cntr=0.3,0.1

Type RM Length L Ch R = 1 ,163195  ,500,500,500
BEGIN DESCRIPTION:
Dry Comal Creek 211.0
END DESCRIPTION:
XS GIS Cut Line= 3
        2200575.     13829225.03        2200675.       13828625.
      2200825.01     13828024.97
#Sta/Elev= 30
  4391.7 1090.74    4412 1090.19  4432.3 1082.61  4442.4 1081.04  4493.1 1079.85
  4513.4    1084  4586.7 1080.38  4655.3 1076.93  4662.9 1076.07    4668 1072.14
  4675.6 1069.83  4685.9 1071.29    4706  1074.2  4785.2 1071.83  4884.5 1068.58
  4983.7 1063.27  5010.6 1061.15  5011.1 1060.65  5025.4 1061.15  5059.3 1064.45
  5084.2 1063.65  5123.7  1063.1  5184.8 1068.86  5216.5 1067.24  5224.2 1068.72
  5304.1 1067.56  5381.4 1070.52  5435.5 1077.19  5493.9 1086.74  5618.5 1098.28
#Mann= 12 ,-1 , 0
  4391.7    .035       0  4586.7     .07       0  4685.9    .035       0
  4785.2     .12       0  4884.5     .07       0  4983.7    .035       0
  5010.6    .035       0  5025.4    .035       0  5084.2    .035       0
  5184.8     .07       0  5304.1    .035       0  5493.9     .07       0
Bank Sta=5010.6,5025.4
XS Rating Curve= 0 ,0
Exp/Cntr=0.3,0.1

Type RM Length L Ch R = 1 ,162695  ,441,441,441
BEGIN DESCRIPTION:
Dry Comal Creek 210.0
END DESCRIPTION:
XS GIS Cut Line= 3
      2200825.01     13829224.99        2201175.       13828625.
      2200875.01     13828025.02
#Sta/Elev= 30
  4305.5 1083.57  4350.6 1081.88  4372.1 1076.94  4386.5  1075.2  4404.9  1075.2
  4421.3 1076.11  4467.6  1074.6  4473.8 1073.48  4502.3 1074.02  4577.8 1072.44
  4628.8  1071.2  4989.8 1061.75  4990.3 1061.25  5004.7 1061.75  5089.5 1064.53
    5165 1064.27  5209.7 1062.21  5225.4 1064.18  5237.7 1065.41  5254.5 1064.81
  5282.4 1067.28  5332.5 1066.95  5394.2 1072.07  5416.6 1075.03  5433.3 1078.44
  5438.9 1078.17  5455.7 1080.97  5461.3  1080.6  5500.4  1085.5  5670.9 1097.91
#Mann= 8 ,-1 , 0
  4305.5    .035       0  4404.9    .063       0  4577.8    .035       0
  4628.8     .07       0  4989.8     .05       0  5004.7     .07       0
  5225.4    .035       0  5332.5     .07       0
Bank Sta=4989.8,5004.7
XS Rating Curve= 0 ,0
Exp/Cntr=0.3,0.1

Type RM Length L Ch R = 1 ,162254  ,447,447,447
BEGIN DESCRIPTION:
Dry Comal Creek 209.0
END DESCRIPTION:
XS GIS Cut Line= 3
      2201975.02     13829125.03        2201575.       13828575.
        2201425.       13828225.
#Sta/Elev= 30
  4313.2 1082.47  4385.5 1081.04  4412.5 1078.76  4471.3 1076.95  4492.1 1074.62
  4506.8 1074.64  4535.8 1071.35  4557.1 1072.35  4577.9 1071.66  4626.7 1066.78
  4686.6 1064.22  4740.4 1061.81  4799.7 1061.58  4843.8 1059.73  4857.3 1060.21
  4864.6 1061.82  4900.2  1062.5  4943.9 1060.43  4950.4 1059.22  4956.6  1059.7
  4965.1 1058.35    4996 1058.08  5007.6  1056.7  5008.1  1056.2  5022.5  1056.7
  5036.8  1057.8    5055 1064.62  5078.5  1066.8  5337.9  1076.2  5374.1 1078.06
#Mann= 7 ,-1 , 0
  4313.2    .035       0  4626.7    .063       0  4686.6    .035       0
  4740.4     .07       0  5007.6     .05       0  5022.5     .07       0
  5337.9    .035       0
Bank Sta=5007.6,5022.5
XS Rating Curve= 0 ,0
Exp/Cntr=0.3,0.1

Type RM Length L Ch R = 1 ,161807  ,459,459,459
BEGIN DESCRIPTION:
Dry Comal Creek 208.0
END DESCRIPTION:
XS GIS Cut Line= 3
        2202075.     13828975.01        2201975.       13828675.
      2201475.03     13828125.03
#Sta/Elev= 30
  4669.6 1089.56  4711.8 1088.15  4743.4 1081.06  4752.7  1077.3  4764.5  1074.1
  4770.7 1074.05  4796.1 1074.59  4838.3  1072.2  4848.8 1074.45  4859.3 1075.47
  4875.4 1073.76  4901.5 1070.64    4912 1067.56  4933.1 1063.84  4943.7 1058.34
  4946.3 1056.23  4946.8 1055.73  4962.1 1056.23  4989.1 1057.39  5113.2 1057.16
  5198.4 1062.06  5261.9  1064.3  5269.3 1065.32  5389.6  1067.5  5580.3 1073.93
  5665.3 1077.67  5679.5 1077.85  5693.7 1076.71  5701.1 1077.85  5729.1 1078.89
#Mann= 8 ,-1 , 0
  4669.6    .063       0  4752.7    .035       0  4770.7    .063       0
  4875.4    .035       0  4946.3     .05       0  4962.1    .035       0
  4989.1     .07       0  5580.3    .035       0
Bank Sta=4946.3,4962.1
XS Rating Curve= 0 ,0
Exp/Cntr=0.3,0.1