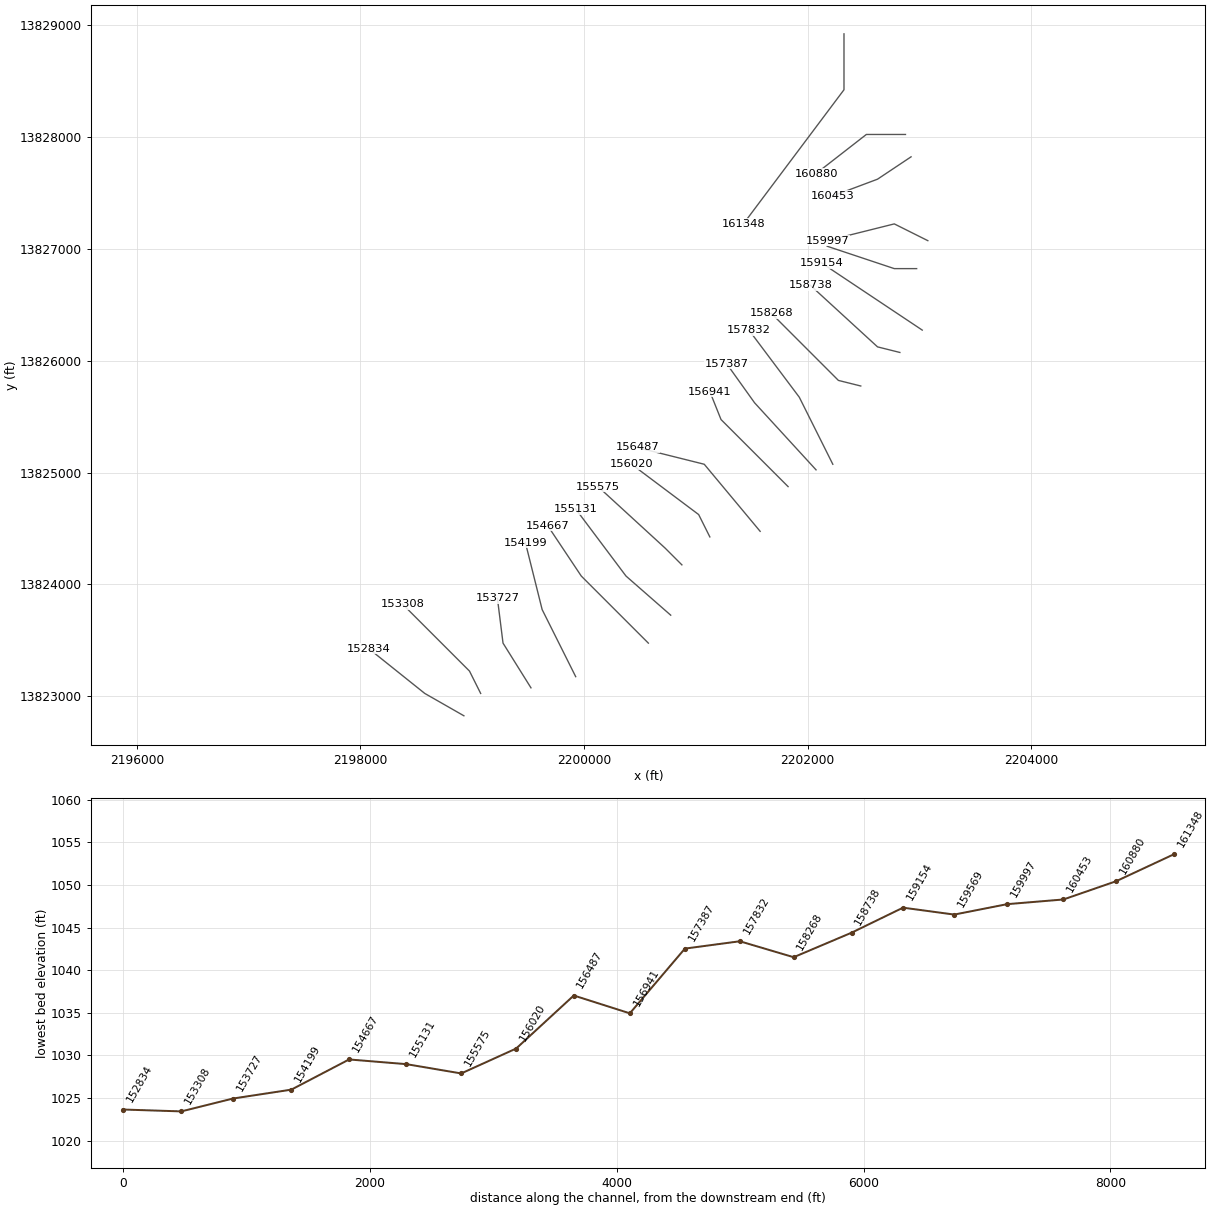
HEC-RAS study Dry Comal Creek.prj: Dry Comal Creek Base Level Engineering

--- Dry Comal Creek.g01 (geometry) --- (continued)

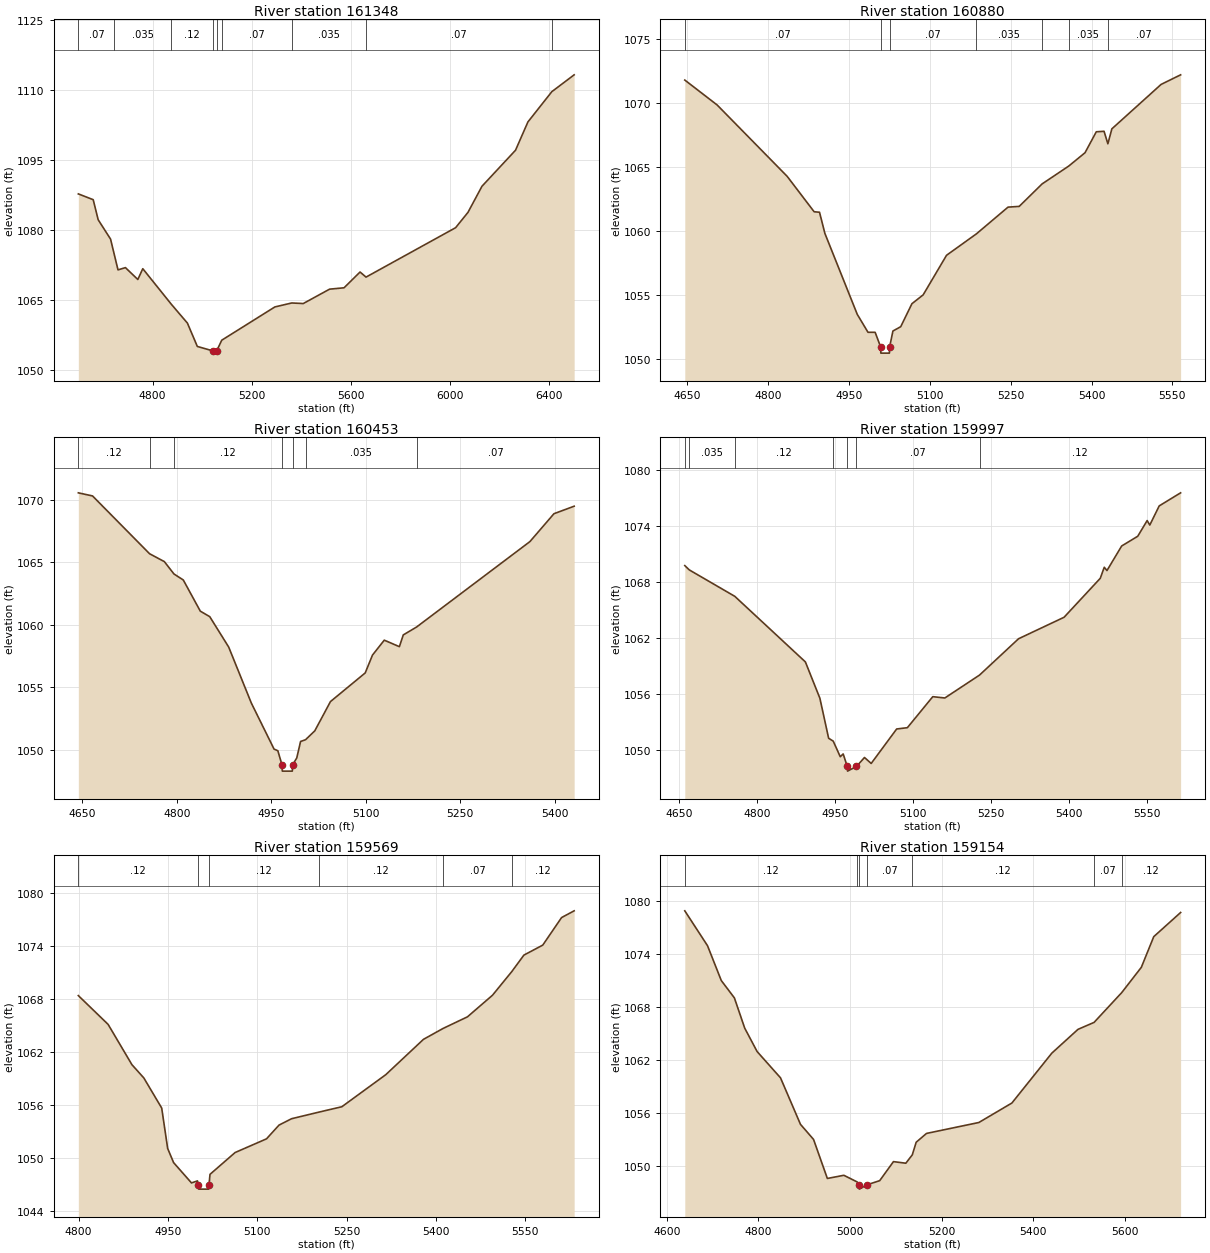
Type RM Length L Ch R = 1 ,161348  ,468,468,468
BEGIN DESCRIPTION:
Dry Comal Creek 207.0
END DESCRIPTION:
XS GIS Cut Line= 3
        2202325.     13828924.97        2202325.       13828425.
      2201424.98     13827224.97
#Sta/Elev= 30
  4500.4 1087.69  4560.4 1086.45  4580.4 1082.16  4630.4 1078.01  4645.7 1074.65
  4660.4 1071.42  4690.4  1071.9  4740.4 1069.36  4760.4 1071.67  4875.8 1064.04
  4940.4 1060.02  4980.4 1055.02    5042 1054.09  5042.5 1053.59  5058.8 1054.09
  5078.7 1056.35  5293.1 1063.48  5361.1 1064.33  5407.7 1064.21  5513.9 1067.29
  5572.2 1067.58  5636.8 1070.96  5660.9 1069.87  6022.2 1080.45  6072.2 1083.74
  6128.5 1089.32  6263.9 1097.04  6313.9  1103.1  6410.3 1109.58  6500.4 1113.19
#Mann= 9 ,-1 , 0
  4500.4     .07       0  4645.7    .035       0  4875.8     .12       0
    5042     .05       0  5058.8     .12       0  5078.7     .07       0
  5361.1    .035       0  5660.9     .07       0  6410.3     .12       0
Bank Sta=5042,5058.8
XS Rating Curve= 0 ,0
Exp/Cntr=0.3,0.1

Type RM Length L Ch R = 1 ,160880  ,427,427,427
BEGIN DESCRIPTION:
Dry Comal Creek 206.0
END DESCRIPTION:
XS GIS Cut Line= 3
      2202875.01       13828025.        2202525.       13828025.
        2202075.       13827675.
#Sta/Elev= 30
  4645.2 1071.81  4705.2 1069.86  4835.2 1064.27  4885.2  1061.5  4895.2 1061.46
  4905.2  1059.8  4965.2 1053.47  4985.2 1052.06  4998.4 1052.06  5008.5 1050.93
    5009 1050.43  5024.9 1050.43  5025.4 1050.93  5031.4 1052.16  5045.9  1052.5
  5066.7  1054.3  5087.5 1054.99  5130.9 1058.09  5186.4 1059.77    5245 1061.86
  5265.8 1061.92  5308.3 1063.68  5357.5 1065.07  5387.9 1066.12  5408.8 1067.76
  5423.2  1067.8  5430.3 1066.82  5437.7 1067.99  5529.1 1071.47  5565.3 1072.22
#Mann= 7 ,-1 , 0
  4645.2     .07       0  5008.5     .05       0  5025.4     .07       0
  5186.4    .035       0  5308.3     .07       0  5357.5    .035       0
  5430.3     .07       0
Bank Sta=5008.5,5025.4
XS Rating Curve= 0 ,0
Exp/Cntr=0.3,0.1

Type RM Length L Ch R = 1 ,160453  ,456,456,456
BEGIN DESCRIPTION:
Dry Comal Creek 205.0
END DESCRIPTION:
XS GIS Cut Line= 3
      2202925.02     13827825.01        2202625.       13827625.
      2202224.98     13827474.99
#Sta/Elev= 30
  4643.4 1070.54    4666 1070.29  4756.6 1065.67  4780.1 1065.04  4795.4 1064.05
  4810.2 1063.57  4837.2 1061.08  4852.2 1060.64  4882.3 1058.21  4918.3 1053.73
  4954.4 1050.05  4960.4 1049.92    4967 1048.79  4967.5 1048.29  4983.4 1048.29
  4983.9 1048.79  4990.5 1049.35  4996.5 1050.66  5004.4  1050.8  5019.1 1051.51
    5044 1053.85  5099.2 1056.14  5110.8 1057.57  5129.5 1058.76  5153.5 1058.24
  5159.7 1059.18  5180.8 1059.81  5360.9 1066.64  5399.1 1068.87  5431.2 1069.47
#Mann= 7 ,-1 , 0
  4643.4     .12       0  4756.6     .07       0  4795.4     .12       0
    4967     .05       0  4983.9     .12       0  5004.4    .035       0
  5180.8     .07       0
Bank Sta=4967,4983.9
XS Rating Curve= 0 ,0
Exp/Cntr=0.3,0.1

Type RM Length L Ch R = 1 ,159997  ,428,428,428
BEGIN DESCRIPTION:
Dry Comal Creek 204.0
END DESCRIPTION:
XS GIS Cut Line= 3
      2203075.01       13827075.        2202775.       13827225.
      2202174.98       13827075.
#Sta/Elev= 30
  4660.4 1069.74    4669 1069.28  4756.6 1066.45  4892.4 1059.43  4920.3 1055.54
  4937.1 1051.26    4946 1050.95  4959.5 1049.28  4965.1 1049.58    4973 1048.24
  4973.5 1047.74  4990.7 1048.24  5006.1  1049.2    5019 1048.56    5068 1052.25
  5088.6 1052.39  5137.5 1055.71  5160.7 1055.57  5227.4 1058.02  5302.5 1061.91
  5390.1 1064.21  5459.7 1068.38  5467.4 1069.56  5472.6 1069.21  5500.9 1071.84
  5531.8 1072.88  5549.9 1074.56    5555 1074.08  5573.1 1076.13  5614.3 1077.53
#Mann= 7 ,-1 , 0
  4660.4     .07       0    4669    .035       0  4756.6     .12       0
    4946     .07       0    4973     .05       0  4990.7     .07       0
  5227.4     .12       0
Bank Sta=4973,4990.7
XS Rating Curve= 0 ,0
Exp/Cntr=0.3,0.1

Type RM Length L Ch R = 1 ,159569  ,415,415,415
BEGIN DESCRIPTION:
Dry Comal Creek 203.0
END DESCRIPTION:
XS GIS Cut Line= 3
        2202975.       13826825.        2202775.       13826825.
      2202174.96     13827025.01
#Sta/Elev= 30
  4799.7 1068.37  4849.7 1065.12  4889.7 1060.57  4909.7 1059.07  4939.7 1055.67
  4949.7 1051.11  4959.7 1049.51  4989.7 1047.22  4999.7 1047.45  5001.3 1047.02
  5001.8 1046.52  5018.6 1046.52  5019.1 1047.02  5020.8 1048.19  5062.9 1050.65
  5115.7  1052.2  5136.7 1053.75  5157.8 1054.47    5204 1055.22  5242.1 1055.82
  5315.9 1059.44  5379.2 1063.43  5412.1 1064.66    5453 1065.97  5495.1 1068.41
  5527.6 1071.09  5547.8 1072.94  5579.5 1074.07  5611.1 1077.18  5632.2 1077.94
#Mann= 6 ,-1 , 0
  4799.7     .12       0  5001.3     .05       0  5019.1     .12       0
    5204     .12       0  5412.1     .07       0  5527.6     .12       0
Bank Sta=5001.3,5019.1
XS Rating Curve= 0 ,0
Exp/Cntr=0.3,0.1

Type RM Length L Ch R = 1 ,159154  ,416,416,416
BEGIN DESCRIPTION:
Dry Comal Creek 202.0
END DESCRIPTION:
XS GIS Cut Line= 3
      2203025.01       13826275.        2202725.       13826475.
      2202124.98     13826875.02
#Sta/Elev= 30
  4639.5 1078.91  4689.1 1074.95  4719.1    1071  4747.7 1069.03  4770.2  1065.6
  4797.3 1062.94  4848.3 1059.96  4891.9 1054.68  4920.4 1052.97  4950.5 1048.54
  4986.5  1048.9  5015.4 1048.15  5019.7 1047.83  5020.2 1047.33  5037.5 1047.83
  5064.7 1048.29  5094.7 1050.45  5121.7 1050.27  5135.8 1051.22  5144.3 1052.65
  5166.8 1053.65    5281 1054.89  5353.1  1057.1  5440.2 1062.76  5497.3 1065.46
  5532.4 1066.25  5592.7 1069.63  5635.5  1072.5  5662.6 1075.98  5721.2 1078.72
#Mann= 7 ,-1 , 0
  4639.5     .12       0  5015.4     .07       0  5019.7     .05       0
  5037.5     .07       0  5135.8     .12       0  5532.4     .07       0
  5592.7     .12       0
Bank Sta=5019.7,5037.5
XS Rating Curve= 0 ,0
Exp/Cntr=0.3,0.1

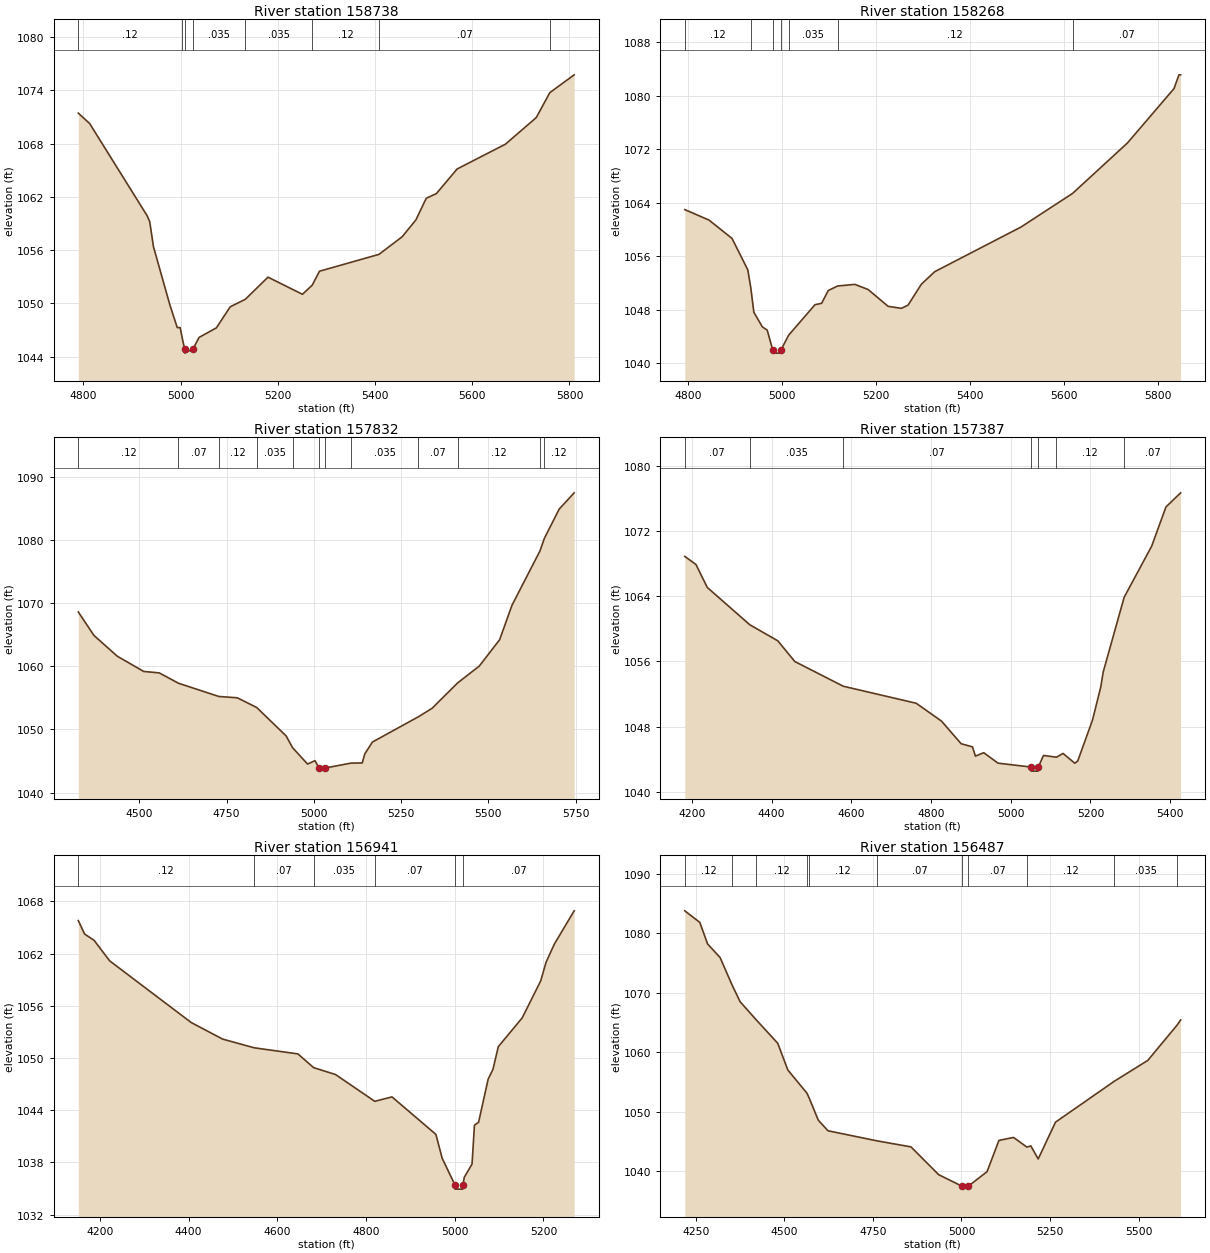
Type RM Length L Ch R = 1 ,158738  ,470,470,470
BEGIN DESCRIPTION:
Dry Comal Creek 201.0
END DESCRIPTION:
XS GIS Cut Line= 3
      2202824.97     13826075.01        2202625.       13826125.
      2202024.97     13826675.02
#Sta/Elev= 30
  4789.6 1071.44  4812.8 1070.28  4931.3 1059.87  4936.5 1059.21  4944.2 1056.39
  4977.7 1049.88  4993.1 1047.28  4999.1 1047.28  5003.6 1046.04  5008.1  1044.9
  5008.6  1044.4  5025.9  1044.9    5038 1046.17  5073.7 1047.25  5102.1 1049.62
  5133.3 1050.47  5179.8 1052.96  5250.7 1051.03  5270.8 1052.06  5285.8 1053.63
  5408.2 1055.53    5456 1057.52  5484.1 1059.41  5505.4 1061.85  5526.3 1062.38
  5568.9 1065.15  5668.2 1067.94  5731.7 1070.94  5759.6 1073.75  5809.7 1075.76
#Mann= 8 ,-1 , 0
  4789.6     .12       0  5003.6    .035       0  5008.1     .05       0
  5025.9    .035       0  5133.3    .035       0  5270.8     .12       0
  5408.2     .07       0  5759.6     .12       0
Bank Sta=5008.1,5025.9
XS Rating Curve= 0 ,0
Exp/Cntr=0.3,0.1

Type RM Length L Ch R = 1 ,158268  ,436,436,436
BEGIN DESCRIPTION:
Dry Comal Creek 200.0
END DESCRIPTION:
XS GIS Cut Line= 3
      2202475.05     13825774.99        2202275.       13825825.
      2201675.02     13826424.98
#Sta/Elev= 30
  4793.8 1062.96  4845.4 1061.39  4894.3 1058.65  4927.8 1053.96  4934.2 1051.28
  4940.7 1047.63  4958.8 1045.44  4969.1 1044.96  4980.7 1042.02  4981.2 1041.52
  4998.1 1041.52  4998.6 1042.02  5014.6 1044.19  5070.7 1048.75  5084.9 1048.96
    5099 1050.88  5119.1 1051.55  5155.6 1051.79  5183.8 1051.02  5226.3 1048.51
  5254.6 1048.21  5268.7 1048.69    5297 1051.81  5325.3 1053.68  5509.1 1060.36
  5618.7 1065.38  5735.4 1072.91  5834.4 1081.03    5845 1083.09  5848.5 1083.09
#Mann= 7 ,-1 , 0
  4793.8     .12       0  4934.2     .07       0  4980.7     .05       0
  4998.6     .07       0  5014.6    .035       0  5119.1     .12       0
  5618.7     .07       0
Bank Sta=4980.7,4998.6
XS Rating Curve= 0 ,0
Exp/Cntr=0.3,0.1

Type RM Length L Ch R = 1 ,157832  ,445,445,445
BEGIN DESCRIPTION:
Dry Comal Creek 199.0
END DESCRIPTION:
XS GIS Cut Line= 3
      2202225.02     13825074.97        2201925.       13825675.
      2201474.97     13826275.03
#Sta/Elev= 30
  4325.1 1068.63  4369.9 1064.91  4436.9 1061.61  4512.4  1059.2  4557.1 1058.97
  4612.1 1057.33  4727.8 1055.23  4780.7 1055.02  4836.1 1053.49  4920.5 1048.98
  4939.2  1047.1    4982 1044.51  5003.2 1045.05    5015 1043.89  5015.5 1043.39
  5033.2 1043.89  5106.4 1044.66  5138.7 1044.69    5146 1046.12  5167.8    1048
  5299.7 1052.01  5338.7 1053.35  5412.1 1057.38  5474.1 1060.05  5532.4 1064.23
  5567.8 1069.69  5647.9  1078.3  5660.6 1080.31  5703.2 1084.96    5746 1087.53
#Mann= 12 ,-1 , 0
  4325.1     .12       0  4612.1     .07       0  4727.8     .12       0
  4836.1    .035       0  4939.2     .07       0    5015     .05       0
  5033.2     .07       0  5106.4    .035       0  5299.7     .07       0
  5412.1     .12       0  5647.9     .07       0  5660.6     .12       0
Bank Sta=5015,5033.2
XS Rating Curve= 0 ,0
Exp/Cntr=0.3,0.1

Type RM Length L Ch R = 1 ,157387  ,446,446,446
BEGIN DESCRIPTION:
Dry Comal Creek 198.0
END DESCRIPTION:
XS GIS Cut Line= 3
      2202075.02     13825024.98        2201525.       13825625.
      2201274.99     13825975.02
#Sta/Elev= 30
  4182.1 1068.88  4210.2 1067.88  4238.5 1065.07  4345.2 1060.49  4415.5 1058.52
  4458.1 1055.98  4579.6 1052.95  4762.7 1050.86  4826.2 1048.67  4875.5 1045.89
  4903.9 1045.51  4911.3 1044.37  4932.2 1044.79    4968 1043.51  5050.9 1043.03
  5051.4 1042.53  5068.6 1042.53  5069.1 1043.03  5082.1 1044.45  5114.7 1044.24
  5131.2  1044.7  5160.7  1043.5  5168.1 1043.78    5205 1048.78  5225.9 1052.87
    5232  1054.7  5284.5 1063.86  5353.7 1070.15  5389.3 1074.94  5426.2 1076.68
#Mann= 7 ,-1 , 0
  4182.1     .07       0  4345.2    .035       0  4579.6     .07       0
  5050.9     .05       0  5069.1     .07       0  5114.7     .12       0
  5284.5     .07       0
Bank Sta=5050.9,5069.1
XS Rating Curve= 0 ,0
Exp/Cntr=0.3,0.1

Type RM Length L Ch R = 1 ,156941  ,454,454,454
BEGIN DESCRIPTION:
Dry Comal Creek 197.0
END DESCRIPTION:
XS GIS Cut Line= 3
      2201825.01     13824874.99        2201225.       13825475.
        2201125.     13825724.99
#Sta/Elev= 30
  4151.5  1065.8  4165.7 1064.25  4186.9 1063.54  4222.2 1061.17  4406.1 1054.08
  4476.8 1052.18    4548 1051.18  4646.5 1050.48    4682  1048.9  4731.3 1048.11
  4819.8 1045.03  4858.6 1045.54  4957.6 1041.23  4971.8 1038.48  5000.4 1035.44
  5000.9 1034.94  5018.1 1034.94  5018.6 1035.44  5021.6  1036.3  5039.1 1037.82
  5044.5 1042.28  5053.9 1042.63  5075.4 1047.58  5086.2 1048.69  5098.3 1051.31
  5152.2 1054.62  5193.9 1058.87    5206 1061.02  5224.9 1063.12  5269.3 1066.92
#Mann= 6 ,-1 , 0
  4151.5     .12       0    4548     .07       0    4682    .035       0
  4819.8     .07       0  5000.4     .05       0  5018.6     .07       0
Bank Sta=5000.4,5018.6
XS Rating Curve= 0 ,0
Exp/Cntr=0.3,0.1

Type RM Length L Ch R = 1 ,156487  ,467,467,467
BEGIN DESCRIPTION:
Dry Comal Creek 196.0
END DESCRIPTION:
XS GIS Cut Line= 3
      2201574.98     13824475.02        2201075.       13825075.
      2200474.97     13825225.01
#Sta/Elev= 30
    4219 1083.81  4261.3 1081.87  4283.4 1078.24  4318.6 1075.96  4352.8  1071.3
  4375.2 1068.53  4420.6 1065.49  4481.3 1061.55  4509.9 1057.05  4563.8 1053.16
  4570.4  1052.3  4595.8 1048.62  4623.2 1046.84  4761.1 1045.15  4857.5 1044.13
  4935.6 1039.46  5001.2 1037.53  5001.7 1037.03  5019.4 1037.53  5072.2 1039.97
  5105.7 1045.22  5146.9 1045.72  5184.4  1044.1  5195.8 1044.29  5216.5  1042.1
  5265.4 1048.29  5431.8 1055.18  5525.7 1058.66  5608.4 1064.59  5618.5 1065.46
#Mann= 11 ,-1 , 0
    4219     .12       0  4352.8     .07       0  4420.6     .12       0
  4563.8     .07       0  4570.4     .12       0  4761.1     .07       0
  5001.2     .05       0  5019.4     .07       0  5184.4     .12       0
  5431.8    .035       0  5608.4     .12       0
Bank Sta=5001.2,5019.4
XS Rating Curve= 0 ,0
Exp/Cntr=0.3,0.1

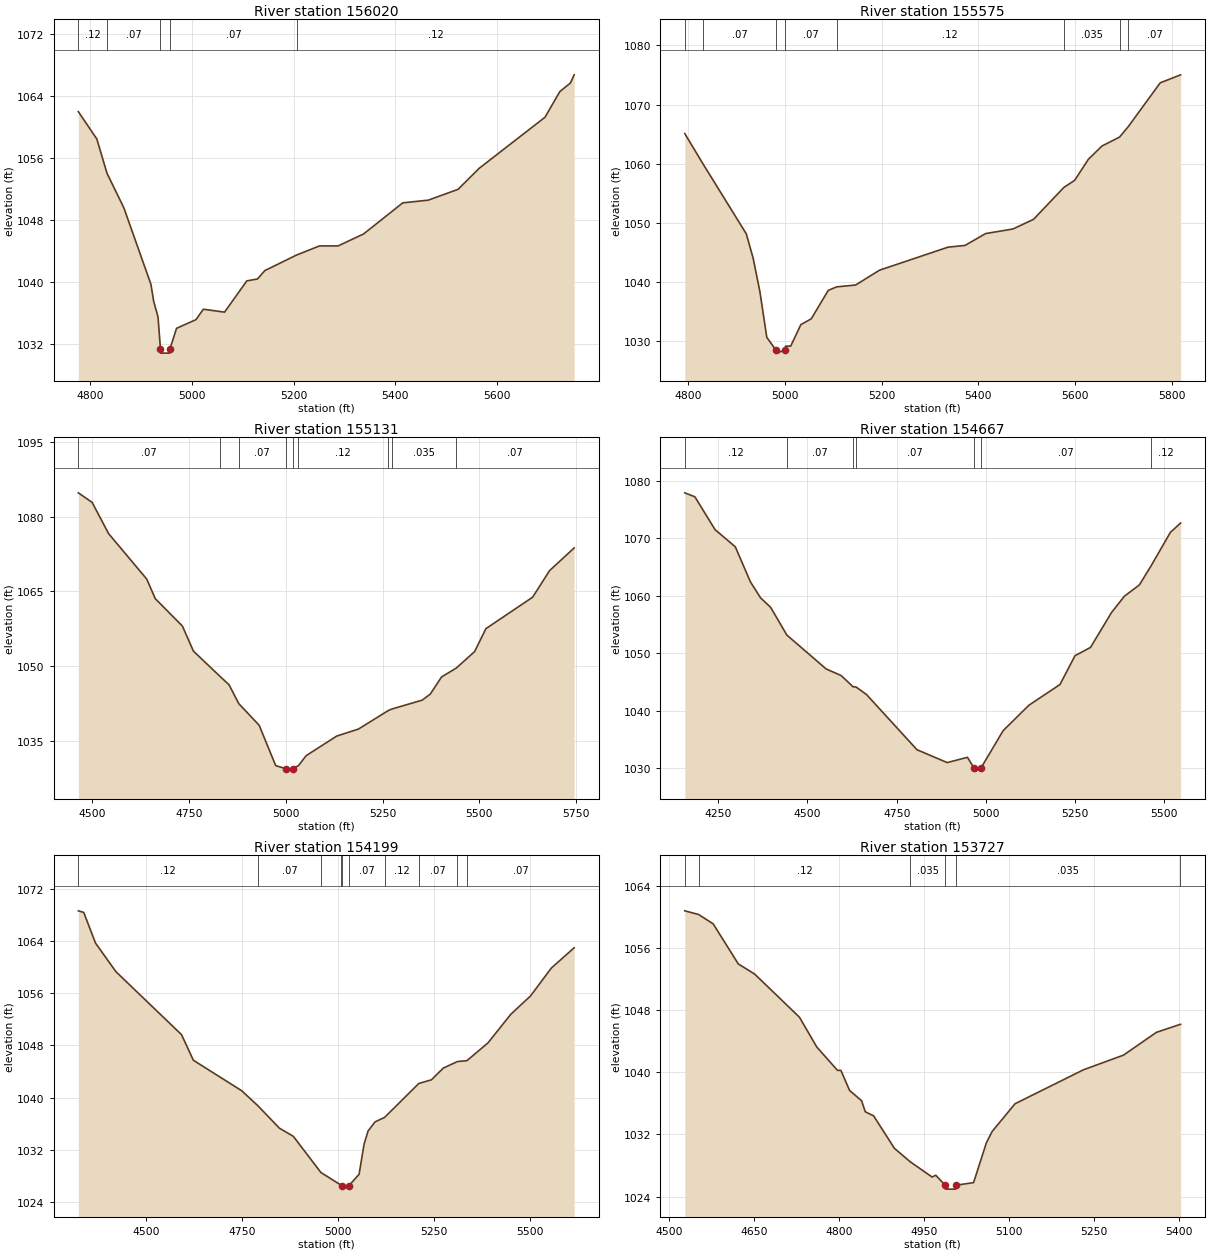
Type RM Length L Ch R = 1 ,156020  ,445,445,445
BEGIN DESCRIPTION:
Dry Comal Creek 195.0
END DESCRIPTION:
XS GIS Cut Line= 3
      2201124.99     13824425.02        2201025.       13824625.
      2200424.99     13825075.01
#Sta/Elev= 30
  4777.4 1061.99  4813.7 1058.46  4833.7 1054.03  4866.8 1049.57  4919.9 1039.71
  4925.5 1037.46  4933.9 1035.47  4938.7 1031.31  4939.2 1030.81  4956.6 1030.81
  4957.1 1031.31  4970.2 1034.01  5008.3 1035.13  5022.9 1036.48  5064.5  1036.1
  5108.3 1040.14  5129.1 1040.38  5143.7 1041.47  5206.5 1043.49    5251 1044.65
  5287.4 1044.65  5337.4 1046.19  5414.5 1050.21  5464.5 1050.56  5522.9 1051.95
  5564.5 1054.67  5693.7 1061.26  5722.9 1064.58  5743.7 1065.69    5751 1066.74
#Mann= 5 ,-1 , 0
  4777.4     .12       0  4833.7     .07       0  4938.7     .05       0
  4957.1     .07       0  5206.5     .12       0
Bank Sta=4938.7,4957.1
XS Rating Curve= 0 ,0
Exp/Cntr=0.3,0.1

Type RM Length L Ch R = 1 ,155575  ,444,444,444
BEGIN DESCRIPTION:
Dry Comal Creek 194.0
END DESCRIPTION:
XS GIS Cut Line= 3
      2200874.98     13824175.02        2200725.       13824325.
      2200124.96     13824875.03
#Sta/Elev= 30
  4792.7 1065.08  4829.7 1060.04    4920 1048.09  4934.1 1043.99  4948.2 1038.27
  4962.4 1030.56  4981.5 1028.39    4982 1027.89  4999.9 1028.39  5001.3 1029.08
  5011.9 1029.08  5032.9 1032.72  5054.4  1033.7  5089.6 1038.52  5106.9 1039.11
  5146.3 1039.43  5195.7 1041.94  5337.5 1045.84  5372.6 1046.13  5415.2 1048.14
  5471.9 1048.92  5514.4 1050.55  5577.1 1055.95  5599.5 1057.16  5627.9 1060.72
    5656 1062.97  5692.5 1064.49  5710.9  1066.3  5776.5 1073.67  5818.8 1075.03
#Mann= 8 ,-1 , 0
  4792.7     .12       0  4829.7     .07       0  4981.5     .05       0
  4999.9     .07       0  5106.9     .12       0  5577.1    .035       0
  5692.5     .12       0  5710.9     .07       0
Bank Sta=4981.5,4999.9
XS Rating Curve= 0 ,0
Exp/Cntr=0.3,0.1

Type RM Length L Ch R = 1 ,155131  ,464,464,464
BEGIN DESCRIPTION:
Dry Comal Creek 193.0
END DESCRIPTION:
XS GIS Cut Line= 3
      2200774.98     13823725.02        2200375.       13824075.
      2199924.99     13824675.02
#Sta/Elev= 30
  4463.8 1084.77  4499.4 1082.86  4542.1 1076.59  4640.8 1067.46  4662.6 1063.56
  4732.8 1058.06  4761.3 1053.04  4829.5 1048.01  4853.4 1046.29  4878.4 1042.52
  4931.2 1038.17  4973.9 1030.09  4999.6 1029.48  5000.1 1028.98  5018.1 1029.48
  5032.7 1030.07  5052.6 1032.08  5131.7 1036.01    5188 1037.42  5264.2 1041.09
  5273.3 1041.41  5352.6 1043.21  5373.4 1044.42  5402.6 1047.86  5440.5 1049.63
    5488 1052.94  5517.2 1057.54    5638 1063.85  5681.7 1069.17  5745.3 1073.72
#Mann= 9 ,-1 , 0
  4463.8     .07       0  4829.5     .12       0  4878.4     .07       0
  4999.6     .05       0  5018.1     .07       0  5032.7     .12       0
  5264.2     .07       0  5273.3    .035       0  5440.5     .07       0
Bank Sta=4999.6,5018.1
XS Rating Curve= 0 ,0
Exp/Cntr=0.3,0.1

Type RM Length L Ch R = 1 ,154667  ,468,468,468
BEGIN DESCRIPTION:
Dry Comal Creek 192.0
END DESCRIPTION:
XS GIS Cut Line= 3
      2200575.03     13823474.97        2199975.       13824075.
        2199675.       13824525.
#Sta/Elev= 30
  4156.2 1077.86  4184.5 1077.17  4241.1 1071.46  4297.7 1068.49  4340.1  1062.4
  4368.4 1059.63  4396.7 1057.98  4442.2 1053.16  4552.2 1047.28  4594.6 1046.12
  4627.7 1044.18    4636 1044.15  4665.4 1042.83  4806.8 1033.25  4891.6 1031.01
  4948.2 1031.93  4967.2 1030.03  4967.7 1029.53  4985.7 1030.03  5048.3 1036.56
  5120.4 1040.97  5207.6 1044.58  5249.6 1049.57  5293.2 1051.02  5351.8 1057.06
  5387.9  1059.9  5429.9 1061.86  5462.3 1065.12  5517.1 1071.01  5545.6 1072.61
#Mann= 7 ,-1 , 0
  4156.2     .12       0  4442.2     .07       0  4627.7     .12       0
    4636     .07       0  4967.2     .05       0  4985.7     .07       0
  5462.3     .12       0
Bank Sta=4967.2,4985.7
XS Rating Curve= 0 ,0
Exp/Cntr=0.3,0.1

Type RM Length L Ch R = 1 ,154199  ,472,472,472
BEGIN DESCRIPTION:
Dry Comal Creek 191.0
END DESCRIPTION:
XS GIS Cut Line= 3
      2199924.99     13823175.02        2199625.       13823775.
      2199474.99     13824375.03
#Sta/Elev= 30
  4324.8 1068.61  4338.8 1068.37  4369.5 1063.67  4422.6 1059.29  4593.1 1049.65
  4623.9 1045.73  4749.6 1041.06  4792.9 1038.69  4847.5 1035.33  4883.8 1034.08
  4955.7 1028.53  5008.7 1026.57  5009.5 1026.49    5010 1025.99    5028 1026.49
  5054.9 1028.27  5067.8 1032.87  5078.1 1034.88  5096.1 1036.28  5121.1 1036.97
  5210.1 1042.17    5243 1042.73  5273.9 1044.53  5310.7 1045.53  5335.1 1045.66
  5389.9 1048.38  5449.1 1052.75  5500.7 1055.58  5554.8 1059.85  5614.1 1062.95
#Mann= 10 ,-1 , 0
  4324.8     .12       0  4792.9     .07       0  4955.7    .035       0
  5008.7     .07       0  5009.5    .035       0    5028     .07       0
  5121.1     .12       0  5210.1     .07       0  5310.7     .12       0
  5335.1     .07       0
Bank Sta=5009.5,5028
XS Rating Curve= 0 ,0
Exp/Cntr=0.3,0.1

Type RM Length L Ch R = 1 ,153727  ,419,419,419
BEGIN DESCRIPTION:
Dry Comal Creek 190.0
END DESCRIPTION:
XS GIS Cut Line= 3
      2199525.01     13823074.98        2199275.       13823475.
        2199225.     13823874.97
#Sta/Elev= 30
    4528 1060.81  4552.3 1060.34  4578.1 1059.13  4622.4 1053.97  4651.3 1052.66
  4730.3  1047.1  4760.9 1043.26  4797.5 1040.25  4803.4 1040.25  4818.7 1037.67
  4839.9 1036.34  4846.4 1034.92  4861.2 1034.39  4897.7 1030.22    4926 1028.46
  4964.3 1026.51  4970.8 1026.74  4987.5 1025.45    4988 1024.95  5005.6 1024.95
  5006.1 1025.45  5037.5 1025.79  5060.2 1030.94  5070.3 1032.38  5110.6 1035.95
  5231.5 1040.33  5302.1 1042.22    5360 1045.15    5402 1046.18  5402.8 1046.18
#Mann= 6 ,-1 , 0
    4528     .07       0  4552.3     .12       0    4926    .035       0
  4987.5     .05       0  5006.1    .035       0    5402     .07       0
Bank Sta=4987.5,5006.1
XS Rating Curve= 0 ,0
Exp/Cntr=0.3,0.1

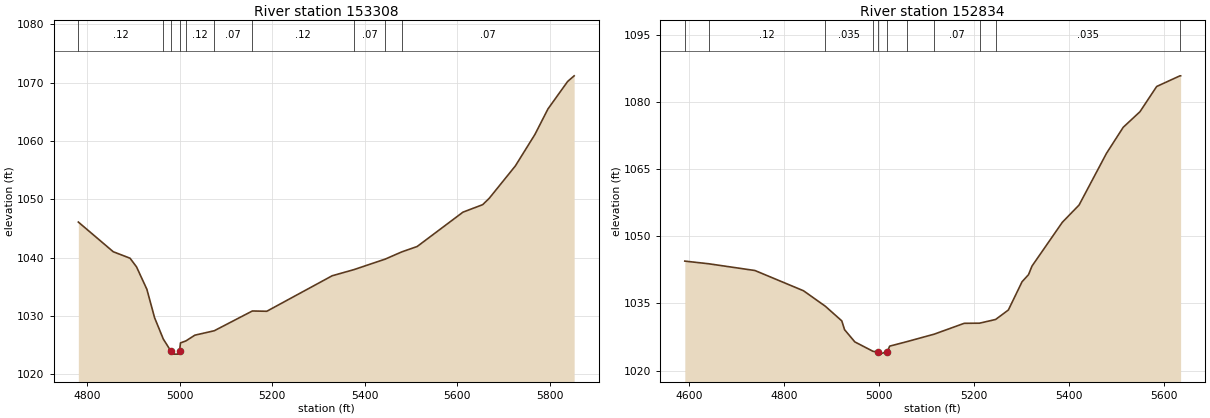
Type RM Length L Ch R = 1 ,153308  ,474,474,474
BEGIN DESCRIPTION:
Dry Comal Creek 189.0
END DESCRIPTION:
XS GIS Cut Line= 3
      2199075.01     13823024.99        2198975.       13823225.
      2198375.03     13823824.97
#Sta/Elev= 30
  4780.7 1046.09  4856.2    1041  4892.5 1039.89  4906.5 1038.41  4928.9 1034.56
  4945.6 1029.68  4964.4 1026.03    4981 1023.94  4981.5 1023.44  4999.1 1023.44
  4999.6 1023.94  5001.5 1025.36  5013.4 1025.71  5032.6 1026.69  5074.6 1027.45
    5157 1030.84  5188.2 1030.79  5329.6 1036.88  5376.5 1037.93  5444.4 1039.74
  5479.9 1040.97  5513.4  1041.9  5612.4 1047.79  5654.9 1049.07    5669 1050.15
  5725.6 1055.71    5768 1061.12  5796.3 1065.51  5838.7  1070.2  5852.8 1071.17
#Mann= 10 ,-1 , 0
  4780.7     .12       0  4964.4     .07       0    4981     .05       0
  4999.6     .07       0  5013.4     .12       0  5074.6     .07       0
    5157     .12       0  5376.5     .07       0  5444.4     .12       0
  5479.9     .07       0
Bank Sta=4981,4999.6
XS Rating Curve= 0 ,0
Exp/Cntr=0.3,0.1

Type RM Length L Ch R = 1 ,152834  ,412,412,412
BEGIN DESCRIPTION:
Dry Comal Creek 188.0
END DESCRIPTION:
XS GIS Cut Line= 3
      2198925.02     13822824.99        2198575.       13823025.
      2198075.04     13823424.97
#Sta/Elev= 30
  4591.5 1044.43  4641.5 1043.84  4739.1 1042.33  4841.3 1037.81  4887.3 1034.35
  4921.9 1031.08  4927.7 1029.12  4949.3 1026.39  4987.9 1024.27  4998.9 1024.16
  4999.4 1023.66  5017.6 1024.16  5022.6 1025.44    5060 1026.48  5116.4 1028.12
  5179.5 1030.54  5211.8 1030.57  5245.6  1031.4  5272.4 1033.51  5301.2 1039.82
  5314.8  1041.4    5322  1043.3    5386  1053.1  5421.2 1056.95  5478.9  1068.5
  5514.1 1074.31  5549.3 1077.78  5584.5 1083.42  5633.5  1085.8  5634.9  1085.8
#Mann= 11 ,-1 , 0
  4591.5     .07       0  4641.5     .12       0  4887.3    .035       0
  4987.9     .07       0  4998.9     .05       0  5017.6     .07       0
    5060    .035       0  5116.4     .07       0  5211.8     .12       0
  5245.6    .035       0  5633.5     .07       0
Bank Sta=4998.9,5017.6
XS Rating Curve= 0 ,0
Exp/Cntr=0.3,0.1