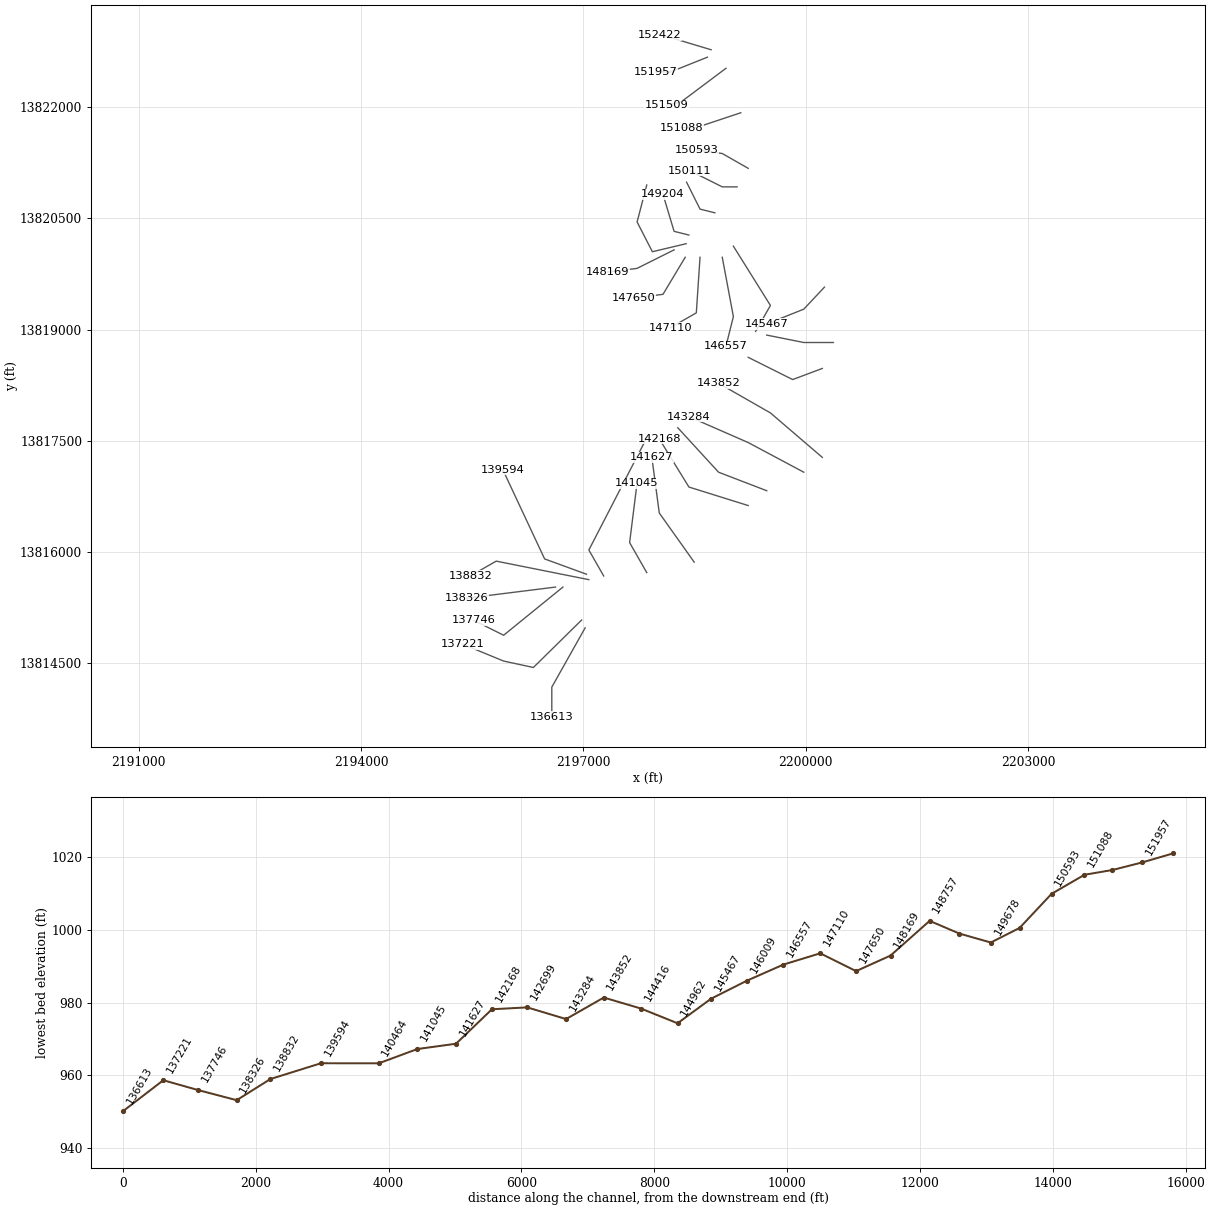
HEC-RAS study Dry Comal Creek.prj: Dry Comal Creek Base Level Engineering

--- Dry Comal Creek.g01 (geometry) --- (continued)

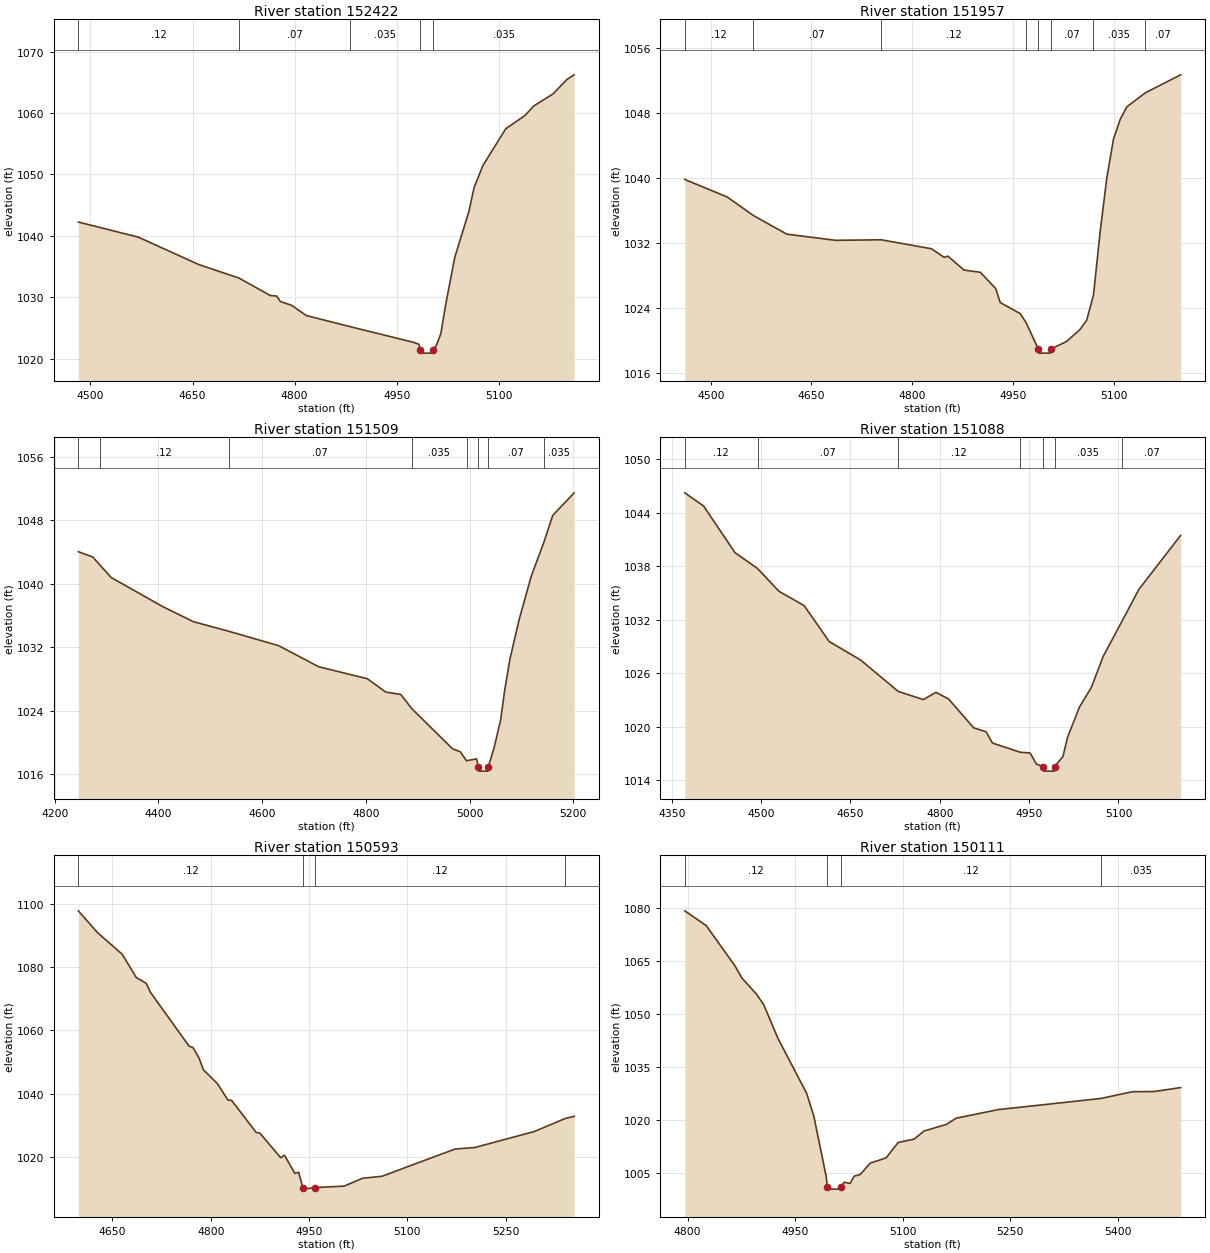
Type RM Length L Ch R = 1 ,152422  ,465,465,465
BEGIN DESCRIPTION:
Dry Comal Creek 187.0
END DESCRIPTION:
XS GIS Cut Line= 3
      2198724.99       13822775.        2198225.       13822925.
      2198024.96     13822975.01
#Sta/Elev= 30
  4482.3 1042.25  4570.2  1039.8  4659.8  1035.3    4718 1033.14  4764.2 1030.29
  4773.7 1030.19    4779 1029.31  4795.5 1028.69  4817.2 1027.02  4881.8  1025.2
    4973 1022.71  4982.6 1022.35  4984.5  1021.4    4985  1020.9  5002.7  1020.9
  5003.2  1021.4  5004.3 1021.84  5006.9 1021.84  5014.6 1024.03  5022.3  1029.1
  5035.2 1036.51  5055.8 1043.92  5063.6  1047.9  5076.5 1051.46    5110 1057.44
  5138.3 1059.61  5151.2 1061.16  5179.5 1063.12  5200.2 1065.51  5210.5 1066.23
#Mann= 5 ,-1 , 0
  4482.3     .12       0    4718     .07       0  4881.8    .035       0
  4984.5    .035       0  5003.2    .035       0
Bank Sta=4984.5,5003.2
XS Rating Curve= 0 ,0
Exp/Cntr=0.3,0.1

Type RM Length L Ch R = 1 ,151957  ,448,448,448
BEGIN DESCRIPTION:
Dry Comal Creek 186.0
END DESCRIPTION:
XS GIS Cut Line= 3
      2198675.01       13822675.        2198175.       13822475.
      2197975.02       13822475.
#Sta/Elev= 30
  4461.4 1039.85  4524.7 1037.68  4563.5  1035.4  4613.5  1033.1  4686.2 1032.34
  4753.8 1032.41  4828.9  1031.3  4847.8 1030.24  4853.2 1030.39  4877.4 1028.67
  4901.6  1028.4  4924.5 1026.39  4931.3 1024.66  4960.9 1023.31  4969.8 1022.19
  4987.9 1018.93  4988.4 1018.43  5006.1 1018.43  5006.6 1018.93  5029.9 1019.86
  5049.9 1021.33  5059.9 1022.47  5070.1 1025.57  5079.9  1033.3  5089.9 1039.99
  5099.9 1044.82  5109.9 1047.26  5119.9 1048.81  5147.3 1050.53  5199.9 1052.75
#Mann= 8 ,-1 , 0
  4461.4     .12       0  4563.5     .07       0  4753.8     .12       0
  4969.8     .07       0  4987.9     .05       0  5006.6     .07       0
  5070.1    .035       0  5147.3     .07       0
Bank Sta=4987.9,5006.6
XS Rating Curve= 0 ,0
Exp/Cntr=0.3,0.1

Type RM Length L Ch R = 1 ,151509  ,421,421,421
BEGIN DESCRIPTION:
Dry Comal Creek 185.0
END DESCRIPTION:
XS GIS Cut Line= 3
        2198925.       13822525.        2198325.       13822075.
      2198124.96     13822024.99
#Sta/Elev= 30
  4245.4 1044.06  4273.5 1043.38  4286.5 1042.41  4308.9 1040.79  4408.9  1037.1
  4467.3 1035.22    4535 1034.02  4631.9 1032.19  4708.9 1029.53  4802.7 1028.02
  4838.1 1026.34  4867.3 1026.03  4888.6 1024.23  4967.3 1019.16  4981.9  1018.8
    4994 1017.66  5013.4  1017.9    5017 1016.85  5017.5 1016.35  5035.2 1016.35
  5035.7 1016.85  5046.9 1019.22  5059.8 1022.79  5067.6 1026.56  5077.9 1030.55
  5095.9 1035.59  5119.1 1041.01  5142.9 1045.19  5160.3 1048.64  5201.6 1051.49
#Mann= 8 ,-1 , 0
  4245.4    .035       0  4286.5     .12       0    4535     .07       0
  4888.6    .035       0    4994     .07       0    5017     .05       0
  5035.7     .07       0  5142.9    .035       0
Bank Sta=5017,5035.7
XS Rating Curve= 0 ,0
Exp/Cntr=0.3,0.1

Type RM Length L Ch R = 1 ,151088  ,495,495,495
BEGIN DESCRIPTION:
Dry Comal Creek 184.0
END DESCRIPTION:
XS GIS Cut Line= 3
      2199124.98     13821924.99        2198525.       13821725.
      2198325.03       13821725.
#Sta/Elev= 30
  4371.9 1046.24  4403.5 1044.76  4456.2 1039.53    4494 1037.76    4530  1035.2
  4572.2  1033.6  4614.3 1029.57    4667  1027.5  4730.2 1023.98  4772.4 1023.06
  4793.5 1023.87  4814.6 1023.14  4856.8  1019.9  4877.8 1019.45  4888.4 1018.19
  4934.9 1017.16  4951.6 1017.07  4962.2 1015.83  4973.9 1015.54  4974.4 1015.04
  4992.1 1015.04  4992.6 1015.54  5006.8 1016.68  5014.3  1018.8  5034.3  1022.2
  5054.3 1024.41  5074.3  1027.9  5106.4 1031.91  5134.3 1035.42  5204.3 1041.47
#Mann= 7 ,-1 , 0
  4371.9     .12       0    4494     .07       0  4730.2     .12       0
  4934.9    .035       0  4973.9    .035       0  4992.6    .035       0
  5106.4     .07       0
Bank Sta=4973.9,4992.6
XS Rating Curve= 0 ,0
Exp/Cntr=0.3,0.1

Type RM Length L Ch R = 1 ,150593  ,482,482,482
BEGIN DESCRIPTION:
Dry Comal Creek 183.0
END DESCRIPTION:
XS GIS Cut Line= 3
      2199224.97     13821175.01        2198875.       13821375.
      2198525.04     13821424.99
#Sta/Elev= 30
  4597.9 1097.72  4627.4 1090.78  4664.8 1084.02  4686.4 1076.65  4701.5 1074.83
    4708 1071.97    4767 1054.96  4772.8 1054.53  4782.2  1051.2  4788.6 1047.55
  4810.2 1043.14  4826.1 1037.98  4831.8 1037.85  4869.3 1027.72    4875  1027.5
  4906.7 1019.74  4912.4 1020.53  4928.3 1014.79    4934 1015.16  4940.5 1010.32
    4941 1009.82  4959.3 1010.32  5003.5 1010.77  5031.3 1013.23  5061.6  1013.9
  5172.7 1022.48    5203 1022.97  5293.9 1028.03  5340.8 1032.12  5354.5 1032.81
#Mann= 4 ,-1 , 0
  4597.9     .12       0  4940.5    .035       0  4959.3     .12       0
  5340.8     .07       0
Bank Sta=4940.5,4959.3
XS Rating Curve= 0 ,0
Exp/Cntr=0.3,0.1

Type RM Length L Ch R = 1 ,150111  ,433,433,433
BEGIN DESCRIPTION:
Dry Comal Creek 182.0
END DESCRIPTION:
XS GIS Cut Line= 4
      2199074.96       13820925.        2198875.       13820925.
        2198675.       13821025.      2198434.91     13821145.05
#Sta/Elev= 30
  4796.1 1079.14  4826.1 1074.95  4866.1 1063.58  4876.1 1060.07  4896.1  1055.6
  4906.1 1052.66  4926.1 1043.09  4966.1 1027.58  4976.1 1021.17  4993.6 1003.89
    4995 1000.96  4995.5 1000.46  5013.3 1000.46  5013.8 1000.96  5018.4 1002.42
  5026.8 1002.06  5032.4 1004.12  5040.8 1004.57  5054.8  1007.8  5077.1  1009.3
  5093.9 1013.65  5116.2 1014.61  5130.2  1016.9    5161 1018.75  5174.9 1020.52
  5233.6 1022.94  5376.8 1026.09  5420.9    1028  5451.7 1028.06  5488.1 1029.17
#Mann= 4 ,-1 , 0
  4796.1     .12       0    4995     .05       0  5013.8     .12       0
  5376.8    .035       0
Bank Sta=4995,5013.8
XS Rating Curve= 0 ,0
Exp/Cntr=0.3,0.1

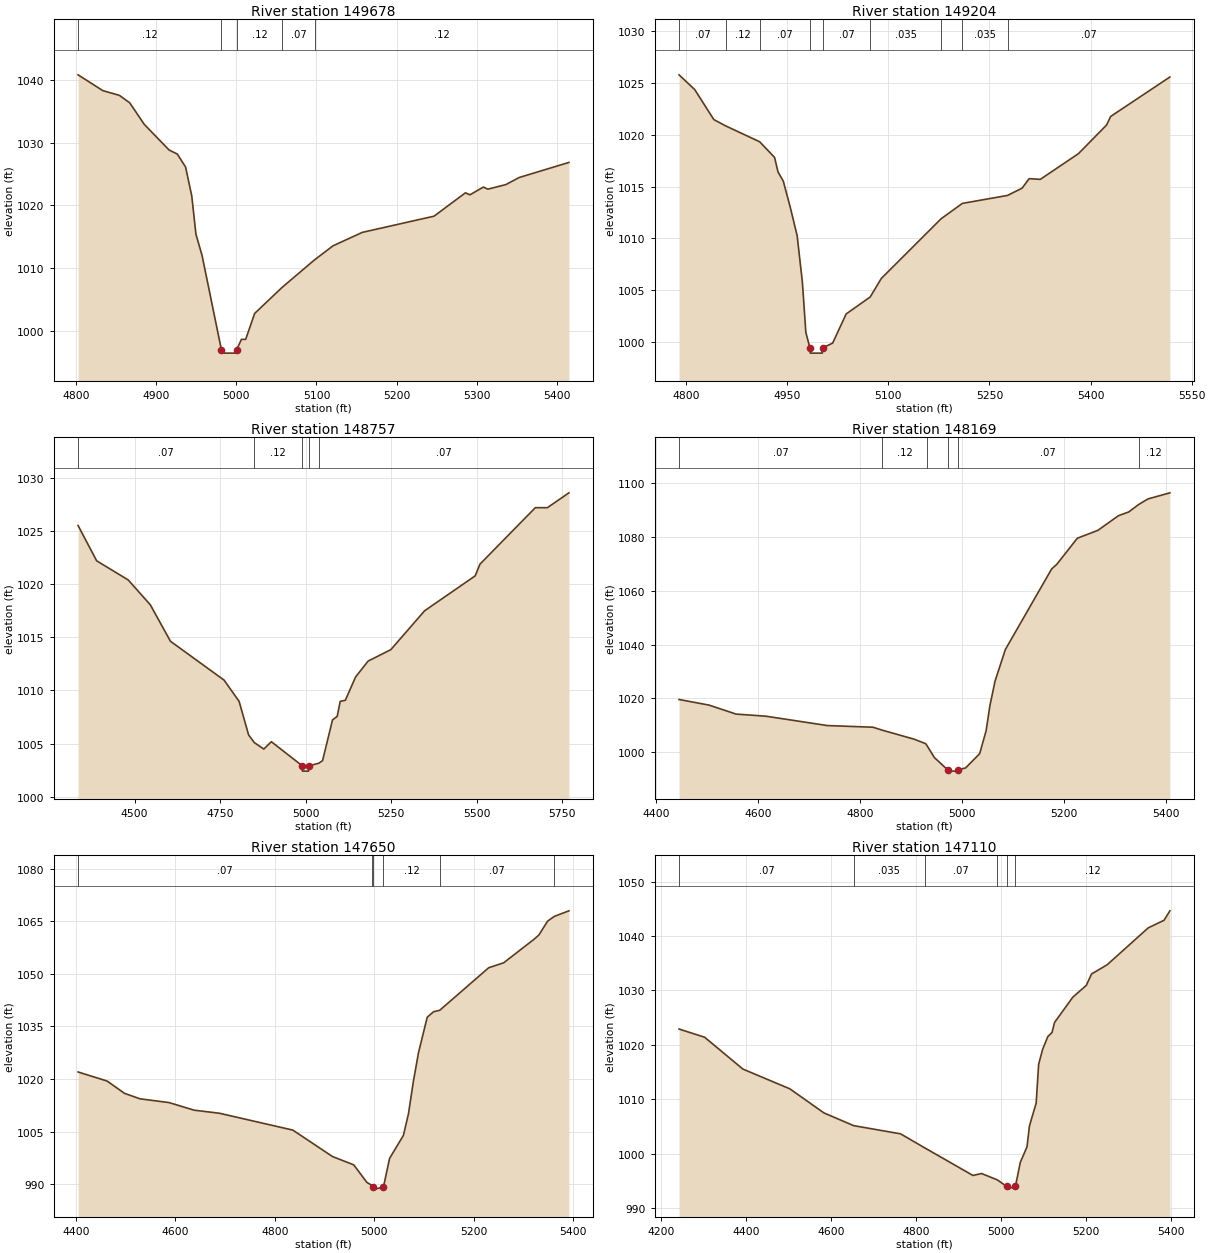
Type RM Length L Ch R = 1 ,149678  ,474,474,474
BEGIN DESCRIPTION:
Dry Comal Creek 181.0
END DESCRIPTION:
XS GIS Cut Line= 4
      2198774.98       13820575.        2198575.       13820625.
        2198475.       13820825.      2198393.58     13820987.84
#Sta/Elev= 30
  4802.9 1040.78  4833.8 1038.26  4854.4 1037.51  4867.3 1036.32  4885.3 1032.91
  4916.3 1028.81  4926.6 1028.16  4936.9  1026.1  4944.6 1021.48  4949.8 1015.41
  4957.5 1011.98  4981.6  996.96  4982.1  996.46  4999.9  996.46  5000.4  996.96
  5006.5  998.65  5011.8  998.65    5023 1002.78  5057.4 1006.95  5097.9 1011.34
  5120.8 1013.56  5157.2 1015.69  5246.6 1018.27  5285.7 1021.99  5291.3 1021.67
  5308.1 1022.91  5313.7 1022.57  5336.1  1023.3  5352.8 1024.43  5414.7 1026.83
#Mann= 5 ,-1 , 0
  4802.9     .12       0  4981.6     .05       0  5000.4     .12       0
  5057.4     .07       0  5097.9     .12       0
Bank Sta=4981.6,5000.4
XS Rating Curve= 0 ,0
Exp/Cntr=0.3,0.1

Type RM Length L Ch R = 1 ,149204  ,447,447,447
BEGIN DESCRIPTION:
Dry Comal Creek 180.0
END DESCRIPTION:
XS GIS Cut Line= 3
      2198425.01       13820275.        2198225.       13820325.
        2198075.     13820825.01
#Sta/Elev= 30
  4789.5 1025.78  4812.7 1024.36  4841.1 1021.46  4858.7 1020.85  4909.1 1019.32
  4931.2 1017.81  4936.4 1016.39  4944.1 1015.53  4954.4 1013.02  4964.7 1010.26
  4972.5 1005.75  4977.6 1000.92  4983.7  999.42  4984.2  998.92    5002  998.92
  5002.5  999.42  5017.4  999.89  5037.4  1002.7  5073.1 1004.34  5089.6 1006.13
  5178.3 1011.89  5209.8 1013.37  5276.8 1014.14  5298.4 1014.84  5308.9 1015.76
  5325.4 1015.69    5382 1018.17  5423.7 1020.93  5429.8 1021.76  5517.7 1025.57
#Mann= 9 ,-1 , 0
  4789.5     .07       0  4858.7     .12       0  4909.1     .07       0
  4983.7     .05       0  5002.5     .07       0  5073.1    .035       0
  5178.3     .07       0  5209.8    .035       0  5276.8     .07       0
Bank Sta=4983.7,5002.5
XS Rating Curve= 0 ,0
Exp/Cntr=0.3,0.1

Type RM Length L Ch R = 1 ,148757  ,588,588,588
BEGIN DESCRIPTION:
X18973
END DESCRIPTION:
XS GIS Cut Line= 4
      2198387.85     13820158.31      2197932.11     13820049.81
      2197725.95     13820451.28       2197856.1      13820950.2
#Sta/Elev= 30
  4334.8 1025.53  4389.1 1022.21  4481.6  1020.4  4545.9 1018.07    4605 1014.63
  4761.8 1010.97  4805.7 1008.97  4833.5 1005.81  4850.4 1005.08  4877.9 1004.48
  4900.1 1005.17  4990.4  1002.9  4990.9  1002.4  5008.7  1002.4  5009.2  1002.9
  5038.6 1003.14  5049.8 1003.39  5078.9 1007.23  5092.5 1007.55  5101.4 1008.97
  5116.3 1009.07  5146.4 1011.27  5182.9 1012.76  5249.4 1013.84  5348.1  1017.5
  5496.1 1020.79    5510 1021.89  5671.9 1027.21  5707.2 1027.21  5770.2 1028.61
#Mann= 5 ,-1 , 0
  4334.8     .07       0  4850.4     .12       0  4990.4     .05       0
  5009.2     .12       0  5038.6     .07       0
Bank Sta=4990.4,5009.2
XS Rating Curve= 0 ,0
Exp/Cntr=0.3,0.1

Type RM Length L Ch R = 1 ,148169  ,519,519,519
BEGIN DESCRIPTION:
Dry Comal Creek 179.0
END DESCRIPTION:
XS GIS Cut Line= 3
      2198225.03     13820075.02        2197725.       13819825.
      2197324.97       13819775.
#Sta/Elev= 30
  4445.1 1019.55  4503.8 1017.47  4556.9 1014.12  4615.6 1013.33  4735.8 1009.85
  4825.3 1009.23  4842.8 1008.17  4906.3 1004.76  4928.7 1003.09  4931.8  1002.2
  4945.5  997.97  4971.6  993.39  4972.1  992.89  4991.5  992.89    4992  993.39
  5006.7  994.06  5034.4  999.39    5047  1007.9  5054.5 1017.28  5064.6 1026.42
  5084.8 1038.17  5175.5 1068.13  5185.6 1069.86  5225.9 1079.58  5266.2 1082.51
  5306.5 1087.96  5326.6 1089.35  5345.9  1092.1  5364.4  1094.2  5407.3 1096.47
#Mann= 6 ,-1 , 0
  4445.1     .07       0  4842.8     .12       0  4931.8     .07       0
  4971.6     .05       0    4992     .07       0  5345.9     .12       0
Bank Sta=4971.6,4992
XS Rating Curve= 0 ,0
Exp/Cntr=0.3,0.1

Type RM Length L Ch R = 1 ,147650  ,540,540,540
BEGIN DESCRIPTION:
Dry Comal Creek 178.0
END DESCRIPTION:
XS GIS Cut Line= 3
      2198374.99     13819974.99        2198075.       13819475.
        2197675.       13819425.
#Sta/Elev= 30
  4404.8 1022.02  4463.1 1019.44  4498.1 1015.93  4529.2 1014.37  4587.5  1013.3
    4638 1011.13  4688.6 1010.26  4836.3 1005.45    4916  997.91  4958.7  995.54
    4985  990.55  4994.6  989.74  4997.8  989.12  4998.3  988.62  5018.2  989.12
  5030.7  997.38  5058.4 1003.93  5068.5 1010.01  5078.6 1019.41  5088.7 1027.47
  5106.3 1037.63  5118.9 1039.18  5131.5 1039.62  5229.8 1051.74    5260 1053.16
  5320.5 1059.81  5330.5 1061.05  5348.2 1065.02  5361.6 1066.38    5391 1067.97
#Mann= 6 ,-1 , 0
  4404.8     .07       0  4994.6     .12       0  4997.8     .05       0
  5018.2     .12       0  5131.5     .07       0  5361.6     .12       0
Bank Sta=4997.8,5018.2
XS Rating Curve= 0 ,0
Exp/Cntr=0.3,0.1

Type RM Length L Ch R = 1 ,147110  ,553,553,553
BEGIN DESCRIPTION:
Dry Comal Creek 177.0
END DESCRIPTION:
XS GIS Cut Line= 3
        2198575.     13819974.99        2198525.       13819225.
      2198174.97     13819024.98
#Sta/Elev= 30
  4242.3 1022.91  4302.4 1021.41  4392.6 1015.55  4502.9 1011.93    4583 1007.51
  4653.2 1005.16  4763.4 1003.66  4820.8 1001.06  4933.8  996.01  4953.9  996.37
  4990.9  995.21  5013.2     994  5013.7   993.5  5033.7     994  5045.1  998.41
  5060.9 1001.26  5066.7 1005.12  5082.5 1009.31  5088.3 1016.42  5097.6 1019.17
  5109.8 1021.51  5119.9  1022.3  5125.7 1024.12  5168.9 1028.78  5200.5 1030.94
  5212.8 1033.03  5249.5 1034.72    5346 1041.49  5383.4  1042.9  5397.1 1044.63
#Mann= 6 ,-1 , 0
  4242.3     .07       0  4653.2    .035       0  4820.8     .07       0
  4990.9     .12       0  5013.2     .05       0  5033.7     .12       0
Bank Sta=5013.2,5033.7
XS Rating Curve= 0 ,0
Exp/Cntr=0.3,0.1

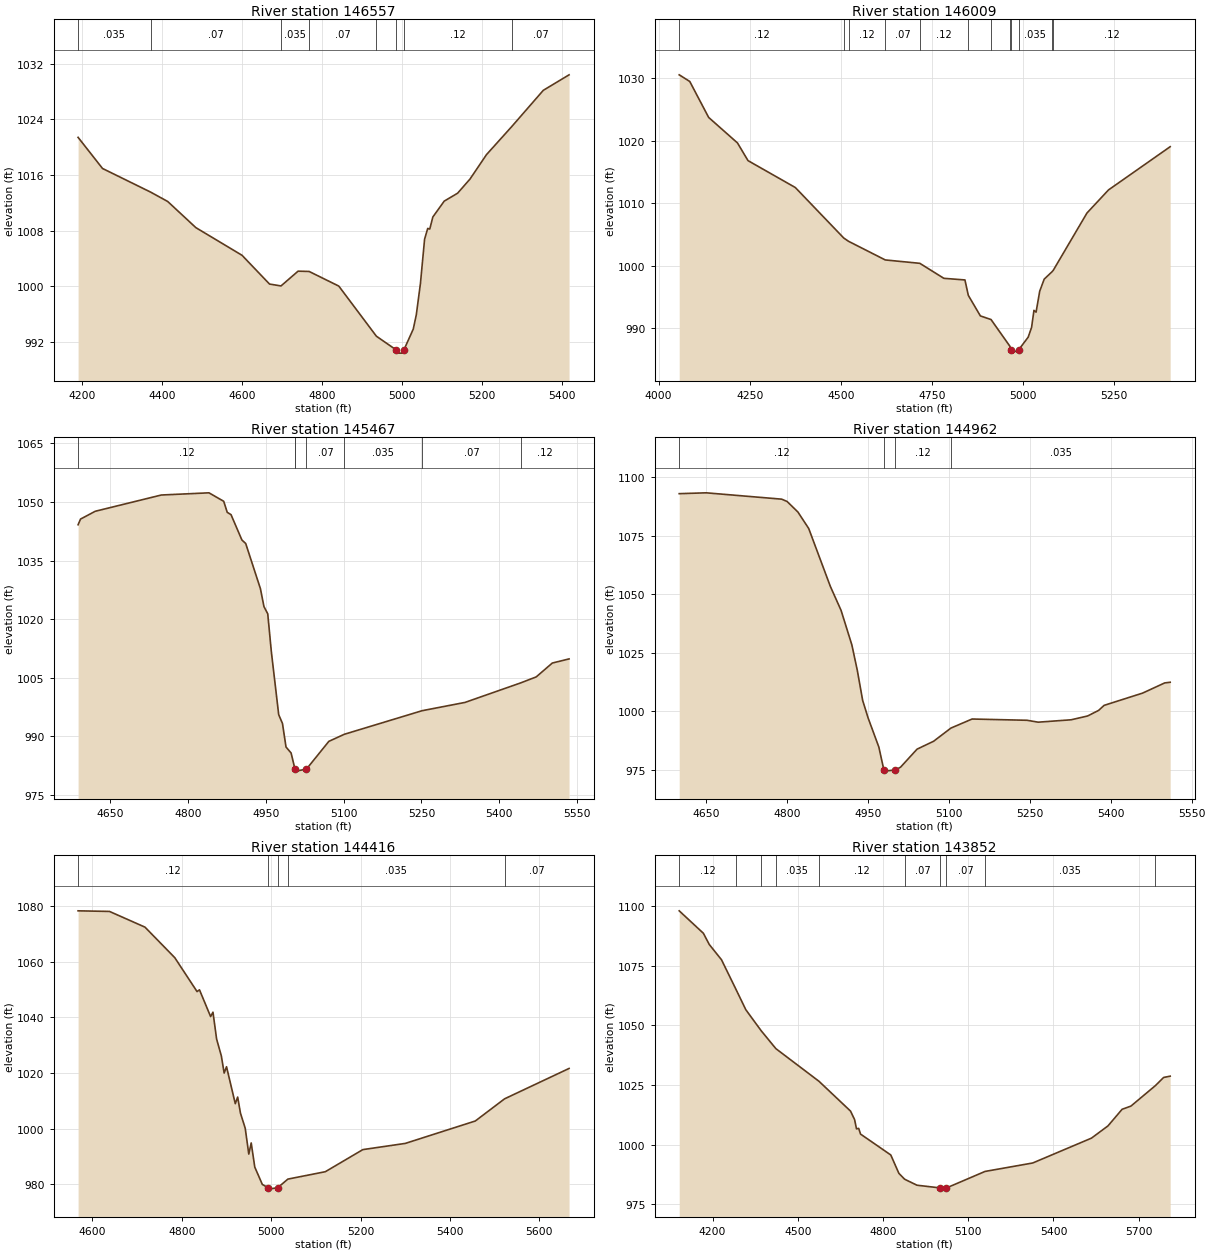
Type RM Length L Ch R = 1 ,146557  ,548,548,548
BEGIN DESCRIPTION:
Dry Comal Creek 176.0
END DESCRIPTION:
XS GIS Cut Line= 3
      2198875.01     13819974.95        2199025.       13819175.
        2198925.       13818775.
#Sta/Elev= 30
  4190.4 1021.41  4251.4 1016.94  4371.4 1013.55  4414.2  1012.2  4484.6 1008.44
  4599.9 1004.47  4668.5 1000.34  4697.2 1000.07  4739.8 1002.19  4767.4 1002.15
  4841.5 1000.05  4935.4  992.85  4983.9  990.92  4984.4  990.42  5003.9  990.42
  5004.4  990.92  5027.5  993.87  5035.2  995.96  5045.5 1000.47  5055.8 1006.79
  5063.6 1008.33  5068.7 1008.24  5076.4 1009.97  5104.8 1012.25  5138.3 1013.39
  5169.2 1015.42  5210.4 1018.93  5273.5 1022.96  5352.2 1028.16  5416.6 1030.39
#Mann= 8 ,-1 , 0
  4190.4    .035       0  4371.4     .07       0  4697.2    .035       0
  4767.4     .07       0  4935.4     .12       0  4983.9     .05       0
  5004.4     .12       0  5273.5     .07       0
Bank Sta=4983.9,5004.4
XS Rating Curve= 0 ,0
Exp/Cntr=0.3,0.1

Type RM Length L Ch R = 1 ,146009  ,542,542,542
BEGIN DESCRIPTION:
Dry Comal Creek 175.0
END DESCRIPTION:
XS GIS Cut Line= 3
      2199025.01     13820124.99        2199525.       13819325.
        2199325.       13818975.
#Sta/Elev= 30
  4056.6 1030.55  4085.5 1029.49  4137.4 1023.73  4216.4 1019.65  4245.3 1016.82
    4375 1012.52  4507.8 1004.44  4521.1 1003.91  4621.7 1000.93  4716.4 1000.39
  4782.4  997.99  4840.2  997.73  4849.5  995.26  4882.6  991.97  4911.7   991.4
  4963.4  987.13  4966.7  986.52  4967.2  986.02  4987.2  986.52  5013.7  988.58
    5023  990.14  5029.5  992.86  5035.3  992.58  5045.3  995.93  5057.6  997.86
  5078.3     999  5082.1  999.24  5174.9 1008.44  5233.9 1012.13  5403.1 1019.05
#Mann= 12 ,-1 , 0
  4056.6     .12       0  4507.8    .035       0  4521.1     .12       0
  4621.7     .07       0  4716.4     .12       0  4849.5    .035       0
  4911.7     .07       0  4963.4    .035       0  4966.7    .035       0
  4987.2    .035       0  5078.3     .07       0  5082.1     .12       0
Bank Sta=4966.7,4987.2
XS Rating Curve= 0 ,0
Exp/Cntr=0.3,0.1

Type RM Length L Ch R = 1 ,145467  ,505,505,505
BEGIN DESCRIPTION:
Dry Comal Creek 174.0
END DESCRIPTION:
XS GIS Cut Line= 3
      2200254.18     13819572.39        2199975.       13819275.
      2199475.01     13819075.01
#Sta/Elev= 30
  4588.2 1044.17  4592.9 1045.62  4621.2 1047.62  4748.7 1051.79  4840.5 1052.35
  4868.9 1050.18  4875.7 1047.35    4883 1046.76    4904 1040.26  4911.3 1039.37
  4939.7 1027.78  4946.5  1023.2  4953.8 1021.35  4960.7 1011.69  4974.9  995.51
  4982.2  993.25    4989  987.23  4998.8   985.7  5005.7  981.87  5006.9  981.55
  5007.4  981.05  5028.3  981.55  5071.5  988.67  5101.4  990.49  5251.3  996.53
    5334  998.65  5441.5 1003.66  5471.3 1005.19  5502.3 1008.74  5534.6  1009.8
#Mann= 7 ,-1 , 0
  4588.2     .12       0  5005.7     .07       0  5006.9     .05       0
  5028.3     .07       0  5101.4    .035       0  5251.3     .07       0
  5441.5     .12       0
Bank Sta=5006.9,5028.3
XS Rating Curve= 0 ,0
Exp/Cntr=0.3,0.1

Type RM Length L Ch R = 1 ,144962  ,546,546,546
BEGIN DESCRIPTION:
Dry Comal Creek 173.0
END DESCRIPTION:
XS GIS Cut Line= 3
      2200375.02       13818825.        2199975.       13818825.
      2199475.02       13818925.
#Sta/Elev= 30
  4600.3 1092.94  4650.3  1093.3  4790.3 1090.59  4800.3 1089.59  4820.3 1085.09
  4840.3 1078.05  4880.3 1053.35  4900.3 1043.02  4920.3 1028.25  4930.3 1017.46
  4940.3 1004.52  4950.3   997.1  4970.3  984.58  4979.6  974.81  4980.1  974.31
    5001  974.81  5010.5     976  5041.1  983.71  5071.7  987.07  5103.8  992.71
  5143.1  996.59  5245.1  996.05  5265.5  995.24  5326.7  996.26  5357.2  997.89
  5377.6 1000.28  5387.8 1002.43  5459.2 1007.68    5500 1012.02  5510.2 1012.31
#Mann= 4 ,-1 , 0
  4600.3     .12       0  4979.6     .05       0    5001     .12       0
  5103.8    .035       0
Bank Sta=4979.6,5001
XS Rating Curve= 0 ,0
Exp/Cntr=0.3,0.1

Type RM Length L Ch R = 1 ,144416  ,564,564,564
BEGIN DESCRIPTION:
Dry Comal Creek 172.0
END DESCRIPTION:
XS GIS Cut Line= 3
      2200225.03     13818475.01        2199825.       13818325.
      2199224.96     13818625.02
#Sta/Elev= 30
  4568.2 1078.33  4638.5 1078.11  4717.8 1072.47  4784.5 1061.49  4834.3 1049.31
  4839.7 1049.95  4864.6 1040.34  4869.9 1041.91    4878 1032.26  4888.6  1026.2
  4894.9 1020.04  4900.2 1022.31  4919.8 1009.03  4925.1 1011.41  4931.4 1005.61
    4942 1000.22    4950  990.92  4955.4  994.92  4963.4  986.24  4980.3  980.01
  4993.1  978.83  4993.6  978.33  5014.6  978.83  5037.4  981.93  5121.2  984.59
  5205.1  992.53  5300.1  994.76  5456.6 1002.81  5522.1 1010.78  5666.3 1021.69
#Mann= 5 ,-1 , 0
  4568.2     .12       0  4993.1     .05       0  5014.6     .12       0
  5037.4    .035       0  5522.1     .07       0
Bank Sta=4993.1,5014.6
XS Rating Curve= 0 ,0
Exp/Cntr=0.3,0.1

Type RM Length L Ch R = 1 ,143852  ,568,568,568
BEGIN DESCRIPTION:
Dry Comal Creek 171.0
END DESCRIPTION:
XS GIS Cut Line= 3
      2200225.03     13817274.98        2199525.       13817875.
      2198825.01     13818274.99
#Sta/Elev= 30
  4082.6 1098.02  4167.7 1088.61  4188.5  1083.9  4231.4 1077.52  4282.3 1065.13
    4317 1056.58  4371.4 1047.72  4422.8 1040.26  4574.5 1026.58  4685.7 1014.07
    4700 1010.49  4706.6 1006.63  4714.3 1006.83  4720.9 1004.44  4827.3  995.69
  4855.9  987.97  4876.2  985.51  4919.5  983.01  5001.7  981.87  5002.2  981.37
  5023.3  981.87    5159  988.78  5327.1  992.33  5533.7 1002.74    5592 1007.89
  5641.6 1014.84  5672.6 1016.17  5758.4 1024.72  5787.8 1028.18  5810.8 1028.72
#Mann= 10 ,-1 , 0
  4082.6     .12       0  4282.3    .035       0  4371.4     .07       0
  4422.8    .035       0  4574.5     .12       0  4876.2     .07       0
  5001.7     .05       0  5023.3     .07       0    5159    .035       0
  5758.4     .07       0
Bank Sta=5001.7,5023.3
XS Rating Curve= 0 ,0
Exp/Cntr=0.3,0.1

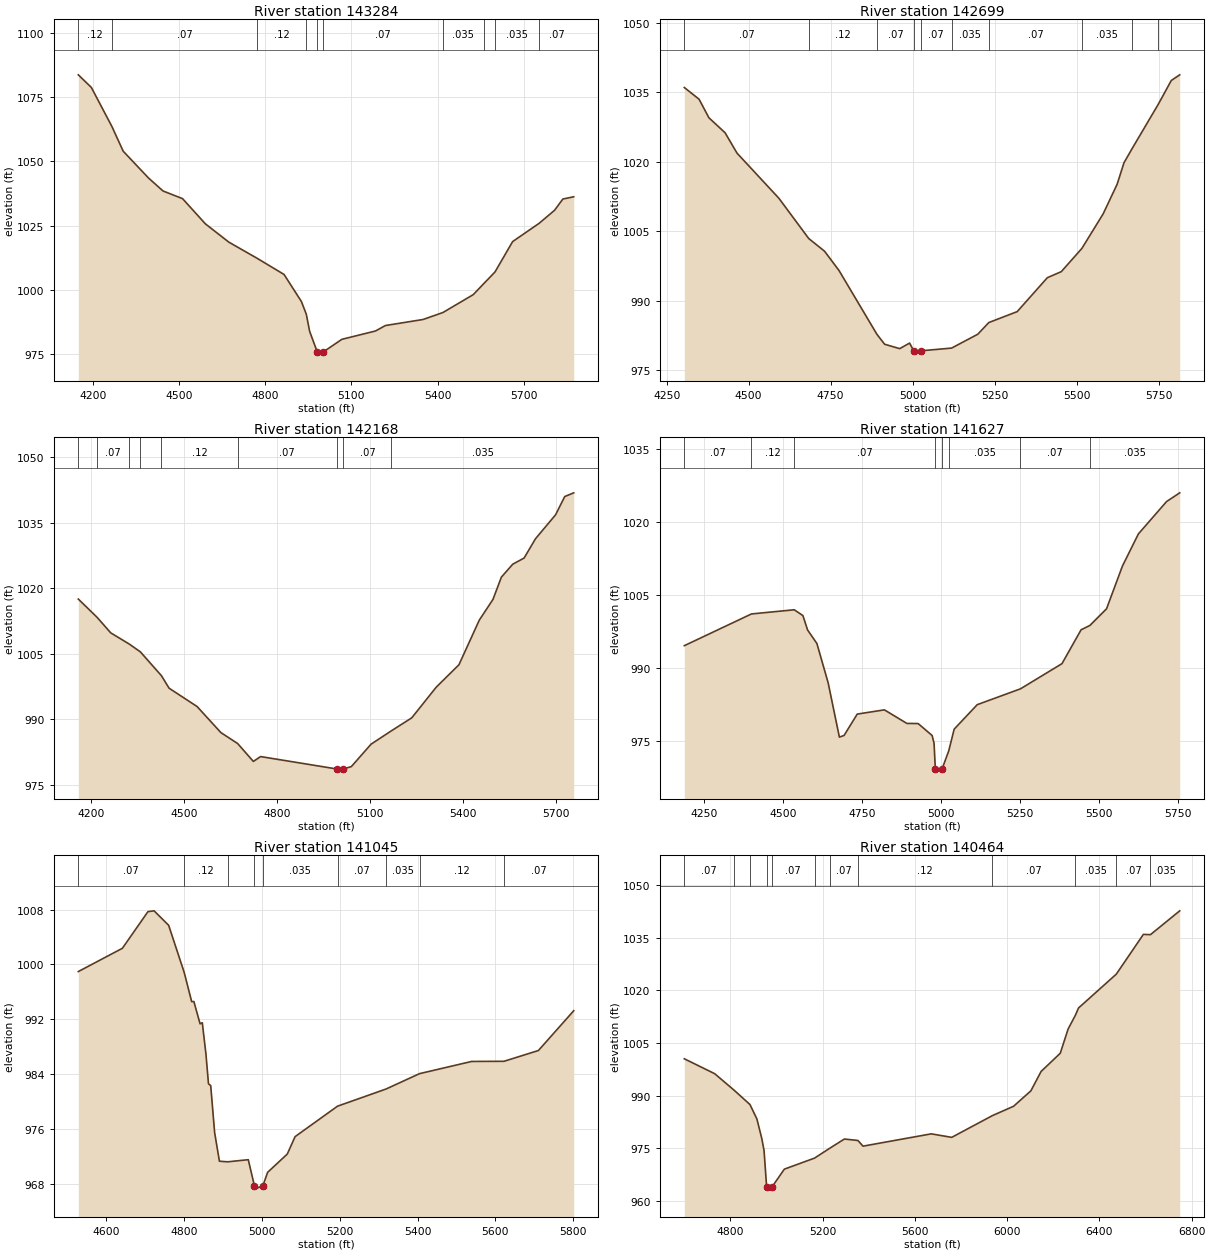
Type RM Length L Ch R = 1 ,143284  ,585,585,585
BEGIN DESCRIPTION:
Dry Comal Creek 170.0
END DESCRIPTION:
XS GIS Cut Line= 3
      2199974.98     13817075.01        2199225.       13817475.
      2198424.99       13817825.
#Sta/Elev= 30
    4150 1083.66  4195.3 1078.77  4267.1 1063.52  4306.2 1053.96    4394 1043.57
  4444.6 1038.51  4512.6 1035.53    4592 1025.73  4673.8  1018.6  4771.5 1012.37
  4865.7 1006.05    4926  995.54    4943  990.61  4954.6  983.97    4981  975.97
  4981.5  975.47  5002.6  975.97  5066.6  980.83  5183.6  984.07  5218.3   986.2
  5349.3  988.55  5418.4  991.26  5523.9  998.22  5560.4  1002.5  5599.3 1007.01
  5660.7 1018.83  5752.6 1025.91  5806.5    1031  5835.4 1035.37  5873.2 1036.26
#Mann= 10 ,-1 , 0
    4150     .12       0  4267.1     .07       0  4771.5     .12       0
    4943     .07       0    4981     .05       0  5002.6     .07       0
  5418.4    .035       0  5560.4     .07       0  5599.3    .035       0
  5752.6     .07       0
Bank Sta=4981,5002.6
XS Rating Curve= 0 ,0
Exp/Cntr=0.3,0.1

Type RM Length L Ch R = 1 ,142699  ,531,531,531
BEGIN DESCRIPTION:
Dry Comal Creek 169.0
END DESCRIPTION:
XS GIS Cut Line= 3
      2199475.04     13816824.99        2198825.       13817075.
        2198275.       13817675.
#Sta/Elev= 30
  4303.9 1036.07  4348.9 1033.54  4378.9 1029.53  4428.2 1026.29  4464.7 1021.88
  4592.2 1012.14  4683.3 1003.43  4731.4  1000.7  4775.4  996.54  4891.2  982.73
  4914.6  980.59  4960.7  979.64  4990.7  980.84  5003.4  979.17  5003.9  978.67
  5025.1  979.17  5118.8  979.76  5198.6  982.75  5232.3  985.28  5318.8  987.64
  5410.7  994.97  5453.3  996.28  5516.2 1001.32  5580.9 1008.77  5623.5 1015.17
  5644.4 1019.82  5668.6  1022.8    5749 1032.46  5788.6 1037.59  5814.3 1038.81
#Mann= 11 ,-1 , 0
  4303.9     .07       0  4683.3     .12       0  4891.2     .07       0
  5003.4     .05       0  5025.1     .07       0  5118.8    .035       0
  5232.3     .07       0  5516.2    .035       0  5668.6     .07       0
    5749    .035       0  5788.6     .07       0
Bank Sta=5003.4,5025.1
XS Rating Curve= 0 ,0
Exp/Cntr=0.3,0.1

Type RM Length L Ch R = 1 ,142168  ,541,541,541
BEGIN DESCRIPTION:
Dry Comal Creek 168.0
END DESCRIPTION:
XS GIS Cut Line= 3
      2199225.01       13816625.        2198425.       13816875.
      2198024.99     13817525.02
#Sta/Elev= 30
  4157.4 1017.53  4217.8 1013.38  4262.2  1009.8    4322 1007.24  4357.9 1005.46
  4426.2  999.99  4450.8  997.14  4541.4  992.94  4618.4  986.97  4672.4  984.48
  4723.2  980.38  4746.7  981.49  4992.4  978.66  4992.9  978.16  5014.1  978.66
    5040   979.2  5103.8  984.33  5169.7   987.4  5235.2  990.35  5314.4  997.37
  5387.8  1002.5  5453.5  1012.7  5497.9 1017.47    5525 1022.55  5561.7 1025.51
  5598.4 1026.92  5635.1 1031.32  5700.1 1036.81  5729.8 1040.99  5758.8 1041.84
#Mann= 9 ,-1 , 0
  4157.4    .035       0  4217.8     .07       0    4322     .12       0
  4357.9     .07       0  4426.2     .12       0  4672.4     .07       0
  4992.4     .05       0  5014.1     .07       0  5169.7    .035       0
Bank Sta=4992.4,5014.1
XS Rating Curve= 0 ,0
Exp/Cntr=0.3,0.1

Type RM Length L Ch R = 1 ,141627  ,582,582,582
BEGIN DESCRIPTION:
Dry Comal Creek 167.0
END DESCRIPTION:
XS GIS Cut Line= 3
      2198496.32     13815861.48        2198025.       13816525.
        2197925.     13817274.98
#Sta/Elev= 30
  4186.1  994.52  4398.9 1001.05  4534.6 1001.91  4562.1 1000.71  4576.9  997.75
  4606.4  994.97  4642.1  986.87  4677.7   975.7  4692.5  976.04  4734.3  980.44
  4820.4  981.31  4891.7  978.52  4927.4  978.49  4971.7  976.03  4977.8  974.45
  4981.8   969.2  4982.3   968.7  5003.5   969.2  5024.3  972.86  5041.6  977.34
  5114.7  982.38  5251.8  985.64  5383.3  990.82  5443.9  997.79  5471.9  998.69
  5524.6 1002.11    5575 1010.91  5625.5 1017.52    5715 1024.19  5756.6 1025.98
#Mann= 8 ,-1 , 0
  4186.1     .07       0  4398.9     .12       0  4534.6     .07       0
  4981.8     .05       0  5003.5     .07       0  5024.3    .035       0
  5251.8     .07       0  5471.9    .035       0
Bank Sta=4981.8,5003.5
XS Rating Curve= 0 ,0
Exp/Cntr=0.3,0.1

Type RM Length L Ch R = 1 ,141045  ,581,581,581
BEGIN DESCRIPTION:
Dry Comal Creek 166.0
END DESCRIPTION:
XS GIS Cut Line= 3
      2197856.17     13815720.36        2197625.       13816125.
        2197725.     13816924.96
#Sta/Elev= 30
  4528.9  998.96  4642.1 1002.35  4707.7 1007.69  4723.5 1007.81  4760.9  1005.7
  4800.7  998.86    4820  994.58  4825.7  994.59  4841.6  991.34  4847.3   991.5
  4856.7  986.92  4863.2   982.6  4868.9  982.34    4879  975.47  4891.3  971.32
  4912.2  971.23  4965.4  971.54  4981.1  967.75  4981.6  967.25  5002.9  967.75
  5015.1   969.7  5065.5  972.36  5085.6   974.9  5194.6  979.34  5319.2  981.84
  5405.1  984.08  5539.1  985.86  5622.1  985.88  5710.4  987.45  5801.1  993.25
#Mann= 9 ,-1 , 0
  4528.9     .07       0  4800.7     .12       0  4912.2    .035       0
  4981.1    .035       0  5002.9    .035       0  5194.6     .07       0
  5319.2    .035       0  5405.1     .12       0  5622.1     .07       0
Bank Sta=4981.1,5002.9
XS Rating Curve= 0 ,0
Exp/Cntr=0.3,0.1

Type RM Length L Ch R = 1 ,140464  ,870,870,870
BEGIN DESCRIPTION:
Dry Comal Creek 165.0
END DESCRIPTION:
XS GIS Cut Line= 3
      2197275.02     13815674.96        2197075.       13816025.
      2197874.98     13817574.97
#Sta/Elev= 30
    4601 1000.52  4732.8  996.26  4817.4  991.52  4885.5  987.47  4915.6  983.35
  4937.2  977.66  4946.6  974.35    4958  963.83  4958.5  963.33  4979.8  963.83
  5034.6  969.03  5165.5  972.18  5231.1  974.98  5294.8  977.62  5353.5  977.21
  5375.5  975.59  5671.4   979.1  5760.1   978.1  5936.3   984.3  6028.2  986.97
  6103.3  991.38  6147.6  996.91  6230.6  1002.1  6264.5 1008.99    6296 1012.92
  6309.6    1015  6473.5 1024.67  6590.9 1036.01  6621.5 1035.93  6748.4 1042.73
#Mann= 12 ,-1 , 0
    4601     .07       0  4817.4     .12       0  4885.5     .07       0
    4958     .05       0  4979.8     .07       0  5165.5     .12       0
  5231.1     .07       0  5353.5     .12       0  5936.3     .07       0
    6296    .035       0  6473.5     .07       0  6621.5    .035       0
Bank Sta=4958,4979.8
XS Rating Curve= 0 ,0
Exp/Cntr=0.3,0.1

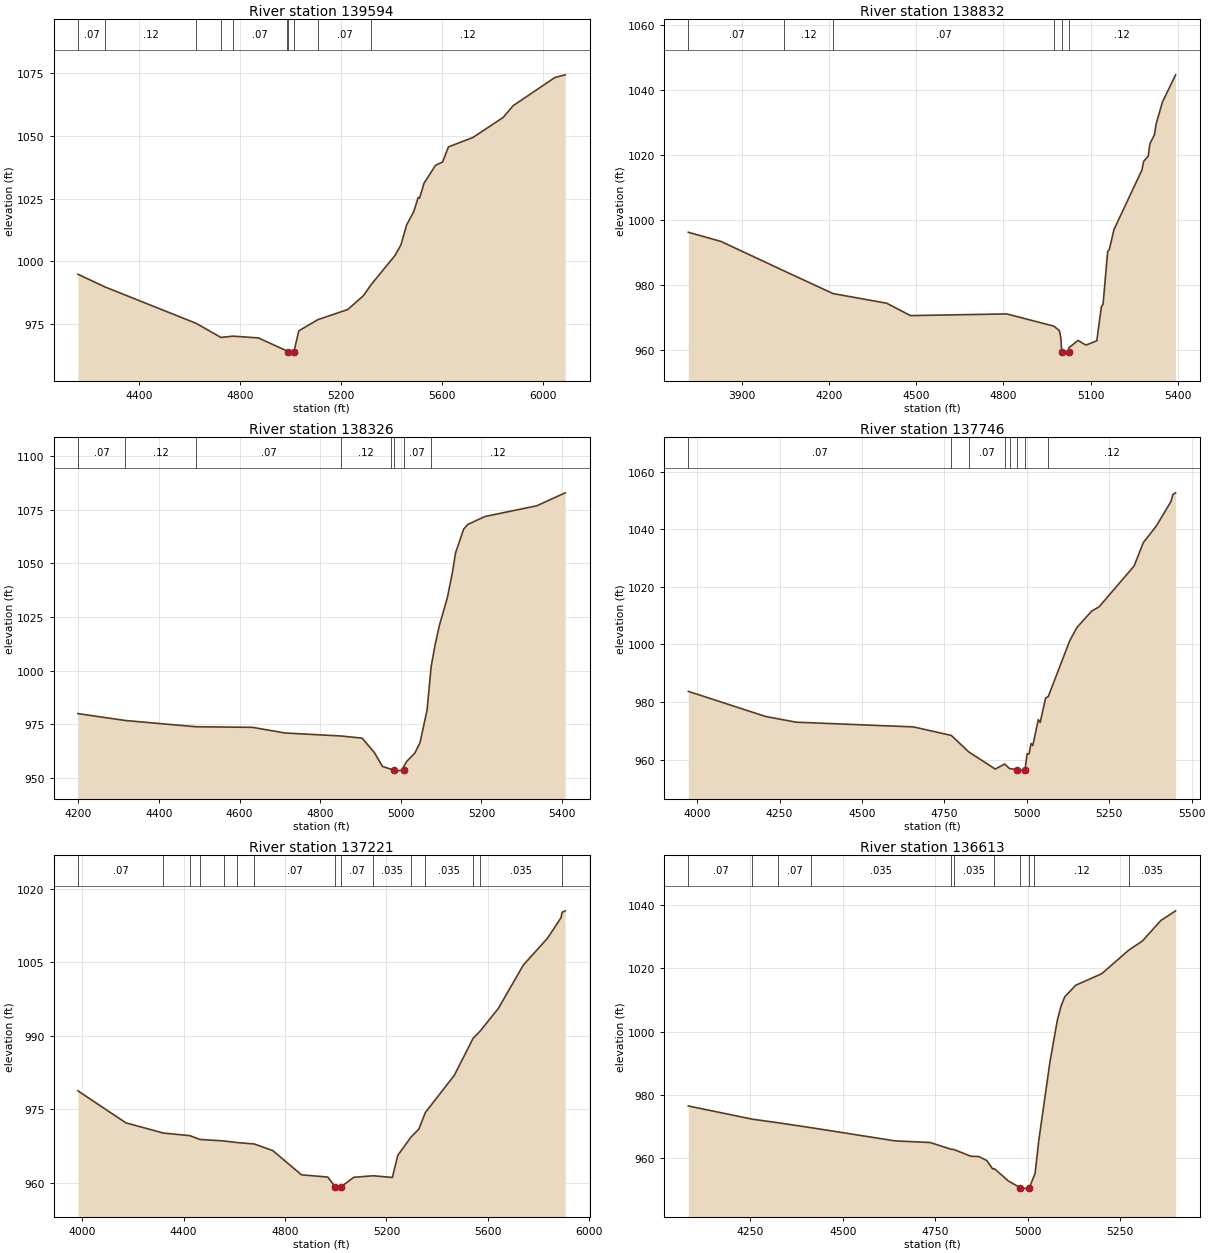
Type RM Length L Ch R = 1 ,139594  ,762,762,762
BEGIN DESCRIPTION:
X18972
END DESCRIPTION:
XS GIS Cut Line= 3
      2197042.32     13815698.69      2196478.12     13815904.84
      2195913.89     13817109.25
#Sta/Elev= 30
  4156.1  994.84    4265   989.7  4624.7  975.24  4722.7  969.62  4770.2  970.13
  4871.6  969.42  4986.5  964.11  4987.9  963.85  4988.4  963.35    5012  963.85
  5031.4  972.25  5107.9  976.75    5225  980.74    5287  986.23  5319.1  990.82
  5413.2 1002.42    5436 1006.55  5458.9  1014.6  5487.2 1019.91  5504.5 1025.53
    5510 1025.22  5527.3 1031.11    5573 1038.29  5601.4 1039.69  5624.2 1045.67
    5721 1049.41  5840.7  1057.4  5880.8 1062.13  6046.1 1073.37  6086.8 1074.44
#Mann= 10 ,-1 , 0
  4156.1     .07       0    4265     .12       0  4624.7     .07       0
  4722.7     .12       0  4770.2     .07       0  4986.5     .12       0
  4987.9     .05       0    5012     .12       0  5107.9     .07       0
  5319.1     .12       0
Bank Sta=4987.9,5012
XS Rating Curve= 0 ,0
Exp/Cntr=0.3,0.1

Type RM Length L Ch R = 1 ,138832  ,506,506,506
BEGIN DESCRIPTION:
Dry Comal Creek 164.0
END DESCRIPTION:
XS GIS Cut Line= 3
      2197075.05     13815624.99        2195825.       13815875.
      2195475.01     13815675.01
#Sta/Elev= 30
  3714.8  996.21    3827   993.4  4045.8  984.26  4212.9  977.35  4398.1  974.36
  4479.7  970.56  4811.1  971.08    4973  967.33  4992.5  965.97  4997.5  963.67
  5000.5  959.51    5001  959.01  5024.8  959.51  5024.9  960.63  5056.5  962.92
  5083.9   961.5  5121.3  962.79  5137.2  973.32  5142.9  974.05  5158.8  990.27
  5164.5  990.92  5180.4  997.03  5276.8 1015.38  5282.6 1018.02  5298.4 1019.66
  5304.2 1023.44    5320 1026.24  5325.8 1029.61  5347.4  1036.3  5392.7 1044.67
#Mann= 6 ,-1 , 0
  3714.8     .07       0  4045.8     .12       0  4212.9     .07       0
    4973     .12       0  5000.5     .05       0  5024.8     .12       0
Bank Sta=5000.5,5024.8
XS Rating Curve= 0 ,0
Exp/Cntr=0.3,0.1

Type RM Length L Ch R = 1 ,138326  ,580,580,580
BEGIN DESCRIPTION:
Dry Comal Creek 163.0
END DESCRIPTION:
XS GIS Cut Line= 3
      2196624.97       13815525.        2195825.       13815425.
        2195425.       13815375.
#Sta/Elev= 30
  4198.6  980.02  4316.6   976.8  4491.4   973.9  4631.9  973.62  4712.5  970.99
  4852.3  969.58    4904  968.58  4934.2  961.93  4954.4  955.43  4974.9  954.16
  4982.6  953.72  4983.1  953.22  5006.9  953.72  5007.3  955.41  5014.9  957.79
    5035  961.69  5047.6  966.44  5065.3   981.8  5073.8  998.96  5075.3 1001.99
  5085.4  1012.3  5095.5  1020.9  5115.6 1034.08  5128.2 1045.87  5135.8 1054.83
    5156 1065.98    5166 1068.11  5208.9 1071.84  5337.4 1076.83  5407.9 1082.87
#Mann= 8 ,-1 , 0
  4198.6     .07       0  4316.6     .12       0  4491.4     .07       0
  4852.3     .12       0  4974.9     .07       0  4982.6     .05       0
  5006.9     .07       0  5073.8     .12       0
Bank Sta=4982.6,5006.9
XS Rating Curve= 0 ,0
Exp/Cntr=0.3,0.1

Type RM Length L Ch R = 1 ,137746  ,525,525,525
BEGIN DESCRIPTION:
Dry Comal Creek 162.0
END DESCRIPTION:
XS GIS Cut Line= 3
      2196725.01     13815525.01        2195925.       13814875.
        2195525.       13815075.
#Sta/Elev= 30
  3973.3  983.71  4207.5  974.99  4300.1     973  4656.2  971.36  4770.9   968.4
  4823.7  962.69  4904.2  956.71    4933  958.46  4947.6  956.88  4970.4  956.49
  4970.9  955.99  4994.7  956.49  5000.9  961.98  5006.9  961.98  5012.5  965.58
  5018.1  964.88  5034.8  973.86  5040.4  972.89  5057.2  981.45  5064.9  981.86
  5129.9 1001.24  5152.2 1005.96  5196.9 1011.62  5219.3  1013.1  5325.5 1027.29
  5353.5 1035.45  5392.6 1041.14  5437.3 1049.71  5442.9 1052.13  5451.3 1052.71
#Mann= 8 ,-1 , 0
  3973.3     .07       0  4770.9     .12       0  4823.7     .07       0
    4933     .12       0  4947.6    .035       0  4970.4    .035       0
  4994.7    .035       0  5064.9     .12       0
Bank Sta=4970.4,4994.7
XS Rating Curve= 0 ,0
Exp/Cntr=0.3,0.1

Type RM Length L Ch R = 1 ,137221  ,608,608,608
BEGIN DESCRIPTION:
X18971
END DESCRIPTION:
XS GIS Cut Line= 4
      2196977.25     13815080.19      2196326.21       13814440.
      2195924.73      13814526.8      2195371.34     13814754.67
#Sta/Elev= 30
    3983  978.75  4172.1  972.22  4319.5  970.14  4424.3   969.6  4464.3  968.83
  4558.4  968.52  4609.1   968.2  4678.7   967.9    4752  966.55  4865.1  961.61
  4968.9  961.15  4997.7  959.19  4998.2  958.69    5022  959.19  5071.2   961.1
    5148  961.42  5223.5  961.07  5245.2  965.59  5297.5  969.34  5328.2  970.93
  5353.7  974.32  5468.1  981.92  5542.1  989.46  5569.5  990.91  5641.8  995.56
    5740 1004.39  5835.8 1009.89  5889.1 1014.07  5893.1 1015.16  5905.3 1015.47
#Mann= 15 ,-1 , 0
    3983     .07       0  4319.5     .12       0  4424.3     .07       0
  4464.3    .035       0  4558.4     .07       0  4609.1    .035       0
  4678.7     .07       0  4997.7     .05       0    5022     .07       0
    5148    .035       0  5297.5     .07       0  5353.7    .035       0
  5542.1     .07       0  5569.5    .035       0  5893.1     .07       0
Bank Sta=4997.7,5022
XS Rating Curve= 0 ,0
Exp/Cntr=0.3,0.1

Type RM Length L Ch R = 1 ,136613  ,567,567,567
BEGIN DESCRIPTION:
Dry Comal Creek 161.0
END DESCRIPTION:
XS GIS Cut Line= 3
      2197025.02     13814975.03        2196575.       13814175.
        2196575.     13813775.01
#Sta/Elev= 30
  4082.1   976.5  4255.6  972.31  4324.2   971.2  4414.2  969.63  4640.8  965.46
  4736.1  964.94  4793.3  962.79  4799.6  962.76  4846.1  960.59  4867.7   960.5
  4889.4  959.23  4905.4  956.54  4909.6  956.69  4948.7  952.68  4979.6  950.69
  4980.1  950.19  5004.5  950.69  5017.3  954.37    5020  955.17    5030  965.59
    5060   990.3    5080 1003.56    5090 1008.02    5100 1011.01    5130  1014.7
    5200 1018.33  5273.7 1025.85    5310 1028.67    5360 1035.18    5400 1038.24
#Mann= 11 ,-1 , 0
  4082.1     .07       0  4255.6    .035       0  4324.2     .07       0
  4414.2    .035       0  4793.3     .07       0  4799.6    .035       0
  4909.6     .07       0  4979.6     .05       0  5004.5     .07       0
  5017.3     .12       0  5273.7    .035       0
Bank Sta=4979.6,5004.5
XS Rating Curve= 0 ,0
Exp/Cntr=0.3,0.1