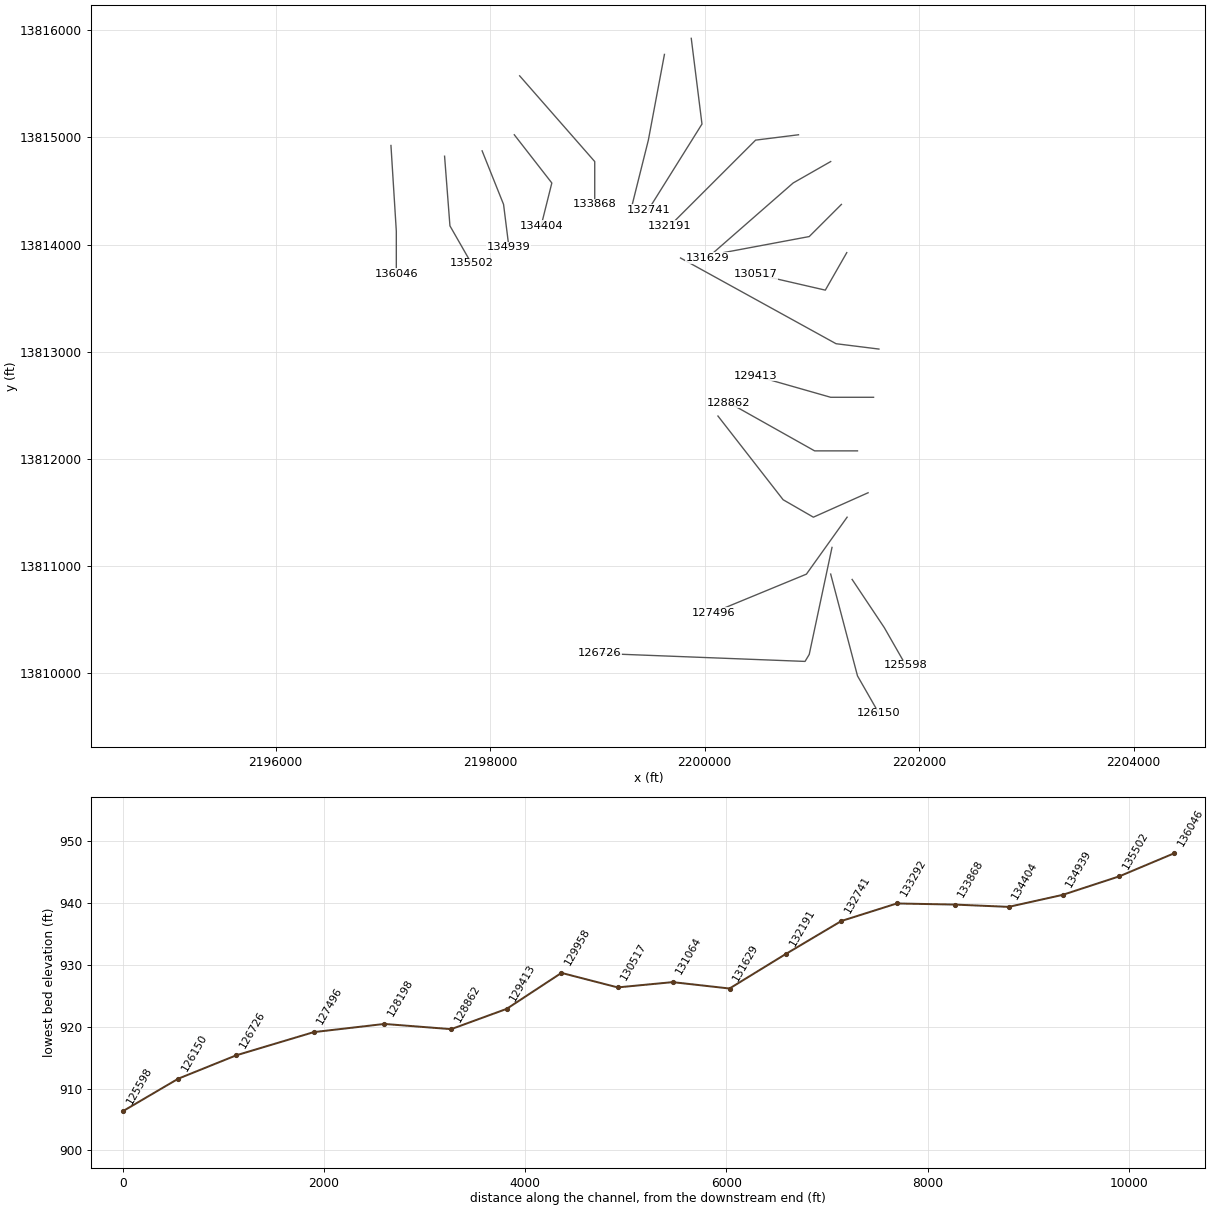
HEC-RAS study Dry Comal Creek.prj: Dry Comal Creek Base Level Engineering

--- Dry Comal Creek.g01 (geometry) --- (continued)

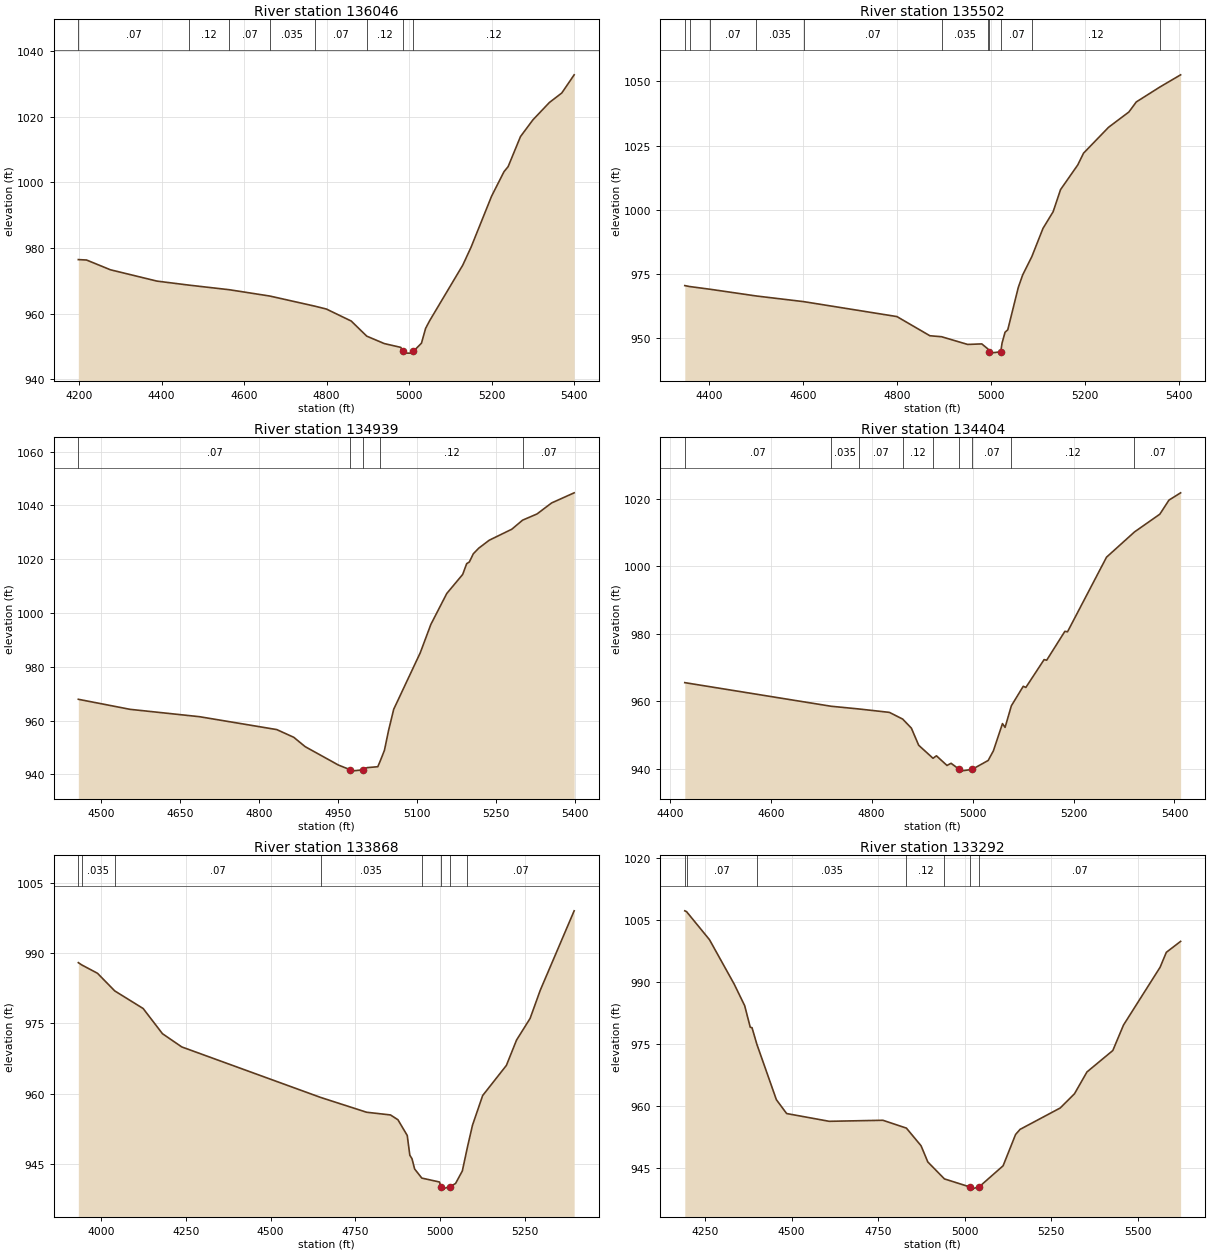
Type RM Length L Ch R = 1 ,136046  ,544,544,544
BEGIN DESCRIPTION:
Dry Comal Creek 160.0
END DESCRIPTION:
XS GIS Cut Line= 3
        2197075.     13814925.01        2197125.       13814125.
        2197125.     13813724.97
#Sta/Elev= 30
  4198.4  976.45  4218.4  976.32  4276.1  973.35  4388.8   969.9  4465.8  968.68
  4564.2  967.27  4662.6  965.34  4771.2  962.27  4799.6  961.38  4859.7  957.73
  4897.4  953.12  4939.9  950.86  4979.9   949.7    4985  948.45  4985.5  947.95
  5009.5  947.95    5010  948.45    5030  950.98    5040  955.49    5050  957.87
    5130  974.75    5150  980.18    5200   995.8    5230 1003.24    5240 1004.78
    5270 1013.95    5300 1019.02    5340 1024.32    5370 1027.21    5400 1032.75
#Mann= 8 ,-1 , 0
  4198.4     .07       0  4465.8     .12       0  4564.2     .07       0
  4662.6    .035       0  4771.2     .07       0  4897.4     .12       0
    4985     .05       0    5010     .12       0
Bank Sta=4985,5010
XS Rating Curve= 0 ,0
Exp/Cntr=0.3,0.1

Type RM Length L Ch R = 1 ,135502  ,563,563,563
BEGIN DESCRIPTION:
Dry Comal Creek 159.0
END DESCRIPTION:
XS GIS Cut Line= 3
        2197575.     13814825.01        2197625.       13814175.
      2197824.98     13813825.04
#Sta/Elev= 30
  4348.4  970.51  4358.7  970.14  4402.4  969.08  4500.8  966.46  4601.3  964.27
  4799.7  958.46  4869.9     951  4894.7  950.62  4950.2  947.62  4980.3  947.83
  4993.2   945.9  4995.7  944.74  4996.2  944.24  5020.7  944.74  5023.4  948.12
  5029.8  952.36  5035.6  953.31  5057.9  969.73  5067.3  974.65  5086.9  981.82
  5110.5  992.74  5132.1  999.24  5147.9 1007.84  5184.6 1017.46  5196.8 1022.01
  5250.1 1032.09  5293.3 1038.03  5309.1 1041.95  5359.2 1047.74  5403.4 1052.49
#Mann= 11 ,-1 , 0
  4348.4     .07       0  4358.7    .035       0  4402.4     .07       0
  4500.8    .035       0  4601.3     .07       0  4894.7    .035       0
  4993.2     .07       0  4995.7     .05       0  5020.7     .07       0
  5086.9     .12       0  5359.2     .07       0
Bank Sta=4995.7,5020.7
XS Rating Curve= 0 ,0
Exp/Cntr=0.3,0.1

Type RM Length L Ch R = 1 ,134939  ,535,535,535
BEGIN DESCRIPTION:
Dry Comal Creek 158.0
END DESCRIPTION:
XS GIS Cut Line= 3
      2197925.02     13814874.96        2198125.       13814375.
        2198175.     13813974.98
#Sta/Elev= 30
  4457.1  967.94  4555.3  964.21  4687.3  961.47    4834  956.68  4866.3  953.81
  4887.9  950.34  4951.1   943.5  4973.6  941.75  4974.1  941.25  4998.6  941.75
  5005.6  942.55  5025.8  942.89  5030.7  945.15  5038.4  948.98    5046  956.13
    5056  964.22  5106.4  985.21  5126.6  995.77  5156.8 1007.25    5187 1014.33
  5194.6 1018.33  5199.6 1018.95  5207.2    1022  5217.3 1024.05  5237.4 1027.04
  5280.3 1031.13  5300.7 1034.49  5328.1 1036.79  5355.9 1040.89  5398.7 1044.65
#Mann= 5 ,-1 , 0
  4457.1     .07       0  4973.6     .05       0  4998.6     .07       0
  5030.7     .12       0  5300.7     .07       0
Bank Sta=4973.6,4998.6
XS Rating Curve= 0 ,0
Exp/Cntr=0.3,0.1

Type RM Length L Ch R = 1 ,134404  ,536,536,536
BEGIN DESCRIPTION:
Dry Comal Creek 157.0
END DESCRIPTION:
XS GIS Cut Line= 3
      2198224.97     13815025.04        2198575.       13814575.
      2198475.01     13814175.05
#Sta/Elev= 30
  4429.8  965.54  4719.9  958.54    4774  957.75  4835.2  956.73  4861.5  954.74
  4878.7  952.07  4893.2  946.99  4921.6  943.13  4928.4  943.86  4949.3     941
  4957.4  941.64  4973.8  939.82  4974.3  939.32  4998.9  939.82  5030.9  942.48
  5041.2  945.33  5059.2   953.4  5064.4  952.29  5076.8  958.67  5100.4  964.46
  5105.6  964.13  5141.7  972.37  5146.8  972.19  5182.9  980.75  5188.1  980.61
  5265.4 1002.72  5320.8  1010.2    5371 1015.46  5389.1 1019.63  5412.2 1021.79
#Mann= 9 ,-1 , 0
  4429.8     .07       0  4719.9    .035       0    4774     .07       0
  4861.5     .12       0  4921.6     .07       0  4973.8     .05       0
  4998.9     .07       0  5076.8     .12       0  5320.8     .07       0
Bank Sta=4973.8,4998.9
XS Rating Curve= 0 ,0
Exp/Cntr=0.3,0.1

Type RM Length L Ch R = 1 ,133868  ,576,576,576
BEGIN DESCRIPTION:
Dry Comal Creek 156.0
END DESCRIPTION:
XS GIS Cut Line= 3
      2198274.98     13815575.02        2198975.       13814775.
        2198975.     13814375.04
#Sta/Elev= 30
  3932.6  987.93  3942.6  987.45  3989.1  985.67  4040.1  981.91  4123.9  978.16
  4180.8   972.8  4237.8  969.98  4647.6  959.22    4783  956.07  4853.7  955.49
  4875.6  954.47  4903.1  951.12  4910.7  946.92  4917.3  946.14  4924.9  943.98
  4946.1  942.04  4998.1  941.21  5003.1  940.19  5003.6  939.69  5028.2  940.19
  5045.6  940.89  5065.6  943.55  5080.6   948.6  5095.6   953.3  5125.6  959.62
  5195.6  966.04  5225.6  971.44  5265.6  976.05  5295.6  982.06  5395.6  998.97
#Mann= 8 ,-1 , 0
  3932.6     .07       0  3942.6    .035       0  4040.1     .07       0
  4647.6    .035       0  4946.1     .12       0  5003.1     .05       0
  5028.2     .12       0  5080.6     .07       0
Bank Sta=5003.1,5028.2
XS Rating Curve= 0 ,0
Exp/Cntr=0.3,0.1

Type RM Length L Ch R = 1 ,133292  ,551,551,551
BEGIN DESCRIPTION:
Dry Comal Creek 155.0
END DESCRIPTION:
XS GIS Cut Line= 3
      2199625.01     13815775.04        2199475.       13814975.
      2199324.99     13814374.95
#Sta/Elev= 30
  4191.7 1007.13  4196.8 1006.93    4263 1000.16  4334.2  989.45  4364.7  984.21
  4380.8     979  4385.9  978.89  4399.8  974.91  4456.3  961.48  4485.9  958.14
  4608.9  956.26    4764  956.51  4831.9  954.62  4874.3  950.35  4893.8  946.44
  4941.8  942.34  5016.3  940.37  5016.8  939.87  5041.5  940.37  5111.3  945.51
  5147.4  953.08  5160.3  954.31  5276.3  959.48  5317.5  962.91  5353.6  968.19
  5428.3  973.37  5459.2  979.53  5564.9  993.49  5582.9   997.1  5624.2  999.75
#Mann= 7 ,-1 , 0
  4191.7    .035       0  4196.8     .07       0  4399.8    .035       0
  4831.9     .12       0  4941.8     .07       0  5016.3     .05       0
  5041.5     .07       0
Bank Sta=5016.3,5041.5
XS Rating Curve= 0 ,0
Exp/Cntr=0.3,0.1

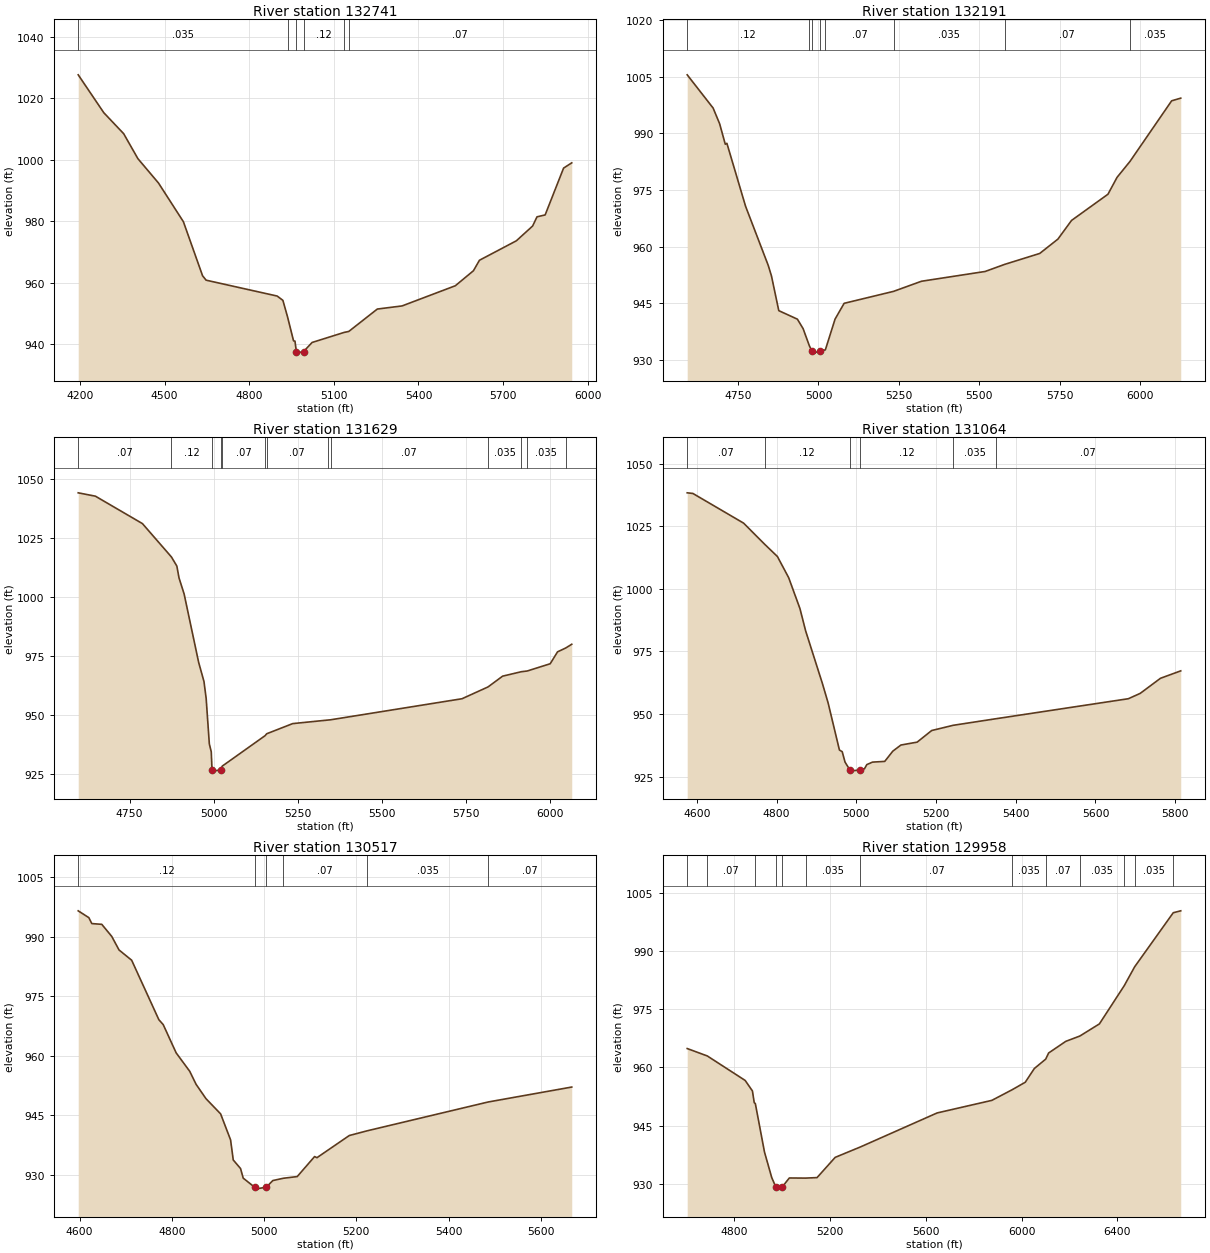
Type RM Length L Ch R = 1 ,132741  ,550,550,550
BEGIN DESCRIPTION:
Dry Comal Creek 154.0
END DESCRIPTION:
XS GIS Cut Line= 3
        2199875.     13815924.98        2199975.       13815125.
        2199475.     13814325.01
#Sta/Elev= 30
  4193.8 1027.54  4284.5 1015.22    4355 1008.39  4405.4 1000.28  4478.5  992.34
  4566.7  979.77  4634.7  962.19  4647.3  960.76  4899.2   955.6  4919.4   954.2
  4935.8  948.87  4957.2  941.03  4962.2  940.94  4967.2  937.54  4967.7  937.04
  4992.5  937.54    5023  940.51  5136.3  943.77    5153  944.09  5254.1  951.37
    5342  952.39  5530.7  958.95  5594.9  963.83  5616.2  967.24  5747.1  973.57
  5804.8  978.38  5820.2  981.36  5849.1  981.98  5914.5  997.21  5943.4  998.92
#Mann= 6 ,-1 , 0
  4193.8    .035       0  4935.8     .12       0  4967.2     .05       0
  4992.5     .12       0  5136.3    .035       0    5153     .07       0
Bank Sta=4967.2,4992.5
XS Rating Curve= 0 ,0
Exp/Cntr=0.3,0.1

Type RM Length L Ch R = 1 ,132191  ,562,562,562
BEGIN DESCRIPTION:
Dry Comal Creek 153.0
END DESCRIPTION:
XS GIS Cut Line= 3
      2200874.97       13815025.        2200475.       13814975.
      2199674.97     13814174.97
#Sta/Elev= 30
  4591.9  1005.5  4672.5  996.69  4692.7  992.54  4710.3   987.1  4715.3  987.35
  4773.3  970.68  4843.8     955  4853.9  952.19  4876.6     943  4934.5  940.74
  4952.2  938.24  4971.6  933.71  4979.7  932.24  4980.2  931.74  5005.2  932.24
  5021.4   932.6  5051.6  940.75  5079.8  944.94  5233.5  948.11  5320.3  950.79
  5518.2  953.38  5578.9  955.26    5688  958.16  5744.5  961.96  5786.9  966.91
  5900.1  973.85  5928.4  978.33  5968.5  982.54  6098.1  998.61  6126.4  999.32
#Mann= 8 ,-1 , 0
  4591.9     .12       0  4971.6    .035       0  4979.7    .035       0
  5005.2    .035       0  5021.4     .07       0  5233.5    .035       0
  5578.9     .07       0  5968.5    .035       0
Bank Sta=4979.7,5005.2
XS Rating Curve= 0 ,0
Exp/Cntr=0.3,0.1

Type RM Length L Ch R = 1 ,131629  ,565,565,565
BEGIN DESCRIPTION:
Dry Comal Creek 152.0
END DESCRIPTION:
XS GIS Cut Line= 3
      2201175.02     13814775.01        2200825.       13814575.
      2200025.04     13813875.03
#Sta/Elev= 30
  4597.2 1043.98  4648.3 1042.56    4788 1030.95  4874.1 1016.82  4890.2 1012.98
  4896.7 1007.92  4911.8 1001.16    4955  972.17  4970.8  964.09  4977.3  956.88
  4986.7  937.67  4992.4  934.34  4994.7  926.64  4995.2  926.14  5020.2  926.64
  5025.1  928.26  5152.6  941.18  5157.1  941.96  5234.3  946.26  5338.5  947.76
  5346.7  947.87  5737.3  956.79  5814.5  961.78  5857.9  966.35  5913.8  968.24
  5930.9  968.53  5999.3  971.61  6021.1  976.65  6045.3  978.27  6063.3  979.86
#Mann= 13 ,-1 , 0
  4597.2     .07       0  4874.1     .12       0  4994.7     .05       0
  5020.2     .12       0  5025.1     .07       0  5152.6    .035       0
  5157.1     .07       0  5338.5    .035       0  5346.7     .07       0
  5814.5    .035       0  5913.8     .07       0  5930.9    .035       0
  6045.3     .07       0
Bank Sta=4994.7,5020.2
XS Rating Curve= 0 ,0
Exp/Cntr=0.3,0.1

Type RM Length L Ch R = 1 ,131064  ,547,547,547
BEGIN DESCRIPTION:
Dry Comal Creek 151.0
END DESCRIPTION:
XS GIS Cut Line= 3
      2201275.03     13814375.03        2200975.       13814075.
      2200175.04     13813925.01
#Sta/Elev= 30
  4575.7  1038.4  4589.9 1038.15  4717.2 1026.29  4770.5 1017.77    4802 1012.95
  4830.3 1004.48  4858.6  992.11  4872.7   983.3  4915.1  962.09  4929.3  954.39
  4957.6  935.61  4964.6  934.93  4971.7  930.77  4983.7  927.67  4984.2  927.17
  5009.2  927.67  5020.3  928.07  5026.3  929.78  5040.7  930.78  5071.2  931.05
  5091.6  935.16  5111.9   937.6  5152.6  938.76  5189.1   943.4  5243.2  945.49
  5349.9   948.1  5682.5  956.11  5712.2  958.24  5763.1  964.28  5813.9  967.24
#Mann= 6 ,-1 , 0
  4575.7     .07       0  4770.5     .12       0  4983.7     .05       0
  5009.2     .12       0  5243.2    .035       0  5349.9     .07       0
Bank Sta=4983.7,5009.2
XS Rating Curve= 0 ,0
Exp/Cntr=0.3,0.1

Type RM Length L Ch R = 1 ,130517  ,559,559,559
BEGIN DESCRIPTION:
Dry Comal Creek 150.0
END DESCRIPTION:
XS GIS Cut Line= 3
        2201325.       13813925.        2201125.       13813575.
      2200474.99       13813725.
#Sta/Elev= 30
  4596.9  996.58  4619.9  994.86  4626.4  993.36    4648  993.17  4669.6  990.12
  4685.4   986.7  4712.8  984.11  4771.8  969.09  4781.2  967.86  4809.3  960.72
  4838.8  956.05  4852.4   952.8    4874  949.15  4905.7  945.32  4927.3  938.75
  4933.1  933.68  4948.9  931.52  4954.7  929.09  4979.3  926.82  4979.8  926.32
  5004.9  926.82  5018.8  928.48  5041.5  929.06  5071.8  929.49  5109.5  934.54
  5114.6  934.26  5184.7  939.85  5222.7  941.02  5485.9  948.32  5667.1  952.09
#Mann= 6 ,-1 , 0
  4596.9     .12       0  4979.3     .05       0  5004.9     .12       0
  5041.5     .07       0  5222.7    .035       0  5485.9     .07       0
Bank Sta=4979.3,5004.9
XS Rating Curve= 0 ,0
Exp/Cntr=0.3,0.1

Type RM Length L Ch R = 1 ,129958  ,545,545,545
BEGIN DESCRIPTION:
Dry Comal Creek 149.0
END DESCRIPTION:
XS GIS Cut Line= 3
      2201625.01       13813025.        2201225.       13813075.
      2199774.97     13813875.02
#Sta/Elev= 30
  4604.9  964.87  4688.7  962.96  4846.8  956.65    4877  953.95  4884.6  950.91
  4889.1  950.71  4927.4   938.2  4957.6  931.63    4975  929.16  4975.5  928.66
  5000.7  929.16  5030.9  931.53    5099   931.5  5146.7  931.63  5222.3  936.84
  5327.8  939.53  5647.6  948.28    5876  951.52    5961  954.27  6015.4  956.19
  6053.2  959.72  6100.8  962.15  6112.8  963.72  6184.4  966.72  6243.1  968.09
  6324.8  971.22  6428.3  981.05  6471.9  985.93  6632.9  999.85  6664.1 1000.34
#Mann= 13 ,-1 , 0
  4604.9    .035       0  4688.7     .07       0  4889.1     .12       0
    4975     .05       0  5000.7     .12       0    5099    .035       0
  5327.8     .07       0    5961    .035       0  6100.8     .07       0
  6243.1    .035       0  6428.3     .07       0  6471.9    .035       0
  6632.9     .07       0
Bank Sta=4975,5000.7
XS Rating Curve= 0 ,0
Exp/Cntr=0.3,0.1

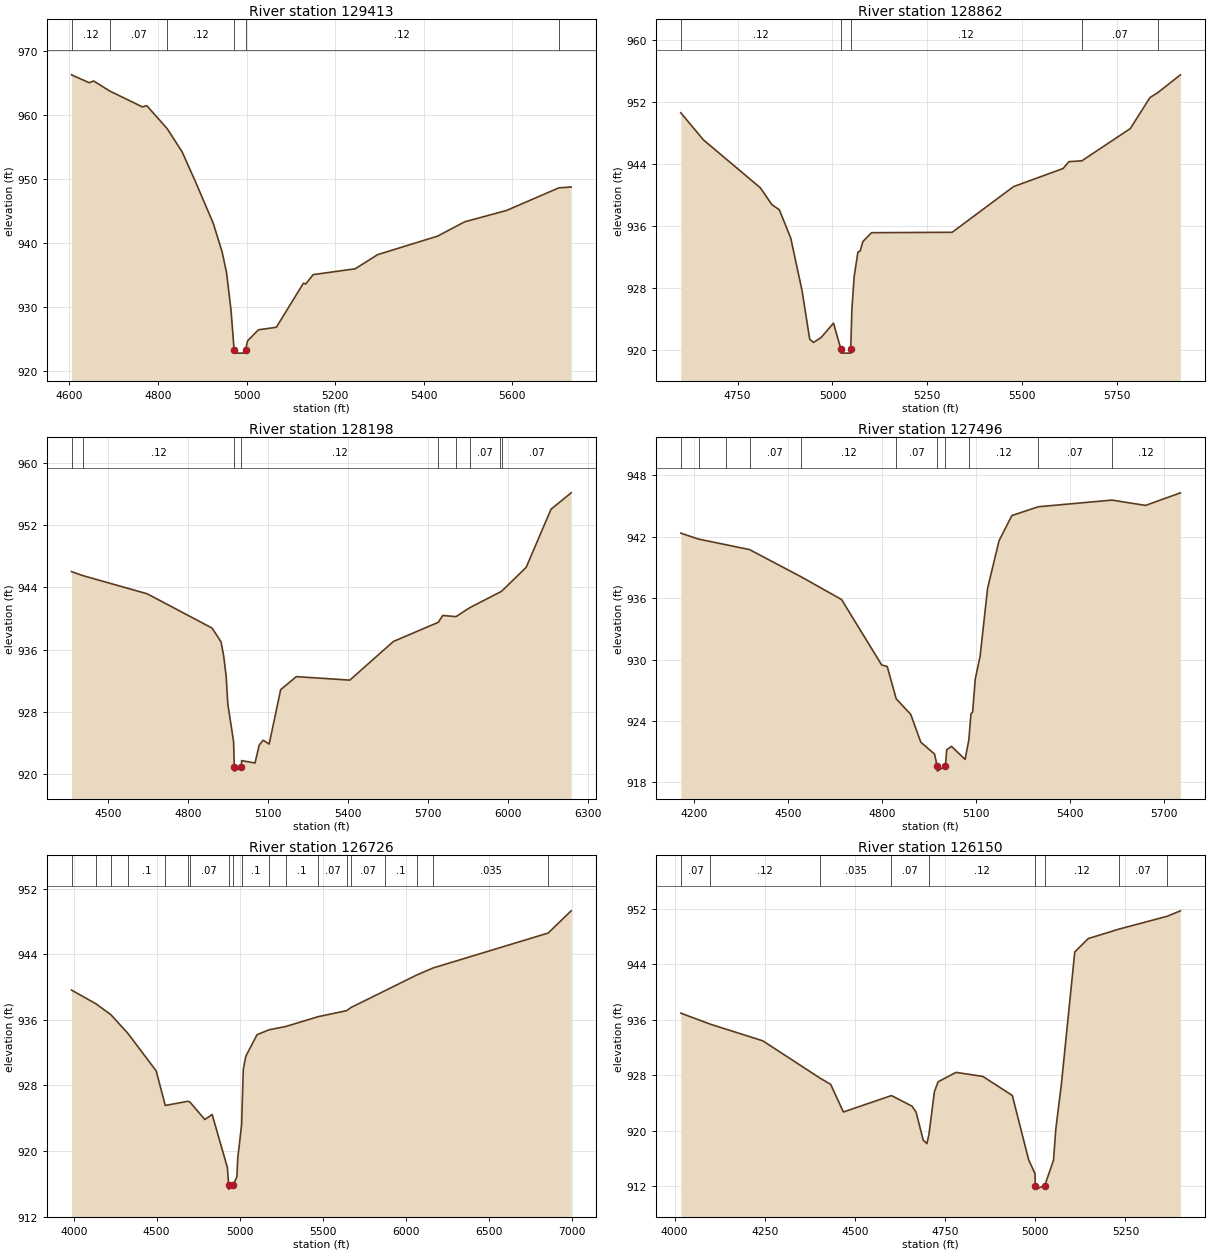
Type RM Length L Ch R = 1 ,129413  ,551,551,551
BEGIN DESCRIPTION:
Dry Comal Creek 148.0
END DESCRIPTION:
XS GIS Cut Line= 3
      2201574.96       13812575.        2201175.       13812575.
      2200474.97     13812775.01
#Sta/Elev= 30
  4604.7  966.24  4644.7  965.01  4654.7  965.28  4691.2  963.71  4764.7  961.24
  4774.7  961.43  4820.9  957.83  4854.7  954.19  4884.7  949.55  4924.7  943.09
  4944.7  938.63  4954.7   935.4  4964.7   929.6  4971.8  923.35  4972.3  922.85
    4997  922.85  4997.5  923.35  5002.2  924.77  5026.8  926.49  5067.1  926.88
  5128.2  933.75  5133.4  933.63  5150.3  935.09  5245.2     936  5295.9  938.21
  5431.1  941.09  5492.2  943.32  5587.1   945.1  5704.9  948.62  5732.7  948.75
#Mann= 6 ,-1 , 0
  4604.7     .12       0  4691.2     .07       0  4820.9     .12       0
  4971.8     .05       0  4997.5     .12       0  5704.9     .07       0
Bank Sta=4971.8,4997.5
XS Rating Curve= 0 ,0
Exp/Cntr=0.3,0.1

Type RM Length L Ch R = 1 ,128862  ,664,664,664
BEGIN DESCRIPTION:
Dry Comal Creek 147.0
END DESCRIPTION:
XS GIS Cut Line= 3
      2201424.97       13812075.        2201025.       13812075.
      2200225.04     13812524.98
#Sta/Elev= 30
    4600  950.61    4660   947.1    4810  940.92    4840  938.77    4860  938.08
    4890  934.44    4920  927.61    4940  921.38    4950  920.96    4970  921.59
  5002.8  923.45  5022.4  920.08  5022.9  919.58  5047.7  919.58  5048.2  920.08
  5051.3  925.26  5057.3  929.47  5067.2  932.63    5073  932.75  5080.3  933.99
  5103.2  935.13  5315.8  935.18  5477.7  941.08  5608.1  943.41  5623.7   944.3
  5657.8  944.41  5785.6  948.57  5837.5  952.58  5857.6  953.19  5917.8  955.51
#Mann= 5 ,-1 , 0
    4600     .12       0  5022.4     .05       0  5048.2     .12       0
  5657.8     .07       0  5857.6     .12       0
Bank Sta=5022.4,5048.2
XS Rating Curve= 0 ,0
Exp/Cntr=0.3,0.1

Type RM Length L Ch R = 1 ,128198  ,702,702,702
BEGIN DESCRIPTION:
X18970
END DESCRIPTION:
XS GIS Cut Line= 4
      2201523.66     13811683.91      2201013.71     13811456.06
      2200731.59     13811618.82        2200124.       13812400.
#Sta/Elev= 30
  4363.1  946.03  4405.9  945.51  4647.1  943.18  4890.2  938.78  4923.8  937.02
  4933.5  935.26  4943.2  932.56  4949.3  929.01  4970.8  924.25  4973.7  920.92
  4974.2  920.42  4999.5  920.92    5001  921.77  5051.3  921.46    5067  923.76
  5081.8  924.39  5104.4  923.89  5147.5  930.88  5206.3  932.55  5406.8   932.1
  5570.6  937.07  5738.7  939.52  5755.2   940.4    5805  940.25  5856.2  941.39
  5971.9  943.43  5978.1  943.57  6068.3  946.58  6161.5  954.04    6237  956.14
#Mann= 9 ,-1 , 0
  4363.1     .07       0  4405.9     .12       0  4973.7     .05       0
  4999.5     .12       0  5738.7     .07       0    5805     .12       0
  5856.2     .07       0  5971.9     .12       0  5978.1     .07       0
Bank Sta=4973.7,4999.5
XS Rating Curve= 0 ,0
Exp/Cntr=0.3,0.1

Type RM Length L Ch R = 1 ,127496  ,770,770,770
BEGIN DESCRIPTION:
X18969
END DESCRIPTION:
XS GIS Cut Line= 3
      2201328.36     13811456.02      2200948.61     13810924.37
      2200080.51     13810566.28
#Sta/Elev= 30
  4158.9  942.35  4215.7  941.77  4302.9  941.22  4378.3  940.74  4540.9  938.11
  4671.2  935.87  4799.2  929.47  4816.9  929.32  4845.4  926.17  4891.9  924.64
  4923.8  921.93  4967.6  920.77  4976.1   919.6  4976.6   919.1  5002.3   919.6
  5006.4  921.19  5021.7  921.52    5065  920.25  5077.1  922.18  5083.6  924.69
    5089  924.87  5097.4  928.09  5112.9  930.34  5136.8  936.97  5173.1   941.6
    5214  944.07  5298.7  944.93  5532.8  945.58  5640.2  945.06  5751.3  946.29
#Mann= 11 ,-1 , 0
  4158.9     .12       0  4215.7     .07       0  4302.9     .12       0
  4378.3     .07       0  4540.9     .12       0  4845.4     .07       0
  4976.1     .05       0  5002.3     .07       0  5077.1     .12       0
  5298.7     .07       0  5532.8     .12       0
Bank Sta=4976.1,5002.3
XS Rating Curve= 0 ,0
Exp/Cntr=0.3,0.1

Type RM Length L Ch R = 1 ,126726  ,576,576,576
BEGIN DESCRIPTION:
Dry Comal Creek 146.0
END DESCRIPTION:
XS GIS Cut Line= 4
      2201187.33     13811173.96        2200975.       13810175.
       2200935.9     13810109.95      2199023.72     13810184.35
#Sta/Elev= 30
  3986.9  939.63  4134.6  937.95    4224  936.63  4325.3  934.38    4497  929.78
  4551.8  925.56  4687.8  926.07  4698.6  926.01  4790.1  923.85  4834.4  924.46
  4926.4  917.97  4933.7  915.86  4934.2  915.36  4959.9  915.86  4983.4  916.85
  4988.5  919.12  5011.8  923.21  5021.8  929.96  5037.3  931.57    5105  934.19
  5178.1  934.79  5276.8  935.18  5474.2  936.39  5645.1  937.12  5671.6  937.51
    5877  939.56  6066.4  941.46  6165.1  942.32  6858.9  946.58  6997.7  949.29
#Mann= 19 ,-1 , 0
  3986.9     .07       0  4134.6    .035       0    4224     .07       0
  4325.3      .1       0  4551.8     .07       0  4687.8      .1       0
  4698.6     .07       0  4933.7     .05       0  4959.9     .07       0
  5011.8      .1       0  5178.1     .07       0  5276.8      .1       0
  5474.2     .07       0  5645.1      .1       0  5671.6     .07       0
    5877      .1       0  6066.4     .07       0  6165.1    .035       0
  6858.9     .07       0
Bank Sta=4933.7,4959.9
XS Rating Curve= 0 ,0
Exp/Cntr=0.3,0.1

Type RM Length L Ch R = 1 ,126150  ,552,552,552
BEGIN DESCRIPTION:
Dry Comal Creek 145.0
END DESCRIPTION:
XS GIS Cut Line= 3
      2201174.99     13810925.05        2201425.       13809975.
        2201625.       13809625.
#Sta/Elev= 30
  4017.1  936.96  4099.5  935.36  4244.6  932.97  4402.4  927.62  4432.8  926.69
    4468  922.71  4601.3  925.08  4658.3  923.55  4669.6   922.7  4689.3  918.67
  4699.6  918.15  4705.3  919.49  4720.3  925.62  4730.6  927.06  4780.3  928.42
  4854.7  927.84  4936.4  925.09  4981.9  915.79  4999.5  913.82  5000.1  912.09
  5000.6  911.59  5026.3  912.09  5050.6  915.75  5057.1  920.29  5072.2  926.57
  5109.6  945.78  5147.1  947.71  5231.9  949.07  5366.2  950.93  5402.6  951.71
#Mann= 9 ,-1 , 0
  4017.1     .07       0  4099.5     .12       0  4402.4    .035       0
  4601.3     .07       0  4705.3     .12       0  5000.1     .05       0
  5026.3     .12       0  5231.9     .07       0  5366.2    .035       0
Bank Sta=5000.1,5026.3
XS Rating Curve= 0 ,0
Exp/Cntr=0.3,0.1

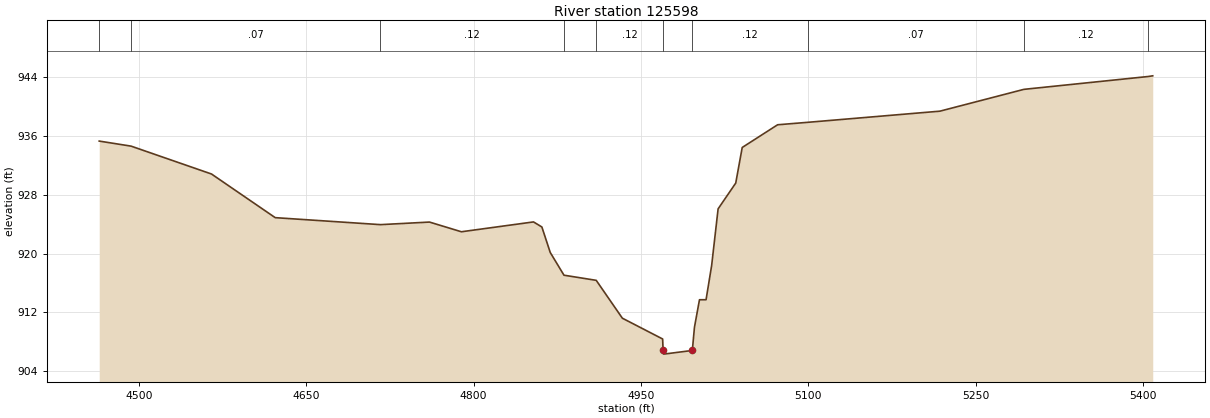
Type RM Length L Ch R = 1 ,125598  ,569,569,569
BEGIN DESCRIPTION:
Dry Comal Creek 144.0
END DESCRIPTION:
XS GIS Cut Line= 3
      2201375.01     13810874.98        2201675.       13810425.
      2201874.99     13810075.02
#Sta/Elev= 30
  4464.6  935.32  4493.2  934.63  4565.2  930.84  4622.3   924.9  4716.6  923.95
  4760.5   924.3  4789.1  922.98  4853.7  924.32  4861.2  923.63  4868.7  920.16
    4881  917.07  4909.9  916.37  4933.3  911.22  4969.4  908.39  4969.8  906.83
  4970.3  906.33    4996  906.83  4997.9  909.98  5002.4  913.73  5008.3  913.73
  5013.3  918.38  5019.1   926.1  5034.9  929.61  5040.7  934.45  5072.4  937.54
  5099.2  937.87  5217.8  939.39  5293.1  942.36  5404.6  944.11  5408.5   944.2
#Mann= 10 ,-1 , 0
  4464.6    .035       0  4493.2     .07       0  4716.6     .12       0
    4881     .07       0  4909.9     .12       0  4969.8     .05       0
    4996     .12       0  5099.2     .07       0  5293.1     .12       0
  5404.6     .07       0
Bank Sta=4969.8,4996
XS Rating Curve= 0 ,0
Exp/Cntr=0.3,0.1