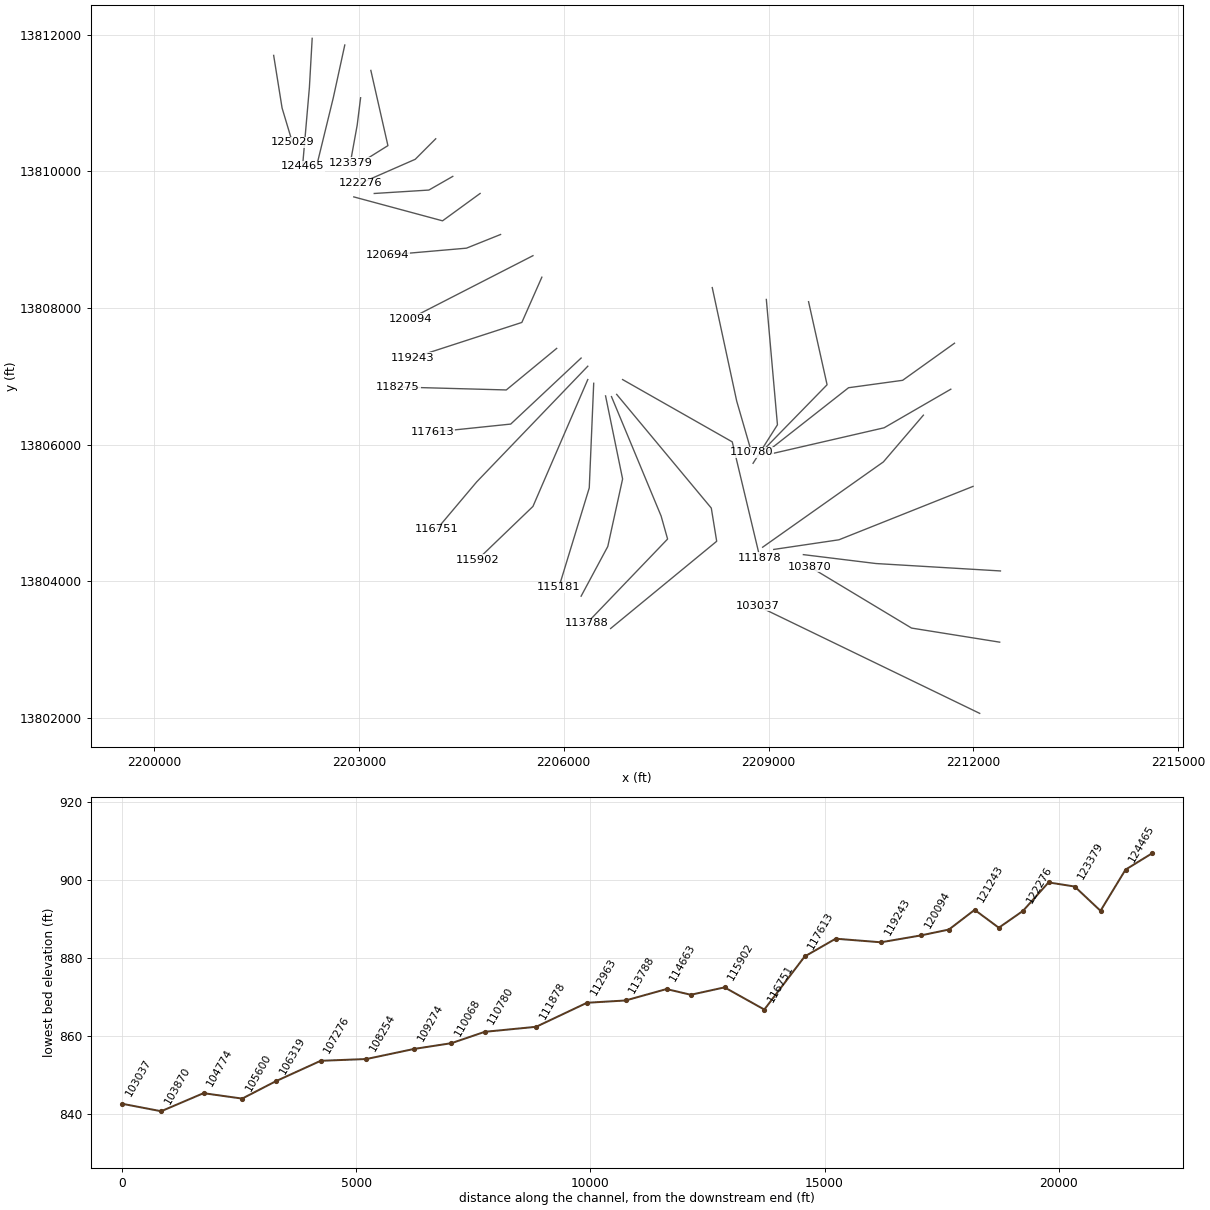
HEC-RAS study Dry Comal Creek.prj: Dry Comal Creek Base Level Engineering

--- Dry Comal Creek.g01 (geometry) --- (continued)

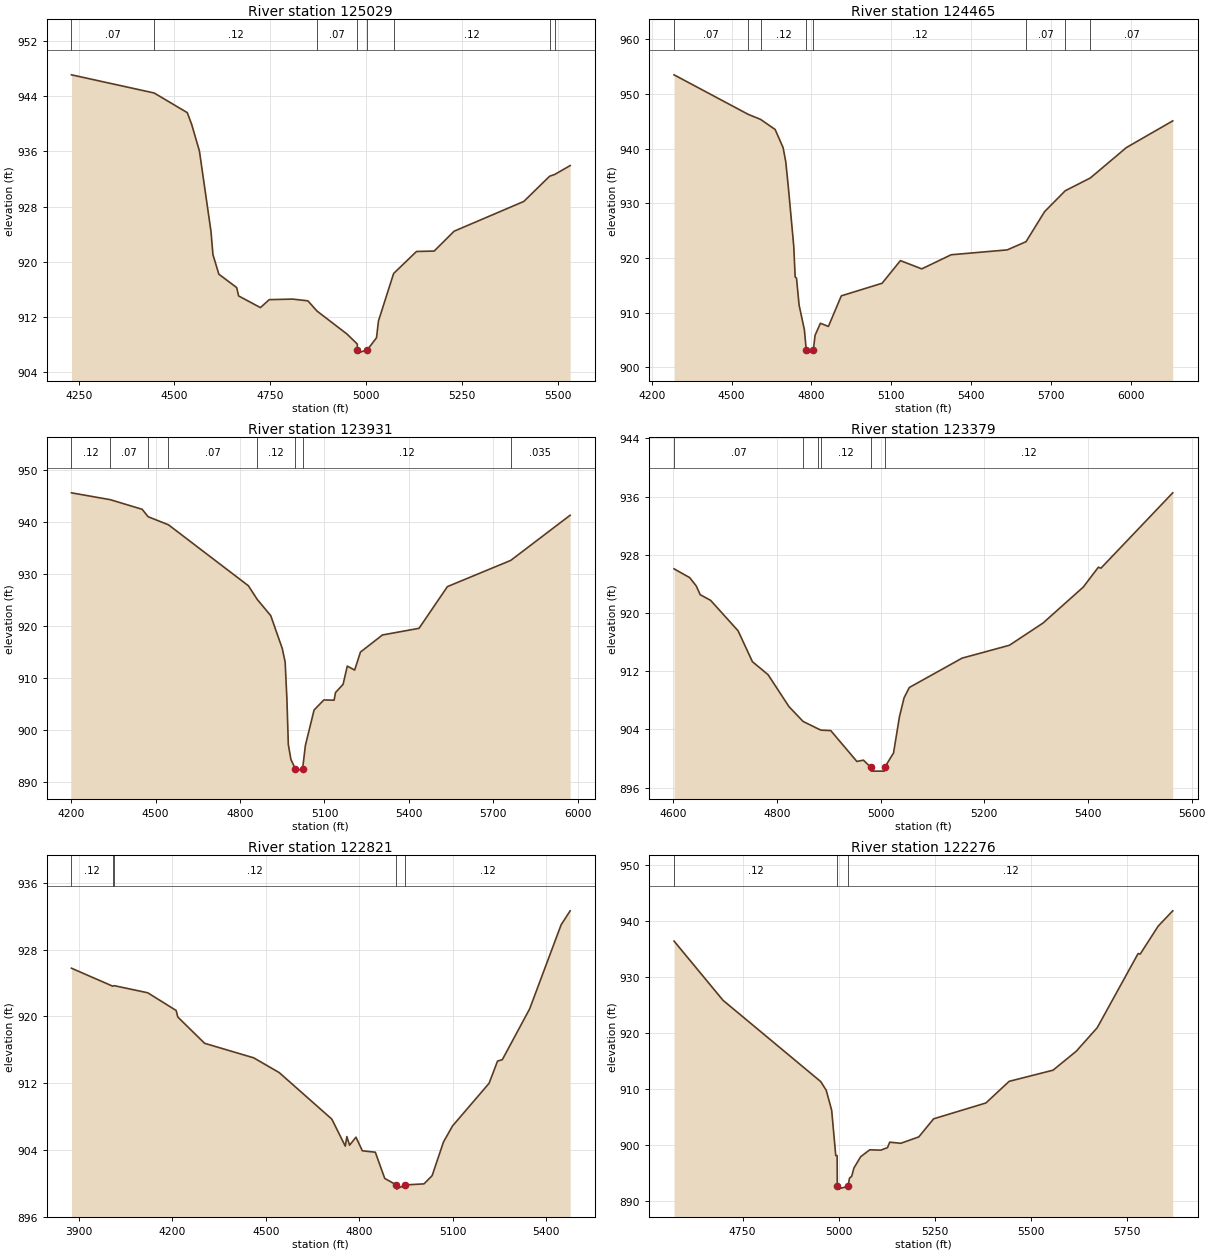
Type RM Length L Ch R = 1 ,125029  ,564,564,564
BEGIN DESCRIPTION:
Dry Comal Creek 143.0
END DESCRIPTION:
XS GIS Cut Line= 3
      2201751.55     13811694.81        2201875.       13810925.
      2202025.01     13810424.96
#Sta/Elev= 30
  4231.2   947.1    4447  944.47  4533.5  941.62    4545  939.91  4565.2  936.06
  4595.4   924.4  4600.5  921.05  4615.9  918.21  4662.5  916.27  4667.5  915.06
  4724.4  913.37  4747.5  914.52  4808.3   914.6  4848.3  914.35  4872.1  912.87
  4950.1  909.55  4977.3  908.09  4977.5  907.27    4978  906.77  5003.7  907.27
  5027.4  908.99  5032.6  911.44  5072.1  918.31  5131.8   921.5  5177.9  921.56
  5230.1  924.44  5411.9  928.75  5479.4  932.41  5492.6  932.66  5532.9  933.95
#Mann= 8 ,-1 , 0
  4231.2     .07       0    4447     .12       0  4872.1     .07       0
  4977.5     .05       0  5003.7     .07       0  5072.1     .12       0
  5479.4     .07       0  5492.6     .12       0
Bank Sta=4977.5,5003.7
XS Rating Curve= 0 ,0
Exp/Cntr=0.3,0.1

Type RM Length L Ch R = 1 ,124465  ,534,534,534
BEGIN DESCRIPTION:
Dry Comal Creek 142.0
END DESCRIPTION:
XS GIS Cut Line= 3
      2202315.79     13811944.35        2202275.       13811225.
        2202175.     13810075.04
#Sta/Elev= 30
  4283.9  953.47  4562.8  946.24    4609  945.33  4663.9  943.48  4693.9  940.16
  4703.9  937.56  4713.9  932.76    4734  922.08  4739.2  916.52  4744.2  916.32
    4754  911.38    4774  906.83    4781   903.1  4781.5   902.6  4807.2   903.1
  4814.1  905.86  4834.1  908.06  4864.2  907.48  4912.7  913.07  5065.9  915.37
  5134.9  919.51  5215.2     918  5325.6  920.58  5536.4  921.47  5607.1  922.97
  5676.9  928.46  5754.5  932.28    5849  934.62  5984.3  940.17  6158.7  945.05
#Mann= 8 ,-1 , 0
  4283.9     .07       0  4562.8    .035       0    4609     .12       0
    4781     .05       0  4807.2     .12       0  5607.1     .07       0
  5754.5     .12       0    5849     .07       0
Bank Sta=4781,4807.2
XS Rating Curve= 0 ,0
Exp/Cntr=0.3,0.1

Type RM Length L Ch R = 1 ,123931  ,552,552,552
BEGIN DESCRIPTION:
Dry Comal Creek 141.0
END DESCRIPTION:
XS GIS Cut Line= 3
      2202793.23     13811846.72        2202625.       13811075.
      2202391.76     13810121.45
#Sta/Elev= 30
  4201.2  945.58  4339.2  944.26  4452.4  942.41  4473.6  940.98  4545.8  939.43
  4829.6  927.71  4861.4  925.06  4909.2  921.95  4950.1  915.62  4960.3  913.03
  4966.5  905.99  4971.6  897.15  4980.8  894.29  4996.1  892.55  4996.6  892.05
  5022.4  892.55  5032.2     897  5063.1  903.81  5097.7  905.74  5134.2   905.7
  5139.3  907.17  5166.1  908.75    5181  912.25  5207.2  911.49  5227.8  914.95
  5305.9  918.24  5435.9  919.52  5536.7  927.54  5761.6  932.58  5972.7  941.27
#Mann= 8 ,-1 , 0
  4201.2     .12       0  4339.2     .07       0  4473.6     .12       0
  4545.8     .07       0  4861.4     .12       0  4996.1     .05       0
  5022.4     .12       0  5761.6    .035       0
Bank Sta=4996.1,5022.4
XS Rating Curve= 0 ,0
Exp/Cntr=0.3,0.1

Type RM Length L Ch R = 1 ,123379  ,558,558,558
BEGIN DESCRIPTION:
Dry Comal Creek 140.0
END DESCRIPTION:
XS GIS Cut Line= 3
        2203025.       13811075.        2202975.       13810675.
      2202875.01     13810125.03
#Sta/Elev= 30
  4601.4  926.07  4631.6  924.86  4644.2  923.72  4651.8  922.52  4671.9  921.74
  4724.9  917.56  4752.6  913.31  4782.8  911.53  4823.1  907.14  4850.3  905.11
  4878.5  904.12  4884.9  903.91  4903.7  903.85  4954.1  899.61  4966.7  899.79
  4981.3  898.78  4981.8  898.28  5007.1  898.28  5007.6  898.78  5024.8  900.77
  5036.3  905.77  5045.2  908.36  5055.3  909.77    5157   913.8  5248.4  915.57
  5313.2  918.62  5390.7  923.55    5420  926.29    5425  926.16  5563.5  936.51
#Mann= 6 ,-1 , 0
  4601.4     .07       0  4850.3     .12       0  4878.5     .07       0
  4884.9     .12       0  4981.3     .05       0  5007.6     .12       0
Bank Sta=4981.3,5007.6
XS Rating Curve= 0 ,0
Exp/Cntr=0.3,0.1

Type RM Length L Ch R = 1 ,122821  ,545,545,545
BEGIN DESCRIPTION:
Dry Comal Creek 139.0
END DESCRIPTION:
XS GIS Cut Line= 3
        2203175.     13811475.01        2203425.       13810375.
      2203024.97     13810124.98
#Sta/Elev= 30
  3876.8  925.78    4009  923.63  4013.9  923.69  4121.4  922.84  4212.7  920.72
  4217.8  919.94  4303.9  916.79  4461.4  915.05  4543.4  913.28  4712.1  907.71
  4755.2  904.48  4760.3  905.62    4769  904.59  4789.5  905.55    4810  903.92
  4851.6  903.75  4881.8  900.61  4919.4  899.83  4919.9  899.33  4945.8  899.83
  5007.8  899.96  5033.8  900.94  5070.3  904.98  5099.2  906.89  5216.5     912
  5243.7  914.66    5259  914.83  5346.8  920.92  5447.7  930.98  5476.6  932.65
#Mann= 5 ,-1 , 0
  3876.8     .12       0    4009    .035       0  4013.9     .12       0
  4919.4     .05       0  4945.8     .12       0
Bank Sta=4919.4,4945.8
XS Rating Curve= 0 ,0
Exp/Cntr=0.3,0.1

Type RM Length L Ch R = 1 ,122276  ,517,517,517
BEGIN DESCRIPTION:
Dry Comal Creek 138.0
END DESCRIPTION:
XS GIS Cut Line= 3
        2204125.       13810475.        2203825.       13810175.
      2203024.98     13809824.99
#Sta/Elev= 30
  4571.8  936.46  4699.1  925.86  4953.6  911.29  4967.8  909.73  4981.9  906.17
  4992.5  898.05  4996.1  898.05  4996.5  892.54    4997  892.04  5024.4  892.54
  5028.4  894.03  5033.9  894.33  5039.7  895.81  5057.3  897.84  5080.7  899.08
  5109.5  899.02  5127.1  899.47  5132.9  900.45  5161.7  900.25  5208.5  901.39
  5247.1  904.63  5383.2  907.47  5443.6  911.34  5557.8  913.34  5618.2  916.73
  5672.8  920.95  5779.2  934.23  5784.7  934.14  5831.5  939.15  5869.3  941.88
#Mann= 3 ,-1 , 0
  4571.8     .12       0  4996.5     .05       0  5024.4     .12       0
Bank Sta=4996.5,5024.4
XS Rating Curve= 0 ,0
Exp/Cntr=0.3,0.1

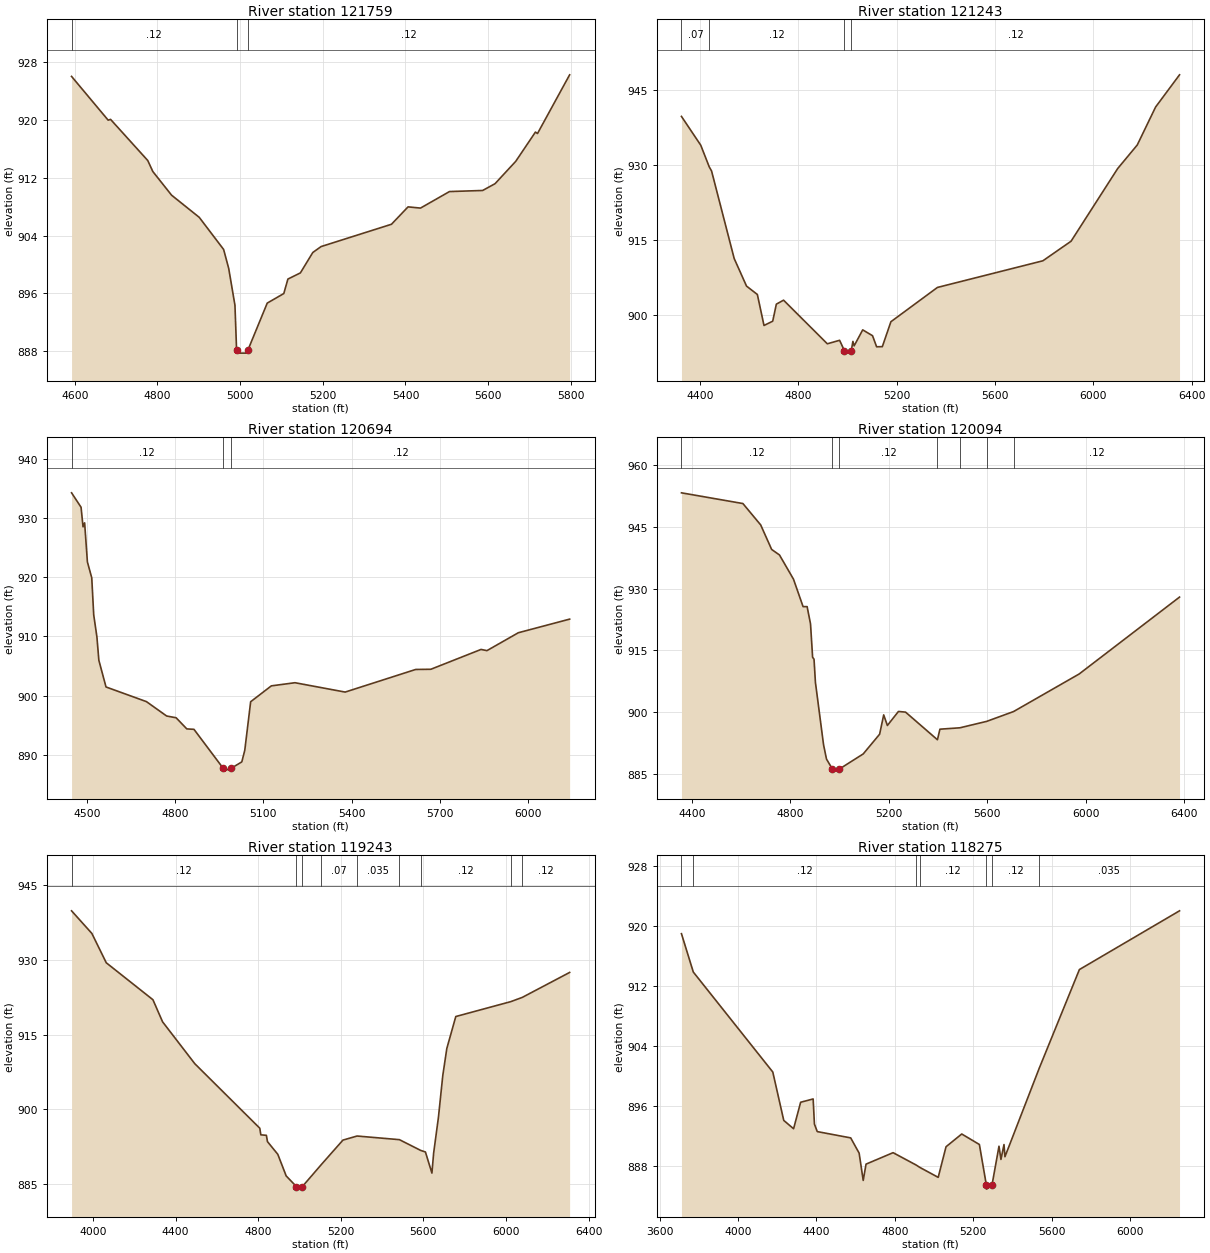
Type RM Length L Ch R = 1 ,121759  ,516,516,516
BEGIN DESCRIPTION:
Dry Comal Creek 137.0
END DESCRIPTION:
XS GIS Cut Line= 3
        2204375.       13809925.        2204025.       13809725.
      2203224.98       13809675.
#Sta/Elev= 30
  4592.4  926.04  4680.9  919.98  4686.7  920.09  4776.7  914.39  4788.9  912.87
  4834.3  909.59  4901.2  906.52  4960.2  902.07  4972.5  899.44  4987.6  894.34
  4991.5  888.21    4992  887.71    5019  887.71  5019.5  888.21  5065.7  894.64
  5105.7  895.96  5115.7  897.97  5145.8  898.82  5175.9  901.65  5195.9  902.47
  5366.2  905.56  5406.3  907.97  5436.4   907.8  5506.5  910.09  5586.7  910.24
  5616.7  911.18  5666.8  914.28  5714.4  918.33  5719.4  918.13  5797.1  926.26
#Mann= 3 ,-1 , 0
  4592.4     .12       0  4991.5     .05       0  5019.5     .12       0
Bank Sta=4991.5,5019.5
XS Rating Curve= 0 ,0
Exp/Cntr=0.3,0.1

Type RM Length L Ch R = 1 ,121243  ,549,549,549
BEGIN DESCRIPTION:
Dry Comal Creek 136.0
END DESCRIPTION:
XS GIS Cut Line= 3
      2204775.01     13809675.01        2204225.       13809275.
      2202924.98     13809625.01
#Sta/Elev= 30
  4324.4  939.73  4402.9  933.96  4437.3  929.63  4446.9  928.79  4538.9  911.26
  4589.1  905.73  4633.2  904.05  4660.2  897.84  4695.7   898.7  4710.4  902.11
  4739.8  902.91  4917.9  894.17  4967.8  894.87  4987.4   892.8  4987.9   892.3
  5015.4   892.8  5021.9  894.65    5027  893.76  5061.8  896.96  5101.8  895.79
  5118.4  893.57  5141.7   893.6  5176.5  898.59  5365.8  905.46  5794.9   910.8
  5909.5  914.72  6098.9  929.26  6178.8     934  6253.5  941.61  6350.8  948.06
#Mann= 4 ,-1 , 0
  4324.4     .07       0  4437.3     .12       0  4987.4     .05       0
  5015.4     .12       0
Bank Sta=4987.4,5015.4
XS Rating Curve= 0 ,0
Exp/Cntr=0.3,0.1

Type RM Length L Ch R = 1 ,120694  ,600,600,600
BEGIN DESCRIPTION:
Dry Comal Creek 135.0
END DESCRIPTION:
XS GIS Cut Line= 3
      2205074.96     13809074.98        2204575.       13808875.
      2203425.01       13808775.
#Sta/Elev= 30
  4448.1  934.25  4480.4  931.81  4487.1  928.51  4492.5  929.18  4501.9  922.58
  4516.7   919.9  4523.4  913.63  4534.2  909.93  4540.9  905.96  4565.2  901.46
  4702.5  898.99  4771.2  896.56  4803.5  896.26  4839.8  894.38  4864.1  894.31
  4963.1  887.75  4963.6  887.25  4991.2  887.75  5026.7  888.81  5036.8  890.77
  5056.8  898.97  5127.1  901.65  5207.4  902.18    5378   900.6  5617.7  904.42
  5669.1  904.45  5839.8   907.8  5859.9   907.6  5966.5  910.62  6140.9  912.92
#Mann= 3 ,-1 , 0
  4448.1     .12       0  4963.1     .05       0  4991.2     .12       0
Bank Sta=4963.1,4991.2
XS Rating Curve= 0 ,0
Exp/Cntr=0.3,0.1

Type RM Length L Ch R = 1 ,120094  ,851,851,851
BEGIN DESCRIPTION:
Dry Comal Creek 134.0
END DESCRIPTION:
XS GIS Cut Line= 3
      2205549.32     13808765.09      2205082.72     13808526.37
      2203749.01     13807843.25
#Sta/Elev= 30
    4358  953.24  4607.5  950.64  4679.8  945.45  4724.2  939.51    4756  938.17
    4813  932.29  4851.8  925.64  4868.3  925.64  4882.1  921.45  4890.6  913.36
  4896.3  912.89    4902  907.28    4935  892.14    4947  888.66    4971  886.24
  4971.5  885.74  4999.1  886.24  5096.1  889.91  5162.7  894.69  5179.3  899.38
  5194.2  896.81  5239.1  900.21  5268.1  900.05  5397.5  893.35  5407.6  895.91
  5488.8  896.25  5597.7  897.81  5706.7  900.19    5973   909.3  6380.6  927.95
#Mann= 7 ,-1 , 0
    4358     .12       0    4971     .05       0  4999.1     .12       0
  5397.5     .07       0  5488.8    .035       0  5597.7     .07       0
  5706.7     .12       0
Bank Sta=4971,4999.1
XS Rating Curve= 0 ,0
Exp/Cntr=0.3,0.1

Type RM Length L Ch R = 1 ,119243  ,968,968,968
BEGIN DESCRIPTION:
Dry Comal Creek 133.0
END DESCRIPTION:
XS GIS Cut Line= 3
      2205679.51     13808450.42      2205386.54     13807788.52
      2203780.63     13807267.68
#Sta/Elev= 30
    3896  939.85  3994.3  935.31  4064.1  929.42  4290.1     922  4336.7  917.57
  4492.8  909.16  4807.5  896.21  4812.7  894.88  4839.5  894.78  4844.7  893.52
  4894.8  890.97  4935.4  886.63  4985.3  884.48  4985.8  883.98  5013.4  884.48
  5106.2  888.94  5210.2  893.82  5278.7  894.64  5483.8  893.91  5586.4  891.76
  5609.7  891.44  5641.2   887.2  5649.4  891.17  5672.7  898.38  5693.8  906.78
  5713.3  912.21  5756.8  918.63  6023.2  921.62  6078.8  922.47  6308.1  927.48
#Mann= 9 ,-1 , 0
    3896     .12       0  4985.3     .05       0  5013.4     .12       0
  5106.2     .07       0  5278.7    .035       0  5483.8     .07       0
  5586.4     .12       0  6023.2     .07       0  6078.8     .12       0
Bank Sta=4985.3,5013.4
XS Rating Curve= 0 ,0
Exp/Cntr=0.3,0.1

Type RM Length L Ch R = 1 ,118275  ,662,662,662
BEGIN DESCRIPTION:
Dry Comal Creek 132.0
END DESCRIPTION:
XS GIS Cut Line= 3
      2205896.48     13807408.72      2205158.68     13806801.11
      2203574.47     13806844.51
#Sta/Elev= 30
  3711.3  918.95  3771.7  913.84  4177.2  900.51  4233.1  894.06  4283.2  892.95
  4319.2  896.48    4383  896.92  4389.5  893.58  4403.9  892.57  4574.6  891.73
  4617.6   889.7  4638.4  886.06  4652.8  888.23  4790.8  889.76  4908.6  888.11
  4926.2  887.81  5020.9  886.47  5060.9  890.55    5141  892.25    5231  890.85
  5266.9   885.4  5267.4   884.9  5295.1   885.4    5331  890.62    5341  888.86
  5356.5  890.84  5361.5  889.22  5535.9  900.99  5741.2  914.17  6251.9     922
#Mann= 7 ,-1 , 0
  3711.3    .035       0  3771.7     .12       0  4908.6    .035       0
  4926.2     .12       0  5266.9     .05       0  5295.1     .12       0
  5535.9    .035       0
Bank Sta=5266.9,5295.1
XS Rating Curve= 0 ,0
Exp/Cntr=0.3,0.1

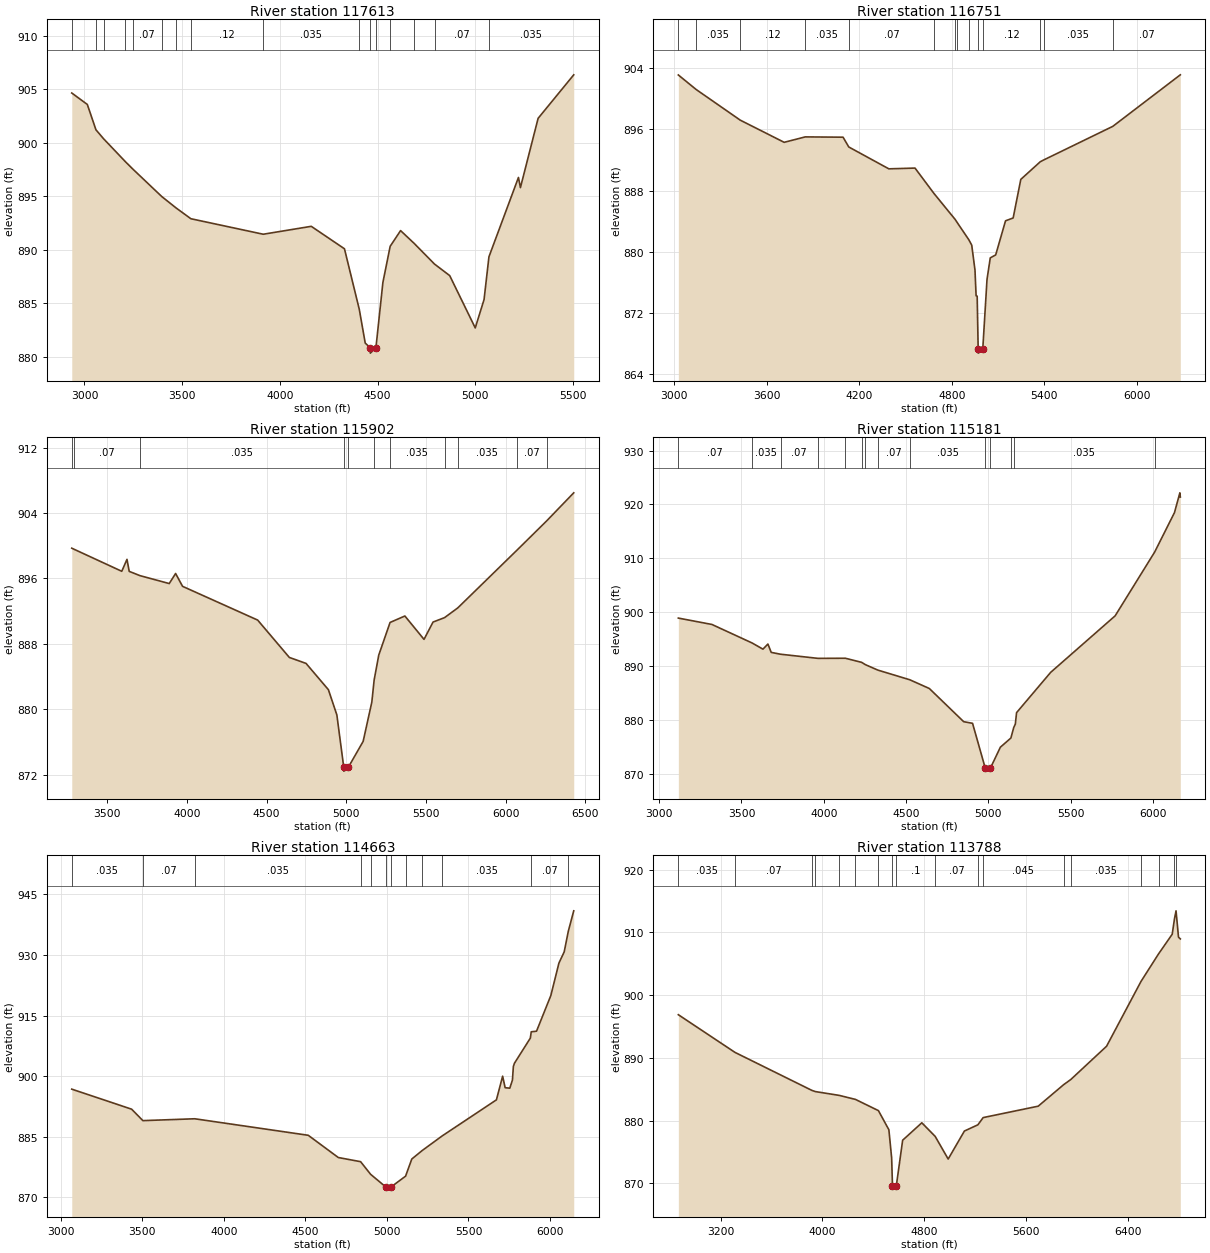
Type RM Length L Ch R = 1 ,117613  ,862,862,862
BEGIN DESCRIPTION:
X18968
END DESCRIPTION:
XS GIS Cut Line= 3
      2206254.59     13807267.68      2205223.78     13806301.98
      2204073.65     13806182.62
#Sta/Elev= 30
  2935.1  904.67  3014.7   903.6  3058.8  901.23  3098.5  900.38  3207.8  898.28
  3247.3  897.56    3396  894.98  3470.4   893.9  3544.7  892.91    3915  891.46
  4160.6   892.2  4330.6   890.1  4406.4  884.44  4436.9  881.28  4462.5  880.84
    4463  880.34  4491.6  880.84  4527.3  886.95  4564.5  890.33  4617.8   891.8
  4686.4  890.62  4791.4  888.67  4869.2  887.59  4999.9   882.7    5045  885.35
    5070  889.35    5221  896.77  5231.1  895.82  5321.6   902.3  5503.9  906.37
#Mann= 16 ,-1 , 0
  2935.1     .07       0  3058.8    .035       0  3098.5     .07       0
  3207.8    .035       0  3247.3     .07       0    3396    .035       0
  3470.4     .07       0  3544.7     .12       0    3915    .035       0
  4406.4     .12       0  4462.5     .05       0  4491.6     .12       0
  4564.5     .07       0  4686.4     .12       0  4791.4     .07       0
    5070    .035       0
Bank Sta=4462.5,4491.6
XS Rating Curve= 0 ,0
Exp/Cntr=0.3,0.1

Type RM Length L Ch R = 1 ,116751  ,849,849,849
BEGIN DESCRIPTION:
X18967
END DESCRIPTION:
XS GIS Cut Line= 3
      2206352.28     13807148.36      2204724.65     13805455.62
      2204139.37     13804761.96
#Sta/Elev= 30
    3026  903.12  3140.9  901.23  3427.6  897.21  3712.4  894.31  3849.4  895.02
  4094.4  894.98  4131.5   893.7  4391.3  890.84  4561.1  890.94  4684.1  887.62
  4821.9  884.21  4833.6  883.85  4909.9  881.57    4929  880.86  4950.1  877.59
  4957.3  874.24  4964.3  874.18  4970.8  867.23  4971.3  866.73  5000.5  867.23
  5028.1  876.37  5049.2  879.19  5084.4  879.58  5148.2  884.04  5197.6  884.41
  5247.3  889.46  5373.1  891.76  5394.6  891.99  5844.1   896.4  6281.9  903.14
#Mann= 14 ,-1 , 0
    3026     .07       0  3140.9    .035       0  3427.6     .12       0
  3849.4    .035       0  4131.5     .07       0  4684.1    .035       0
  4821.9     .12       0  4833.6    .035       0  4909.9     .12       0
  4970.8     .05       0  5000.5     .12       0  5373.1     .07       0
  5394.6    .035       0  5844.1     .07       0
Bank Sta=4970.8,5000.5
XS Rating Curve= 0 ,0
Exp/Cntr=0.3,0.1

Type RM Length L Ch R = 1 ,115902  ,721,721,721
BEGIN DESCRIPTION:
X18966
END DESCRIPTION:
XS GIS Cut Line= 3
      2206352.24     13806952.99       2205549.3     13805097.55
      2204735.52     13804316.32
#Sta/Elev= 30
  3277.8   899.7  3293.9  899.55  3591.6  896.87  3624.3  898.33  3638.3  896.86
  3705.4  896.34  3889.5  895.37  3929.4   896.6    3973  895.03  4444.3   890.9
  4643.1  886.33  4747.9   885.6  4888.3  882.38  4941.3  879.29  4984.3  872.92
  4984.8  872.42    5014  872.92  5106.2  876.06  5160.7  880.87  5175.2  883.57
  5204.2  886.62  5275.2  890.61    5368   891.4  5488.2  888.54  5544.8  890.66
    5617   891.2    5700  892.39  6071.7  899.46  6257.4  903.03  6427.6  906.47
#Mann= 11 ,-1 , 0
  3277.8    .035       0  3293.9     .07       0  3705.4    .035       0
  4984.3    .035       0    5014    .035       0  5175.2     .12       0
  5275.2    .035       0    5617     .07       0    5700    .035       0
  6071.7     .07       0  6257.4     .12       0
Bank Sta=4984.3,5014
XS Rating Curve= 0 ,0
Exp/Cntr=0.3,0.1

Type RM Length L Ch R = 1 ,115181  ,518,518,518
BEGIN DESCRIPTION:
X18965
END DESCRIPTION:
XS GIS Cut Line= 3
      2206439.06     13806898.77      2206373.95     13805368.82
      2205929.53     13803916.32
#Sta/Elev= 30
  3116.7  898.91  3320.7  897.73  3564.5   894.3  3630.9  893.15    3661   894.1
    3681  892.55  3737.5  892.21  3965.2  891.44    4132  891.46  4230.6   890.7
  4252.9  890.28  4329.2  889.26    4523  887.47  4641.8  885.85  4850.7  879.69
  4904.5  879.39  4982.2  871.02  4982.7  870.52  5012.1  871.02  5073.6  874.96
  5137.4  876.66  5154.8  878.61  5164.4  879.24    5172  881.37  5379.1  888.84
    5771  899.33  6010.7  911.14  6131.5  918.48  6164.3  922.15    6167  921.37
#Mann= 14 ,-1 , 0
  3116.7     .07       0  3564.5    .035       0  3737.5     .07       0
  3965.2    .035       0    4132     .12       0  4230.6     .07       0
  4252.9     .12       0  4329.2     .07       0    4523    .035       0
  4982.2    .035       0  5012.1    .035       0  5137.4     .12       0
  5154.8    .035       0  6010.7     .12       0
Bank Sta=4982.2,5012.1
XS Rating Curve= 0 ,0
Exp/Cntr=0.3,0.1

Type RM Length L Ch R = 1 ,114663  ,875,875,875
BEGIN DESCRIPTION:
X18964
END DESCRIPTION:
XS GIS Cut Line= 4
      2206612.68     13806714.26      2206862.23     13805499.02
      2206645.22     13804511.61      2206254.58     13803784.59
#Sta/Elev= 30
  3068.3  896.76  3435.1   891.8  3504.3  888.96  3822.2  889.42  4517.8  885.33
  4702.1  879.82  4838.9  878.79  4900.2  875.66  4994.3  872.49  4994.8  871.99
  5024.2  872.49  5114.4   875.2  5152.6  879.45  5215.9  881.54  5337.3  885.13
  5671.3  894.11  5709.4  899.97  5724.7  897.12  5753.3     897  5769.5  899.01
  5775.2  902.39  5781.5  903.16  5879.1   909.4  5884.8  910.97  5917.2  911.12
  6004.9  919.96  6054.4  927.99  6086.9  930.79  6111.9  935.87  6145.2  940.94
#Mann= 12 ,-1 , 0
  3068.3    .035       0  3504.3     .07       0  3822.2    .035       0
  4838.9     .07       0  4900.2    .035       0  4994.3    .035       0
  5024.2    .035       0  5114.4    .035       0  5215.9     .07       0
  5337.3    .035       0  5884.8     .07       0  6111.9     .12       0
Bank Sta=4994.3,5024.2
XS Rating Curve= 0 ,0
Exp/Cntr=0.3,0.1

Type RM Length L Ch R = 1 ,113788  ,825,825,825
BEGIN DESCRIPTION:
X18963
END DESCRIPTION:
XS GIS Cut Line= 4
      2206699.47     13806703.46      2207426.47     13804956.49
      2207521.23     13804620.25      2206339.75     13803390.19
#Sta/Elev= 30
  2866.9  896.88  3312.2  890.87  3916.9  884.81  3943.9  884.62  4132.3  884.01
  4259.7  883.37  4440.2  881.58  4522.4  878.53  4544.1  874.04  4550.8  869.56
  4551.3  869.06  4580.7  869.56  4630.7  876.86  4781.4  879.64  4886.5  877.47
  4988.7  873.86  5116.4  878.33  5222.4  879.32  5263.8  880.47  5696.6  882.29
    5896  885.71  5953.2  886.55  6234.1  891.85  6504.7  902.18  6642.6  906.57
  6750.4  909.72  6768.1  912.18  6780.4  913.45  6799.8  909.25    6814  908.97
#Mann= 18 ,-1 , 0
  2866.9    .035       0  3312.2     .07       0  3916.9    .035       0
  3943.9     .07       0  4132.3    .035       0  4259.7     .07       0
  4440.2      .1       0  4550.8     .05       0  4580.7      .1       0
  4886.5     .07       0  5222.4      .1       0  5263.8    .045       0
    5896      .1       0  5953.2    .035       0  6504.7     .07       0
  6642.6    .035       0  6768.1     .07       0  6780.4      .1       0
Bank Sta=4550.8,4580.7
XS Rating Curve= 0 ,0
Exp/Cntr=0.3,0.1

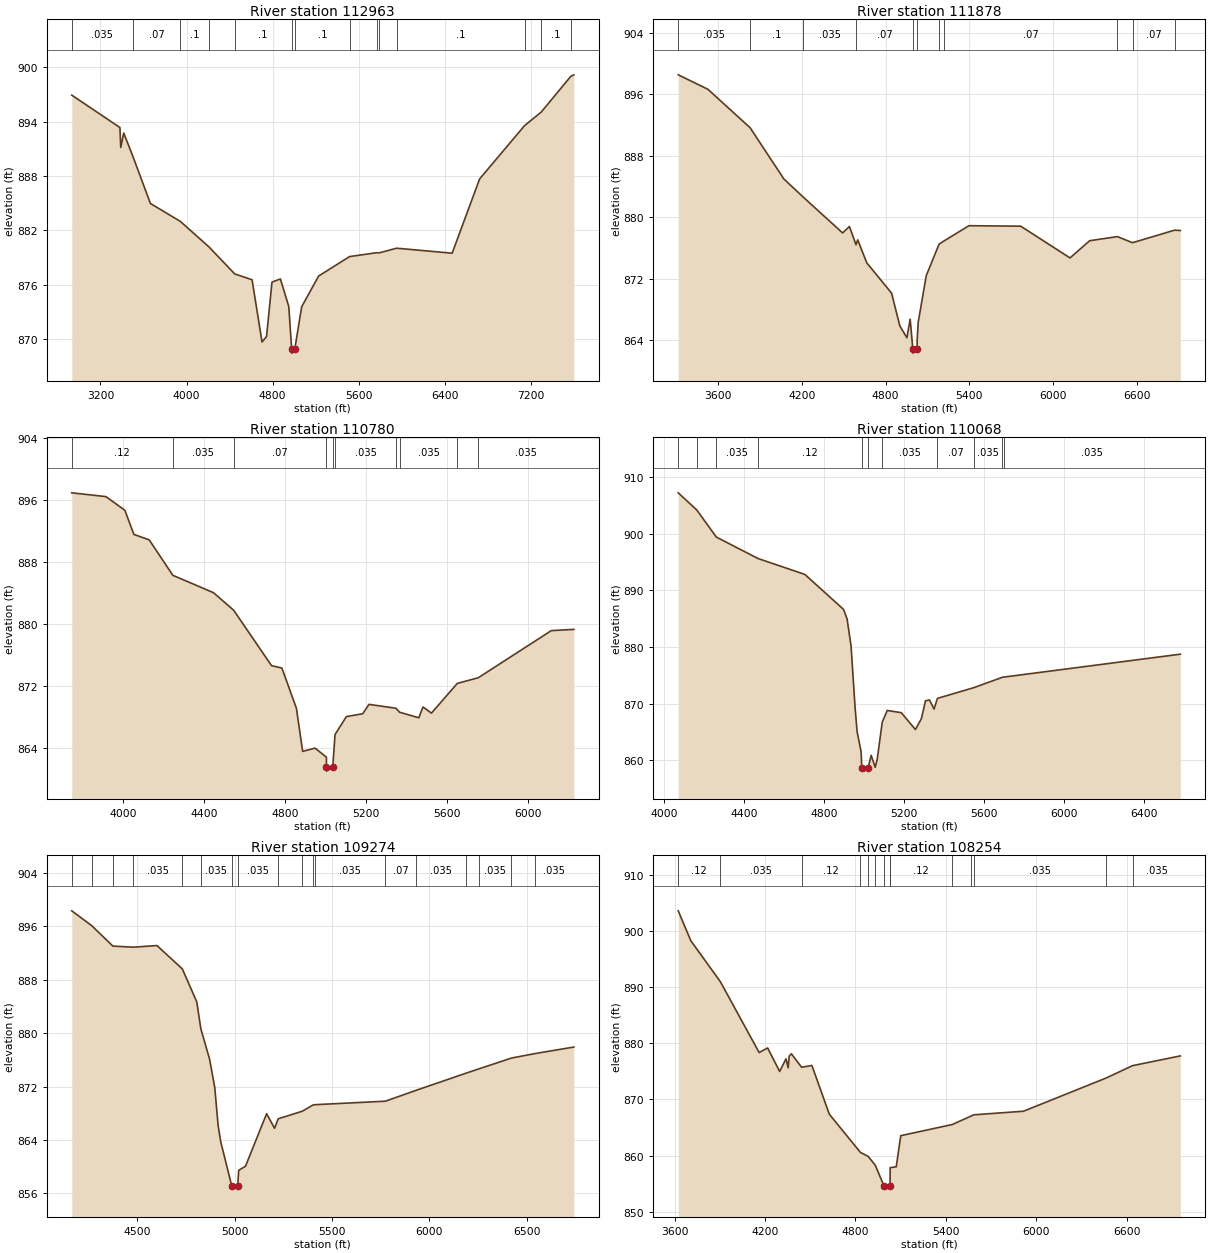
Type RM Length L Ch R = 1 ,112963  ,1085,1085,1085
BEGIN DESCRIPTION:
X18962
END DESCRIPTION:
XS GIS Cut Line= 4
       2206775.4     13806736.04      2208161.29     13805072.97
      2208240.27     13804587.57      2206686.42     13803311.49
#Sta/Elev= 30
  2933.2  896.92  3380.7  893.35  3388.5  891.15  3416.2  892.74  3500.3   890.2
  3664.5  884.97  3942.4     883  4209.7  880.17  4447.5  877.21  4609.5  876.56
  4701.9   869.7  4743.9   870.3  4794.4   876.3  4872.5  876.65  4950.6  873.61
  4977.2  868.97  4977.7  868.47  5007.2  868.97  5070.3  873.58  5227.7  876.97
  5516.3  879.12  5766.1  879.54  5792.5  879.53  5953.4  880.04  6469.2  879.49
  6724.7  887.68  7142.5  893.56  7297.9  895.06  7572.6     899  7600.5  899.16
#Mann= 14 ,-1 , 0
  2933.2    .035       0  3500.3     .07       0  3942.4      .1       0
  4209.7    .035       0  4447.5      .1       0  4977.2     .05       0
  5007.2      .1       0  5516.3     .07       0  5766.1      .1       0
  5792.5     .07       0  5953.4      .1       0  7142.5    .035       0
  7297.9      .1       0  7572.6     .07       0
Bank Sta=4977.2,5007.2
XS Rating Curve= 0 ,0
Exp/Cntr=0.3,0.1

Type RM Length L Ch R = 1 ,111878  ,1098,1098,1098
BEGIN DESCRIPTION:
X18961
END DESCRIPTION:
XS GIS Cut Line= 3
      2206862.24     13806953.01      2208468.14     13806041.56
      2208873.95     13804344.53
#Sta/Elev= 30
  3317.2   898.5  3529.5  896.62  3831.4  891.62  4073.2  884.95  4210.1  882.62
  4492.9  877.94  4541.9  878.78  4588.8   876.4    4601  877.04  4665.9  874.05
  4843.3  870.11  4902.5  865.84  4953.1  864.31  4976.1  866.73  4995.6  862.81
  4996.1  862.31  5025.7  862.81  5026.5   864.1  5033.6  866.29  5091.4  872.39
    5183  876.48  5215.9  876.87  5396.7  878.88  5766.8  878.82  6119.6  874.69
  6260.4  876.93  6458.8  877.46  6566.6  876.67    6868   878.3  6908.6  878.25
#Mann= 11 ,-1 , 0
  3317.2    .035       0  3831.4      .1       0  4210.1    .035       0
  4588.8     .07       0  4995.6     .05       0  5025.7     .07       0
    5183      .1       0  5215.9     .07       0  6458.8    .035       0
  6566.6     .07       0    6868    .035       0
Bank Sta=4995.6,5025.7
XS Rating Curve= 0 ,0
Exp/Cntr=0.3,0.1

Type RM Length L Ch R = 1 ,110780  ,712,712,712
BEGIN DESCRIPTION:
X18960
END DESCRIPTION:
XS GIS Cut Line= 3
      2208175.17     13808298.48      2208533.24     13806638.35
      2208750.08     13805890.25
#Sta/Elev= 30
  3747.2  896.95    3916  896.46  4009.4  894.69  4053.6  891.58  4129.3  890.88
    4246   886.3  4446.4  884.06  4546.1  881.79  4732.8  874.64    4784  874.33
  4855.6  869.13  4886.3  863.57  4947.7  863.99  5003.6  862.82  5003.8  861.52
  5004.3  861.02  5034.7  861.52  5046.2  865.75  5102.2  868.06    5183  868.43
  5213.6  869.64  5346.3  869.14  5365.1  868.62  5459.4  867.91  5480.2   869.3
  5521.9  868.51  5649.5  872.35  5752.5  873.07  6113.2  879.16  6224.4  879.32
#Mann= 10 ,-1 , 0
  3747.2     .12       0    4246    .035       0  4546.1     .07       0
  5003.8     .05       0  5034.7     .07       0  5046.2    .035       0
  5346.3     .12       0  5365.1    .035       0  5649.5     .12       0
  5752.5    .035       0
Bank Sta=5003.8,5034.7
XS Rating Curve= 0 ,0
Exp/Cntr=0.3,0.1

Type RM Length L Ch R = 1 ,110068  ,794,794,794
BEGIN DESCRIPTION:
X18959
END DESCRIPTION:
XS GIS Cut Line= 3
      2208967.27     13808124.85      2209130.03     13806291.12
      2208772.92     13805728.41
#Sta/Elev= 30
  4071.6  907.23  4164.8  904.18  4261.9  899.42  4470.5  895.63  4703.9  892.83
    4897  886.66  4914.8  884.99  4934.8  880.17  4954.9  869.29  4964.9  865.08
    4985  861.51  4988.3  858.61  4988.8  858.11  5019.2  858.61  5035.2  860.88
  5055.3  858.79  5065.3  860.18  5090.4  866.75  5115.5  868.82  5185.8  868.42
  5256.1  865.45  5286.2  867.39  5306.3  870.52  5326.4  870.67  5349.1  869.06
  5366.1  870.95  5547.7  872.84  5690.9  874.68  5700.3  874.72    6579  878.75
#Mann= 11 ,-1 , 0
  4071.6    .035       0  4164.8     .12       0  4261.9    .035       0
  4470.5     .12       0  4988.3     .05       0  5019.2     .12       0
  5090.4    .035       0  5366.1     .07       0  5547.7    .035       0
  5690.9     .07       0  5700.3    .035       0
Bank Sta=4988.3,5019.2
XS Rating Curve= 0 ,0
Exp/Cntr=0.3,0.1

Type RM Length L Ch R = 1 ,109274  ,1020,1020,1020
BEGIN DESCRIPTION:
X18958
END DESCRIPTION:
XS GIS Cut Line= 3
      2209585.77      13808092.3      2209857.03     13806877.06
      2208923.84     13805922.17
#Sta/Elev= 30
  4162.7   898.3  4265.7  896.07    4374  893.02  4478.6  892.86  4600.5   893.1
  4730.9  889.61  4805.4  884.65    4826  880.65  4871.3  876.06  4897.6  871.85
  4914.8  866.18  4928.4  863.72  4984.7  857.14  4985.2  856.64  5015.6  857.14
  5020.6  859.46  5055.4  860.06    5164  867.93    5205  865.75  5223.6  867.17
  5347.5   868.3  5402.2  869.23  5411.9  869.28  5774.4   869.8  5931.3  871.42
  6189.3     874  6253.9  874.63  6422.5  876.26  6542.9  876.93    6743  877.91
#Mann= 18 ,-1 , 0
  4162.7     .12       0  4265.7    .035       0    4374     .12       0
  4478.6    .035       0  4730.9     .07       0    4826    .035       0
  4984.7    .035       0  5015.6    .035       0  5223.6     .07       0
  5347.5    .035       0  5402.2     .07       0  5411.9    .035       0
  5774.4     .07       0  5931.3    .035       0  6189.3     .07       0
  6253.9    .035       0  6422.5     .07       0  6542.9    .035       0
Bank Sta=4984.7,5015.6
XS Rating Curve= 0 ,0
Exp/Cntr=0.3,0.1

Type RM Length L Ch R = 1 ,108254  ,978,978,978
BEGIN DESCRIPTION:
X18957
END DESCRIPTION:
XS GIS Cut Line= 4
      2211723.32     13807484.68       2210963.8     13806942.17
       2210171.7     13806833.66      2208913.05     13805846.27
#Sta/Elev= 30
  3623.8  903.56  3707.8  898.22  3903.1  890.97  4160.8  878.35  4217.3  879.16
  4297.2  874.98  4338.9  877.23  4353.7  875.63  4359.8  877.67  4374.6  878.13
  4442.8  875.73    4511  876.05  4626.6  867.38    4833  860.59  4884.9  859.86
    4932  858.29  4990.4  854.55  4991.4  854.05    5030  854.55  5030.4  857.84
    5031  857.88  5070.7  858.01    5101  863.56  5443.6  865.55    5566  867.03
  5585.6  867.27  5915.8  867.91  6464.5  873.82  6639.7  876.02  6956.4  877.75
#Mann= 14 ,-1 , 0
  3623.8     .12       0  3903.1    .035       0  4442.8     .12       0
    4833     .07       0  4884.9     .12       0    4932     .07       0
  4990.4     .05       0    5030     .07       0    5031     .12       0
  5443.6    .035       0    5566     .07       0  5585.6    .035       0
  6464.5     .07       0  6639.7    .035       0
Bank Sta=4990.4,5030
XS Rating Curve= 0 ,0
Exp/Cntr=0.3,0.1

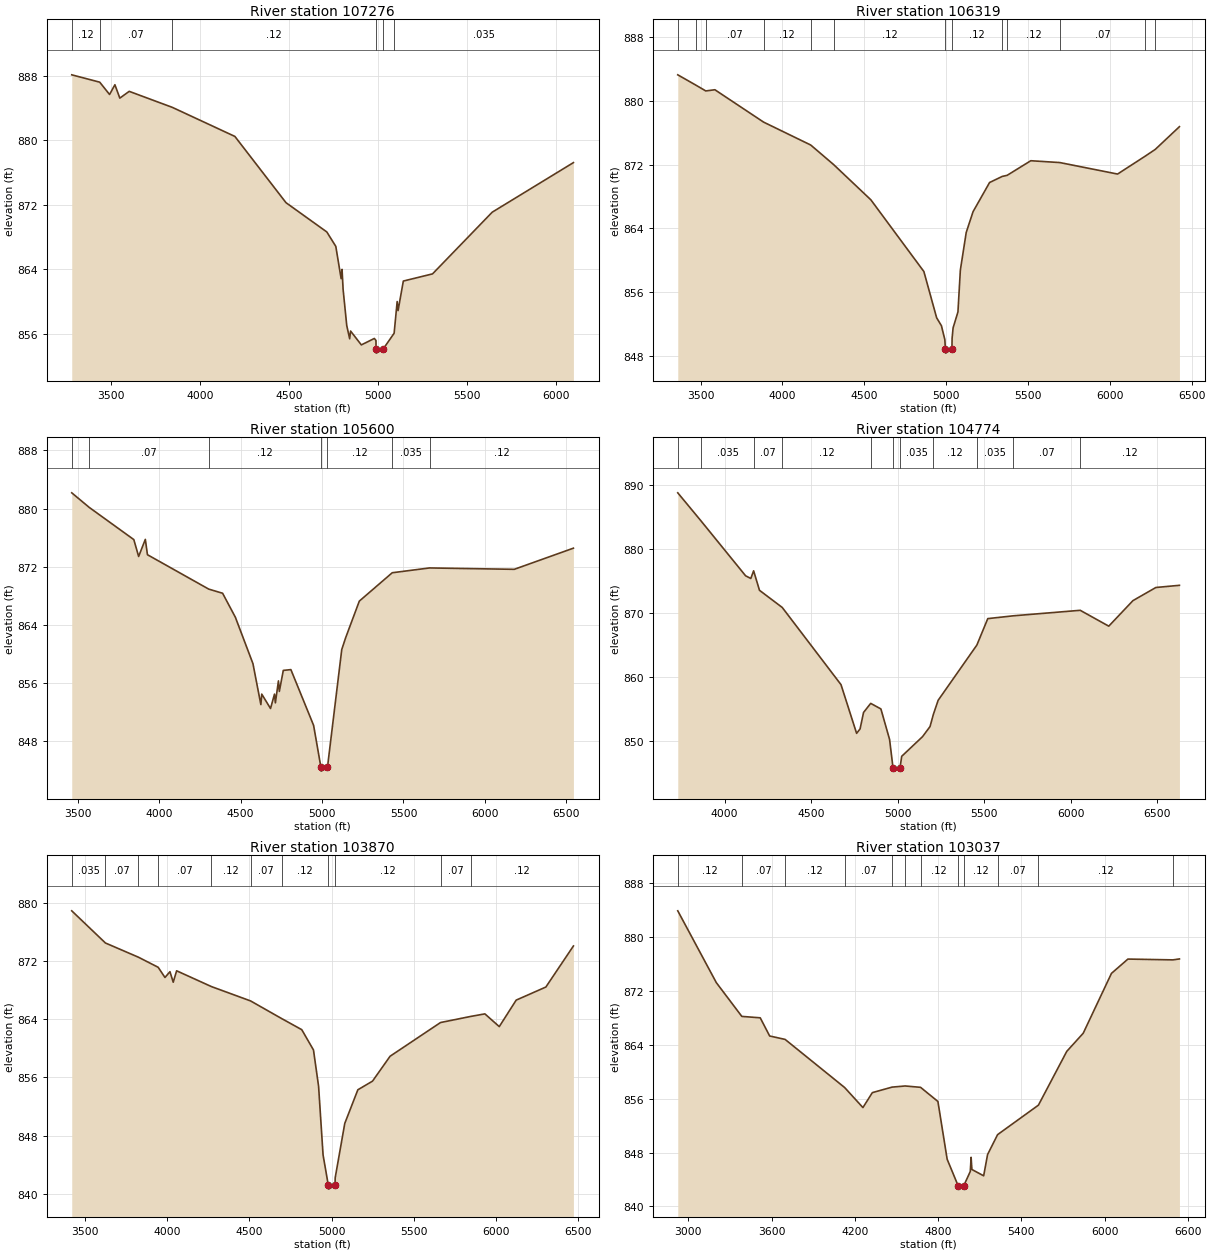
Type RM Length L Ch R = 1 ,107276  ,957,957,957
BEGIN DESCRIPTION:
X18956
END DESCRIPTION:
XS GIS Cut Line= 3
      2211669.08     13806811.95      2210692.53     13806247.72
      2209043.23     13805867.95
#Sta/Elev= 30
  3277.9  888.11  3435.1   887.2  3490.5  885.67  3520.5  886.88  3548.2  885.22
  3600.9  886.06  3843.7  884.07    4195  880.47  4482.4  872.25  4711.9  868.62
  4762.4  866.83  4792.3  862.83  4797.5  863.98  4803.4   861.5  4823.9  857.01
  4840.3  855.37  4845.4  856.33    4906  854.61    4979  855.41  4988.1  855.16
  4988.8  854.09  4989.8  853.59  5028.4  854.09  5090.3  856.06  5107.4  859.99
  5112.5  858.87    5142  862.53  5306.2  863.42  5641.6  871.07  6098.2  877.22
#Mann= 6 ,-1 , 0
  3277.9     .12       0  3435.1     .07       0  3843.7     .12       0
  4988.8     .05       0  5028.4     .12       0  5090.3    .035       0
Bank Sta=4988.8,5028.4
XS Rating Curve= 0 ,0
Exp/Cntr=0.3,0.1

Type RM Length L Ch R = 1 ,106319  ,719,719,719
BEGIN DESCRIPTION:
X18955
END DESCRIPTION:
XS GIS Cut Line= 3
      2211267.63      13806432.2      2210681.68     13805748.59
      2208913.02     13804500.76
#Sta/Elev= 30
  3360.6  883.25  3469.3  881.98  3531.6  881.23  3587.4  881.38  3885.1  877.32
  4172.9  874.45  4312.7     872  4540.3  867.58  4864.2  858.59  4942.2  852.79
  4971.3   851.8  4992.2  850.06  4995.8  848.86  4996.8  848.36  5035.5  848.86
  5036.6   850.2  5042.7  851.53  5072.3  853.52  5087.1  858.78  5122.8  863.48
  5164.6  866.09  5265.6  869.75  5342.7  870.51  5372.9  870.65  5517.4  872.48
  5694.7  872.25  6047.5  870.81  6215.4  873.04  6277.8   873.9  6425.5  876.75
#Mann= 13 ,-1 , 0
  3360.6     .07       0  3469.3     .12       0  3531.6     .07       0
  3885.1     .12       0  4172.9    .035       0  4312.7     .12       0
  4995.8     .05       0  5035.5     .12       0  5342.7    .035       0
  5372.9     .12       0  5694.7     .07       0  6215.4    .035       0
  6277.8     .12       0
Bank Sta=4995.8,5035.5
XS Rating Curve= 0 ,0
Exp/Cntr=0.3,0.1

Type RM Length L Ch R = 1 ,105600  ,826,826,826
BEGIN DESCRIPTION:
X18954
END DESCRIPTION:
XS GIS Cut Line= 3
      2211994.65     13805390.53      2210030.64     13804609.27
      2209075.79     13804468.21
#Sta/Elev= 30
    3464  882.17  3571.6  880.16  3844.9  875.74  3874.6  873.42  3915.6  875.77
  3928.6  873.66  4304.7  868.93  4389.9  868.36  4468.2  865.06  4576.1  858.68
  4624.7  853.05  4630.1  854.49    4684  852.51  4708.3  854.49  4713.7  853.29
  4732.6  856.31    4738  854.86  4762.3  857.75  4808.9  857.86  4948.4  850.19
  4993.5   844.4  4994.5   843.9  5033.3   844.4  5121.1  860.62  5145.4  862.27
    5229  867.28    5431  871.18    5660  871.84  6179.8  871.65  6542.9  874.56
#Mann= 7 ,-1 , 0
    3464    .035       0  3571.6     .07       0  4304.7     .12       0
  4993.5     .05       0  5033.3     .12       0    5431    .035       0
    5660     .12       0
Bank Sta=4993.5,5033.3
XS Rating Curve= 0 ,0
Exp/Cntr=0.3,0.1

Type RM Length L Ch R = 1 ,104774  ,904,904,904
BEGIN DESCRIPTION:
X18953
END DESCRIPTION:
XS GIS Cut Line= 3
      2212396.12     13804153.54      2210573.17     13804262.04
      2209509.89     13804392.24
#Sta/Elev= 30
  3730.1  888.83    3867  884.35  4121.9  875.85    4152  875.43  4168.2  876.63
  4202.1  873.58  4333.7  870.89  4672.9  858.82    4763   851.2  4783.1   851.9
  4803.1  854.47  4844.4  855.89  4903.3  855.02  4953.4  850.25  4973.4  845.79
  4974.4  845.29  5013.5  845.79  5023.5  847.61  5143.7  850.68    5187  852.26
  5206.5  854.18  5233.9  856.37  5457.5  865.01  5520.6  869.15  5668.4  869.59
  6054.4  870.45  6219.4  867.97  6358.8  871.96  6491.4  874.02  6627.5  874.36
#Mann= 11 ,-1 , 0
  3730.1     .12       0    3867    .035       0  4168.2     .07       0
  4333.7     .12       0  4844.4    .035       0  4973.4     .05       0
  5013.5    .035       0  5206.5     .12       0  5457.5    .035       0
  5668.4     .07       0  6054.4     .12       0
Bank Sta=4973.4,5013.5
XS Rating Curve= 0 ,0
Exp/Cntr=0.3,0.1

Type RM Length L Ch R = 1 ,103870  ,833,833,833
BEGIN DESCRIPTION:
X18952
END DESCRIPTION:
XS GIS Cut Line= 3
       2212385.2     13803111.88      2211094.01     13803318.03
      2209598.34      13804217.6
#Sta/Elev= 30
  3418.5   878.9  3623.5  874.48    3824  872.53  3944.6  871.14  3985.8  869.74
  4016.2  870.54  4036.1  869.09  4056.7  870.66  4268.6  868.49  4506.8  866.52
  4697.1  864.08  4818.2  862.57  4889.6  859.78  4920.7  854.78  4947.9  845.36
  4980.1  841.16  4981.1  840.66  5020.5  841.16  5021.7  842.22    5080  849.69
  5159.6  854.31  5248.9   855.5  5355.8  858.92  5662.6  863.55  5848.9   864.4
  5932.7  864.74  6020.2  862.99  6123.1  866.63  6303.8  868.43  6471.4  874.07
#Mann= 11 ,-1 , 0
  3418.5    .035       0  3623.5     .07       0    3824    .035       0
  3944.6     .07       0  4268.6     .12       0  4506.8     .07       0
  4697.1     .12       0  4980.1     .05       0  5020.5     .12       0
  5662.6     .07       0  5848.9     .12       0
Bank Sta=4980.1,5020.5
XS Rating Curve= 0 ,0
Exp/Cntr=0.3,0.1

Type RM Length L Ch R = 1 ,103037  ,888,888,888
BEGIN DESCRIPTION:
X18951
END DESCRIPTION:
XS GIS Cut Line= 2
      2212092.27     13802070.21       2208838.5     13803642.86
#Sta/Elev= 30
  2924.4  883.93  3202.1  873.26  3385.8  868.24  3518.5  868.03  3586.3  865.33
  3697.7  864.82  4126.5  857.67  4258.2  854.69    4326  856.91  4468.1  857.73
  4562.3   857.9  4673.3   857.7  4798.4   855.6  4865.1  847.01  4944.1  843.07
  4945.1  842.57  4984.5  843.07  5031.7   845.2  5037.6   847.3  5043.2  845.49
    5128  844.55  5156.2  847.71  5228.4  850.67  5522.5  855.05  5726.6  863.04
  5845.2  865.74  6048.5  874.63  6167.1  876.76  6491.3  876.64  6538.3  876.78
#Mann= 12 ,-1 , 0
  2924.4     .12       0  3385.8     .07       0  3697.7     .12       0
  4126.5     .07       0  4468.1    .035       0  4562.3     .07       0
  4673.3     .12       0  4944.1     .05       0  4984.5     .12       0
  5228.4     .07       0  5522.5     .12       0  6491.3    .035       0
Bank Sta=4944.1,4984.5
XS Rating Curve= 0 ,0
Exp/Cntr=0.3,0.1