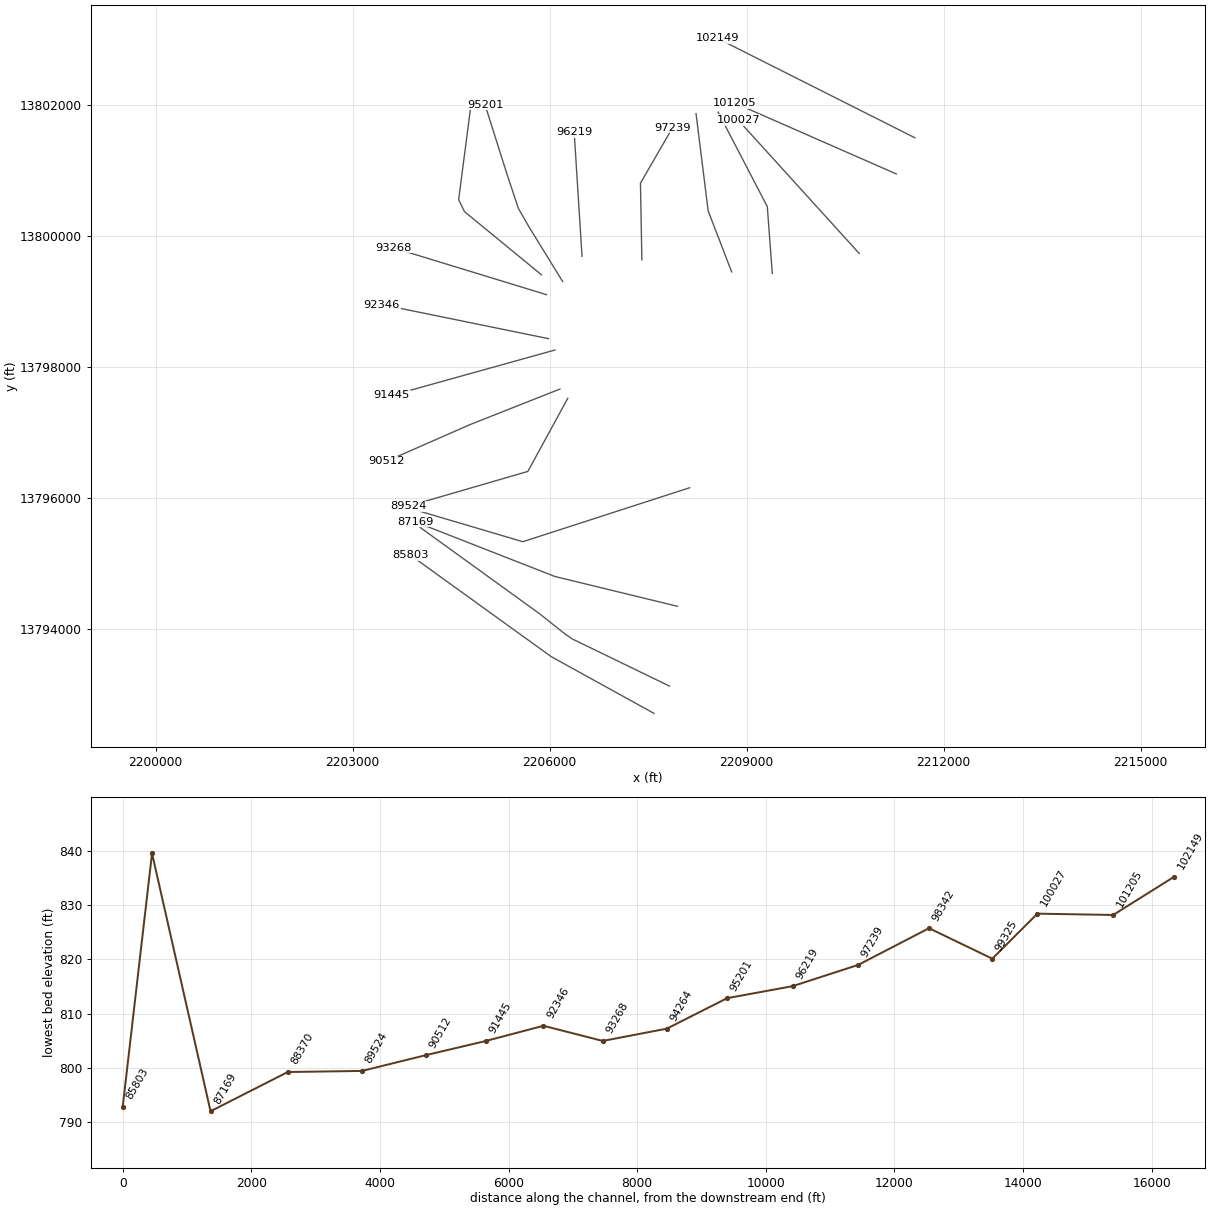
HEC-RAS study Dry Comal Creek.prj: Dry Comal Creek Base Level Engineering

--- Dry Comal Creek.g01 (geometry) --- (continued)

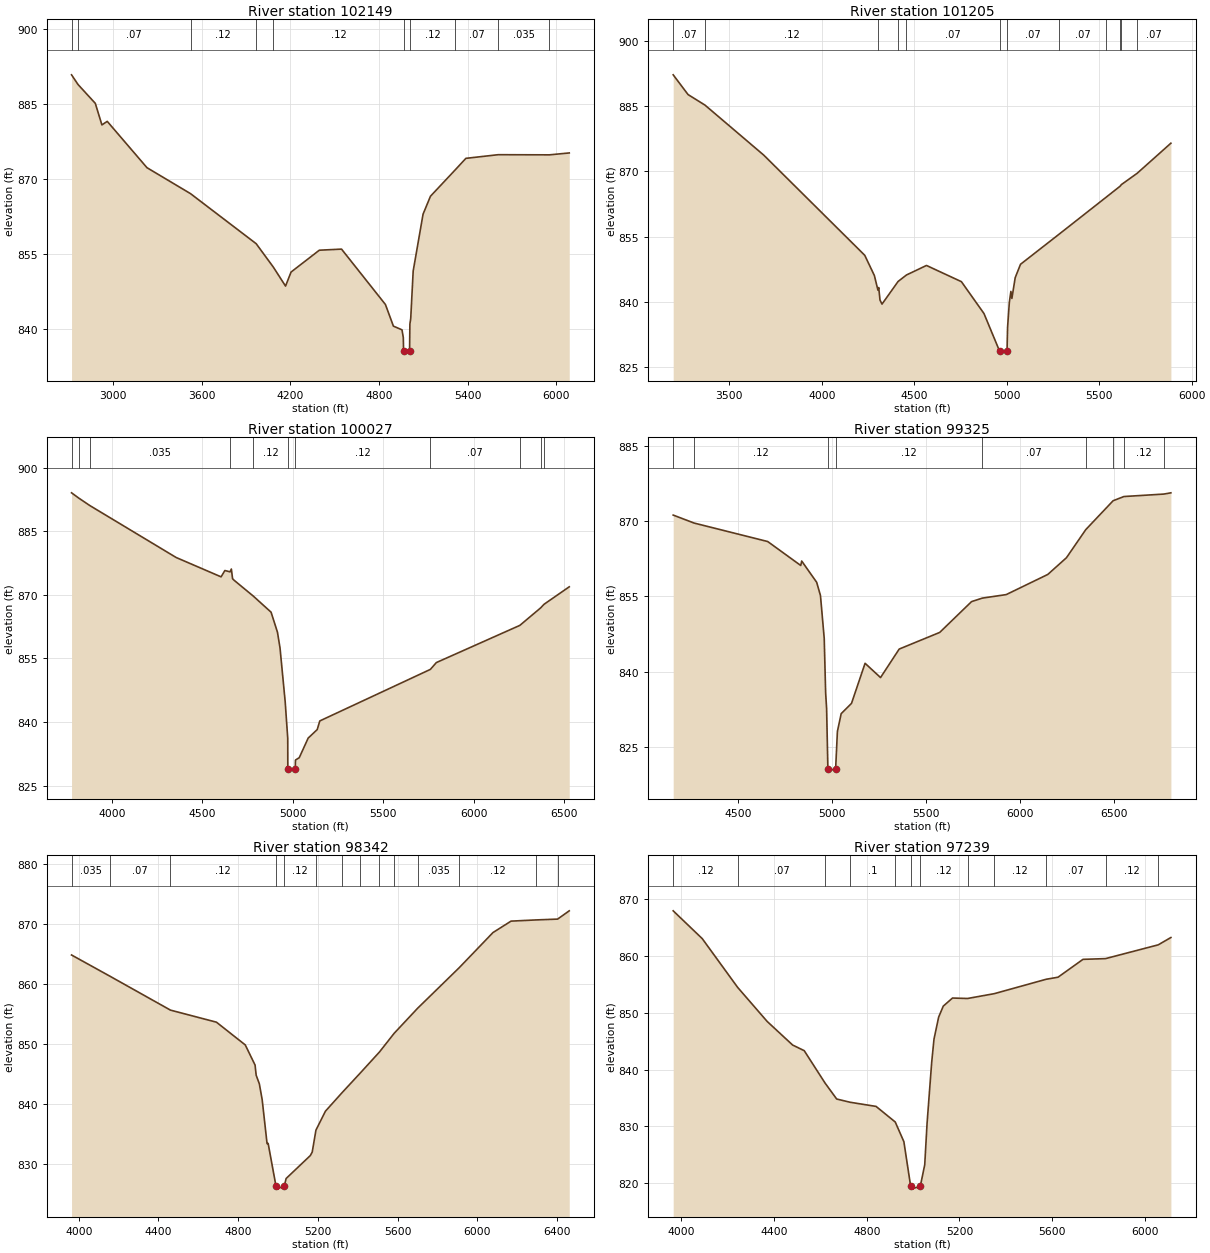
Type RM Length L Ch R = 1 ,102149  ,944,944,944
BEGIN DESCRIPTION:
X18950
END DESCRIPTION:
XS GIS Cut Line= 2
      2211560.57     13801505.98      2208554.94     13803025.07
#Sta/Elev= 30
  2718.6  890.87  2762.5  888.93  2879.4  885.16    2924  880.85  2960.1  881.56
    3229  872.29  3523.6   867.1  3968.1  857.08    4084   852.4  4166.6   848.6
  4203.9  851.41  4395.1  855.78  4545.5     856  4842.5  844.92  4896.5  840.59
  4954.6  839.85  4963.4   838.3  4965.4  835.69  4966.4  835.19  5005.9  835.69
    5008  841.01  5013.6  842.09  5030.3  851.62  5097.1  862.99  5147.3  866.58
  5314.9  871.86  5386.9  874.16  5605.6  874.89    5952  874.86  6086.3  875.24
#Mann= 10 ,-1 , 0
  2718.6    .035       0  2762.5     .07       0  3523.6     .12       0
  3968.1    .035       0    4084     .12       0  4965.4     .05       0
  5005.9     .12       0  5314.9     .07       0  5605.6    .035       0
    5952     .07       0
Bank Sta=4965.4,5005.9
XS Rating Curve= 0 ,0
Exp/Cntr=0.3,0.1

Type RM Length L Ch R = 1 ,101205  ,1178,1178,1178
BEGIN DESCRIPTION:
X18949
END DESCRIPTION:
XS GIS Cut Line= 2
      2211278.46     13800952.59      2208815.37     13802037.65
#Sta/Elev= 30
  3196.2  892.22  3276.5  887.68  3367.9  885.26  3686.1  873.74  4232.1   850.7
  4284.2  846.04  4303.4  842.68  4307.6  843.28  4314.6   840.4  4325.4  839.47
  4412.5  844.68  4457.8  846.17  4565.9  848.36  4754.8  844.63  4876.9   837.3
  4960.9  828.69  4961.9  828.19  5001.5  828.69  5004.5  834.12  5013.9  839.83
  5022.4  842.39  5027.8  840.77  5045.7  845.55  5074.5  848.63  5285.1  855.62
    5539  864.11  5613.5  866.61  5619.5  866.95  5705.4  869.57  5887.7  876.49
#Mann= 12 ,-1 , 0
  3196.2     .07       0  3367.9     .12       0  4303.4     .07       0
  4412.5     .12       0  4457.8     .07       0  4960.9     .05       0
  5001.5     .07       0  5285.1     .07       0    5539    .035       0
  5613.5     .07       0  5619.5    .035       0  5705.4     .07       0
Bank Sta=4960.9,5001.5
XS Rating Curve= 0 ,0
Exp/Cntr=0.3,0.1

Type RM Length L Ch R = 1 ,100027  ,702,702,702
BEGIN DESCRIPTION:
X18948
END DESCRIPTION:
XS GIS Cut Line= 2
      2210714.26     13799737.27      2208869.82     13801777.01
#Sta/Elev= 30
  3777.5  894.08  3815.9  892.88    3878  891.09  4355.7  878.82  4603.7  874.26
  4624.7  875.75  4653.4  875.44  4660.5   876.1  4667.3  873.82  4674.7  873.49
  4782.5  869.69    4880  865.92  4915.3   861.2  4929.5  857.46  4957.9  844.82
  4972.1  836.15  4972.5  828.93  4973.5  828.43  5013.6  828.93  5014.7  831.04
  5035.6   831.6    5085  836.22    5135  838.24  5149.2  840.27  5760.2  852.43
  5793.3  854.04  6254.5  862.81  6369.3  866.93    6388  867.78  6527.5  871.91
#Mann= 11 ,-1 , 0
  3777.5    .035       0  3815.9     .12       0    3878    .035       0
  4653.4     .07       0  4782.5     .12       0  4972.5     .05       0
  5013.6     .12       0  5760.2     .07       0  6254.5    .035       0
  6369.3     .07       0    6388    .035       0
Bank Sta=4972.5,5013.6
XS Rating Curve= 0 ,0
Exp/Cntr=0.3,0.1

Type RM Length L Ch R = 1 ,99325   ,983,983,983
BEGIN DESCRIPTION:
X18947
END DESCRIPTION:
XS GIS Cut Line= 3
      2209390.45     13799433.49      2209314.49     13800453.45
      2208565.78     13801896.62
#Sta/Elev= 30
  4156.6  871.24  4267.6  869.65  4659.5  865.96  4835.4  861.18  4840.4  862.07
  4920.2  857.82  4940.3  855.19  4960.3  846.63  4967.9  835.73    4973  832.65
  4979.8  820.64  4980.8  820.14  5021.1  820.64  5030.5  828.07  5050.6  831.61
  5105.5  833.66  5177.7  841.66    5260  838.81  5359.3   844.5  5574.9  847.82
  5744.4  853.97    5802  854.67  5928.9  855.37  6150.1  859.39  6249.4  862.73
  6352.1  868.33  6497.7   874.1  6555.2  874.94  6767.4  875.43  6805.2  875.68
#Mann= 9 ,-1 , 0
  4156.6     .07       0  4267.6     .12       0  4979.8     .05       0
  5021.1     .12       0    5802     .07       0  6352.1    .035       0
  6497.7     .07       0  6555.2     .12       0  6767.4     .07       0
Bank Sta=4979.8,5021.1
XS Rating Curve= 0 ,0
Exp/Cntr=0.3,0.1

Type RM Length L Ch R = 1 ,98342   ,1103,1103,1103
BEGIN DESCRIPTION:
X18946
END DESCRIPTION:
XS GIS Cut Line= 3
      2208771.95     13799455.19      2208413.88     13800388.35
      2208229.43     13801874.85
#Sta/Elev= 30
    3964  864.82  4157.1  861.27  4460.4  855.62    4691  853.61  4835.8  849.81
  4884.9  846.45  4890.4  844.76  4906.4  843.31  4920.5  840.69  4945.1  833.34
  4950.5  833.38  4989.9  826.25  4990.9  825.75  5031.2  826.25  5040.7  827.52
  5162.1  831.35  5171.7  831.94  5190.3  835.59  5237.9  838.75    5321  841.83
  5413.5  845.15    5509  848.63  5582.8  851.75  5700.8  855.94  5909.6  862.71
  6078.6  868.56  6169.3  870.47  6293.6  870.67    6403  870.81  6461.4  872.19
#Mann= 14 ,-1 , 0
    3964    .035       0  4157.1     .07       0  4460.4     .12       0
  4989.9     .05       0  5031.2     .12       0  5190.3     .07       0
    5321    .035       0  5413.5     .07       0    5509    .035       0
  5582.8     .07       0  5700.8    .035       0  5909.6     .12       0
  6293.6    .035       0    6403     .07       0
Bank Sta=4989.9,5031.2
XS Rating Curve= 0 ,0
Exp/Cntr=0.3,0.1

Type RM Length L Ch R = 1 ,97239   ,1020,1020,1020
BEGIN DESCRIPTION:
X18945
END DESCRIPTION:
XS GIS Cut Line= 3
      2207404.77     13799639.67      2207383.07     13800811.52
      2207870.67      13801656.7
#Sta/Elev= 30
  3964.5  867.91  4089.9  863.02  4242.9  854.44  4369.9  848.47  4479.9  844.32
  4529.9  843.33  4619.8  837.64    4670  834.83    4728  834.26    4840  833.53
  4922.7  830.79    4960  827.33  4989.3  819.49  4990.3  818.99  5030.8  819.49
    5050  823.27    5060  830.52    5080  841.27    5090  845.36    5110  849.22
    5130  851.16  5169.9  852.58  5234.6   852.5  5350.2  853.35  5574.1  855.88
  5625.2  856.24  5732.9  859.38  5830.2  859.51  6057.7  861.93  6112.3  863.22
#Mann= 12 ,-1 , 0
  3964.5     .12       0  4242.9     .07       0  4619.8     .12       0
    4728      .1       0  4922.7     .12       0  4989.3     .05       0
  5030.8     .12       0  5234.6     .07       0  5350.2     .12       0
  5574.1     .07       0  5830.2     .12       0  6057.7     .07       0
Bank Sta=4989.3,5030.8
XS Rating Curve= 0 ,0
Exp/Cntr=0.3,0.1

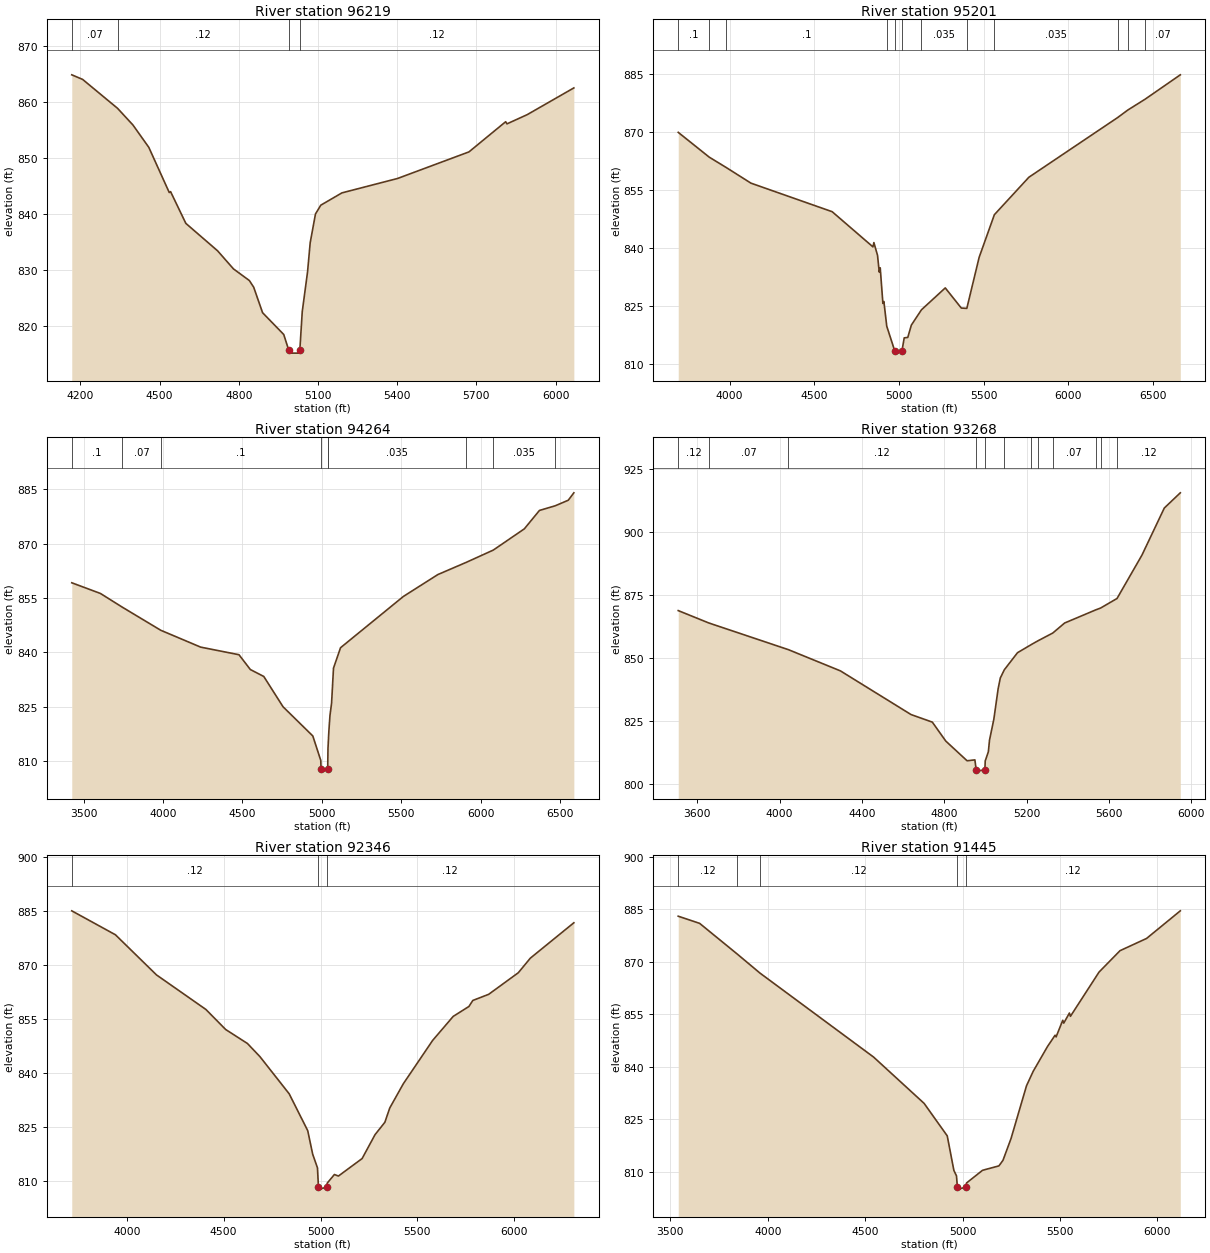
Type RM Length L Ch R = 1 ,96219   ,1018,1018,1018
BEGIN DESCRIPTION:
X18944
END DESCRIPTION:
XS GIS Cut Line= 2
      2206493.31     13799693.87      2206374.04     13801591.42
#Sta/Elev= 30
  4167.6   864.8  4208.8  863.98  4340.9  858.82  4399.2  855.84  4459.3  851.85
  4536.8  843.77  4541.8  843.93  4599.6  838.26  4719.8  833.36  4779.9  830.13
  4840.1  828.05  4856.6  826.85  4890.2   822.3  4970.3  818.41  4989.5  815.58
  4990.5  815.08  5030.2  815.08  5031.2  815.58  5040.4  822.48  5060.5   829.6
  5070.5  834.81  5090.5  839.94  5110.6  841.51  5190.7  843.71  5401.2  846.28
  5671.7  851.03  5810.7  856.42  5815.7  856.04  5892.1  857.68  6068.9  862.46
#Mann= 4 ,-1 , 0
  4167.6     .07       0  4340.9     .12       0  4989.5     .05       0
  5031.2     .12       0
Bank Sta=4989.5,5031.2
XS Rating Curve= 0 ,0
Exp/Cntr=0.3,0.1

Type RM Length L Ch R = 1 ,95201   ,937,937,937
BEGIN DESCRIPTION:
Dry Comal Creek 107.0
END DESCRIPTION:
XS GIS Cut Line= 5
      2206197.75     13799308.66      2205684.29     13800146.23
        2205525.       13800425.      2205360.33     13800919.01
      2205017.19     13802008.31
#Sta/Elev= 30
  3696.1  869.89  3878.9   863.5  3981.1  860.77  4125.8  856.77  4605.5   849.4
  4846.3  840.32    4852  841.42  4873.6  838.12  4883.7   833.8  4889.5   834.9
  4905.3  825.71  4911.1   826.2  4928.1  819.82  4975.8  813.37  4976.8  812.87
  5017.6  813.37  5031.2  816.81  5052.3  816.93  5073.4  820.11  5133.2  824.07
  5273.7  829.71  5368.5  824.51  5401.1  824.43  5473.9  837.61  5563.8  848.62
  5767.8   858.3  6292.1  873.71  6352.1  875.65  6454.3  878.45  6662.4  884.75
#Mann= 12 ,-1 , 0
  3696.1      .1       0  3878.9     .07       0  3981.1      .1       0
  4928.1     .07       0  4975.8     .05       0  5017.6     .07       0
  5133.2    .035       0  5401.1      .1       0  5563.8    .035       0
  6292.1     .07       0  6352.1    .035       0  6454.3     .07       0
Bank Sta=4975.8,5017.6
XS Rating Curve= 0 ,0
Exp/Cntr=0.3,0.1

Type RM Length L Ch R = 1 ,94264   ,996,996,996
BEGIN DESCRIPTION:
X18943
END DESCRIPTION:
XS GIS Cut Line= 4
      2205874.82     13799411.79      2204702.95      13800377.5
      2204614.88      13800561.4      2204800.03     13801989.84
#Sta/Elev= 30
  3425.1  859.23  3605.4  856.29  3743.8  852.49  3985.6  846.13  4237.3  841.47
  4478.4  839.38  4550.1  835.29  4634.7  833.38    4756  825.02  4943.6  816.96
  4993.7  810.21  4995.4  807.76  4996.4  807.26  5037.3  807.76  5038.2  810.63
  5039.1   813.5  5044.6  818.21  5051.7  822.64  5061.7  825.99  5073.9  835.68
  5118.2  841.31  5514.2  855.46  5731.4   861.5  5908.9  864.84  6080.4  868.25
    6276  874.11  6371.3  879.19    6471  880.48  6552.8  882.01  6587.9  884.05
#Mann= 9 ,-1 , 0
  3425.1      .1       0  3743.8     .07       0  3985.6      .1       0
  4995.4     .05       0  5037.3      .1       0  5038.2    .035       0
  5908.9     .07       0  6080.4    .035       0    6471     .07       0
Bank Sta=4995.4,5037.3
XS Rating Curve= 0 ,0
Exp/Cntr=0.3,0.1

Type RM Length L Ch R = 1 ,93268   ,922,922,922
BEGIN DESCRIPTION:
X18942
END DESCRIPTION:
XS GIS Cut Line= 2
      2205950.74     13799107.97      2203618.94     13799823.78
#Sta/Elev= 30
    3508  868.85  3656.5  863.93  4043.6   853.3    4296  844.87    4639   827.5
  4742.4  824.49  4807.8  816.95  4911.3  809.12  4949.2  809.47  4955.6   805.5
  4956.6     805  4997.9   805.5  4999.4  809.04  5014.7  812.71  5020.3  817.35
  5041.3  825.64  5062.2  837.77  5072.6  842.01  5092.2  845.31  5156.3   852.1
  5223.7  855.36  5254.9   856.8  5327.7  859.93  5385.2  863.91  5535.7  869.11
  5560.3  869.88  5639.7  873.66  5760.9  890.92  5869.5  909.65  5947.2  915.69
#Mann= 12 ,-1 , 0
    3508     .12       0  3656.5     .07       0  4043.6     .12       0
  4955.6     .05       0  4997.9     .12       0  5092.2    .035       0
  5223.7     .07       0  5254.9    .035       0  5327.7     .07       0
  5535.7    .035       0  5560.3     .07       0  5639.7     .12       0
Bank Sta=4955.6,4997.9
XS Rating Curve= 0 ,0
Exp/Cntr=0.3,0.1

Type RM Length L Ch R = 1 ,92346   ,901,901,901
BEGIN DESCRIPTION:
X18941
END DESCRIPTION:
XS GIS Cut Line= 2
      2205983.29     13798435.23      2203444.25     13798956.06
#Sta/Elev= 30
  3715.8  885.08  3941.2  878.43    4153  867.29  4408.2  857.69  4510.3  852.12
  4622.6  848.24    4687   844.6  4838.2  834.26  4933.9  824.03  4959.5  817.49
  4984.3  813.68  4989.3  808.29  4990.3  807.79  5031.6  808.29  5034.7  809.47
  5071.7  811.85  5092.2  811.42  5214.7  816.28  5281.6  822.94    5332  826.34
  5357.6  830.35  5427.7  837.08  5578.9   849.1  5684.9  855.76  5765.9  858.51
  5786.3  860.19    5868  861.89  6021.1  867.89    6083  871.93  6307.7  881.76
#Mann= 3 ,-1 , 0
  3715.8     .12       0  4989.3     .05       0  5031.6     .12       0
Bank Sta=4989.3,5031.6
XS Rating Curve= 0 ,0
Exp/Cntr=0.3,0.1

Type RM Length L Ch R = 1 ,91445   ,933,933,933
BEGIN DESCRIPTION:
X18940
END DESCRIPTION:
XS GIS Cut Line= 2
      2206080.96      13798261.6       2203598.1      13797567.7
#Sta/Elev= 30
  3540.2  883.03  3650.2  880.98  3841.4  872.29  3960.7  866.73  4543.2  842.75
  4802.8   829.5  4921.5  820.21  4955.6  810.32  4968.9  808.78  4973.7  805.48
  4974.7  804.98  5016.2  805.48  5020.8  806.75  5102.6  810.36  5186.9  811.63
  5207.7  813.22  5249.2  819.48  5328.3  834.51  5362.4  838.63  5435.9  845.73
  5475.3     849  5480.5  848.52  5514.6  853.27  5519.8  852.46  5548.8  855.34
    5554   854.4  5700.9  867.05  5808.6  873.17  5944.9  876.67  6118.2  884.57
#Mann= 5 ,-1 , 0
  3540.2     .12       0  3841.4     .07       0  3960.7     .12       0
  4973.7     .05       0  5016.2     .12       0
Bank Sta=4973.7,5016.2
XS Rating Curve= 0 ,0
Exp/Cntr=0.3,0.1

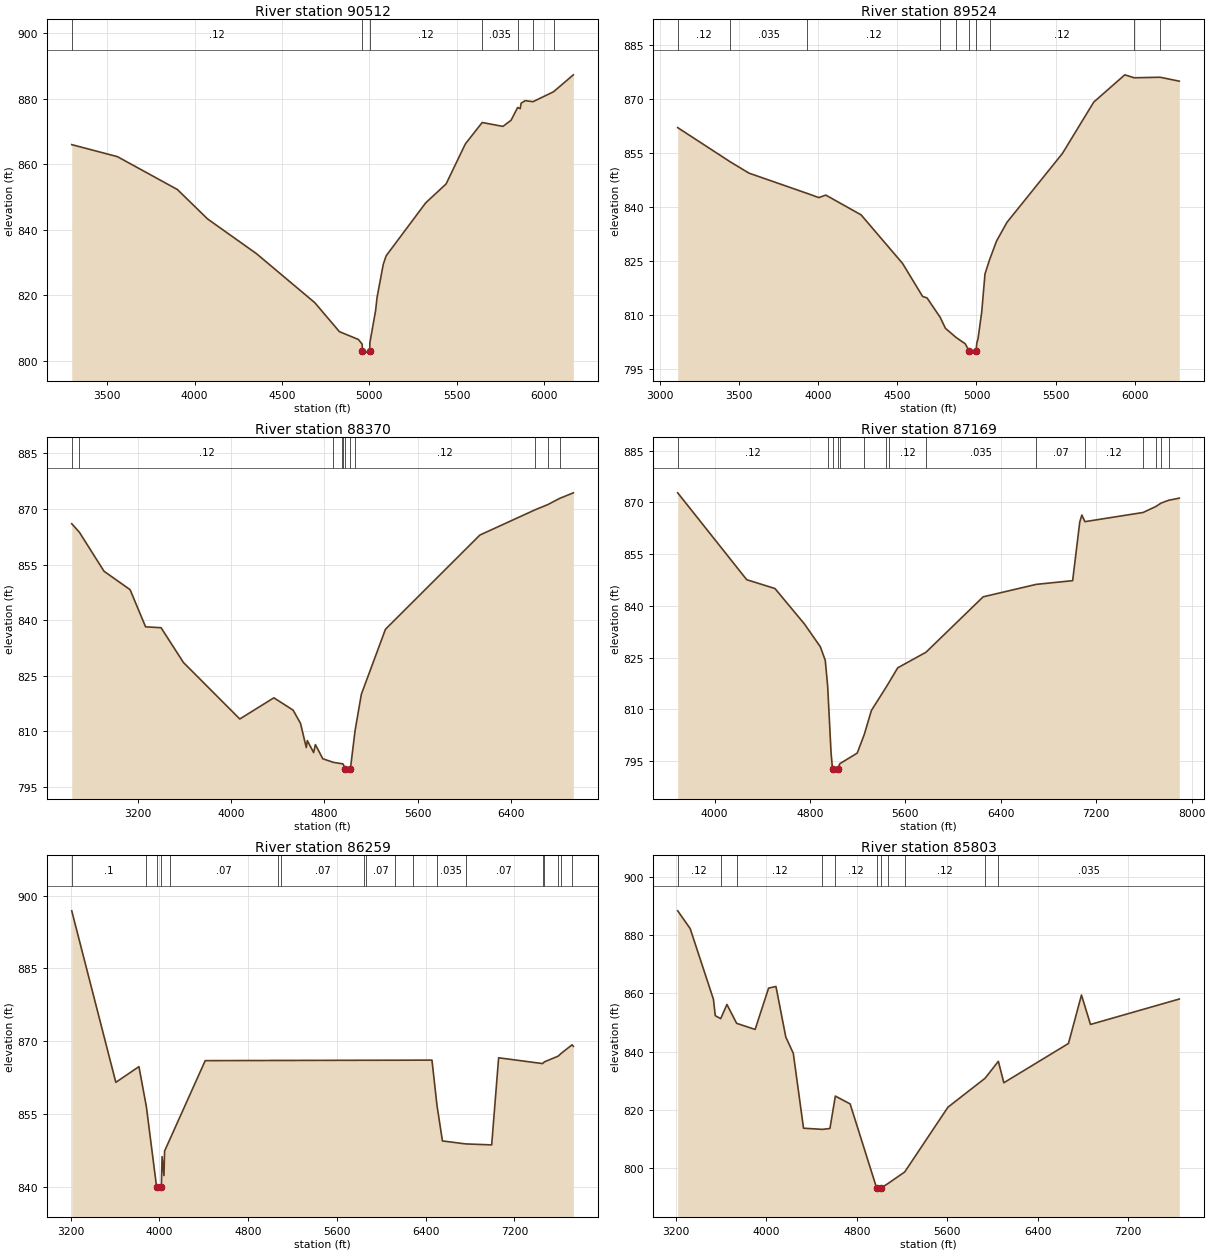
Type RM Length L Ch R = 1 ,90512   ,988,988,988
BEGIN DESCRIPTION:
X18939
END DESCRIPTION:
XS GIS Cut Line= 3
      2206156.96     13797664.83      2204789.75     13797122.29
      2203509.65     13796558.18
#Sta/Elev= 30
  3297.6  866.05    3559  862.38    3902  852.34  4074.8  843.35    4354  832.77
  4687.6  817.81  4828.8  808.94  4937.6  806.54  4959.5  805.08  4960.1  802.87
  4961.1  802.37  5002.6  802.87  5003.2  805.51    5036  815.36  5044.2  819.33
  5079.7  829.46  5096.3  832.09  5322.7  848.27  5439.3  854.04  5549.6  866.28
  5645.9  872.81  5764.4  871.62  5811.1   873.5  5848.7   877.4  5863.2  877.04
  5868.6  878.71    5892  879.48  5936.7  879.17  6054.2   882.2  6167.4  887.37
#Mann= 7 ,-1 , 0
  3297.6     .12       0  4960.1     .05       0  5002.6     .12       0
  5645.9    .035       0  5848.7     .12       0  5936.7     .07       0
  6054.2     .12       0
Bank Sta=4960.1,5002.6
XS Rating Curve= 0 ,0
Exp/Cntr=0.3,0.1

Type RM Length L Ch R = 1 ,89524   ,1154,1154,1154
BEGIN DESCRIPTION:
X18938
END DESCRIPTION:
XS GIS Cut Line= 3
      2206276.31     13797523.79      2205668.66     13796406.14
      2203845.77     13795874.47
#Sta/Elev= 30
  3111.4  862.02  3443.6  852.53  3561.9   849.4    3927  843.82  4003.7  842.61
  4047.4  843.31  4270.7  837.83  4533.2  824.34  4659.5  815.21  4687.7  814.79
  4770.8  809.41    4804  806.35  4872.5  803.78    4929  802.08  4955.1  799.98
  4956.1  799.48  4997.7  799.98    5002  802.22  5009.9  803.46  5033.2  810.84
    5054  821.44  5082.6  825.34    5127  830.56  5192.9  835.75  5543.4  854.85
  5741.5   869.1  5937.7  876.66  5997.4  875.84  6161.1  875.99  6282.4   874.9
#Mann= 10 ,-1 , 0
  3111.4     .12       0  3443.6    .035       0    3927     .12       0
  4770.8     .07       0  4872.5    .035       0  4955.1    .035       0
  4997.7    .035       0  5082.6     .12       0  5997.4    .035       0
  6161.1     .12       0
Bank Sta=4955.1,4997.7
XS Rating Curve= 0 ,0
Exp/Cntr=0.3,0.1

Type RM Length L Ch R = 1 ,88370   ,1201,1201,1201
BEGIN DESCRIPTION:
X18937
END DESCRIPTION:
XS GIS Cut Line= 3
      2208131.76     13796156.57       2205592.7     13795331.92
      2204019.63     13795798.42
#Sta/Elev= 30
  2628.3  866.04  2693.3  863.77    2906  853.21  3129.6  848.25  3262.8  838.22
  3395.9  837.98  3587.7  828.61  4072.3  813.35  4365.2  819.06  4530.2  815.75
  4594.1  812.17  4643.6  805.65  4652.8  807.52  4706.7  804.29    4722  806.44
  4785.9  802.61  4877.5  801.64  4954.7  801.26  4960.3  801.19  4979.7  799.78
  4980.7  799.28  5022.4  799.78    5063  810.23  5116.8  820.01    5324  837.56
  6135.2  862.98  6612.8  869.84  6718.9   871.2  6822.6   872.9  6938.7  874.38
#Mann= 11 ,-1 , 0
  2628.3    .035       0  2693.3     .12       0  4877.5    .035       0
  4954.7     .07       0  4960.3    .035       0  4979.7    .035       0
  5022.4    .035       0    5063     .12       0  6612.8     .07       0
  6718.9     .12       0  6822.6    .035       0
Bank Sta=4979.7,5022.4
XS Rating Curve= 0 ,0
Exp/Cntr=0.3,0.1

Type RM Length L Ch R = 1 ,87169   ,910,910,910
BEGIN DESCRIPTION:
X18936
END DESCRIPTION:
XS GIS Cut Line= 3
      2207947.27     13794344.52      2206080.98     13794800.24
      2203954.24     13795635.75
#Sta/Elev= 30
  3690.6  872.77  4269.4  847.57  4506.1  845.02  4753.2  834.74    4887  828.11
  4928.2  824.16  4948.1  816.71  4976.4   797.5  4988.9  792.56  4989.9  792.06
  5032.1  792.56  5050.2  794.22  5195.8  797.29  5254.5  802.63  5314.9  809.66
  5437.7  816.37  5462.2  817.77  5535.5  822.02  5772.6  826.54    6252  842.61
  6696.9  846.22  7002.3   847.3  7061.9  864.29  7079.3  866.33  7105.2  864.41
  7593.2  867.07  7700.3  868.81    7744   869.8  7807.4  870.61  7896.7  871.23
#Mann= 15 ,-1 , 0
  3690.6     .12       0  4948.1    .035       0  4988.9    .035       0
  5032.1    .035       0  5050.2     .07       0  5254.5     .12       0
  5437.7     .07       0  5462.2     .12       0  5772.6    .035       0
  6696.9     .07       0  7105.2     .12       0  7593.2    .035       0
  7700.3     .07       0    7744    .035       0  7807.4     .07       0
Bank Sta=4988.9,5032.1
XS Rating Curve= 0 ,0
Exp/Cntr=0.3,0.1

Type RM Length L Ch R = 1 ,86259   ,456,456,456
BEGIN DESCRIPTION:
Dry Comal Creek 91.0
END DESCRIPTION:
XS GIS Cut Line= 5
        2207825.       13793125.       2206341.4     13793847.55
      2206212.92     13793938.88      2205849.55     13794229.22
       2204029.8     13795549.17
#Sta/Elev= 30
  3210.8  896.86  3608.1  861.52  3816.5  864.76  3883.8  856.45  3975.2  840.02
  3976.2  839.52  4018.5  840.02  4024.9  846.21  4041.9  842.31  4047.5  847.36
  4094.3  849.74  4413.7  865.99  5067.4  866.03  5093.4  866.03    5849  866.07
  5859.1  866.07  6125.5  866.08  6288.8  866.09  6457.5   866.1  6502.8  856.76
  6551.8  849.45  6759.8  848.84  6995.6  848.63  7058.3  866.58  7454.1  865.39
  7471.4  865.75  7595.8  866.93  7617.9  867.41  7720.2  869.26  7731.8  868.95
#Mann= 18 ,-1 , 0
  3210.8      .1       0  3883.8    .035       0  3975.2     .05       0
  4018.5    .035       0  4094.3     .07       0  5067.4    .035       0
  5093.4     .07       0    5849    .035       0  5859.1     .07       0
  6125.5    .035       0  6288.8     .07       0  6502.8    .035       0
  6759.8     .07       0  7454.1      .1       0  7471.4     .07       0
  7595.8    .035       0  7617.9     .07       0  7720.2    .035       0
Bank Sta=3975.2,4018.5
XS Rating Curve= 0 ,0
Exp/Cntr=0.3,0.1

Type RM Length L Ch R = 1 ,85803   ,560,560,560
BEGIN DESCRIPTION:
Dry Comal Creek 90.0
END DESCRIPTION:
XS GIS Cut Line= 3
      2207589.26     13792708.21        2206025.       13793575.
      2203879.17      13795127.3
#Sta/Elev= 30
    3216  888.29  3326.2  882.22  3532.2  857.94  3548.3  852.34  3596.3  851.32
  3651.3  856.18  3737.5  849.71  3900.8  847.62  4019.9  861.78  4085.1  862.35
  4172.1  845.02  4238.4  839.44    4329  813.75  4495.9  813.35  4562.5  813.65
  4610.4  824.77  4741.1  822.08  4974.7  793.36  4975.7  792.86    5018  793.36
  5073.9  794.72  5223.9  798.75  5606.5  820.96  5934.6  830.87  6052.3  836.69
  6100.7  829.34  6672.3   842.8  6787.5  859.42  6867.2  849.33  7652.8  858.05
#Mann= 11 ,-1 , 0
    3216     .12       0  3596.3     .07       0  3737.5     .12       0
  4495.9     .07       0  4610.4     .12       0  4974.7     .05       0
    5018     .12       0  5073.9      .1       0  5223.9     .12       0
  5934.6     .07       0  6052.3    .035       0
Bank Sta=4974.7,5018
XS Rating Curve= 0 ,0
Exp/Cntr=0.3,0.1