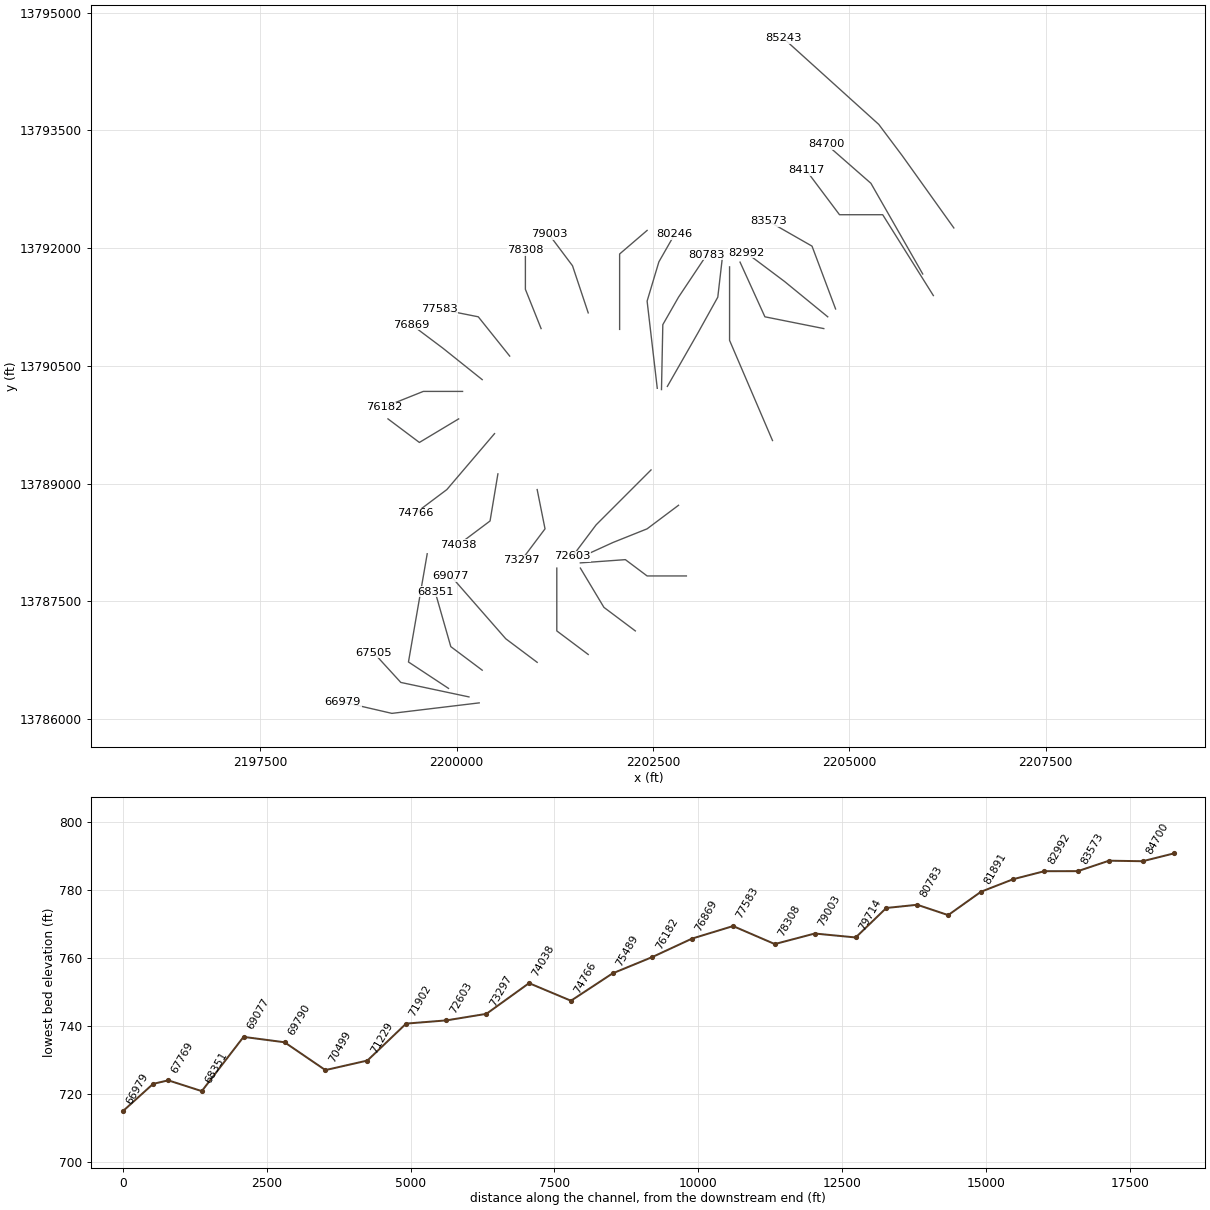
HEC-RAS study Dry Comal Creek.prj: Dry Comal Creek Base Level Engineering

--- Dry Comal Creek.g01 (geometry) --- (continued)

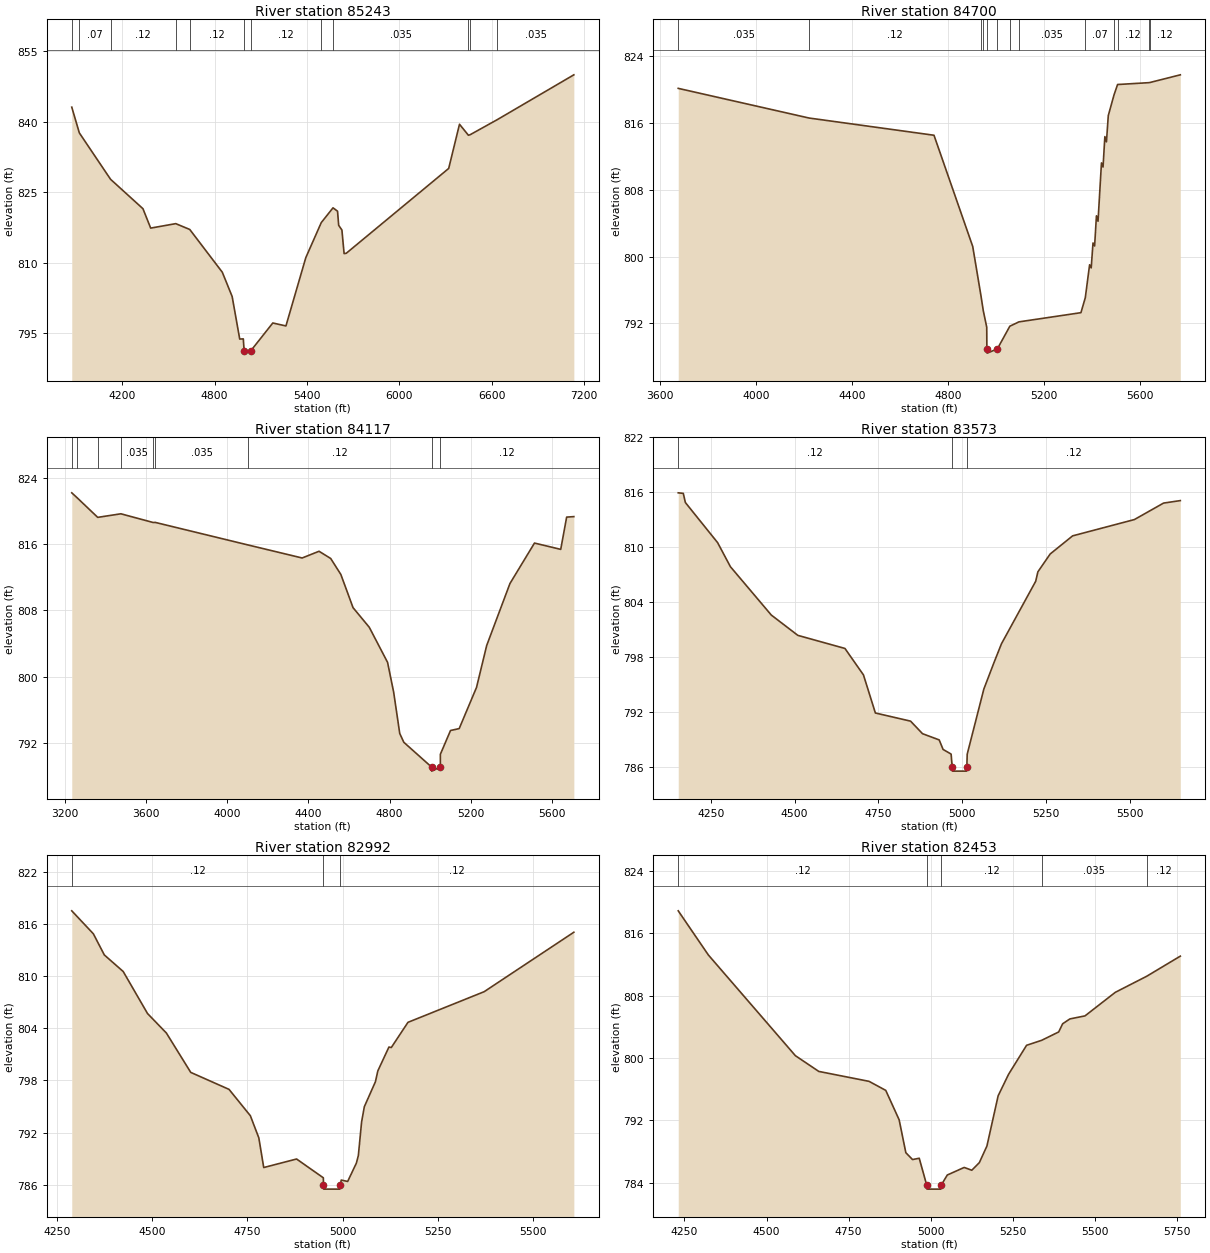
Type RM Length L Ch R = 1 ,85243   ,543,543,543
BEGIN DESCRIPTION:
Dry Comal Creek 89.0
END DESCRIPTION:
XS GIS Cut Line= 5
      2206331.01     13792256.58        2205925.       13792825.
        2205675.       13793175.        2205375.       13793575.
      2204161.63      13794671.1
#Sta/Elev= 30
  3871.1  843.06  3920.3  837.59  4123.3  827.72  4333.7  821.47  4384.1  817.34
  4547.2  818.29  4638.1  817.05  4849.8  807.95  4913.7  802.79  4962.9  793.74
  4986.2  793.78  4991.6  791.25  4992.6  790.75    5035  791.25  5177.9  797.16
  5263.3  796.53  5392.5  811.06    5493  818.51  5569.3  821.65  5598.8  820.94
  5606.2  817.93  5627.2  816.94  5641.4  811.92  5655.6  811.99  6321.4  830.03
  6391.6  839.43  6449.5  837.09  6460.6   837.2  6637.3  840.41  7134.9  849.94
#Mann= 12 ,-1 , 0
  3871.1     .12       0  3920.3     .07       0  4123.3     .12       0
  4547.2    .033       0  4638.1     .12       0  4991.6     .05       0
    5035     .12       0    5493     .07       0  5569.3    .035       0
  6449.5     .12       0  6460.6     .07       0  6637.3    .035       0
Bank Sta=4991.6,5035
XS Rating Curve= 0 ,0
Exp/Cntr=0.3,0.1

Type RM Length L Ch R = 1 ,84700   ,583,583,583
BEGIN DESCRIPTION:
Dry Comal Creek 88.0
END DESCRIPTION:
XS GIS Cut Line= 5
      2205934.79     13791670.38        2205475.       13792475.
        2205275.       13792825.        2204875.       13793175.
      2204702.55      13793325.9
#Sta/Elev= 30
  3675.8  820.13  4220.6  816.58  4740.7  814.52    4902  801.21  4936.6  795.26
    4946  793.52  4960.3  791.55  4960.9  788.95  4961.9  788.45  5004.4  788.95
  5056.5  791.67  5094.3  792.19  5352.5  793.29  5370.7  795.08  5388.6  799.02
  5395.3  798.65  5402.8  801.63  5409.5  801.27  5417.1  804.88  5423.7  804.23
    5438  811.21  5444.6  810.72  5452.2  814.36  5458.8  813.73  5466.4  816.87
    5490  819.32  5505.1  820.59  5634.4  820.81  5639.5  820.83  5766.3  821.75
#Mann= 13 ,-1 , 0
  3675.8    .035       0  4220.6     .12       0  4936.6     .07       0
    4946    .035       0  4960.9    .035       0  5004.4    .035       0
  5056.5     .07       0  5094.3    .035       0  5370.7     .07       0
    5490    .035       0  5505.1     .12       0  5634.4     .07       0
  5639.5     .12       0
Bank Sta=4960.9,5004.4
XS Rating Curve= 0 ,0
Exp/Cntr=0.3,0.1

Type RM Length L Ch R = 1 ,84117   ,544,544,544
BEGIN DESCRIPTION:
Dry Comal Creek 87.0
END DESCRIPTION:
XS GIS Cut Line= 5
      2206070.12     13791395.31        2205425.       13792425.
        2204875.       13792425.        2204575.       13792825.
      2204450.62     13792990.85
#Sta/Elev= 30
  3234.9  822.18  3262.8  821.55  3362.7  819.22  3476.7  819.65  3635.8   818.6
  3646.3  818.61  4101.3   815.9  4369.3  814.32  4452.5  815.13    4510  814.26
    4560  812.33    4620  808.33    4700  805.96    4790  801.73    4820  798.14
    4850  793.15    4870  792.09  5006.4  789.11  5007.4  788.61  5049.9  789.11
    5050  790.64    5100  793.51  5142.7  793.74  5228.1  798.71  5278.1  803.76
  5392.7  811.24  5513.5  816.12  5642.7  815.36  5671.9  819.25  5707.3  819.31
#Mann= 9 ,-1 , 0
  3234.9     .07       0  3262.8    .035       0  3362.7     .07       0
  3476.7    .035       0  3635.8     .07       0  3646.3    .035       0
  4101.3     .12       0  5006.4     .05       0  5049.9     .12       0
Bank Sta=5006.4,5049.9
XS Rating Curve= 0 ,0
Exp/Cntr=0.3,0.1

Type RM Length L Ch R = 1 ,83573   ,581,581,581
BEGIN DESCRIPTION:
Dry Comal Creek 86.0
END DESCRIPTION:
XS GIS Cut Line= 4
        2204825.     13791225.01        2204525.       13792025.
        2204175.       13792225.      2203966.02     13792344.42
#Sta/Elev= 30
  4152.9  815.93    4168  815.87  4174.2  814.87  4270.4  810.49  4308.6  807.86
  4430.6  802.58  4509.8  800.36  4650.4  798.93  4705.6  796.04  4741.2  791.88
  4846.2  790.99  4881.8  789.62  4931.6  788.94  4943.2   787.9  4967.2  787.39
  4970.3  786.03  4971.3  785.53  5013.1  785.53  5014.1  786.03  5015.2  787.38
  5064.9   794.5  5095.8  797.45  5117.4  799.44  5219.6  806.27  5226.1   807.3
  5262.8  809.25  5329.8  811.23  5514.1  813.01  5601.2  814.81  5651.1  815.08
#Mann= 3 ,-1 , 0
  4152.9     .12       0  4970.3     .05       0  5014.1     .12       0
Bank Sta=4970.3,5014.1
XS Rating Curve= 0 ,0
Exp/Cntr=0.3,0.1

Type RM Length L Ch R = 1 ,82992   ,539,539,539
BEGIN DESCRIPTION:
Dry Comal Creek 85.0
END DESCRIPTION:
XS GIS Cut Line= 4
      2204725.03     13791124.98        2204175.       13791575.
        2203775.       13791875.      2203689.22     13791939.34
#Sta/Elev= 30
  4289.1  817.49  4345.8  814.85  4374.6  812.42  4424.1  810.52    4488  805.69
  4537.5  803.45  4601.4  798.93  4701.9  796.98  4757.9  793.95  4780.1  791.41
    4793     788  4879.2  788.98  4949.5  786.82  4949.8  786.02  4950.8  785.52
  4992.7  785.52  4993.7  786.02  4996.5  786.56  5013.3   786.4  5036.2  788.51
  5041.4  789.39  5049.8  793.22  5057.1  794.99  5086.2  797.86  5092.5   799.1
  5121.6  801.84  5127.9  801.79  5171.6  804.68  5371.6   808.2    5607  815.03
#Mann= 3 ,-1 , 0
  4289.1     .12       0  4949.8     .05       0  4993.7     .12       0
Bank Sta=4949.8,4993.7
XS Rating Curve= 0 ,0
Exp/Cntr=0.3,0.1

Type RM Length L Ch R = 1 ,82453   ,562,562,562
BEGIN DESCRIPTION:
Dry Comal Creek 84.0
END DESCRIPTION:
XS GIS Cut Line= 4
        2204675.       13790975.        2203925.       13791125.
        2203675.       13791675.      2203608.46     13791821.38
#Sta/Elev= 30
    4231  818.86  4322.8   813.2  4587.9  800.29  4659.3  798.27  4812.3     797
  4863.3  795.84  4904.1  792.07  4924.5  787.85  4944.9  786.97  4965.3  787.14
  4988.2  783.68  4989.2  783.18  5031.1  783.18  5032.1  783.68  5050.8  784.99
  5102.4  785.96  5125.5   785.6  5148.5  786.58  5171.6  788.71  5205.7  795.14
  5237.5   797.9  5292.4  801.62  5338.4  802.26  5390.2  803.33  5402.3  804.38
  5424.3     805  5470.4  805.39  5562.7  808.41  5658.4  810.47  5760.8  813.05
#Mann= 5 ,-1 , 0
    4231     .12       0  4988.2     .05       0  5032.1     .12       0
  5338.4    .035       0  5658.4     .12       0
Bank Sta=4988.2,5032.1
XS Rating Curve= 0 ,0
Exp/Cntr=0.3,0.1

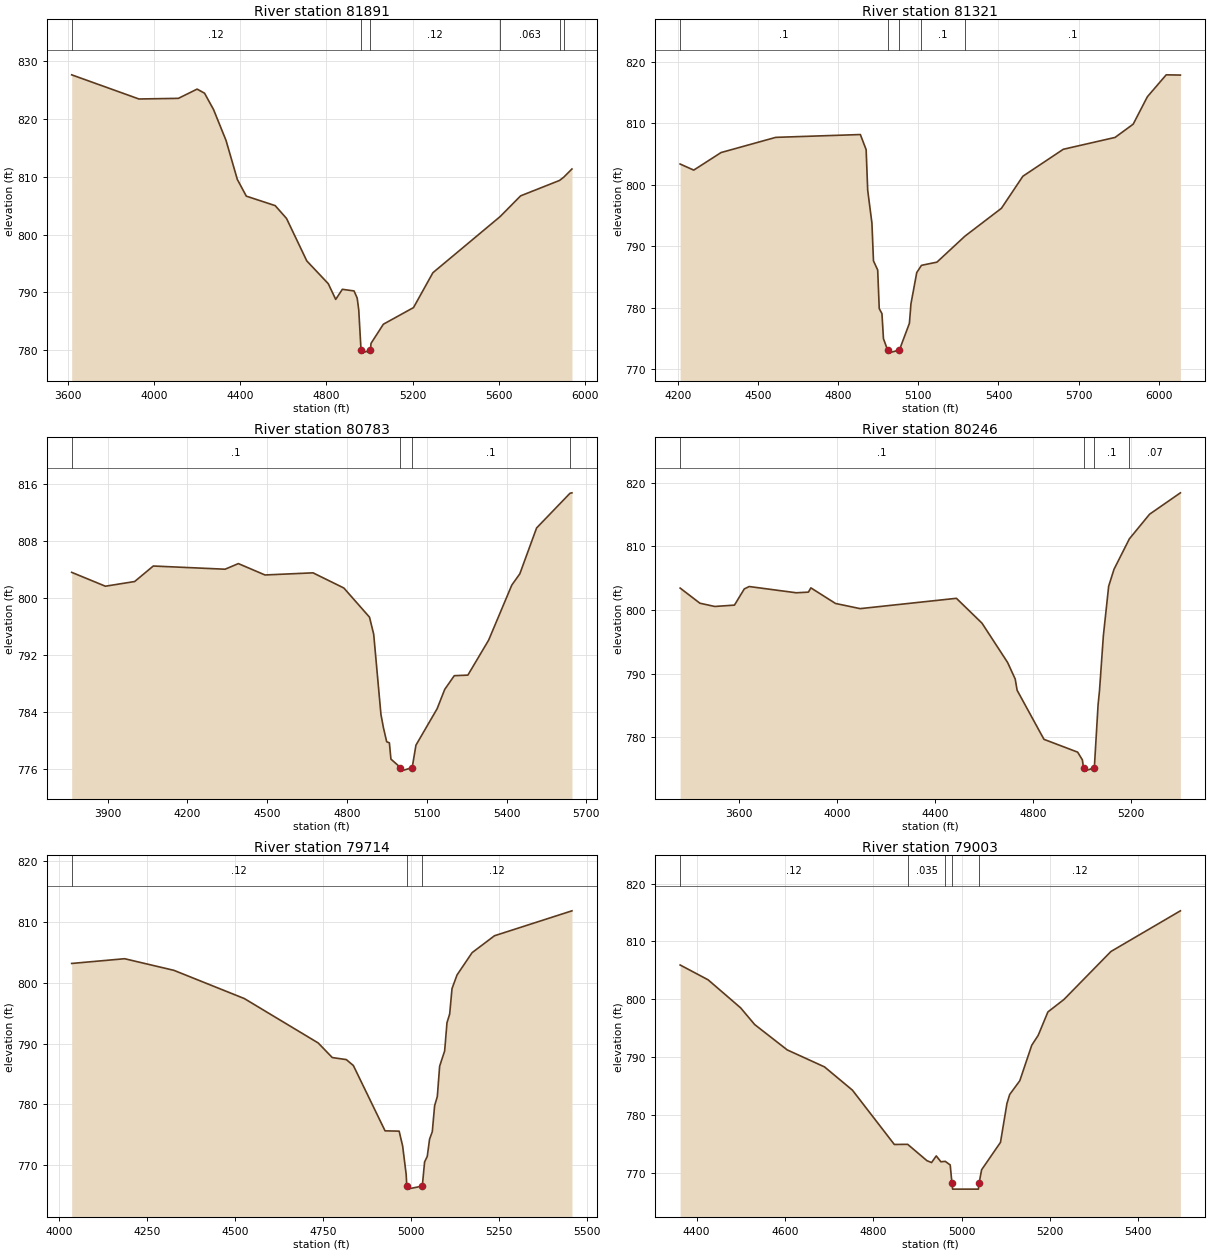
Type RM Length L Ch R = 1 ,81891   ,570,570,570
BEGIN DESCRIPTION:
Dry Comal Creek 83.0
END DESCRIPTION:
XS GIS Cut Line= 5
      2204021.68      13789549.4        2203775.       13790125.
        2203475.       13790825.        2203475.       13791525.
        2203475.     13791760.99
#Sta/Elev= 30
  3616.7  827.63  3929.2  823.45  4112.4  823.56  4199.4  825.16  4233.9  824.45
  4275.6  821.63  4333.6  816.29  4386.2  809.53  4427.9  806.64  4562.1     805
  4614.7  802.78  4708.9  795.43  4808.7  791.49  4843.1  788.78    4874  790.52
  4928.4  790.24  4942.9     789  4950.1  786.99  4960.8  779.98  4961.8  779.48
  5004.7  779.98    5007  781.16  5064.5  784.48  5204.5  787.36  5294.5  793.39
  5607.1  803.11    5702  806.69    5883  809.36  5902.3  809.92  5940.5  811.34
#Mann= 6 ,-1 , 0
  3616.7     .12       0  4960.8     .05       0  5004.7     .12       0
  5607.1    .063       0    5883    .035       0  5902.3     .12       0
Bank Sta=4960.8,5004.7
XS Rating Curve= 0 ,0
Exp/Cntr=0.3,0.1

Type RM Length L Ch R = 1 ,81321   ,538,538,538
BEGIN DESCRIPTION:
Dry Comal Creek 82.0
END DESCRIPTION:
XS GIS Cut Line= 5
      2202682.93     13790238.88        2202875.       13790575.
        2203075.       13790925.        2203325.       13791375.
        2203390.     13791937.74
#Sta/Elev= 30
  4209.1  803.39  4260.1   802.4  4362.3  805.26  4566.7  807.73  4883.4  808.19
    4905  805.72  4910.8  799.12  4926.6  793.79  4932.4  787.63  4948.2  786.14
    4954  779.85  4964.1  779.04  4969.8  774.95  4985.3  773.11  4986.3  772.61
  5029.3  773.11  5066.8  777.46  5072.6  780.63  5094.3  785.73    5112   786.9
  5169.8  787.42  5274.3  791.64  5411.2  796.19  5491.2   801.4  5642.4  805.79
  5836.2  807.72    5904  809.88    5957  814.34  6027.5  817.91  6080.6  817.87
#Mann= 5 ,-1 , 0
  4209.1      .1       0  4985.3     .05       0  5029.3      .1       0
    5112      .1       0  5274.3      .1       0
Bank Sta=4985.3,5029.3
XS Rating Curve= 0 ,0
Exp/Cntr=0.3,0.1

Type RM Length L Ch R = 1 ,80783   ,537,537,537
BEGIN DESCRIPTION:
Dry Comal Creek 81.0
END DESCRIPTION:
XS GIS Cut Line= 5
       2202608.1      13790198.2        2202625.       13791025.
        2202825.       13791375.        2203125.       13791825.
      2203186.28     13791916.92
#Sta/Elev= 30
  3764.7   803.6  3891.5  801.65  4001.6  802.31  4071.6  804.49  4341.6  804.04
  4391.6  804.83  4491.7  803.23  4672.3  803.53  4788.2   801.4  4884.7   797.3
  4900.5   794.9  4927.8  783.61  4937.2  781.75  4949.4  779.78  4959.5  779.63
  4965.3  777.34  5001.3  776.15  5002.3  775.65  5045.3  776.15  5059.4   779.3
    5139  784.42  5167.6  787.14  5203.6  789.07  5254.7  789.15  5332.8  794.07
  5419.9  801.81    5450  803.39  5513.1  809.84  5638.8  814.72  5646.1  814.78
#Mann= 4 ,-1 , 0
  3764.7      .1       0  5001.3     .05       0  5045.3      .1       0
  5638.8     .07       0
Bank Sta=5001.3,5045.3
XS Rating Curve= 0 ,0
Exp/Cntr=0.3,0.1

Type RM Length L Ch R = 1 ,80246   ,532,532,532
BEGIN DESCRIPTION:
Dry Comal Creek 80.0
END DESCRIPTION:
XS GIS Cut Line= 4
      2202554.29     13790214.69        2202425.       13791325.
        2202575.       13791825.      2202774.98     13792174.97
#Sta/Elev= 30
  3359.7  803.45  3440.5  801.07    3501  800.56  3581.5  800.77  3621.8  803.32
  3641.9  803.69  3833.6  802.71  3883.5  802.81  3893.6  803.48  3994.3  801.03
  4094.9  800.22  4487.9  801.84  4592.4  797.94  4696.8  791.78  4728.1  789.16
  4735.9   787.4  4845.5   779.7    4983  777.69  5002.4  776.47    5007  775.21
    5008  774.71  5051.1  775.21  5066.5  785.15  5072.2  787.32  5088.1     796
  5109.7  803.74  5131.3  806.38  5194.1  811.17  5276.7  815.04  5402.6   818.4
#Mann= 4 ,-1 , 0
  3359.7      .1       0    5007     .05       0  5051.1      .1       0
  5194.1     .07       0
Bank Sta=5007,5051.1
XS Rating Curve= 0 ,0
Exp/Cntr=0.3,0.1

Type RM Length L Ch R = 1 ,79714   ,711,711,711
BEGIN DESCRIPTION:
Dry Comal Creek 79.0
END DESCRIPTION:
XS GIS Cut Line= 4
        2202075.     13790964.59        2202075.       13791525.
        2202075.       13791925.      2202425.01     13792225.01
#Sta/Elev= 30
  4035.4  803.17  4185.8  803.95  4325.8  802.04  4525.8   797.4  4735.8  790.09
  4775.8  787.69  4815.8  787.35  4835.8  786.37  4925.8  775.63  4965.8  775.58
  4975.8  773.12  4985.8  768.46  4987.5  766.54  4988.5  766.04  5031.6  766.54
  5038.1  770.51  5045.7  771.43  5052.3  774.27    5060  775.49  5066.6  779.76
  5074.3  781.28  5080.9  786.27  5095.1  788.78  5101.7  793.41  5109.4  794.86
    5116  799.03  5130.3  801.28  5173.1  804.95  5236.7  807.73  5456.8  811.83
#Mann= 3 ,-1 , 0
  4035.4     .12       0  4987.5     .05       0  5031.6     .12       0
Bank Sta=4987.5,5031.6
XS Rating Curve= 0 ,0
Exp/Cntr=0.3,0.1

Type RM Length L Ch R = 1 ,79003   ,695,695,695
BEGIN DESCRIPTION:
Dry Comal Creek 78.0
END DESCRIPTION:
XS GIS Cut Line= 3
        2201675.     13791174.99        2201475.       13791775.
      2201174.98     13792175.02
#Sta/Elev= 30
  4362.8  805.94  4426.1  803.38  4499.8  798.53  4531.5  795.65  4605.3  791.26
  4689.6  788.33  4752.8  784.31  4847.7  774.92    4878  774.94  4921.5  772.12
    4932  771.79  4942.6  772.94  4953.1  771.93    4963     772  4974.2  771.38
  4978.2   768.2  4979.7   767.2    5038   767.2  5039.5   768.2  5045.3  770.55
    5088  775.28  5102.6  781.99  5108.8  783.55  5131.7  785.93  5158.8  792.07
  5173.4  793.78  5195.3  797.82  5231.7  799.98    5338  808.27  5495.3   815.3
#Mann= 5 ,-1 , 0
  4362.8     .12       0    4878    .035       0    4963     .12       0
  4978.2     .05       0  5039.5     .12       0
Bank Sta=4978.2,5039.5
XS Rating Curve= 0 ,0
Exp/Cntr=0.3,0.1

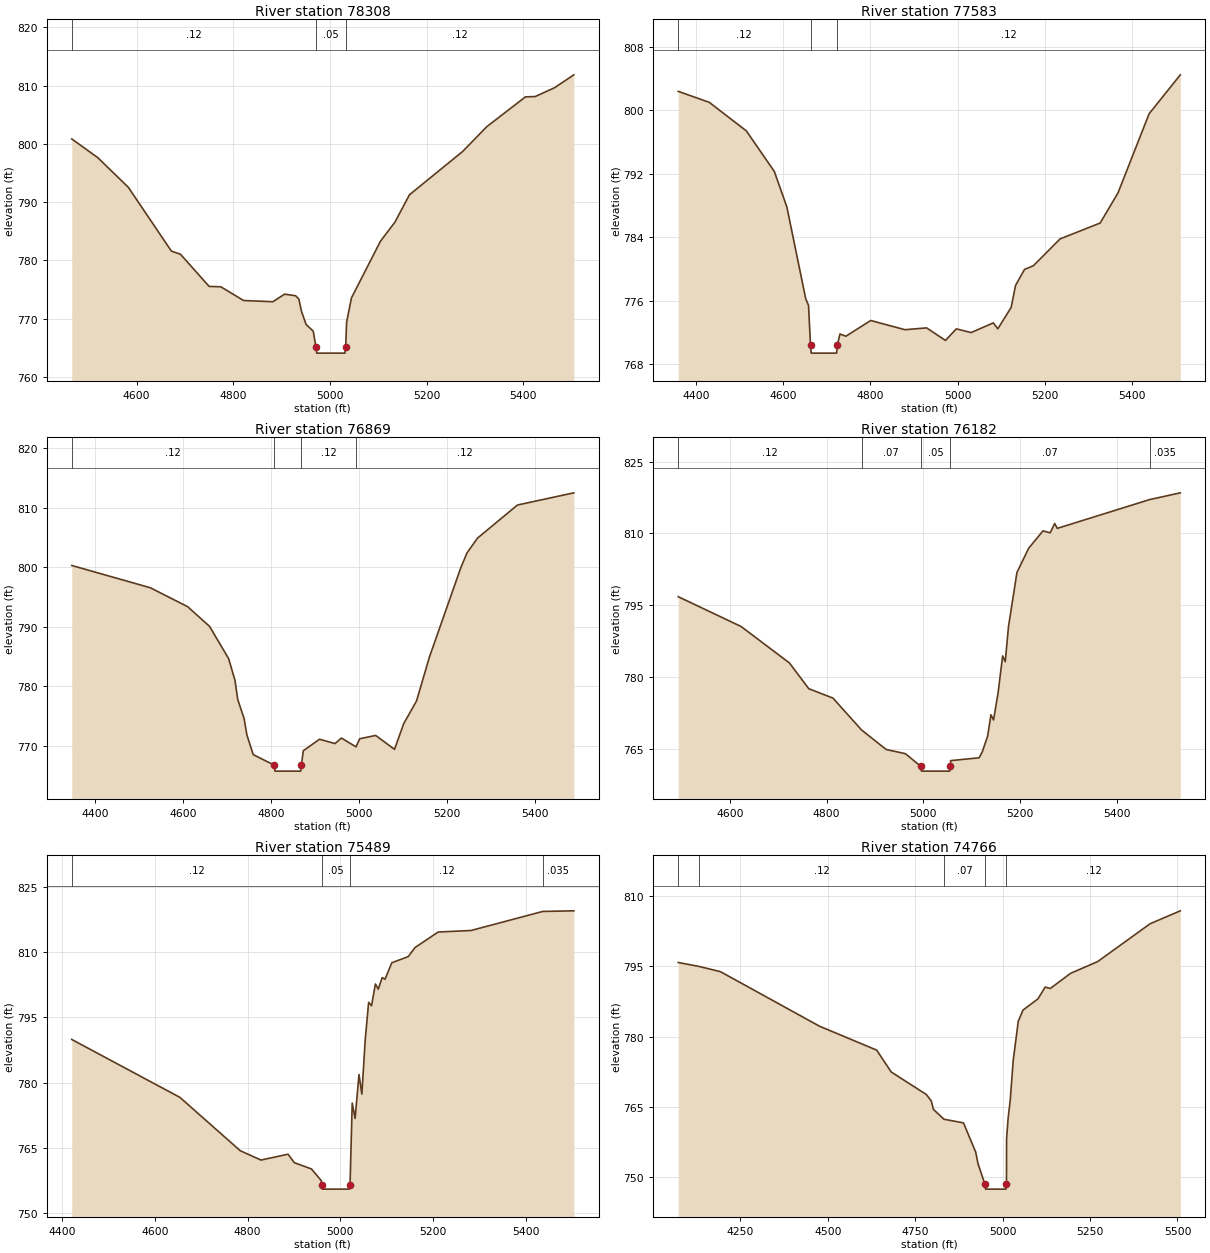
Type RM Length L Ch R = 1 ,78308   ,725,725,725
BEGIN DESCRIPTION:
Dry Comal Creek 77.0
END DESCRIPTION:
XS GIS Cut Line= 3
        2201075.     13790975.01        2200875.       13791475.
        2200875.     13791974.99
#Sta/Elev= 30
    4466  800.85  4519.8  797.64  4583.1  792.54    4672  781.61  4690.8  781.07
  4750.1  775.55  4774.3  775.48  4821.4  773.13    4882  772.92  4906.2  774.22
  4929.1  773.94  4935.8  773.36  4941.2  771.25  4950.7  769.02  4965.5  767.86
  4971.2   765.1  4972.7   764.1    5031   764.1  5032.5   765.1  5034.5  769.41
  5044.5  773.57  5104.5   783.3  5134.5  786.58  5164.5  791.27  5274.5   798.7
  5324.5  802.96  5404.5  808.07  5424.5  808.12  5464.5  809.63  5504.5  811.85
#Mann= 3 ,-1 , 0
    4466     .12       0  4971.2     .05       0  5032.5     .12       0
Bank Sta=4971.2,5032.5
XS Rating Curve= 0 ,0
Exp/Cntr=0.3,0.1

Type RM Length L Ch R = 1 ,77583   ,714,714,714
BEGIN DESCRIPTION:
Dry Comal Creek 76.0
END DESCRIPTION:
XS GIS Cut Line= 3
      2200674.98     13790625.03        2200275.       13791125.
      2199774.98       13791225.
#Sta/Elev= 30
  4359.7  802.37  4430.9  800.98  4515.7  797.39  4579.8  792.28  4608.6   787.8
  4651.8  776.23  4658.2  775.41  4662.7  770.39  4664.2  769.39  4722.6  769.39
  4724.1  770.39  4730.2   771.8  4743.8  771.52  4800.7   773.5  4879.1  772.34
  4928.7  772.57    4972  770.99  4996.8  772.45  5030.6  771.98  5081.6   773.2
  5091.8  772.45  5122.3  775.14  5132.5  777.92  5152.9  779.93  5173.3   780.4
  5234.5  783.78  5326.3  785.78  5367.1  789.57  5438.5  799.55  5509.9  804.45
#Mann= 3 ,-1 , 0
  4359.7     .12       0  4662.7     .05       0  4724.1     .12       0
Bank Sta=4662.7,4724.1
XS Rating Curve= 0 ,0
Exp/Cntr=0.3,0.1

Type RM Length L Ch R = 1 ,76869   ,687,687,687
BEGIN DESCRIPTION:
Dry Comal Creek 75.0
END DESCRIPTION:
XS GIS Cut Line= 3
      2200325.02     13790324.98        2199825.       13790725.
      2199425.03     13791024.98
#Sta/Elev= 30
    4347  800.27  4525.5  796.52  4610.4  793.33    4660  790.03  4703.2  784.62
  4717.6  780.99    4724  777.73  4738.4  774.55  4744.8  771.76  4759.2  768.47
    4807   766.7  4808.5   765.7  4866.9   765.7  4868.4   766.7  4872.9  769.13
  4909.7  771.06  4944.9  770.33  4959.3  771.26  4992.6  769.78  5000.9  771.14
  5037.3   771.7    5080  769.36  5100.9  773.68    5130  777.49  5159.2  784.85
    5230  799.78  5244.6  802.38  5268.6  804.87  5359.2  810.43  5487.3  812.48
#Mann= 4 ,-1 , 0
    4347     .12       0    4807     .05       0  4868.4     .12       0
  4992.6     .12       0
Bank Sta=4807,4868.4
XS Rating Curve= 0 ,0
Exp/Cntr=0.3,0.1

Type RM Length L Ch R = 1 ,76182   ,693,693,693
BEGIN DESCRIPTION:
Dry Comal Creek 74.0
END DESCRIPTION:
XS GIS Cut Line= 3
      2200075.03       13790175.        2199575.       13790175.
      2199075.04     13789975.02
#Sta/Elev= 30
  4493.1  796.76  4623.1  790.53  4723.1  782.91  4763.1  777.53  4813.1  775.57
  4872.2  768.91  4923.1  764.83  4963.1  763.94  4994.7   761.3  4996.2   760.3
  5054.7   760.3  5056.2   761.3  5056.4  762.49  5115.6  763.09  5122.4  764.43
  5133.1  767.64  5139.9  772.07  5145.3  770.99  5154.7  776.66  5164.1  784.39
  5169.5  783.17  5176.2  790.49  5193.7  801.83    5218  806.89  5247.6  810.52
  5262.4  810.11  5271.8  812.06  5277.2  811.04  5468.3  817.06  5531.6  818.47
#Mann= 5 ,-1 , 0
  4493.1     .12       0  4872.2     .07       0  4994.7     .05       0
  5056.2     .07       0  5468.3    .035       0
Bank Sta=4994.7,5056.2
XS Rating Curve= 0 ,0
Exp/Cntr=0.3,0.1

Type RM Length L Ch R = 1 ,75489   ,723,723,723
BEGIN DESCRIPTION:
Dry Comal Creek 73.0
END DESCRIPTION:
XS GIS Cut Line= 3
      2200025.02     13789825.01        2199525.       13789525.
      2199125.02     13789824.99
#Sta/Elev= 30
  4420.8  789.93  4654.1   776.6  4784.3  764.32    4829  762.17  4887.3  763.52
  4900.9  761.57  4937.8  760.13  4959.2  757.41  4959.6  756.48  4961.1  755.48
  5019.6  755.48  5021.1  756.48  5025.8  775.29    5032  771.76  5040.4  781.86
  5046.6  777.36  5053.9  789.95  5061.2  798.47  5067.5  797.71  5075.8   802.7
    5082  801.51  5090.4  804.16  5096.6   803.8  5111.2  807.59  5146.6     809
  5161.2  811.08  5211.2  814.66    5282  815.01  5436.9   819.4  5503.9  819.54
#Mann= 4 ,-1 , 0
  4420.8     .12       0  4959.6     .05       0  5021.1     .12       0
  5436.9    .035       0
Bank Sta=4959.6,5021.1
XS Rating Curve= 0 ,0
Exp/Cntr=0.3,0.1

Type RM Length L Ch R = 1 ,74766   ,728,728,728
BEGIN DESCRIPTION:
Dry Comal Creek 72.0
END DESCRIPTION:
XS GIS Cut Line= 3
      2200482.03     13789637.48        2199875.       13788925.
      2199475.01     13788625.01
#Sta/Elev= 30
  4072.1  795.83  4131.3  794.99  4192.8  793.87  4476.1  782.23  4639.7  777.12
  4681.4  772.44  4781.4  767.66  4795.6  766.31  4802.2  764.45  4832.2  762.36
  4887.9  761.59    4923  755.33  4929.6  752.85  4949.4  748.44  4950.9  747.44
  5009.4  747.44  5010.9  748.44  5011.2  758.13  5015.4   762.4  5021.7  766.46
    5030  774.78  5044.6  783.26  5058.1  785.66  5100.8  788.05  5121.7  790.58
  5136.2  790.27  5194.6  793.53  5271.7  796.02  5421.7   804.1  5508.1  806.86
#Mann= 5 ,-1 , 0
  4072.1    .035       0  4131.3     .12       0  4832.2     .07       0
  4949.4     .05       0  5010.9     .12       0
Bank Sta=4949.4,5010.9
XS Rating Curve= 0 ,0
Exp/Cntr=0.3,0.1

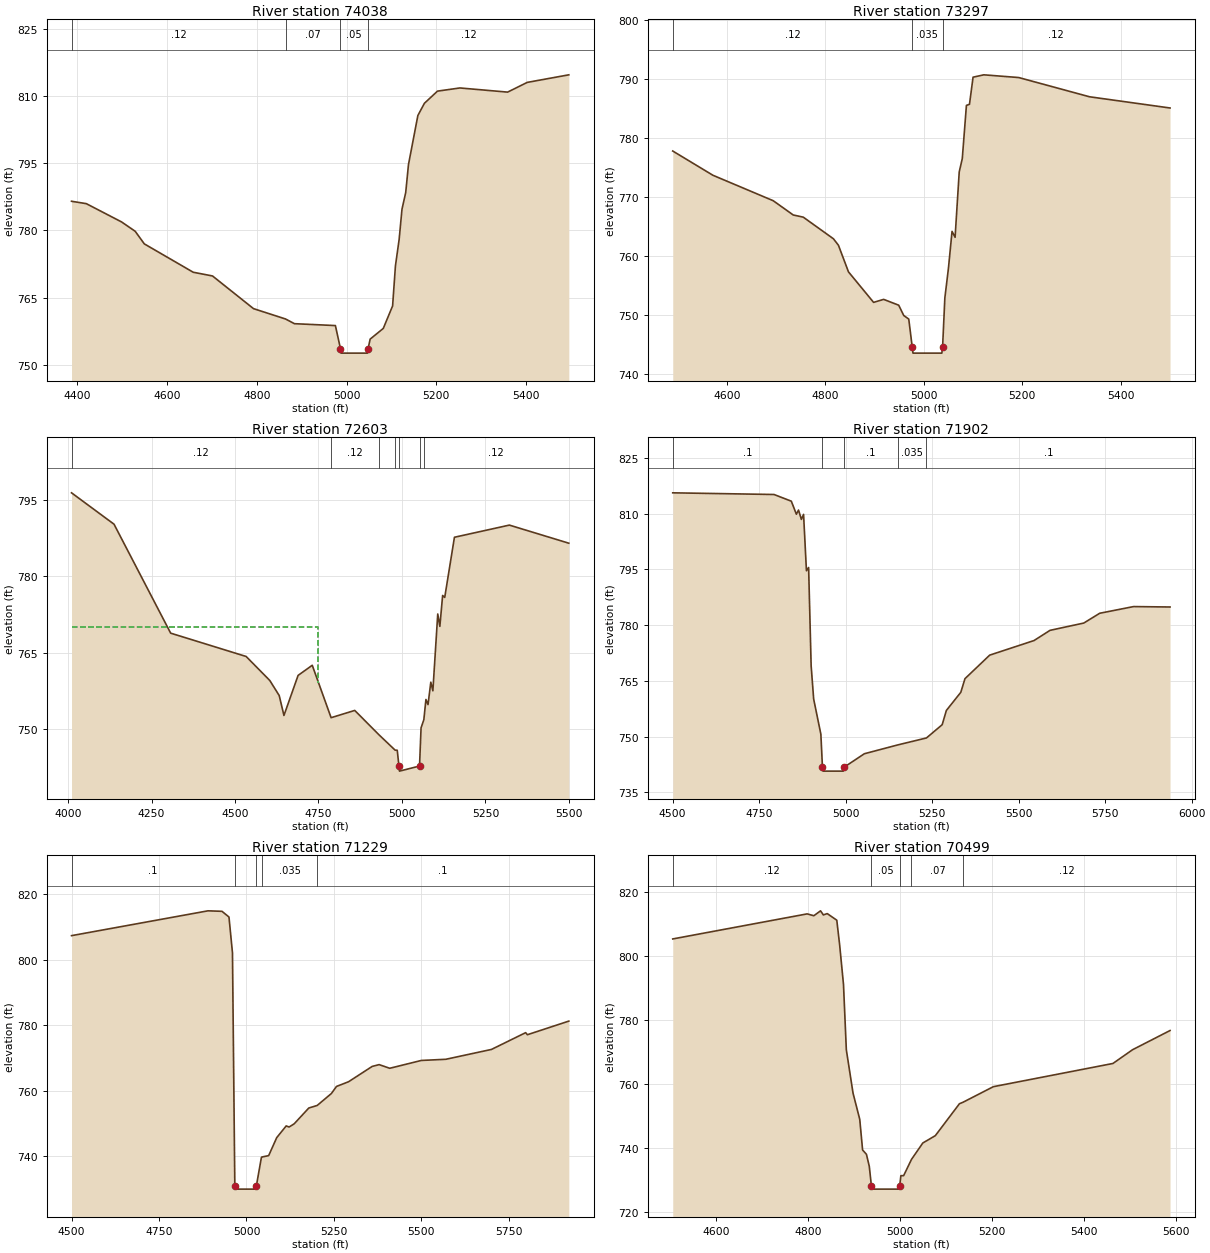
Type RM Length L Ch R = 1 ,74038   ,741,741,741
BEGIN DESCRIPTION:
Dry Comal Creek 71.0
END DESCRIPTION:
XS GIS Cut Line= 3
      2200524.99     13789124.97        2200425.       13788525.
      2200025.03     13788225.02
#Sta/Elev= 30
  4387.1   786.5    4420  785.97  4498.6  781.89    4529   779.8  4549.3  776.99
  4658.3  770.66  4701.3  769.83  4792.6  762.54    4864  760.23  4883.8  759.18
  4975.1  758.76  4986.4  753.61  4987.9  752.61  5046.5  752.61    5048  753.61
  5052.6  755.74  5081.8  758.12  5102.6  763.14  5108.9  772.07  5117.2  778.01
  5123.5  784.73  5131.8  788.44    5138   794.7  5158.9  805.64  5173.5  808.37
  5202.6  811.08  5252.6  811.79  5358.9  810.86  5402.6  813.03  5495.3  814.72
#Mann= 4 ,-1 , 0
  4387.1     .12       0    4864     .07       0  4986.4     .05       0
    5048     .12       0
Bank Sta=4986.4,5048
XS Rating Curve= 0 ,0
Exp/Cntr=0.3,0.1

Type RM Length L Ch R = 1 ,73297   ,694,694,694
BEGIN DESCRIPTION:
Dry Comal Creek 70.0
END DESCRIPTION:
XS GIS Cut Line= 3
        2201025.     13788924.99        2201125.       13788425.
        2200825.       13788025.
#Sta/Elev= 30
  4490.1  777.84  4571.7  773.73  4694.1  769.42  4734.8     767  4755.2  766.63
  4816.4  762.97  4826.6  761.87    4847  757.36    4898  752.19  4918.4   752.7
    4949  751.71  4959.2  749.97  4969.4  749.36  4976.5  744.59    4978  743.59
  5036.6  743.59  5038.1  744.59  5042.7  752.93    5050  757.98  5057.3  764.22
  5063.5  763.22  5071.9   774.3  5078.1  776.55  5086.5  785.57  5092.7  785.75
    5100  790.35  5121.9  790.75  5192.7  790.29  5336.5  787.03    5500  785.13
#Mann= 3 ,-1 , 0
  4490.1     .12       0  4976.5    .035       0  5038.1     .12       0
Bank Sta=4976.5,5038.1
XS Rating Curve= 0 ,0
Exp/Cntr=0.3,0.1

Type RM Length L Ch R = 1 ,72603   ,701,701,701
BEGIN DESCRIPTION:
Dry Comal Creek 69.0
END DESCRIPTION:
XS GIS Cut Line= 3
      2202474.99     13789174.99        2201775.       13788475.
      2201475.02     13788075.02
#Sta/Elev= 30
  4010.1  796.41  4137.4  790.24  4307.1  768.81  4533.3  764.22  4604.1   759.5
  4632.3  756.54  4646.5  752.62  4688.9   760.5  4731.3  762.49  4787.8  752.18
  4858.6  753.61  4931.3  748.81  4979.7  745.79  4985.9  745.78  4991.1  742.67
  4992.6  741.67  5052.7  742.67  5057.3  750.18  5065.6  751.78  5071.9  755.76
  5078.2  754.76  5086.5  759.17  5092.7  757.47  5107.3  772.58  5113.6  770.14
  5121.9  776.22  5128.2  775.84  5157.3  787.67  5321.9  790.06    5500   786.5
#Mann= 7 ,-1 , 0
  4010.1     .12       0  4787.8     .12       0  4931.3     .12       0
  4979.7     .12       0  4991.1     .05       0  5052.7     .12       0
  5065.6     .12       0
#XS Ineff= 2 , 0
       0    4750     770               0
Permanent Ineff=
       F       F
Bank Sta=4991.1,5052.7
XS Rating Curve= 0 ,0
Exp/Cntr=0.3,0.1

Type RM Length L Ch R = 1 ,71902   ,673,673,673
BEGIN DESCRIPTION:
Dry Comal Creek 68.0
END DESCRIPTION:
XS GIS Cut Line= 4
      2202824.98     13788724.98        2202425.       13788425.
      2201991.15     13788251.46      2201563.58      13788056.4
#Sta/Elev= 30
  4500.3  815.63    4793  815.18    4843  813.38  4857.6  809.87  4863.8  810.99
  4872.1  808.48  4878.4  809.83  4886.7  794.65    4893  795.53  4900.3  769.06
  4907.6  760.12  4928.4  750.65    4933  741.72  4934.5  740.72  4993.1  740.72
  4994.6  741.72  5054.1   745.4  5150.5  747.77  5233.6  749.65    5279  753.22
  5291.1  757.05  5332.8  761.93  5344.9  765.61  5416.3  771.94  5544.5  775.87
  5590.6  778.61  5688.3  780.58  5734.3  783.21    5832  785.01  5937.5   784.9
#Mann= 5 ,-1 , 0
  4500.3      .1       0    4933     .05       0  4994.6      .1       0
  5150.5    .035       0  5233.6      .1       0
Bank Sta=4933,4994.6
XS Rating Curve= 0 ,0
Exp/Cntr=0.3,0.1

Type RM Length L Ch R = 1 ,71229   ,730,730,730
BEGIN DESCRIPTION:
Dry Comal Creek 67.0
END DESCRIPTION:
XS GIS Cut Line= 4
      2202924.99       13787825.        2202425.       13787825.
      2202148.02     13788032.73      2201574.43     13787991.28
#Sta/Elev= 30
    4500  807.34    4890  814.93    4930  814.78    4950  813.04    4960  802.07
  4966.7  730.86  4968.2  729.86  5026.8  729.86  5028.3  730.86  5042.7  739.57
  5044.4  739.68  5063.5  740.11  5086.4  745.59  5113.5  749.18  5121.9  748.85
  5136.4  749.83  5178.1  754.65  5202.2  755.44  5242.7  759.09  5257.3  761.25
  5291.7  762.68  5359.3  767.37  5379.2  767.92  5409.4   766.8  5499.6  769.19
  5569.8  769.55  5700.2  772.56  5797.9  777.69  5802.9  777.06  5921.3  781.22
#Mann= 5 ,-1 , 0
    4500      .1       0  4966.7     .05       0  5028.3      .1       0
  5044.4    .035       0  5202.2      .1       0
Bank Sta=4966.7,5028.3
XS Rating Curve= 0 ,0
Exp/Cntr=0.3,0.1

Type RM Length L Ch R = 1 ,70499   ,709,709,709
BEGIN DESCRIPTION:
Dry Comal Creek 66.0
END DESCRIPTION:
XS GIS Cut Line= 3
        2202275.       13787125.        2201875.       13787425.
        2201575.       13787925.
#Sta/Elev= 30
  4504.9  805.44  4797.6  813.29  4812.2  812.71  4826.8  814.25    4833  812.97
  4841.4  813.38  4862.2  811.31  4868.4  803.62  4876.8  791.16    4883  770.69
  4897.6  757.12  4912.2  748.92  4918.4  739.32  4926.8  737.96    4933  734.18
  4937.6  728.05  4939.1  727.05  4997.7  727.05  4999.2  728.05  5001.8  731.27
  5007.8  731.27  5024.9  736.37  5049.6  741.51  5076.8   743.8  5129.3   753.8
  5137.7  754.31  5203.2  759.15  5463.6  766.42  5506.4  770.73    5588  776.74
#Mann= 5 ,-1 , 0
  4504.9     .12       0  4937.6     .05       0  4999.2     .12       0
  5024.9     .07       0  5137.7     .12       0
Bank Sta=4937.6,4999.2
XS Rating Curve= 0 ,0
Exp/Cntr=0.3,0.1

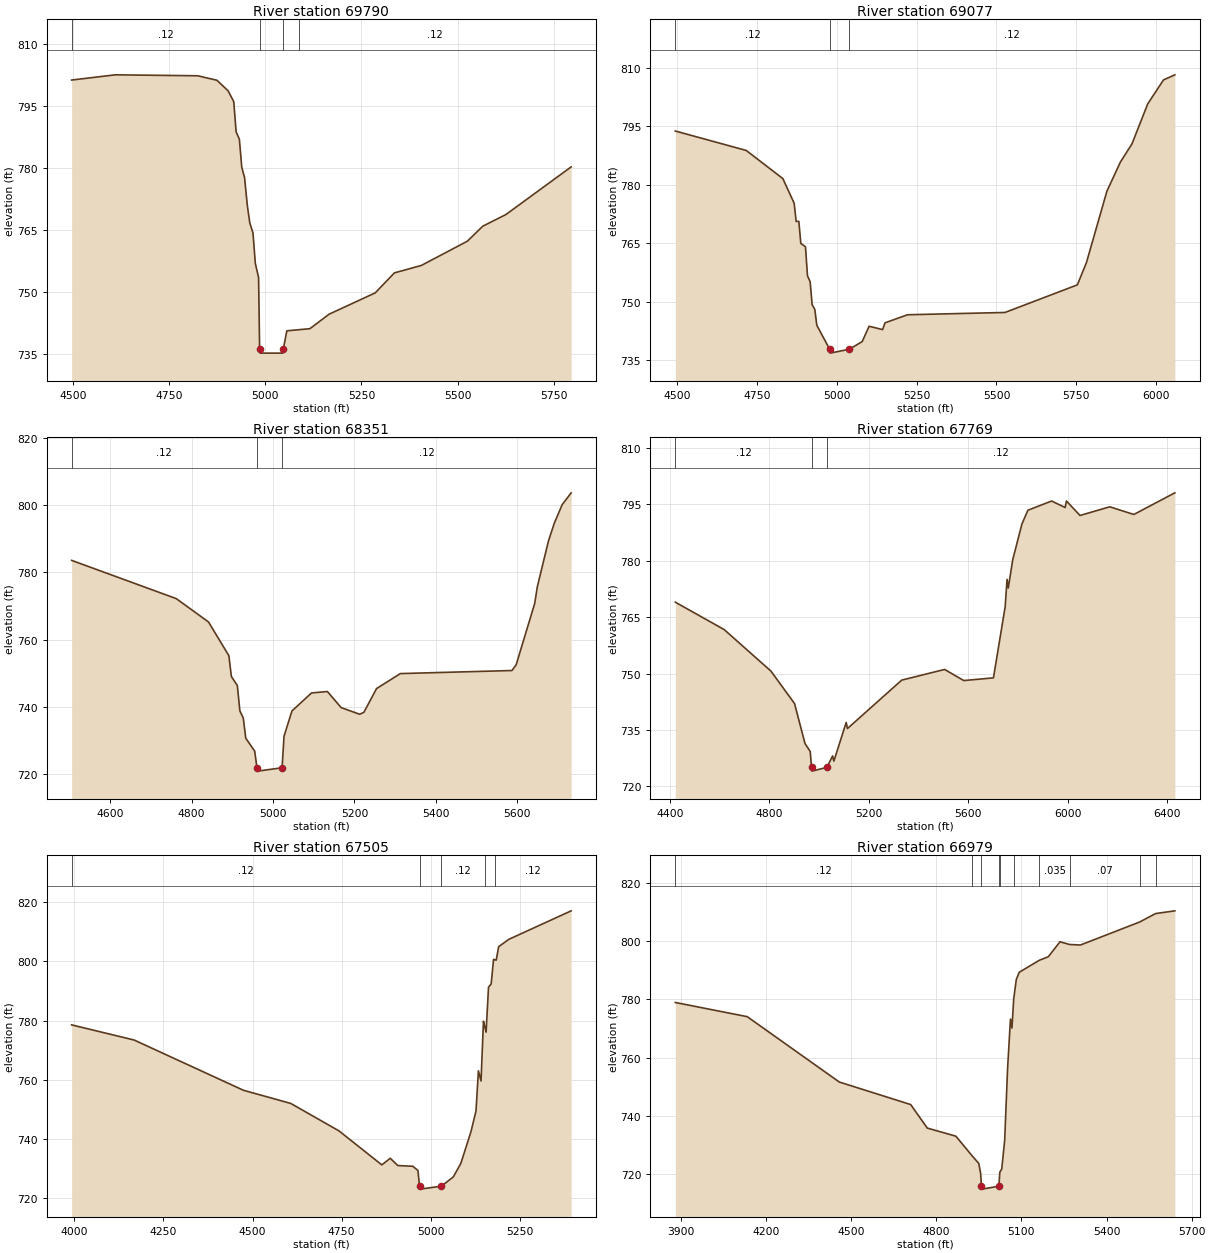
Type RM Length L Ch R = 1 ,69790   ,713,713,713
BEGIN DESCRIPTION:
Dry Comal Creek 65.0
END DESCRIPTION:
XS GIS Cut Line= 3
      2201675.02     13786824.99        2201275.       13787125.
        2201275.     13787924.98
#Sta/Elev= 30
  4495.7  801.18  4609.3  802.44  4823.8  802.21  4873.8  801.13    4903  798.57
  4917.6  795.95  4923.8  788.65  4932.2  786.89  4938.4  780.15  4945.7  777.63
    4953  770.83  4959.3  766.69  4967.6  764.27  4973.8  756.86  4982.2  753.49
  4984.9  736.23  4986.4  735.23  5045.1  735.23  5046.6  736.23  5055.7  740.62
  5087.3  740.89  5115.7  741.13  5165.7  744.63  5285.7  749.78  5335.7  754.61
  5405.7   756.4  5525.7  762.27  5565.7  765.89  5625.7  768.69  5795.7  780.21
#Mann= 4 ,-1 , 0
  4495.7     .12       0  4984.9    .035       0  5046.6     .12       0
  5087.3     .12       0
Bank Sta=4984.9,5046.6
XS Rating Curve= 0 ,0
Exp/Cntr=0.3,0.1

Type RM Length L Ch R = 1 ,69077   ,726,726,726
BEGIN DESCRIPTION:
Dry Comal Creek 64.0
END DESCRIPTION:
XS GIS Cut Line= 3
        2201025.       13786725.        2200625.       13787025.
      2199925.01     13787824.99
#Sta/Elev= 30
  4495.1  793.74    4717  788.76  4831.6  781.55    4867  775.22  4873.2  770.57
  4881.6  770.59  4887.8  764.92  4902.4  764.08  4908.6  756.66    4917   755.1
  4923.2  749.24  4931.6  748.01  4937.8  743.97    4978  737.82  4979.5  736.82
  5039.7  737.82    5080  739.79  5101.4  743.71  5143.6  742.85  5151.2  744.58
  5221.5  746.65  5526.6  747.24    5753  754.31  5781.4     760  5845.5  778.32
  5887.8   785.8  5923.8  790.42  5973.2  800.68  6022.5  806.83  6058.1  808.14
#Mann= 3 ,-1 , 0
  4495.1     .12       0    4978     .05       0  5039.7     .12       0
Bank Sta=4978,5039.7
XS Rating Curve= 0 ,0
Exp/Cntr=0.3,0.1

Type RM Length L Ch R = 1 ,68351   ,582,582,582
BEGIN DESCRIPTION:
Dry Comal Creek 63.0
END DESCRIPTION:
XS GIS Cut Line= 3
      2200325.02     13786624.99        2199925.       13786925.
      2199725.01     13787624.97
#Sta/Elev= 30
  4504.9  783.53  4762.2  772.15  4841.4  765.21  4891.4   755.2  4897.6     749
  4912.2  746.34  4918.5  738.76  4926.8  736.67    4933  730.66  4954.9  726.82
  4960.5  721.87    4962  720.87  5022.2  721.87    5027  731.24  5046.5  738.76
  5094.6  744.11  5133.6  744.54  5167.4  739.76  5212.9  737.78  5223.3  738.36
  5254.5  745.42    5313  749.87  5587.3  750.78  5597.7   752.5  5643.2  770.71
  5649.7  775.69    5677  789.27  5691.3  794.54  5710.8   800.1  5732.9  803.61
#Mann= 3 ,-1 , 0
  4504.9     .12       0  4960.5     .05       0  5022.2     .12       0
Bank Sta=4960.5,5022.2
XS Rating Curve= 0 ,0
Exp/Cntr=0.3,0.1

Type RM Length L Ch R = 1 ,67769   ,264,264,264
BEGIN DESCRIPTION:
X18935
END DESCRIPTION:
XS GIS Cut Line= 3
      2199896.05     13786393.15      2199386.11     13786729.49
      2199624.81     13788107.49
#Sta/Elev= 30
  4421.2     769  4617.7  761.71  4805.8  750.67  4900.8  742.02  4942.9  731.38
  4963.9  729.26  4969.2  725.04  4970.7  724.04  5030.9  725.04  5053.9  728.08
    5059   726.7  5108.6     737  5113.6  735.37    5332  748.26  5504.5   751.1
  5581.4  748.14  5700.9  748.86  5748.1  767.81  5755.6  775.07  5760.6  772.78
  5778.5  780.31  5815.3  789.78  5839.4  793.46  5934.8  795.92  5989.4  794.19
  5994.5  795.92  6049.2  792.07  6168.7  794.38  6265.7  792.34  6430.6   798.1
#Mann= 3 ,-1 , 0
  4421.2     .12       0  4969.2     .05       0  5030.9     .12       0
Bank Sta=4969.2,5030.9
XS Rating Curve= 0 ,0
Exp/Cntr=0.3,0.1

Type RM Length L Ch R = 1 ,67505   ,526,526,526
BEGIN DESCRIPTION:
X18934
END DESCRIPTION:
XS GIS Cut Line= 3
      2200156.52     13786284.61      2199288.45     13786469.08
      2198941.25     13786848.82
#Sta/Elev= 30
  3992.2  778.54  4167.6  773.42  4474.3  756.43  4607.2  751.98  4742.5   742.7
  4862.7   731.2  4886.5  733.43  4907.5  730.98  4950.1  730.72  4964.2  729.27
  4968.5     724    4970     723  5030.2     724  5063.5  727.15  5084.5   731.7
  5112.9   742.4  5127.1  749.47  5133.8  763.01  5141.2   759.6    5148  779.79
    5152   777.8  5155.4   776.1  5162.2  791.27  5169.6  792.37  5176.4  800.69
  5179.9  800.57  5183.8  800.43  5190.6  804.97  5218.9  807.45  5394.2  817.11
#Mann= 5 ,-1 , 0
  3992.2     .12       0  4968.5     .05       0  5030.2     .12       0
    5152      .1       0  5179.9     .12       0
Bank Sta=4968.5,5030.2
XS Rating Curve= 0 ,0
Exp/Cntr=0.3,0.1

Type RM Length L Ch R = 1 ,66979   ,727,727,727
BEGIN DESCRIPTION:
Dry Comal Creek 62.0
END DESCRIPTION:
XS GIS Cut Line= 3
      2200286.72     13786208.66        2199175.       13786075.
      2198550.63      13786219.5
#Sta/Elev= 30
  3880.2  778.92  4133.7  774.06  4458.2  751.66  4709.8  743.94  4768.3  735.88
    4869  733.11  4925.6  726.46  4949.6  723.78  4956.3  720.38    4959  715.96
  4960.5  714.96  5020.7  715.96  5023.8  720.71    5026  721.08  5030.7  721.88
    5041  731.66  5051.3  756.37  5061.4  773.23  5066.6  770.15  5072.9  780.21
    5082   786.8  5092.3  789.27  5163.4   793.4  5194.7  794.59    5236  799.72
  5269.7   798.8  5307.9  798.61  5516.5  806.49  5573.3   809.4  5640.8  810.33
#Mann= 10 ,-1 , 0
  3880.2     .12       0  4925.6     .07       0    4959     .05       0
  5020.7     .07       0    5026     .12       0  5072.9     .07       0
  5163.4    .035       0  5269.7     .07       0  5516.5    .035       0
  5573.3     .12       0
Bank Sta=4959,5020.7
XS Rating Curve= 0 ,0
Exp/Cntr=0.3,0.1