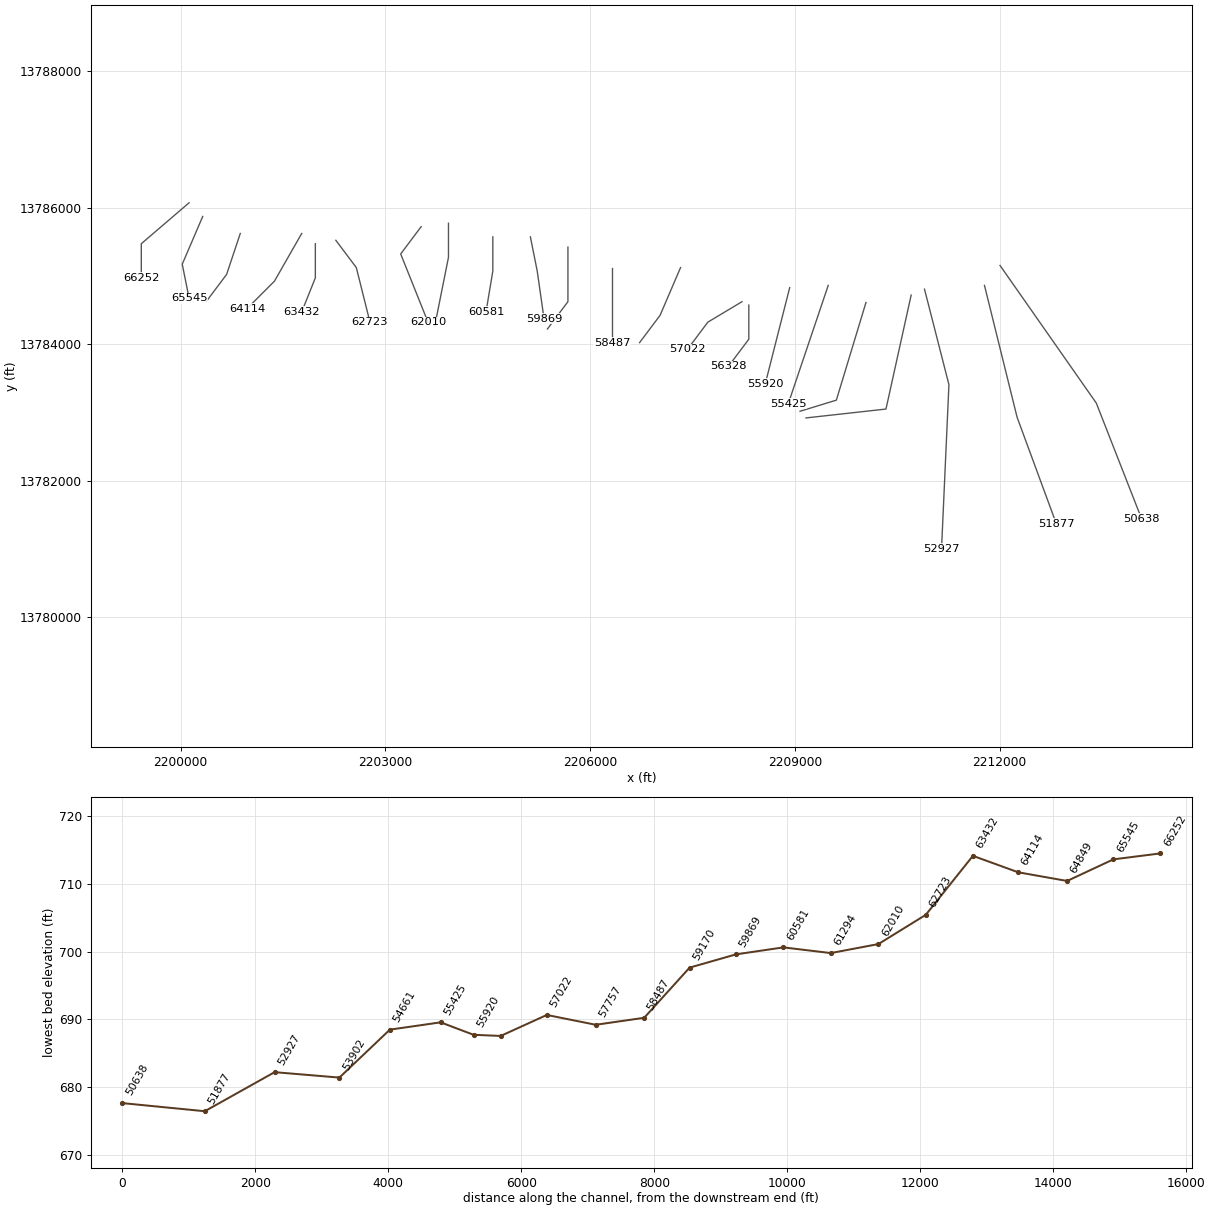
HEC-RAS study Dry Comal Creek.prj: Dry Comal Creek Base Level Engineering

--- Dry Comal Creek.g01 (geometry) --- (continued)

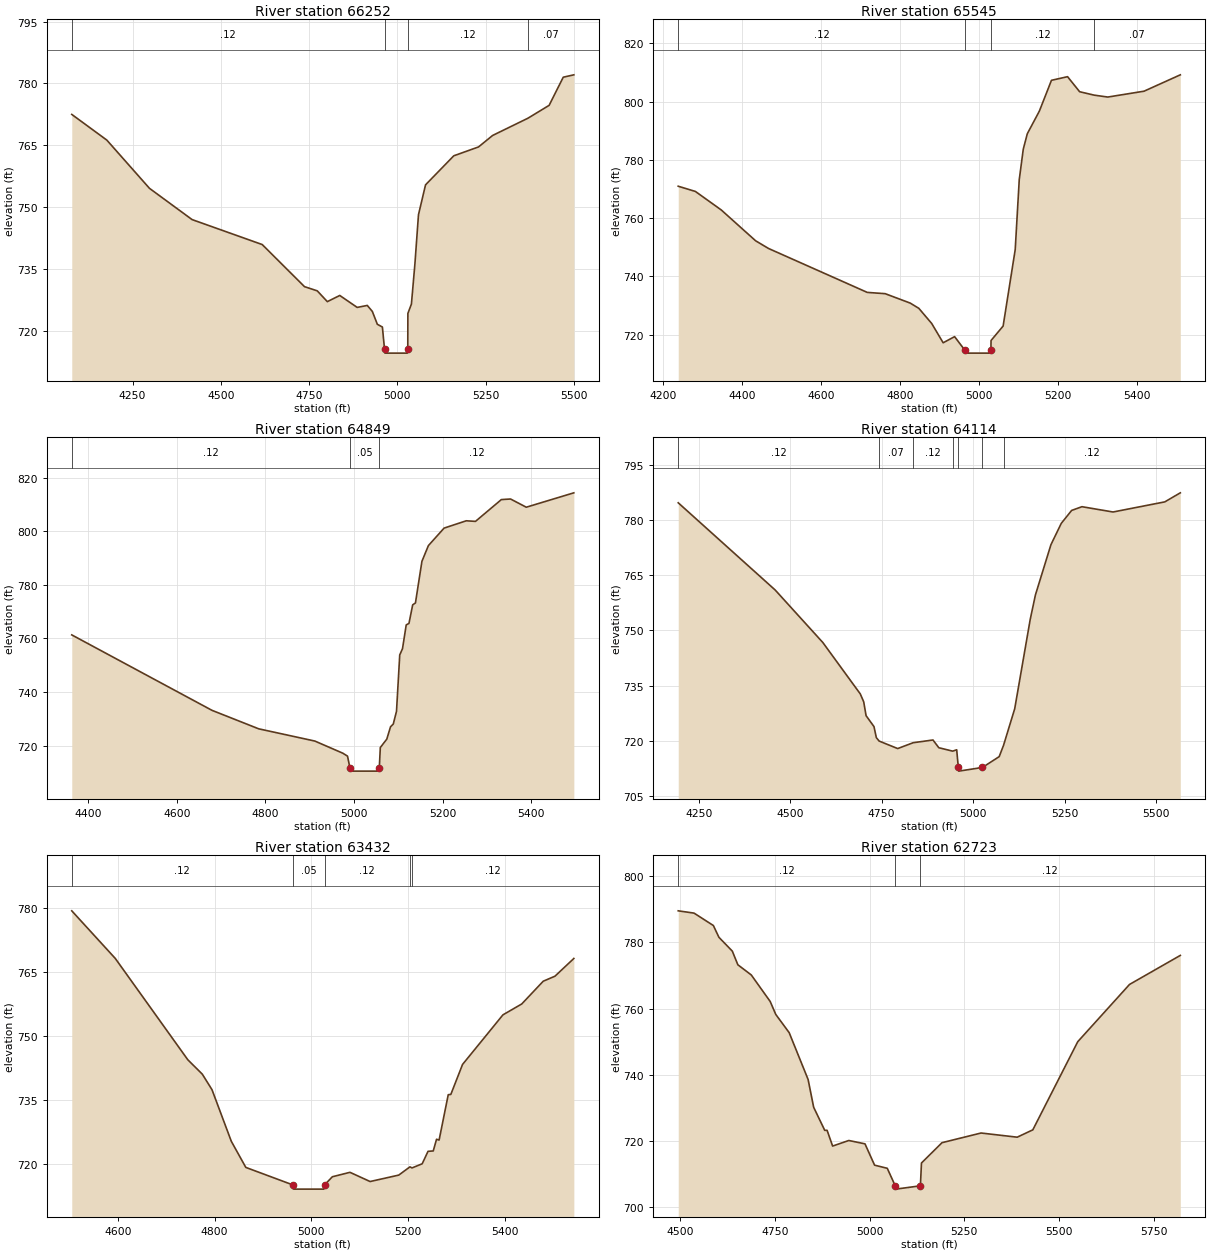
Type RM Length L Ch R = 1 ,66252   ,707,707,707
BEGIN DESCRIPTION:
Dry Comal Creek 61.0
END DESCRIPTION:
XS GIS Cut Line= 3
      2200124.99     13786074.99        2199425.       13785475.
        2199425.     13784975.04
#Sta/Elev= 30
  4077.7  772.49    4177  766.25  4297.8  754.54  4418.5  746.95  4617.1  740.89
  4736.8  730.67    4773  729.65  4801.5  727.03  4836.7  728.53    4886  725.63
  4914.6  726.11  4928.9  724.66  4943.1  721.53  4957.4  720.87  4963.4  715.53
  4964.9  714.53  5027.8  714.53  5029.3  715.53  5029.6  724.17  5039.6  726.44
  5049.6  736.31  5059.6  748.13  5079.6  755.39  5159.6  762.44  5229.6  764.59
  5269.6  767.38  5369.7  771.57  5429.6  774.69  5469.6  781.52  5499.6   782.1
#Mann= 4 ,-1 , 0
  4077.7     .12       0  4963.4     .05       0  5029.3     .12       0
  5369.7     .07       0
Bank Sta=4963.4,5029.3
XS Rating Curve= 0 ,0
Exp/Cntr=0.3,0.1

Type RM Length L Ch R = 1 ,65545   ,696,696,696
BEGIN DESCRIPTION:
Dry Comal Creek 60.0
END DESCRIPTION:
XS GIS Cut Line= 3
      2200325.01     13785875.02        2200025.       13785175.
        2200125.       13784675.
#Sta/Elev= 30
  4238.4  770.95  4281.9  769.16  4347.2  762.82  4434.3  752.23  4466.9  749.59
  4717.1   734.5  4762.5  734.06  4825.9  730.83  4847.7  729.03  4880.3  723.83
  4909.3   717.2  4938.3  719.31  4964.3  714.65  4965.8  713.65  5028.7  713.65
  5030.2  714.65  5030.6  717.98  5061.2  722.95  5091.8  749.19    5102  773.18
  5112.2  783.68  5122.4  788.96    5153  796.76  5183.6  807.32  5224.4  808.56
  5254.9   803.4  5291.9  802.22  5326.3  801.57  5418.1  803.58  5509.9   809.2
#Mann= 4 ,-1 , 0
  4238.4     .12       0  4964.3     .05       0  5030.2     .12       0
  5291.9     .07       0
Bank Sta=4964.3,5030.2
XS Rating Curve= 0 ,0
Exp/Cntr=0.3,0.1

Type RM Length L Ch R = 1 ,64849   ,735,735,735
BEGIN DESCRIPTION:
Dry Comal Creek 59.0
END DESCRIPTION:
XS GIS Cut Line= 3
      2200875.01     13785625.04        2200675.       13785025.
        2200375.       13784625.
#Sta/Elev= 30
  4363.2  761.31  4679.5  733.15  4784.9  726.25  4911.4  721.69  4974.6  717.15
  4985.2  716.05  4990.9  711.46  4992.4  710.46  5055.3  710.46  5056.8  711.46
  5059.2  719.28  5073.8  722.41  5082.2     727  5088.4  728.03  5095.7  732.81
    5103  753.85  5109.2  756.15  5117.6  765.04  5123.8   765.6  5132.2  772.54
  5138.4  773.22    5153  788.75  5167.6  794.63    5203  801.17    5253   803.9
  5273.8  803.68  5332.2  811.82    5353  812.03  5388.4  808.97  5495.7  814.34
#Mann= 3 ,-1 , 0
  4363.2     .12       0  4990.9     .05       0  5056.8     .12       0
Bank Sta=4990.9,5056.8
XS Rating Curve= 0 ,0
Exp/Cntr=0.3,0.1

Type RM Length L Ch R = 1 ,64114   ,682,682,682
BEGIN DESCRIPTION:
Dry Comal Creek 58.0
END DESCRIPTION:
XS GIS Cut Line= 3
      2201775.01     13785625.02        2201375.       13784925.
      2200975.03     13784525.03
#Sta/Elev= 30
  4194.2  784.66  4459.1  760.96  4589.4  746.68  4691.6  732.73    4701  730.58
  4707.5  726.81  4729.1  723.84  4735.5  720.84  4743.2  719.91  4793.9  717.87
  4836.1  719.46  4890.3   720.2  4906.2   718.1  4944.2  717.17  4955.1  717.54
  4959.5  712.74    4961  711.74  5025.5  712.74  5071.2  715.68    5083  718.73
  5113.6  728.69    5156  752.98  5170.2  759.62  5212.6  773.28  5240.9  779.08
  5269.2  782.59  5297.4   783.6  5382.3  782.16  5523.7  784.91  5566.1  787.37
#Mann= 7 ,-1 , 0
  4194.2     .12       0  4743.2     .07       0  4836.1     .12       0
  4944.2     .07       0  4959.5     .05       0  5025.5     .07       0
    5083     .12       0
Bank Sta=4959.5,5025.5
XS Rating Curve= 0 ,0
Exp/Cntr=0.3,0.1

Type RM Length L Ch R = 1 ,63432   ,709,709,709
BEGIN DESCRIPTION:
Dry Comal Creek 57.0
END DESCRIPTION:
XS GIS Cut Line= 3
        2201975.       13785475.        2201975.       13784975.
      2201775.01     13784475.02
#Sta/Elev= 30
  4504.5  779.41  4594.5  768.25  4744.5   744.5  4774.5  741.12  4794.5  737.49
  4834.5  725.38  4864.5  719.26  4961.5  715.17    4963  714.17    5026  714.17
  5027.5  715.17  5043.5  717.07  5079.9  718.11  5121.6  715.95  5180.9  717.46
    5204  719.39  5208.3  719.14  5229.3  720.11  5241.4  723.03  5252.2  723.12
    5259  725.86  5264.3  725.67  5283.2   736.3  5288.6  736.38  5312.8   743.4
  5396.3  755.02  5435.3  757.58  5479.7  762.91    5504  764.09    5543  768.24
#Mann= 5 ,-1 , 0
  4504.5     .12       0  4961.5     .05       0  5027.5     .12       0
    5204     .07       0  5208.3     .12       0
Bank Sta=4961.5,5027.5
XS Rating Curve= 0 ,0
Exp/Cntr=0.3,0.1

Type RM Length L Ch R = 1 ,62723   ,713,713,713
BEGIN DESCRIPTION:
Dry Comal Creek 56.0
END DESCRIPTION:
XS GIS Cut Line= 3
        2202275.       13785525.        2202575.       13785125.
      2202774.99     13784325.02
#Sta/Elev= 30
  4495.4  789.53  4537.1  788.84  4588.1  785.09  4602.7  781.54  4638.1  777.35
  4652.7  773.23  4688.1  770.16  4738.1  762.13  4752.7  758.24  4788.1  752.73
  4838.1  738.56  4852.7  730.19  4881.9  723.22  4888.1  723.23  4902.7  718.47
  4945.4  720.15  4988.1  719.14  5013.4   712.7  5046.9  711.75  5067.9  706.46
  5069.4  705.46  5134.3  706.46  5137.1  713.35  5191.3  719.49  5294.3  722.41
  5389.7  721.15  5430.9  723.37  5549.4  749.99    5686  767.29    5820  776.06
#Mann= 3 ,-1 , 0
  4495.4     .12       0  5067.9     .05       0  5134.3     .12       0
Bank Sta=5067.9,5134.3
XS Rating Curve= 0 ,0
Exp/Cntr=0.3,0.1

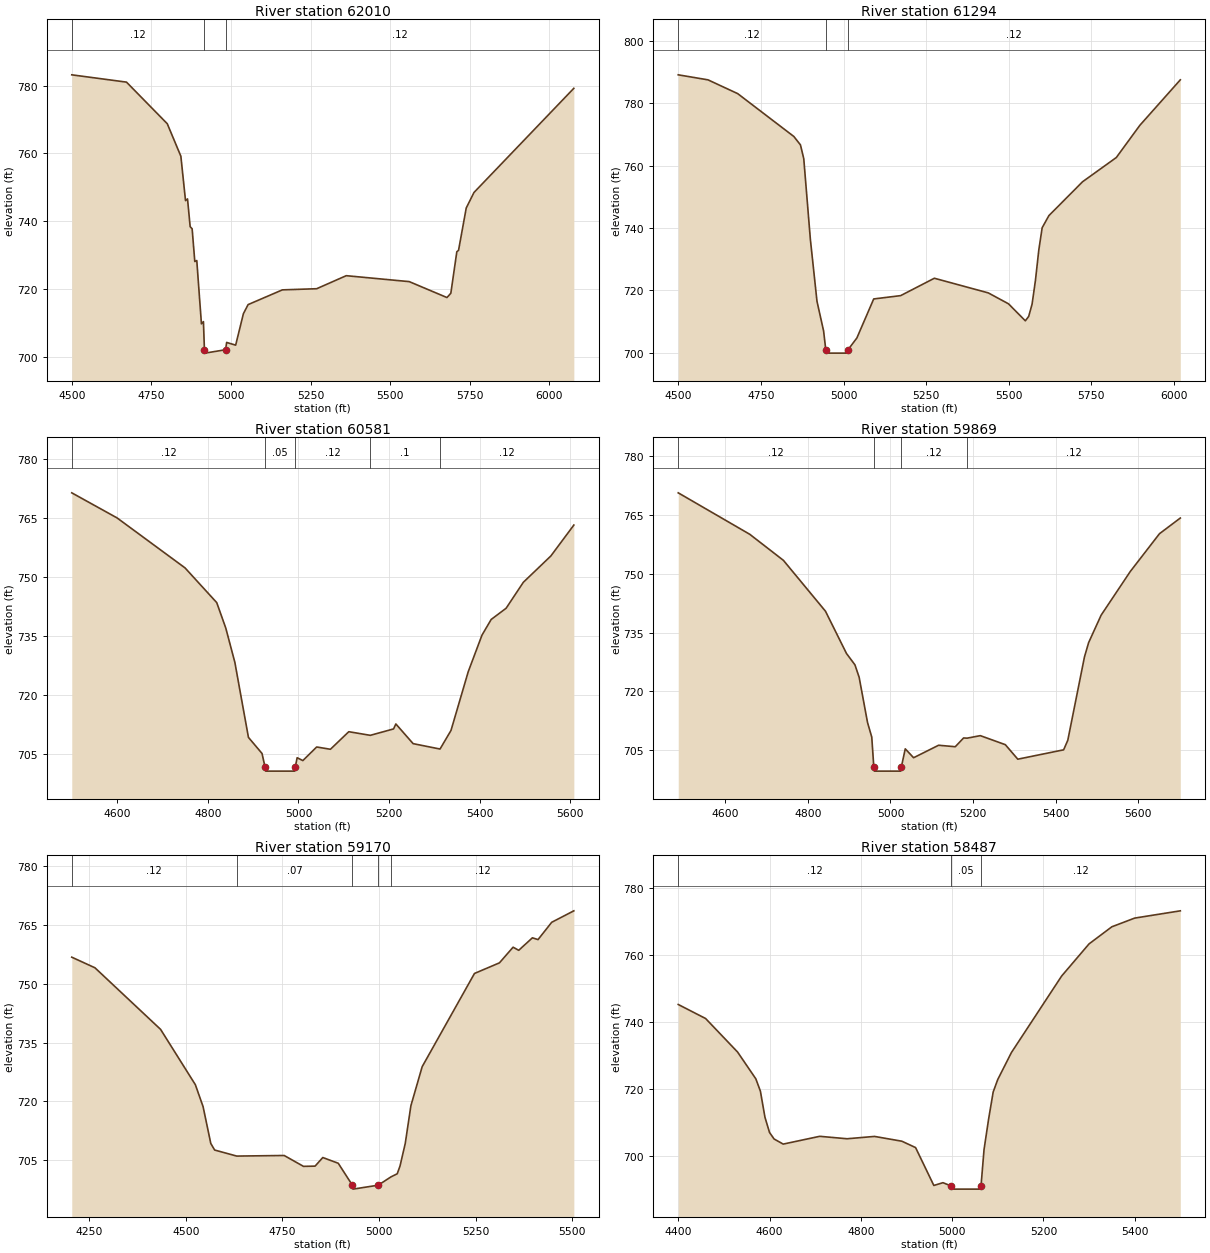
Type RM Length L Ch R = 1 ,62010   ,716,716,716
BEGIN DESCRIPTION:
Dry Comal Creek 55.0
END DESCRIPTION:
XS GIS Cut Line= 3
      2203525.01     13785725.01        2203225.       13785325.
      2203625.02     13784324.96
#Sta/Elev= 30
    4500  783.15  4671.9     781    4800  768.74  4842.7  759.17  4857.3  746.09
  4863.6  746.58  4871.9   738.4  4878.1  737.78  4886.5  728.12  4892.7  728.43
  4907.3  709.77  4913.6  710.42  4916.7  702.14  4918.2  701.14  4983.3  702.14
  4986.5  704.29  5014.8  703.49  5039.1  712.75  5053.9  715.44  5161.6  719.78
  5269.3  720.12  5362.2  723.96  5560.1  722.21  5678.5  717.52  5690.7  718.78
  5709.5  731.01  5714.9  731.43  5739.1  743.91  5763.4  748.48  6077.1  779.18
#Mann= 3 ,-1 , 0
    4500     .12       0  4916.7     .05       0  4983.3     .12       0
Bank Sta=4916.7,4983.3
XS Rating Curve= 0 ,0
Exp/Cntr=0.3,0.1

Type RM Length L Ch R = 1 ,61294   ,713,713,713
BEGIN DESCRIPTION:
Dry Comal Creek 54.0
END DESCRIPTION:
XS GIS Cut Line= 3
        2203925.     13785774.96        2203925.       13785275.
      2203724.99     13784274.97
#Sta/Elev= 30
  4499.7   789.2  4589.7  787.59  4679.7  783.16  4849.7  769.39  4869.7  766.69
  4879.7  762.26  4899.7  736.33  4919.7  716.46  4939.7  706.94  4946.4  700.81
  4947.9  699.81  5011.5  699.81    5013  700.81  5040.5  704.68  5091.4  717.21
    5173  718.28    5275  723.86  5438.2  719.16  5499.4  715.65  5550.4  710.19
  5560.6  711.61  5570.8  715.56    5581  723.19  5591.1  732.88  5601.3  740.08
  5621.7  743.98  5723.7  754.86  5825.7  762.63  5897.1  772.99  6019.5  787.59
#Mann= 3 ,-1 , 0
  4499.7     .12       0  4946.4     .05       0    5013     .12       0
Bank Sta=4946.4,5013
XS Rating Curve= 0 ,0
Exp/Cntr=0.3,0.1

Type RM Length L Ch R = 1 ,60581   ,712,712,712
BEGIN DESCRIPTION:
Dry Comal Creek 53.0
END DESCRIPTION:
XS GIS Cut Line= 3
        2204575.     13785575.01        2204575.       13785075.
        2204475.     13784474.99
#Sta/Elev= 30
  4499.6  771.32  4599.6  764.95  4749.6  752.26  4819.6  743.44  4839.6  736.97
  4859.6  728.28  4889.6  709.22  4919.6  705.13  4926.3  701.65  4927.8  700.65
  4991.4  700.65  4992.9  701.65  4997.1  704.05  5009.7  703.33  5040.2  706.78
  5070.6   706.2  5111.1  710.66  5158.6  709.74    5210  711.37    5215  712.63
  5253.1  707.63  5312.5  706.26  5336.7  710.97  5374.7  725.87  5405.1  735.18
  5425.4  739.16  5458.4  742.01  5496.4   748.6  5557.2  755.29  5607.9  763.13
#Mann= 5 ,-1 , 0
  4499.6     .12       0  4926.3     .05       0  4992.9     .12       0
  5158.6      .1       0  5312.5     .12       0
Bank Sta=4926.3,4992.9
XS Rating Curve= 0 ,0
Exp/Cntr=0.3,0.1

Type RM Length L Ch R = 1 ,59869   ,699,699,699
BEGIN DESCRIPTION:
Dry Comal Creek 52.0
END DESCRIPTION:
XS GIS Cut Line= 3
        2205125.     13785575.01        2205225.       13785075.
        2205325.     13784375.02
#Sta/Elev= 30
  4485.5  770.69  4658.9   760.1  4740.5  753.44  4842.4  740.46  4893.4  729.65
  4913.8  726.77    4924   723.6  4944.4  712.01  4954.6  708.32  4959.6  700.62
  4961.1  699.62  5024.7  699.62  5026.2  700.62  5035.8  705.31    5056  703.04
  5116.6  706.23    5157  705.85  5177.2  708.09  5185.7  708.04  5217.7  708.68
  5278.3  706.38  5308.6  702.67  5419.7  705.06  5429.8  707.51  5470.2  728.79
  5480.3  732.44  5510.6  739.45  5581.3  750.61    5652  760.25  5702.5  764.25
#Mann= 4 ,-1 , 0
  4485.5     .12       0  4959.6     .05       0  5026.2     .12       0
  5185.7     .12       0
Bank Sta=4959.6,5026.2
XS Rating Curve= 0 ,0
Exp/Cntr=0.3,0.1

Type RM Length L Ch R = 1 ,59170   ,683,683,683
BEGIN DESCRIPTION:
Dry Comal Creek 51.0
END DESCRIPTION:
XS GIS Cut Line= 3
        2205675.     13785424.97        2205675.       13784625.
      2205374.98     13784224.98
#Sta/Elev= 30
  4204.6  756.76  4264.6  754.06  4434.6  738.36  4524.6  724.27  4544.6  718.68
  4564.6  709.28  4574.6  707.62  4631.7  706.08  4754.6  706.23  4804.6  703.46
  4834.6  703.52  4854.6  705.71  4894.6  704.25  4931.2  698.66  4932.7  697.66
  4997.9  698.66  5031.3  700.79  5047.3  701.57  5054.6  703.58  5068.1  709.31
  5082.7  718.92  5111.9  728.86  5247.3  752.61  5311.9  755.31  5347.3   759.3
  5361.9  758.51  5397.3  761.69  5411.9  761.24  5447.3  765.65  5504.6  768.57
#Mann= 5 ,-1 , 0
  4204.6     .12       0  4631.7     .07       0  4931.2     .05       0
  4997.9     .07       0  5031.3     .12       0
Bank Sta=4931.2,4997.9
XS Rating Curve= 0 ,0
Exp/Cntr=0.3,0.1

Type RM Length L Ch R = 1 ,58487   ,730,730,730
BEGIN DESCRIPTION:
Dry Comal Creek 50.0
END DESCRIPTION:
XS GIS Cut Line= 3
        2206325.     13785125.02        2206325.       13784525.
        2206325.     13784025.02
#Sta/Elev= 30
  4399.9  745.32  4459.9  741.13  4529.9  731.14  4569.9  723.15  4579.9  719.48
  4589.9  711.68  4599.9  707.15  4609.9   705.2  4629.9  703.68  4709.9     706
  4769.9  705.27  4829.9  705.97  4889.9  704.54  4919.9  702.64  4959.9  691.34
  4979.9  692.17  4996.6  691.25  4998.1  690.25  5061.8  690.25  5063.3  691.25
  5069.9  702.05  5079.9  711.14  5089.9  719.21  5099.9  722.93  5129.9  730.99
  5239.9   753.8  5299.9  763.38  5349.9  768.49  5399.9  771.08  5499.9  773.25
#Mann= 3 ,-1 , 0
  4399.9     .12       0  4996.6     .05       0  5063.3     .12       0
Bank Sta=4996.6,5063.3
XS Rating Curve= 0 ,0
Exp/Cntr=0.3,0.1

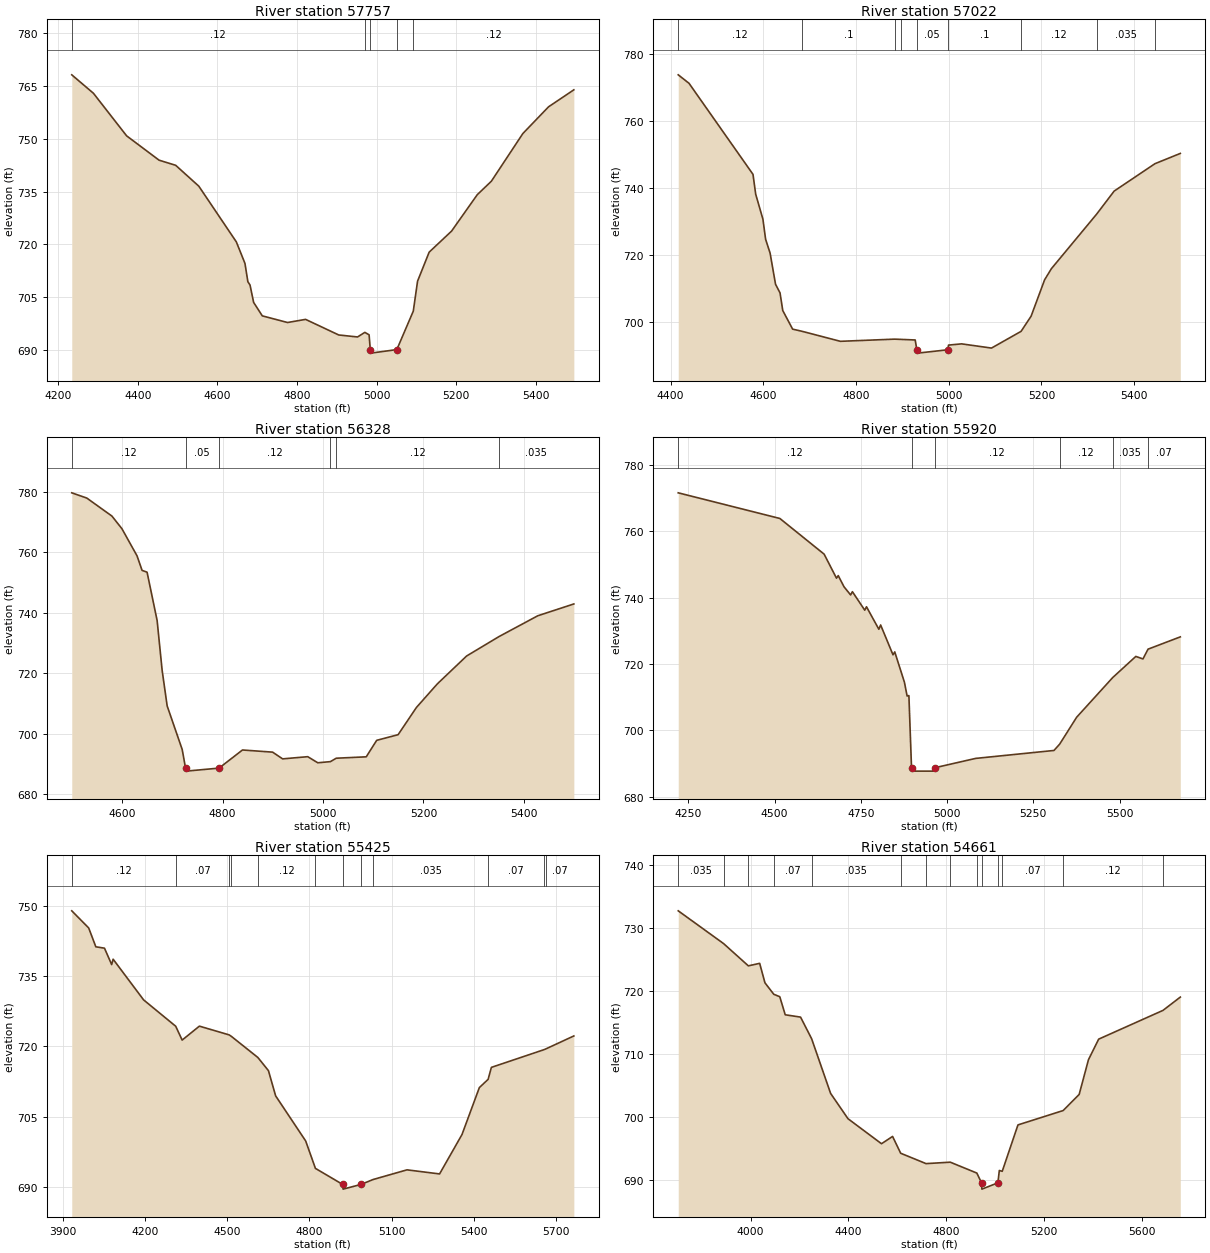
Type RM Length L Ch R = 1 ,57757   ,735,735,735
BEGIN DESCRIPTION:
Dry Comal Creek 49.0
END DESCRIPTION:
XS GIS Cut Line= 3
      2207325.01     13785125.03        2207025.       13784425.
      2206725.01     13784025.01
#Sta/Elev= 30
  4234.1  768.06  4288.5  762.84  4371.9  750.78  4453.5  743.88  4495.2  742.43
  4553.3  736.52  4647.6  720.74  4669.3  714.64  4676.6  709.45    4682  708.52
  4691.1  703.59  4712.8  699.78  4776.3  697.89  4821.6  698.78    4905  694.36
  4952.2   693.8  4970.5   695.1  4981.2  694.42  4984.2  690.22  4985.7  689.22
  5050.9  690.22  5092.3  701.12    5103   709.6  5132.2  717.83  5188.4  723.78
    5253   734.1  5288.4  737.91  5367.6  751.43  5432.2     759  5495.7  763.81
#Mann= 5 ,-1 , 0
  4234.1     .12       0  4970.5     .07       0  4984.2     .05       0
  5050.9     .07       0  5092.3     .12       0
Bank Sta=4984.2,5050.9
XS Rating Curve= 0 ,0
Exp/Cntr=0.3,0.1

Type RM Length L Ch R = 1 ,57022   ,694,694,694
BEGIN DESCRIPTION:
Dry Comal Creek 48.0
END DESCRIPTION:
XS GIS Cut Line= 3
      2208224.99       13784625.        2207725.       13784325.
      2207424.99     13783924.99
#Sta/Elev= 30
  4416.5  773.88  4439.8  771.34  4577.8  744.12  4583.6  738.19  4599.2  730.71
    4605  724.71  4614.7  720.56  4626.4  711.26  4636.1  708.68    4642   703.4
  4663.3  697.84  4683.7  697.19  4766.3   694.2  4883.2  694.85  4896.6  694.78
  4927.7   694.6  4931.2  691.67  4932.7  690.67    4998  691.67  4999.6  693.07
  5027.7  693.44  5092.3  692.18  5156.1  697.18  5177.7  701.71  5206.9   712.6
  5221.5  715.92    5319  732.21  5356.9  739.12  5444.9  747.31  5499.6  750.38
#Mann= 9 ,-1 , 0
  4416.5     .12       0  4683.7      .1       0  4883.2     .12       0
  4896.6      .1       0  4931.2     .05       0    4998      .1       0
  5156.1     .12       0    5319    .035       0  5444.9     .12       0
Bank Sta=4931.2,4998
XS Rating Curve= 0 ,0
Exp/Cntr=0.3,0.1

Type RM Length L Ch R = 1 ,56328   ,408,408,408
BEGIN DESCRIPTION:
Dry Comal Creek 47.0
END DESCRIPTION:
XS GIS Cut Line= 3
        2208325.     13784575.02        2208325.       13784075.
      2208025.01     13783675.02
#Sta/Elev= 30
  4499.5   779.6  4529.5  777.86  4579.5  771.91  4599.5  767.71  4629.5  758.76
  4639.5  753.96  4649.5  753.35  4669.5  737.39  4679.5   720.9  4689.5  709.14
  4719.5   694.7  4726.1  688.57  4727.6  687.57  4792.9  688.57  4839.5  694.56
  4899.5  693.85  4919.5  691.62  4969.5  692.35  4989.5  690.33  5014.6  690.71
  5026.3  691.84    5086   692.3  5106.8  697.75  5149.5  699.62    5186  708.63
  5227.6  716.42    5286  725.65  5350.3  732.05  5427.6  738.94  5499.5  742.85
#Mann= 6 ,-1 , 0
  4499.5     .12       0  4726.1     .05       0  4792.9     .12       0
  5014.6     .07       0  5026.3     .12       0  5350.3    .035       0
Bank Sta=4726.1,4792.9
XS Rating Curve= 0 ,0
Exp/Cntr=0.3,0.1

Type RM Length L Ch R = 1 ,55920   ,495,495,495
BEGIN DESCRIPTION:
X18933
END DESCRIPTION:
XS GIS Cut Line= 2
      2208923.86     13784830.59      2208565.79     13783420.02
#Sta/Elev= 30
  4220.9  771.51  4515.5  763.79  4643.8  753.05  4679.6  745.82  4684.7  746.59
  4701.3  743.25  4720.5  740.77  4725.7  741.76  4761.5  736.19  4766.6  737.21
  4802.4  730.45  4807.6  731.73  4843.4  722.75  4848.5  723.63  4876.6  714.48
  4884.3  710.35  4889.5  710.47  4897.1  688.74  4898.6  687.74  4962.4  687.74
  4963.9  688.74    5083  691.57    5310  693.96  5326.4  695.85  5375.8  703.97
  5480.3  715.91  5547.3  722.27  5567.9  721.51  5582.7  724.45  5676.2  728.15
#Mann= 6 ,-1 , 0
  4220.9     .12       0  4897.1     .05       0  4963.9     .12       0
  5326.4     .12       0  5480.3    .035       0  5582.7     .07       0
Bank Sta=4897.1,4963.9
XS Rating Curve= 0 ,0
Exp/Cntr=0.3,0.1

Type RM Length L Ch R = 1 ,55425   ,764,764,764
BEGIN DESCRIPTION:
X18932
END DESCRIPTION:
XS GIS Cut Line= 2
      2209488.11     13784863.18      2208902.65     13783128.51
#Sta/Elev= 30
  3933.3   748.9    3995  745.25  4021.1  741.23  4052.6  740.94  4078.8  737.44
  4084.1  738.59  4195.2  729.92  4312.3   724.3  4335.8  721.35  4398.7  724.32
    4507  722.46  4515.1  722.15  4611.9  717.64  4650.5  714.83  4676.7  709.46
  4786.3  699.84  4821.8     694  4921.2  690.58  4922.7  689.58    4988  690.58
  5031.7  691.62  5155.7  693.69  5274.5  692.82  5356.2  701.21  5419.5  711.22
  5451.5  712.98  5463.4  715.53    5654  719.28  5661.4  719.45  5764.1  722.23
#Mann= 12 ,-1 , 0
  3933.3     .12       0  4312.3     .07       0    4507     .12       0
  4515.1     .07       0  4611.9     .12       0  4821.8     .07       0
  4921.2     .05       0    4988     .07       0  5031.7    .035       0
  5451.5     .07       0    5654    .035       0  5661.4     .07       0
Bank Sta=4921.2,4988
XS Rating Curve= 0 ,0
Exp/Cntr=0.3,0.1

Type RM Length L Ch R = 1 ,54661   ,759,759,759
BEGIN DESCRIPTION:
X18931
END DESCRIPTION:
XS GIS Cut Line= 3
      2210041.49      13784613.6      2209607.46     13783181.32
      2209075.81     13783018.57
#Sta/Elev= 30
  3704.1   732.7  3889.4   727.5  3990.8  723.96    4037  724.36  4058.6  721.27
  4094.6  719.45  4119.2  719.06  4141.5  716.19  4204.2  715.82  4249.4  712.39
  4327.1   703.7  4398.2  699.68  4535.1  695.71  4580.4  696.87  4613.5   694.2
  4717.3  692.55  4816.2  692.78  4924.9  691.05    4944   689.5  4945.5   688.5
  5010.9   689.5  5016.8  691.46  5028.7  691.33    5093   698.7  5277.8  700.98
  5343.2  703.54  5381.1  709.04  5422.9  712.32    5686  716.89  5756.7     719
#Mann= 14 ,-1 , 0
  3704.1    .035       0  3889.4     .07       0  3990.8    .035       0
  4094.6     .07       0  4249.4    .035       0  4613.5     .12       0
  4717.3    .035       0  4816.2     .12       0  4924.9    .035       0
    4944    .035       0  5010.9    .035       0  5028.7     .07       0
  5277.8     .12       0    5686     .07       0
Bank Sta=4944,5010.9
XS Rating Curve= 0 ,0
Exp/Cntr=0.3,0.1

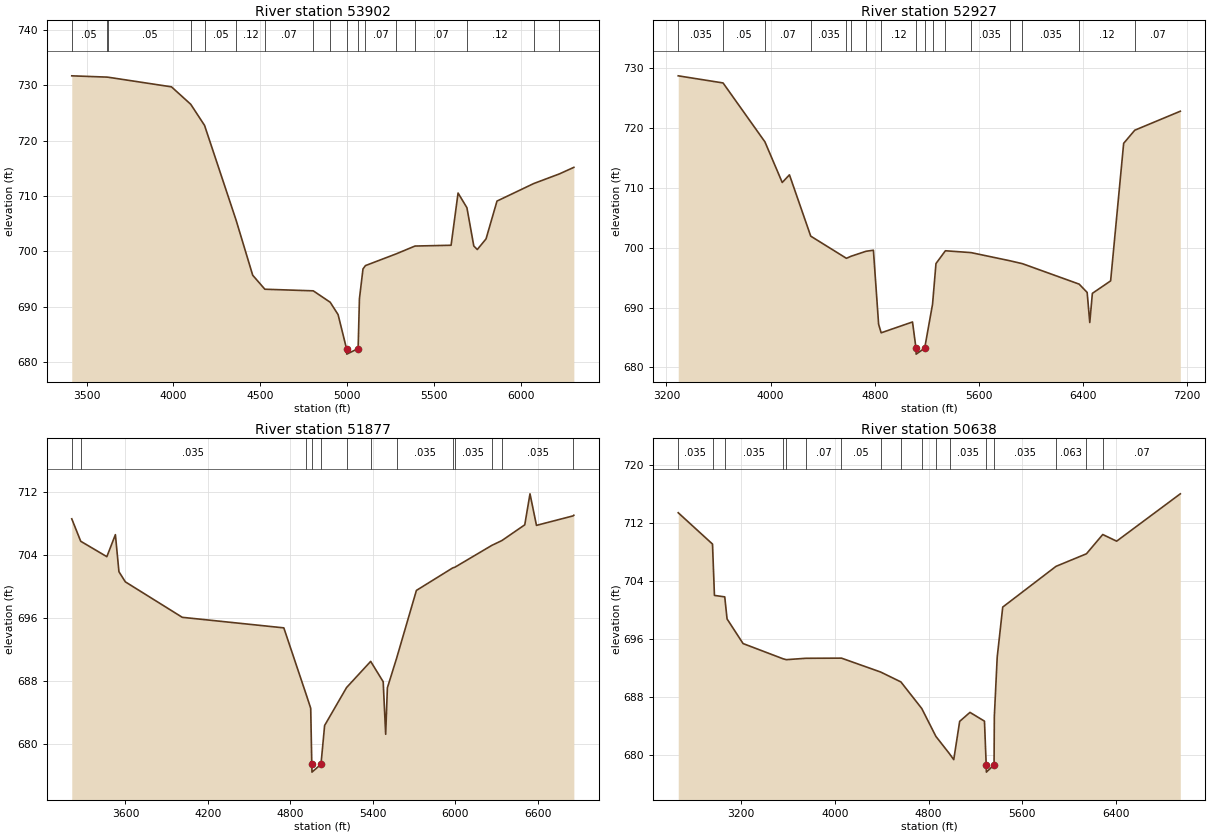
Type RM Length L Ch R = 1 ,53902   ,975,975,975
BEGIN DESCRIPTION:
Dry Comal Creek 46.0
END DESCRIPTION:
XS GIS Cut Line= 3
      2210703.38     13784722.09      2210334.46     13783051.11
      2209162.59      13782920.9
#Sta/Elev= 30
  3414.7  731.68    3616  731.45  3623.5  731.43  3988.7  729.69  4099.6  726.54
  4179.3  722.72  4360.9  705.59  4456.3  695.67  4526.3  693.14    4805  692.85
  4902.4  690.79  4947.8  688.56  4996.3  682.42  4997.8  681.42  5063.2  682.42
  5070.7  691.42  5091.2  696.81  5105.4  697.41  5281.7  699.52  5390.7  700.94
  5598.3  701.08  5638.5  710.51  5689.5  707.86  5729.1  700.95  5749.2  700.31
  5799.5  702.23  5862.6  709.06  6074.3  712.23  6221.9  713.97    6305  715.15
#Mann= 17 ,-1 , 0
  3414.7     .05       0    3616    .035       0  3623.5     .05       0
  4099.6     .07       0  4179.3     .05       0  4360.9     .12       0
  4526.3     .07       0    4805     .12       0  4902.4    .035       0
  4996.3    .035       0  5063.2    .035       0  5105.4     .07       0
  5281.7     .12       0  5390.7     .07       0  5689.5     .12       0
  6074.3     .07       0  6221.9     .12       0
Bank Sta=4996.3,5063.2
XS Rating Curve= 0 ,0
Exp/Cntr=0.3,0.1

Type RM Length L Ch R = 1 ,52927   ,1050,1050,1050
BEGIN DESCRIPTION:
Dry Comal Creek 45.0
END DESCRIPTION:
XS GIS Cut Line= 3
       2210898.7     13784808.88      2211256.77     13783409.18
      2211148.26     13781000.29
#Sta/Elev= 30
  3290.2  728.69  3634.5   727.5  3956.2  717.66    4089  710.88  4144.3  712.16
  4307.9  701.92  4581.9  698.22  4617.3  698.56  4731.8  699.39  4789.2  699.57
  4829.2  687.21  4848.8  685.78  5089.5  687.59  5116.1  683.22  5117.6  682.22
    5183  683.22  5243.5  690.56  5269.7  697.34  5342.1  699.48  5539.4  699.17
  5835.4  697.82  5934.1  697.32  6369.3  693.91  6430.9  692.52  6450.9   687.5
  6470.9  692.37  6611.1  694.45  6711.2  717.42  6796.6  719.61  7146.3  722.78
#Mann= 17 ,-1 , 0
  3290.2    .035       0  3634.5     .05       0  3956.2     .07       0
  4307.9    .035       0  4581.9     .07       0  4617.3    .035       0
  4731.8     .07       0  4848.8     .12       0  5116.1     .05       0
    5183     .12       0  5243.5      .1       0  5342.1     .07       0
  5539.4    .035       0  5835.4     .07       0  5934.1    .035       0
  6369.3     .12       0  6796.6     .07       0
Bank Sta=5116.1,5183
XS Rating Curve= 0 ,0
Exp/Cntr=0.3,0.1

Type RM Length L Ch R = 1 ,51877   ,1239,1239,1239
BEGIN DESCRIPTION:
Dry Comal Creek 44.0
END DESCRIPTION:
XS GIS Cut Line= 3
      2211777.59     13784863.19      2212255.03     13782931.75
      2212829.93     13781369.76
#Sta/Elev= 30
  3209.5  708.65  3274.7   705.8  3464.8  703.84    3527  706.64  3552.8  701.93
  3599.4  700.64  4013.8  696.13  4752.8  694.79    4914   686.4  4948.5  684.57
  4956.3  677.45  4957.8  676.45  5023.2  677.45  5049.7  682.38  5209.3   687.2
  5384.9  690.53    5476  687.94    5494  681.26  5506.5  687.17  5573.8  690.94
  5717.7  699.55  5981.8  702.41  5997.9   702.5  6266.9  705.28    6340  705.89
  6506.3  707.89  6544.4  711.83  6591.5  707.82  6858.7  709.03  6863.5  709.11
#Mann= 13 ,-1 , 0
  3209.5     .05       0  3274.7    .035       0    4914     .12       0
  4956.3     .05       0  5023.2     .12       0  5209.3    .035       0
  5384.9     .12       0  5573.8    .035       0  5981.8     .07       0
  5997.9    .035       0  6266.9     .07       0    6340    .035       0
  6858.7     .07       0
Bank Sta=4956.3,5023.2
XS Rating Curve= 0 ,0
Exp/Cntr=0.3,0.1

Type RM Length L Ch R = 1 ,50638   ,719,719,719
BEGIN DESCRIPTION:
Dry Comal Creek 43.0
END DESCRIPTION:
XS GIS Cut Line= 3
      2212005.48     13785156.11      2213416.05     13783137.91
      2214077.95      13781445.2
#Sta/Elev= 30
    2666  713.42  2958.2   709.1  2974.6  702.02  3062.5  701.82  3082.2  698.78
  3218.7  695.38  3561.4  693.27  3588.6  693.16  3753.5  693.35  4057.6  693.37
  4391.9  691.45  4564.1  690.09    4742  686.42  4862.3  682.58  4979.9  680.15
  5014.5  679.37    5065  684.65  5152.9  685.89  5276.4  684.68  5291.2  678.65
  5292.7  677.65  5358.2  678.65  5360.5  685.32    5385  693.51  5432.1  700.41
  5886.4  706.03  6145.6  707.76  6284.6  710.42    6403   709.5  6945.8  716.03
#Mann= 17 ,-1 , 0
    2666    .035       0  2958.2     .07       0  3062.5    .035       0
  3561.4     .07       0  3588.6    .035       0  3753.5     .07       0
  4057.6     .05       0  4391.9     .12       0  4564.1      .1       0
    4742     .12       0  4862.3     .07       0  4979.9    .035       0
  5291.2    .035       0  5358.2    .035       0  5886.4    .063       0
  6145.6    .035       0  6284.6     .07       0
Bank Sta=5291.2,5358.2
XS Rating Curve= 0 ,0
Exp/Cntr=0.3,0.1