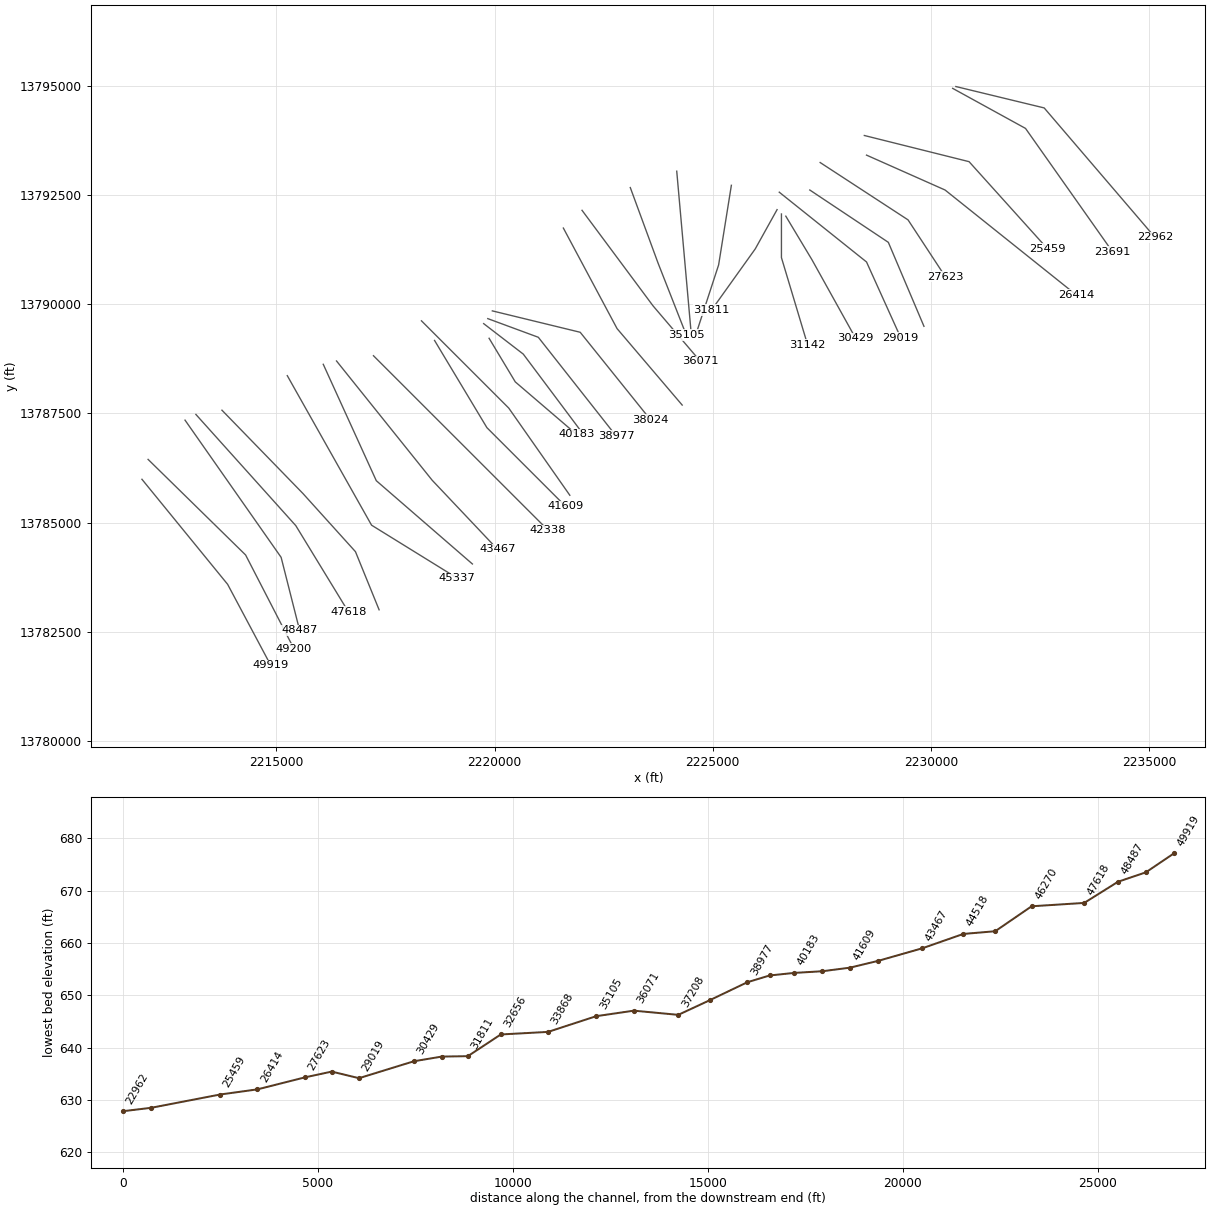
HEC-RAS study Dry Comal Creek.prj: Dry Comal Creek Base Level Engineering

--- Dry Comal Creek.g01 (geometry) --- (continued)

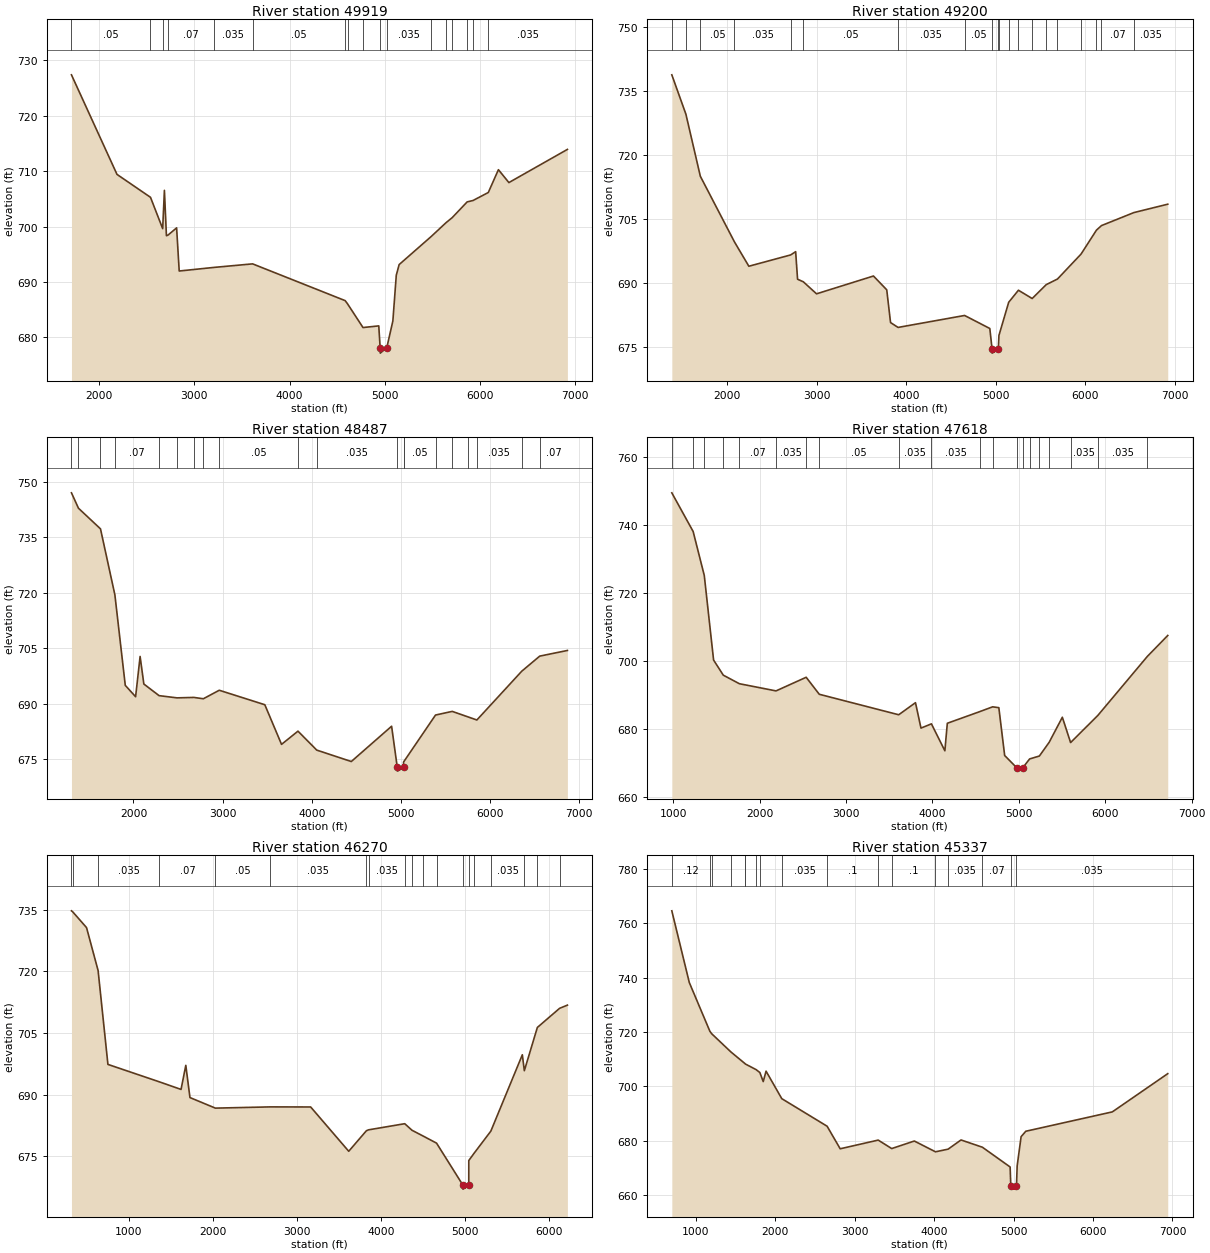
Type RM Length L Ch R = 1 ,49919   ,719,719,719
BEGIN DESCRIPTION:
X18930
END DESCRIPTION:
XS GIS Cut Line= 3
      2211918.68     13785991.62      2213882.63     13783582.79
      2214869.33     13781728.67
#Sta/Elev= 30
  1709.1   727.4  2187.3  709.42  2539.1  705.28  2667.1  699.62  2685.3  706.54
  2706.4  698.34  2724.2  698.47  2813.4  699.76  2840.7  691.97  3206.7  692.62
  3611.5  693.26  4583.6  686.62    4609  686.03  4770.9  681.76  4936.4  682.06
  4950.9  678.14  4952.4  677.14    5021  678.14  5084.5  682.95  5120.4  691.21
  5150.4  693.13  5488.3  698.22  5642.4  700.69  5707.8  701.61  5864.6  704.45
  5927.2  704.71  6086.8  706.15    6193  710.27  6302.9  707.94  6917.4  713.93
#Mann= 17 ,-1 , 0
  1709.1     .05       0  2539.1    .035       0  2667.1     .05       0
  2724.2     .07       0  3206.7    .035       0  3611.5     .05       0
  4583.6     .12       0    4609     .05       0  4770.9    .035       0
  4950.9    .035       0    5021    .035       0  5488.3    .094       0
  5642.4    .035       0  5707.8    .094       0  5864.6    .035       0
  5927.2    .094       0  6086.8    .035       0
Bank Sta=4950.9,5021
XS Rating Curve= 0 ,0
Exp/Cntr=0.3,0.1

Type RM Length L Ch R = 1 ,49200   ,713,713,713
BEGIN DESCRIPTION:
X18929
END DESCRIPTION:
XS GIS Cut Line= 3
      2212059.73     13786447.37      2214294.96     13784255.53
      2215400.12     13782110.22
#Sta/Elev= 30
    1379   738.7  1536.6  729.47  1697.7  714.95  2079.2  699.57  2240.1  693.87
  2707.7  696.52  2763.3  697.28  2784.6  690.83  2849.4  690.22  2996.7  687.41
  3633.1  691.58  3781.5  688.35    3824  680.68    3908  679.54  4651.8  682.34
  4933.7  679.29  4958.8  674.52  4960.3  673.52  5028.9  674.52  5035.7  677.66
  5144.7  685.43  5253.7  688.25  5407.3  686.31  5564.3  689.56  5689.9  690.87
  5953.6  696.72    6126  702.33  6181.9  703.39  6544.5  706.44  6922.8   708.4
#Mann= 20 ,-1 , 0
    1379    .035       0  1536.6     .07       0  1697.7     .05       0
  2079.2    .035       0  2707.7     .07       0  2849.4     .05       0
    3908    .035       0  4651.8     .05       0  4958.8     .05       0
  5028.9     .05       0  5035.7    .035       0  5144.7     .07       0
  5253.7     .05       0  5407.3     .07       0  5564.3     .05       0
  5689.9    .035       0  5953.6     .07       0    6126    .035       0
  6181.9     .07       0  6544.5    .035       0
Bank Sta=4958.8,5028.9
XS Rating Curve= 0 ,0
Exp/Cntr=0.3,0.1

Type RM Length L Ch R = 1 ,48487   ,869,869,869
BEGIN DESCRIPTION:
X18928
END DESCRIPTION:
XS GIS Cut Line= 3
      2212906.08     13787347.97      2215108.76     13784201.28
      2215531.94     13782530.25
#Sta/Elev= 30
  1304.4  747.05  1383.1  742.88  1630.1   737.3  1791.6  719.44  1908.2  694.94
  2024.1  691.86  2074.7  702.76  2116.6   695.3  2287.8  692.15    2489  691.55
  2677.4  691.67  2784.3  691.31  2962.8  693.61  3474.1  689.69  3661.6  678.96
  3846.1  682.54  4056.8  677.41  4444.5  674.32  4896.7  683.87  4960.5  672.72
    4962  671.72  5030.6  672.72  5030.8  674.18  5389.4   686.9    5577  687.89
  5752.6  686.41  5853.4  685.56  6357.2  698.77  6558.8  702.85  6869.2  704.38
#Mann= 20 ,-1 , 0
  1304.4     .12       0  1383.1     .07       0  1630.1     .12       0
  1791.6     .07       0  2287.8     .07       0    2489     .12       0
  2677.4    .035       0  2784.3     .07       0  2962.8     .05       0
  3846.1    .035       0  4056.8    .035       0  4960.5     .05       0
  5030.6     .12       0  5030.8     .05       0  5389.4    .035       0
    5577    .035       0  5752.6     .05       0  5853.4    .035       0
  6357.2    .035       0  6558.8     .07       0
Bank Sta=4960.5,5030.6
XS Rating Curve= 0 ,0
Exp/Cntr=0.3,0.1

Type RM Length L Ch R = 1 ,47618   ,1348,1348,1348
BEGIN DESCRIPTION:
X18927
END DESCRIPTION:
XS GIS Cut Line= 3
      2213155.61     13787478.22      2215445.13     13784928.28
      2216649.56     13782953.45
#Sta/Elev= 30
   983.2  749.43    1230  738.07  1358.8  725.16  1466.7   700.3  1579.1  695.86
    1765  693.35  2189.2  691.24  2538.2  695.24  2689.7  690.25  3609.2  684.23
  3803.4  687.78    3867  680.31    3988  681.56  4143.5  673.64    4172  681.73
    4545  685.13  4696.5  686.56  4768.2  686.31  4835.7  672.26    4975  668.67
  4976.5  667.67  5045.5  668.67  5124.5  671.25  5237.7  672.11  5350.9  676.15
  5503.3   683.5  5598.8  676.06  5914.7  684.05  6487.1  701.37  6723.3  707.52
#Mann= 20 ,-1 , 0
   983.2     .12       0    1230    .035       0  1358.8     .12       0
  1579.1    .035       0    1765     .07       0  2189.2    .035       0
  2538.2     .07       0  2689.7     .05       0  3609.2    .035       0
    3988    .035       0    4545    .035       0  4696.5    .035       0
    4975     .05       0  5045.5      .1       0  5124.5      .1       0
  5237.7     .12       0  5350.9      .1       0  5598.8    .035       0
  5914.7    .035       0  6487.1      .1       0
Bank Sta=4975,5045.5
XS Rating Curve= 0 ,0
Exp/Cntr=0.3,0.1

Type RM Length L Ch R = 1 ,46270   ,933,933,933
BEGIN DESCRIPTION:
X18926
END DESCRIPTION:
XS GIS Cut Line= 4
      2213752.43     13787575.84      2215607.89     13785666.12
      2216812.32     13784331.49      2217354.22     13782998.43
#Sta/Elev= 30
   316.5  734.75   330.4  734.53   495.8  730.67   633.5   720.2   750.2  697.38
  1361.6  693.14  1620.1  691.29  1676.7  697.15  1726.1  689.31  2028.3  686.74
    2680  687.04    3162  687.02  3614.8  676.24  3824.9  681.24  3851.3  681.46
  4281.1  682.95  4367.6  681.35  4496.7  679.98  4659.5  678.22  4972.1  668.03
  4973.6  667.03  5042.8  668.03    5043  673.99  5107.1  675.79  5305.2  681.14
  5679.9  699.72  5703.7  695.85  5858.5  706.37  6123.5  711.03  6215.9   711.8
#Mann= 19 ,-1 , 0
   316.5    .035       0   330.4     .12       0   633.5    .035       0
  1361.6     .07       0  2028.3     .05       0    2680    .035       0
  3824.9     .07       0  3851.3    .035       0  4281.1     .07       0
  4367.6    .035       0  4496.7     .07       0  4659.5    .035       0
  4972.1    .035       0  5042.8    .035       0  5107.1     .07       0
  5305.2    .035       0  5703.7    .063       0  5858.5      .1       0
  6123.5    .094       0
Bank Sta=4972.1,5042.8
XS Rating Curve= 0 ,0
Exp/Cntr=0.3,0.1

Type RM Length L Ch R = 1 ,45337   ,819,819,819
BEGIN DESCRIPTION:
Dry Comal Creek 42.0
END DESCRIPTION:
XS GIS Cut Line= 3
      2215249.84     13788367.91      2217181.24     13784939.13
      2219145.21     13783723.85
#Sta/Elev= 30
   695.7  764.55   915.8   738.2  1175.2  720.27  1198.6  719.35  1441.1  712.65
  1619.5  708.34  1622.6  708.24  1758.4  706.16  1804.5  705.11  1846.8  701.79
  1882.4  705.62  2080.1  695.52  2651.2  685.38  2815.8  677.09  3294.5  680.28
  3464.6  677.17  3749.3  679.94  4015.7  675.98  4174.5  676.95  4337.4  680.33
  4606.6  677.66  4955.7   670.4  4964.4  663.26  4965.9  662.26  5035.6  663.26
  5044.3  670.82  5094.1  681.54  5152.9  683.53  6242.7  690.65  6940.6   704.7
#Mann= 17 ,-1 , 0
   695.7     .12       0  1175.2     .07       0  1198.6     .12       0
  1441.1     .07       0  1619.5     .12       0  1622.6     .07       0
  1758.4     .12       0  1804.5     .07       0  2080.1    .035       0
  2651.2      .1       0  3294.5     .12       0  3464.6      .1       0
  4015.7     .12       0  4174.5    .035       0  4606.6     .07       0
  4964.4     .05       0  5035.6    .035       0
Bank Sta=4964.4,5035.6
XS Rating Curve= 0 ,0
Exp/Cntr=0.3,0.1

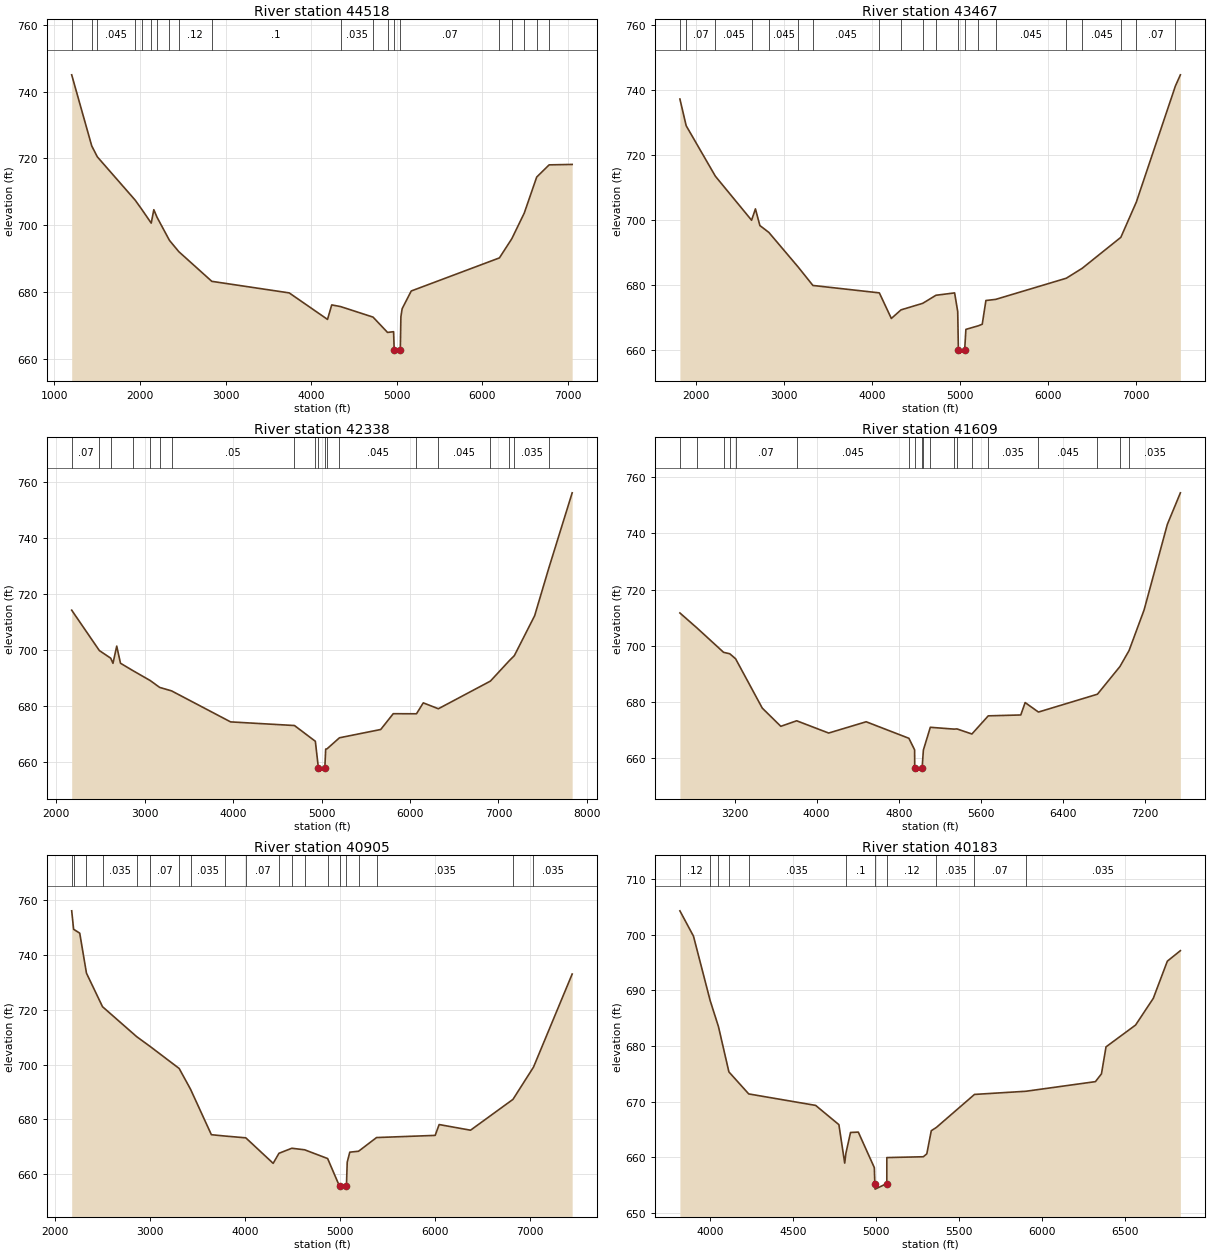
Type RM Length L Ch R = 1 ,44518   ,1051,1051,1051
BEGIN DESCRIPTION:
Dry Comal Creek 41.0
END DESCRIPTION:
XS GIS Cut Line= 3
      2216074.49     13788628.34      2217289.75     13785959.09
      2219492.47     13784049.34
#Sta/Elev= 30
  1202.3  745.01  1436.4  723.75  1502.3  720.46  1945.4  707.48  2024.9  704.62
  2131.6  700.64  2162.1  704.65  2199.9  702.38    2345  695.47  2454.4  692.09
  2839.4  683.22  3744.1  679.76  4191.6  671.83    4241  676.17    4345  675.66
  4723.5  672.52  4893.2  667.93  4963.7  668.15  4970.8  662.74  4972.3  661.74
  5042.1  662.74  5049.2  672.62  5063.5  675.02  5169.8  680.33  6200.3  690.23
  6345.5  695.99  6490.7  703.65  6635.9  714.42  6781.2  718.07  7050.5   718.2
#Mann= 20 ,-1 , 0
  1202.3     .12       0  1436.4    .035       0  1502.3    .045       0
  1945.4    .045       0  2024.9     .07       0  2131.6     .12       0
  2199.9     .07       0    2345     .12       0  2454.4     .12       0
  2839.4      .1       0    4345    .035       0  4723.5     .07       0
  4893.2     .07       0  4970.8    .035       0  5042.1     .07       0
  6200.3     .07       0  6345.5     .07       0  6490.7    .035       0
  6635.9     .07       0  6781.2     .07       0
Bank Sta=4970.8,5042.1
XS Rating Curve= 0 ,0
Exp/Cntr=0.3,0.1

Type RM Length L Ch R = 1 ,43467   ,1129,1129,1129
BEGIN DESCRIPTION:
Dry Comal Creek 40.0
END DESCRIPTION:
XS GIS Cut Line= 3
      2216378.32     13788704.29      2218570.13     13785969.94
      2220067.55     13784385.72
#Sta/Elev= 30
  1815.9  737.22  1887.4  728.99  2218.8  713.46  2629.9  699.91  2673.7   703.4
  2724.2  698.28  2826.5  696.15  3157.1  685.57  3326.5  679.83  4081.1  677.55
  4217.4  669.67  4327.4  672.32  4573.8  674.33  4723.8  676.81    4936  677.54
  4971.3  671.79  4978.8     660  4980.3     659  5050.1     660  5064.1  666.31
  5204.5  667.41  5249.7  667.89  5291.3   675.2  5401.9  675.54  6204.6  682.06
  6383.8  685.09  6823.9  694.65  6999.9  705.51  7443.2  741.21  7500.2  744.67
#Mann= 20 ,-1 , 0
  1815.9     .12       0  1887.4     .07       0  2218.8    .045       0
  2629.9    .035       0  2826.5    .045       0  3157.1    .035       0
  3326.5    .045       0  4081.1    .035       0  4327.4    .045       0
  4573.8    .035       0  4723.8    .035       0  4978.8    .035       0
  5050.1    .035       0  5204.5    .035       0  5401.9    .045       0
  6204.6    .035       0  6383.8    .045       0  6823.9    .035       0
  6999.9     .07       0  7443.2    .045       0
Bank Sta=4978.8,5050.1
XS Rating Curve= 0 ,0
Exp/Cntr=0.3,0.1

Type RM Length L Ch R = 1 ,42338   ,729,729,729
BEGIN DESCRIPTION:
Dry Comal Creek 39.0
END DESCRIPTION:
XS GIS Cut Line= 3
      2217224.99     13788825.01        2219225.       13786825.
      2221225.03     13784824.97
#Sta/Elev= 30
  2176.4   714.2  2489.3  699.74  2617.3  697.02  2643.1  695.19  2685.5  701.34
    2728  695.21  2866.5   692.6  3063.7  689.02  3170.7  686.56  3305.9  685.31
  3972.5  674.22  4694.3  672.92  4930.5  667.28  4965.3   657.6  4966.8   656.6
  5037.3   657.6  5047.3  664.48  5062.6  664.58    5203  668.53  5669.5   671.5
  5810.9  677.15  6073.5  677.12  6150.3  681.03    6321  678.92  6909.4  688.82
  7124.6  696.19  7179.7  697.93    7409   712.2  7567.6  729.09  7833.3  756.19
#Mann= 19 ,-1 , 0
  2176.4     .07       0  2489.3    .035       0  2617.3     .07       0
  2866.5    .035       0  3063.7     .05       0  3170.7    .035       0
  3305.9     .05       0  4694.3    .035       0  4930.5     .07       0
  4965.3     .05       0  5037.3     .07       0  5062.6    .035       0
    5203    .045       0  6073.5    .035       0    6321    .045       0
  6909.4    .035       0  7124.6    .045       0  7179.7    .035       0
  7567.6     .07       0
Bank Sta=4965.3,5037.3
XS Rating Curve= 0 ,0
Exp/Cntr=0.3,0.1

Type RM Length L Ch R = 1 ,41609   ,704,704,704
BEGIN DESCRIPTION:
Dry Comal Creek 38.0
END DESCRIPTION:
XS GIS Cut Line= 3
      2218625.02     13789174.97        2219825.       13787175.
      2221624.98     13785375.02
#Sta/Elev= 30
  2667.6  711.65  2835.2  706.27  3093.5  697.62  3153.9  697.11  3210.4  695.33
  3470.3  677.75  3651.1  671.26  3805.7  673.23  4117.5  668.86  4482.9  672.88
  4899.4  666.99  4955.2  662.87  4956.2  656.29  4957.7  655.29  5028.2  656.29
  5040.7  662.81  5108.2  670.91  5339.5  670.26  5367.9  670.33  5513.6  668.52
    5673  674.99  5989.9   675.3  6032.3  679.72  6162.1  676.34    6737   682.7
  6956.3  692.56  7045.5  698.27    7192  712.76  7418.3  743.21  7545.5  754.46
#Mann= 19 ,-1 , 0
  2667.6    .035       0  2835.2     .05       0  3093.5     .07       0
  3153.9     .05       0  3210.4     .07       0  3805.7    .045       0
  4899.4    .035       0  4956.2    .035       0  5028.2    .035       0
  5040.7     .07       0  5108.2    .035       0  5339.5    .045       0
  5367.9    .035       0  5513.6    .045       0    5673    .035       0
  6162.1    .045       0    6737    .035       0  6956.3     .07       0
  7045.5    .035       0
Bank Sta=4956.2,5028.2
XS Rating Curve= 0 ,0
Exp/Cntr=0.3,0.1

Type RM Length L Ch R = 1 ,40905   ,722,722,722
BEGIN DESCRIPTION:
Dry Comal Creek 37.0
END DESCRIPTION:
XS GIS Cut Line= 3
      2218325.01     13789624.99        2220325.       13787625.
      2221724.99     13785625.02
#Sta/Elev= 30
  2171.8  756.01  2192.1  749.29  2256.6  747.87  2327.3  733.31  2496.5  721.07
  2856.2  710.16  2999.8  706.54  3303.6  698.57  3422.9  691.03  3642.6  674.44
  3783.2  673.96    4005   673.3  4293.1  664.01  4354.3  667.67  4489.5   669.5
  4624.6  668.94  4866.7  665.75  4992.5  655.61    4994  654.61  5064.6  655.61
    5073  664.44    5100  668.08  5192.2  668.41  5381.7   673.4    5999  674.19
  6040.8  678.14  6371.3  676.08  6818.1  687.31  7034.2  699.06  7441.5  732.98
#Mann= 20 ,-1 , 0
  2171.8     .12       0  2192.1     .07       0  2327.3     .12       0
  2496.5    .035       0  2856.2     .05       0  2999.8     .07       0
  3303.6     .12       0  3422.9    .035       0  3783.2      .1       0
    4005     .07       0  4354.3      .1       0  4489.5     .07       0
  4624.6     .12       0  4866.7      .1       0  4992.5     .05       0
  5064.6      .1       0  5192.2    .035       0  5381.7    .035       0
  6818.1     .07       0  7034.2    .035       0
Bank Sta=4992.5,5064.6
XS Rating Curve= 0 ,0
Exp/Cntr=0.3,0.1

Type RM Length L Ch R = 1 ,40183   ,632,632,632
BEGIN DESCRIPTION:
Dry Comal Creek 36.0
END DESCRIPTION:
XS GIS Cut Line= 3
      2219875.02     13789224.97        2220475.       13788225.
      2221875.03     13787024.97
#Sta/Elev= 30
  3820.8  704.31  3902.4  699.76  4002.7  688.19  4052.7   683.5  4115.5  675.36
  4234.8   671.4  4637.1  669.34    4777  665.88    4812  658.97  4819.3  660.76
    4847  664.47  4893.7  664.54  4990.2  658.15  4993.2  655.29  4994.7  654.29
  5065.3  655.29  5065.4  659.96  5284.9  660.11  5305.8  660.64  5332.7  664.79
  5363.4  665.38  5592.5  671.31  5901.7  671.88  6319.9  673.61  6356.2  675.01
  6383.6  679.86  6561.4  683.78  6667.9  688.58  6752.4  695.26  6830.9  697.15
#Mann= 11 ,-1 , 0
  3820.8     .12       0  4002.7    .035       0  4052.7     .12       0
  4115.5      .1       0  4234.8    .035       0  4819.3      .1       0
  4993.2     .05       0  5065.3     .12       0  5363.4    .035       0
  5592.5     .07       0  5901.7    .035       0
Bank Sta=4993.2,5065.3
XS Rating Curve= 0 ,0
Exp/Cntr=0.3,0.1

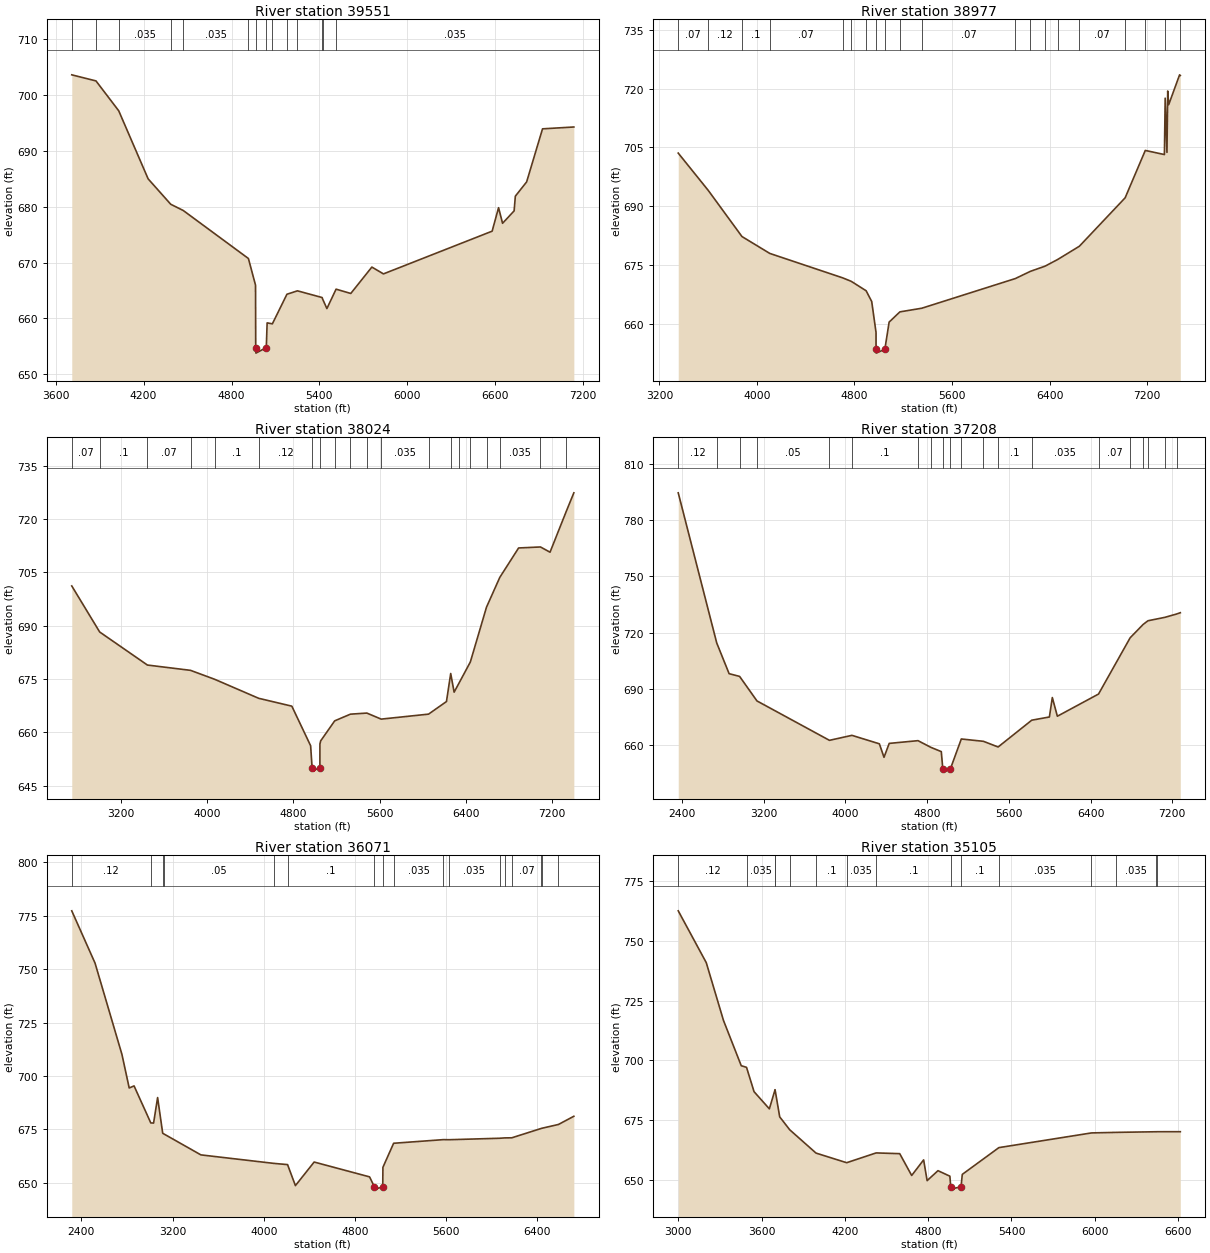
Type RM Length L Ch R = 1 ,39551   ,574,574,574
BEGIN DESCRIPTION:
X18925
END DESCRIPTION:
XS GIS Cut Line= 3
      2219750.82     13789560.87      2220658.66     13788861.73
      2222025.68     13787035.56
#Sta/Elev= 30
  3709.7  703.57    3875  702.48  4030.2  697.14  4230.9  684.97  4385.4  680.42
  4470.5  679.31  4915.5  670.72    4964  665.95  4965.3   654.8  4966.8   653.8
  5037.5   654.8  5043.2  659.21    5079  659.04  5178.3  664.33  5250.2  664.94
  5418.8  663.74  5421.5   663.5  5451.1  661.77  5513.8  665.24  5614.2  664.47
    5758  669.19  5837.2  667.97    6579  675.61  6622.8  679.81  6650.2  677.02
  6729.1  679.24  6737.4  681.87  6814.5  684.42  6922.9  693.91  7136.7  694.24
#Mann= 14 ,-1 , 0
  3709.7     .07       0    3875     .12       0  4030.2    .035       0
  4385.4     .07       0  4470.5    .035       0  4915.5     .12       0
  4965.3     .05       0  5037.5     .12       0    5079     .07       0
  5178.3     .12       0  5250.2     .07       0  5418.8    .035       0
  5421.5     .07       0  5513.8    .035       0
Bank Sta=4965.3,5037.5
XS Rating Curve= 0 ,0
Exp/Cntr=0.3,0.1

Type RM Length L Ch R = 1 ,38977   ,953,953,953
BEGIN DESCRIPTION:
X18924
END DESCRIPTION:
XS GIS Cut Line= 3
      2219844.74     13789675.68      2221003.03     13789247.84
      2222787.44      13786983.4
#Sta/Elev= 30
  3354.7  703.56  3601.1  694.03  3877.4  682.26  4105.6  677.95  4703.8  671.71
  4773.4  670.83  4895.8  668.42  4941.6  665.67  4976.9  657.79  4977.1   653.5
  4978.6   652.5  5049.4   653.5  5084.4  660.42  5172.6  663.03  5352.1  663.96
    6120  671.54  6242.4  673.37  6363.3   674.7  6467.1  676.41  6644.5  679.78
  7019.9  692.14  7185.3  704.24  7342.1  703.19  7344.1  707.76  7348.4  717.57
  7362.9  703.75  7369.3  719.41  7377.3  715.92  7466.6  723.54  7472.5  723.38
#Mann= 20 ,-1 , 0
  3354.7     .07       0  3601.1     .12       0  3877.4      .1       0
  4105.6     .07       0  4703.8     .12       0  4773.4     .07       0
  4895.8      .1       0  4977.1     .05       0  5049.4      .1       0
  5172.6     .12       0  5352.1     .07       0    6120    .035       0
  6242.4     .07       0  6363.3     .07       0  6467.1    .035       0
  6644.5     .07       0  7019.9     .07       0  7185.3    .063       0
  7344.1    .094       0  7466.6    .063       0
Bank Sta=4977.1,5049.4
XS Rating Curve= 0 ,0
Exp/Cntr=0.3,0.1

Type RM Length L Ch R = 1 ,38024   ,816,816,816
BEGIN DESCRIPTION:
Dry Comal Creek 35.0
END DESCRIPTION:
XS GIS Cut Line= 3
      2219949.04     13789853.09      2221963.08     13789362.63
      2223579.73     13787349.63
#Sta/Elev= 30
  2745.8  701.16  3004.6  688.21    3447  678.92  3846.9  677.43  4071.7   674.9
  4478.7  669.57  4786.1  667.36  4960.3  656.23  4973.7   650.1  4975.2   649.1
  5046.1   650.1  5046.5  656.72  5053.1  657.59  5183.4  663.23  5328.9  665.11
  5481.4  665.42  5614.4  663.72  6053.6  665.12  6219.6  668.66  6258.9  676.54
  6290.6   671.3  6338.8     674  6440.9  679.78  6590.8  695.19    6714  703.56
  6888.4  711.83  7091.3  712.11  7179.7  710.64  7330.4  722.13  7400.5  727.33
#Mann= 20 ,-1 , 0
  2745.8     .07       0  3004.6      .1       0    3447     .07       0
  3846.9     .07       0  4071.7      .1       0  4478.7     .12       0
  4973.7     .05       0  5046.1    .035       0  5183.4     .07       0
  5328.9     .12       0  5481.4     .12       0  5614.4    .035       0
  6053.6     .07       0  6258.9      .1       0  6338.8     .07       0
  6440.9    .035       0  6590.8     .07       0    6714    .035       0
  7091.3    .035       0  7330.4     .12       0
Bank Sta=4973.7,5046.1
XS Rating Curve= 0 ,0
Exp/Cntr=0.3,0.1

Type RM Length L Ch R = 1 ,37208   ,1137,1137,1137
BEGIN DESCRIPTION:
Dry Comal Creek 34.0
END DESCRIPTION:
XS GIS Cut Line= 3
      2221576.99      13791752.3      2222808.34     13789446.11
      2224300.29     13787693.33
#Sta/Elev= 30
  2362.8   794.5  2739.7  714.55  2860.9  698.18  2963.5  696.73  3133.9  683.65
  3843.4  662.67  4063.6  665.33  4332.2  660.82  4377.6  653.64  4428.6  661.04
  4710.3   662.5  4835.3  658.97  4938.5  656.66  4953.9  647.27  4955.4  646.27
  5026.3  647.27  5134.6  663.39    5351  662.15    5495  659.13  5824.3   673.4
  5997.1  675.11  6025.7  685.46  6075.1  675.51  6478.2  687.33  6787.8  717.29
  6914.6  724.38  6962.2  726.36  7126.9  728.17  7241.6  729.94  7278.9  730.64
#Mann= 20 ,-1 , 0
  2362.8     .12       0  2739.7      .1       0  2963.5    .035       0
  3133.9     .05       0  3843.4    .035       0  4063.6      .1       0
  4710.3     .12       0  4835.3      .1       0  4953.9     .05       0
  5026.3      .1       0  5134.6    .035       0    5351     .12       0
    5495      .1       0  5824.3    .035       0  6478.2     .07       0
  6787.8    .035       0  6914.6     .07       0  6962.2    .035       0
  7126.9     .07       0  7241.6     .07       0
Bank Sta=4953.9,5026.3
XS Rating Curve= 0 ,0
Exp/Cntr=0.3,0.1

Type RM Length L Ch R = 1 ,36071   ,966,966,966
BEGIN DESCRIPTION:
Dry Comal Creek 33.0
END DESCRIPTION:
XS GIS Cut Line= 3
       2222004.8     13792159.33      2223632.74     13789967.88
      2224718.04     13788694.74
#Sta/Elev= 30
  2316.5  777.36  2520.7  752.87  2756.4  710.16  2820.2  694.43  2862.8  695.39
  3009.6  678.06  3033.9  677.99  3069.3  689.93  3113.9  673.24  3129.5  672.75
    3449   663.1    4089  659.12  4208.9  658.55  4277.7  648.71    4442  659.75
  4928.1  652.81  4971.1  648.07  4972.6  647.07  5043.6  648.07  5045.1  657.28
    5139  668.54  5575.2  670.24  5624.3   670.2  6070.5  670.89  6112.1  671.05
  6175.4   671.1  6431.3  675.44  6435.8  675.52  6584.2  677.34  6719.4  681.18
#Mann= 17 ,-1 , 0
  2316.5     .12       0  3009.6    .035       0  3113.9     .07       0
  3129.5     .05       0    4089     .12       0  4208.9      .1       0
  4971.1     .05       0  5043.6      .1       0    5139    .035       0
  5575.2     .07       0  5624.3    .035       0  6070.5     .07       0
  6112.1    .035       0  6175.4     .07       0  6431.3    .035       0
  6435.8     .07       0  6584.2    .035       0
Bank Sta=4971.1,5043.6
XS Rating Curve= 0 ,0
Exp/Cntr=0.3,0.1

Type RM Length L Ch R = 1 ,35105   ,1237,1237,1237
BEGIN DESCRIPTION:
X18923
END DESCRIPTION:
XS GIS Cut Line= 3
      2223110.96     13792681.09      2223747.52      13790948.8
      2224394.51     13789300.04
#Sta/Elev= 30
  2999.5  762.62  3201.4  740.91  3325.6  716.67  3453.4  697.73  3491.4  697.05
  3545.8  686.84  3655.9  679.65  3696.9  687.68  3698.9  687.05  3730.4   676.3
  3802.6  670.89    3992  661.12  4212.7  657.09  4424.9  661.19    4595  660.88
  4681.1  651.74  4767.2  658.27  4792.4  649.58  4870.6  653.75  4956.3  651.44
  4962.4  647.02  4963.9  646.02  5036.7  647.02  5045.7   652.2  5309.4  663.41
  5976.4  669.57  6155.5   669.8  6441.2  670.06  6447.1  670.07  6616.2  670.08
#Mann= 15 ,-1 , 0
  2999.5     .12       0  3491.4    .035       0  3696.9    .063       0
  3698.9    .035       0  3802.6     .12       0    3992      .1       0
  4212.7    .035       0  4424.9      .1       0  4962.4     .05       0
  5036.7      .1       0  5309.4    .035       0  5976.4     .07       0
  6155.5    .035       0  6441.2     .07       0  6447.1    .035       0
Bank Sta=4962.4,5036.7
XS Rating Curve= 0 ,0
Exp/Cntr=0.3,0.1

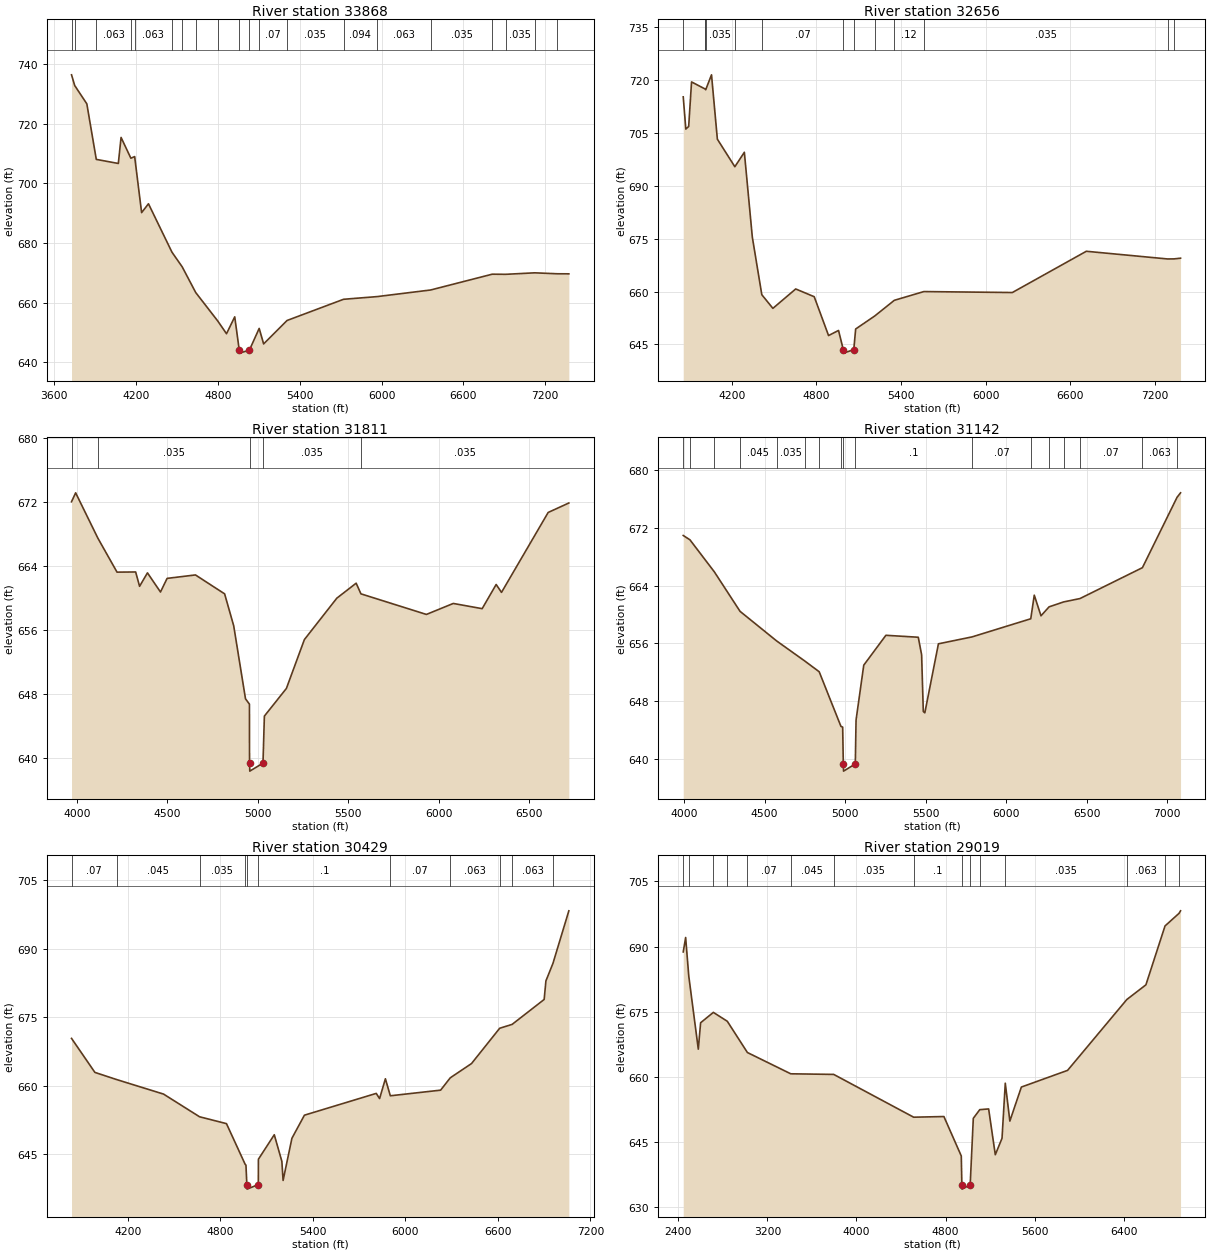
Type RM Length L Ch R = 1 ,33868   ,1212,1212,1212
BEGIN DESCRIPTION:
X18922
END DESCRIPTION:
XS GIS Cut Line= 2
      2224175.37     13793056.75      2224498.87     13789425.23
#Sta/Elev= 30
  3726.6  736.41  3749.8  732.83  3838.8  726.67  3908.1  708.03  4069.7  706.66
  4089.8   715.4  4161.7  708.42  4189.4  708.97  4240.4  690.16  4290.6  693.14
  4462.8   676.9  4538.2  671.95  4636.8  663.36  4798.5   653.8  4862.8  649.52
  4923.1  655.19  4956.2  644.01  4957.7  643.01  5030.5  644.01  5102.3   651.3
    5135   646.1  5306.4  653.96  5720.8  661.08  5966.7  661.98  6359.4   664.2
  6810.8   669.5    6910  669.46  7121.6  669.96  7287.9  669.64  7372.5  669.62
#Mann= 20 ,-1 , 0
  3726.6    .035       0  3749.8     .07       0  3908.1    .063       0
  4161.7    .035       0  4189.4    .063       0  4462.8    .035       0
  4538.2     .12       0  4636.8    .035       0  4798.5     .12       0
  4956.2     .05       0  5030.5     .12       0  5102.3     .07       0
  5306.4    .035       0  5720.8    .094       0  5966.7    .063       0
  6359.4    .035       0  6810.8     .07       0    6910    .035       0
  7121.6     .07       0  7287.9    .035       0
Bank Sta=4956.2,5030.5
XS Rating Curve= 0 ,0
Exp/Cntr=0.3,0.1

Type RM Length L Ch R = 1 ,32656   ,845,845,845
BEGIN DESCRIPTION:
X18921
END DESCRIPTION:
XS GIS Cut Line= 3
      2225427.61     13792733.22      2225135.43     13790907.06
      2224613.66     13789310.44
#Sta/Elev= 30
    3855  715.21  3873.4  706.07  3893.7  706.82    3914  719.45  4010.8  717.43
  4011.8  717.37  4014.4  717.23  4055.7  721.46  4097.2  703.21  4221.3  695.39
  4288.7  699.49  4345.3  675.43  4412.6  659.09  4491.2  655.22  4653.2  660.72
  4784.6  658.52  4886.2  647.51  4957.1  648.95  4990.8  643.52  4992.3  642.52
  5065.2  643.52  5078.6  649.36  5213.8  653.05    5353   657.5  5562.6  659.98
  6190.5  659.71  6715.5  671.41  7292.4  669.23  7337.9  669.25  7384.1  669.45
#Mann= 13 ,-1 , 0
    3855    .063       0  4010.8    .035       0  4011.8    .063       0
  4014.4    .035       0  4221.3    .063       0  4412.6     .07       0
  4990.8     .05       0  5065.2     .07       0  5213.8    .035       0
    5353     .12       0  5562.6    .035       0  7292.4     .07       0
  7337.9    .035       0
Bank Sta=4990.8,5065.2
XS Rating Curve= 0 ,0
Exp/Cntr=0.3,0.1

Type RM Length L Ch R = 1 ,31811   ,669,669,669
BEGIN DESCRIPTION:
Dry Comal Creek 30.0
END DESCRIPTION:
XS GIS Cut Line= 3
      2226474.98     13792174.97        2225975.       13791275.
      2224974.99     13789874.99
#Sta/Elev= 30
  3970.5     672  3993.3  673.11  4116.2  667.45  4222.1  663.21  4325.1  663.23
  4346.8  661.44  4390.3  663.12  4462.4  660.73    4499  662.43  4655.7  662.86
    4817   660.5  4867.3  656.51  4932.5   647.4  4954.3  646.73  4954.8  639.37
  4956.3  638.37  5029.2  639.37  5036.9  645.24  5158.6  648.69  5258.1  654.79
  5437.5  659.96  5544.4  661.83  5570.8   660.5  5932.8  657.93  6081.5   659.3
  6241.2  658.65  6318.6  661.67  6348.1  660.68  6606.2  670.66  6720.5  671.84
#Mann= 5 ,-1 , 0
  3970.5    .063       0  4116.2    .035       0  4954.8    .035       0
  5029.2    .035       0  5570.8    .035       0
Bank Sta=4954.8,5029.2
XS Rating Curve= 0 ,0
Exp/Cntr=0.3,0.1

Type RM Length L Ch R = 1 ,31142   ,713,713,713
BEGIN DESCRIPTION:
Dry Comal Creek 29.0
END DESCRIPTION:
XS GIS Cut Line= 3
        2226575.     13792074.98        2226575.       13791075.
      2227174.99     13789075.04
#Sta/Elev= 30
  3994.4  670.94  4036.1  670.34  4187.6   665.9  4347.2  660.43  4574.3  656.33
    4749  653.55  4838.6  652.06  4973.7  644.49  4984.4  644.39  4988.5  639.29
    4990  638.29  5062.9  639.29  5067.5  645.36  5115.3  652.97  5252.8  657.11
  5453.8  656.84  5474.6  654.42  5485.1  646.55  5494.6  646.37    5579  655.93
  5788.2  656.89  6152.3   659.4  6174.1  662.67  6215.9  659.81    6266  661.05
    6356  661.73  6457.8   662.2  6845.7  666.48  7060.8  676.23  7082.4  676.85
#Mann= 17 ,-1 , 0
  3994.4    .063       0  4036.1     .07       0  4187.6    .035       0
  4347.2    .045       0  4574.3    .035       0    4749    .045       0
  4838.6    .035       0  4973.7      .1       0  4988.5     .05       0
  5062.9      .1       0  5788.2     .07       0  6152.3    .035       0
    6266     .07       0    6356    .035       0  6457.8     .07       0
  6845.7    .063       0  7060.8    .094       0
Bank Sta=4988.5,5062.9
XS Rating Curve= 0 ,0
Exp/Cntr=0.3,0.1

Type RM Length L Ch R = 1 ,30429   ,1410,1410,1410
BEGIN DESCRIPTION:
Dry Comal Creek 28.0
END DESCRIPTION:
XS GIS Cut Line= 3
      2226674.99     13792025.01        2227275.       13791025.
      2228274.98     13789225.03
#Sta/Elev= 30
  3834.3  670.36  3985.9  662.92  4129.4  661.33    4431  658.18  4664.6  653.22
  4839.2  651.72  4960.9  642.79  4965.5  642.66  4971.3   638.4  4972.8   637.4
  5045.7   638.4  5046.3  643.94  5149.2  649.29  5198.4  643.47  5206.4   639.3
  5263.6  648.52  5344.8  653.57  5810.4  658.33  5832.2   657.2  5869.9  661.53
  5901.8  657.81    6228  659.04  6290.6  661.74  6428.2  664.85    6611  672.57
  6691.7  673.42  6899.5  678.87  6910.9  682.93  6956.4  686.75  7059.6  698.25
#Mann= 11 ,-1 , 0
  3834.3     .07       0  4129.4    .045       0  4664.6    .035       0
  4960.9      .1       0  4971.3     .05       0  5045.7      .1       0
  5901.8     .07       0  6290.6    .063       0    6611    .094       0
  6691.7    .063       0  6956.4    .035       0
Bank Sta=4971.3,5045.7
XS Rating Curve= 0 ,0
Exp/Cntr=0.3,0.1

Type RM Length L Ch R = 1 ,29019   ,699,699,699
BEGIN DESCRIPTION:
Dry Comal Creek 27.0
END DESCRIPTION:
XS GIS Cut Line= 3
      2226524.98     13792575.02        2228525.       13790975.
        2229309.     13789238.67
#Sta/Elev= 30
  2444.1  688.77  2465.7  692.09  2493.9   683.2  2579.4  666.38  2600.2  672.46
  2714.7  674.85  2839.9   672.8  3020.4  665.61  3409.8  660.71  3795.5  660.57
  4513.4  650.72  4785.3  650.87  4941.3  641.79  4946.4  635.16  4947.9  634.16
  5021.2  635.16  5049.3  650.46  5107.4  652.46    5187  652.62  5246.8  642.08
  5307.1  645.86  5336.5  658.55  5377.5  649.83  5480.9  657.66    5896   661.5
  6428.3  677.82  6599.4  681.19  6771.1  694.75  6897.7  697.67  6910.5  698.23
#Mann= 15 ,-1 , 0
  2444.1    .094       0  2493.9    .063       0  2714.7      .1       0
  2839.9    .063       0  3020.4     .07       0  3409.8    .045       0
  3795.5    .035       0  4513.4      .1       0  4946.4     .05       0
  5021.2      .1       0  5107.4     .07       0  5336.5    .035       0
  6428.3    .063       0  6771.1      .1       0  6897.7    .094       0
Bank Sta=4946.4,5021.2
XS Rating Curve= 0 ,0
Exp/Cntr=0.3,0.1

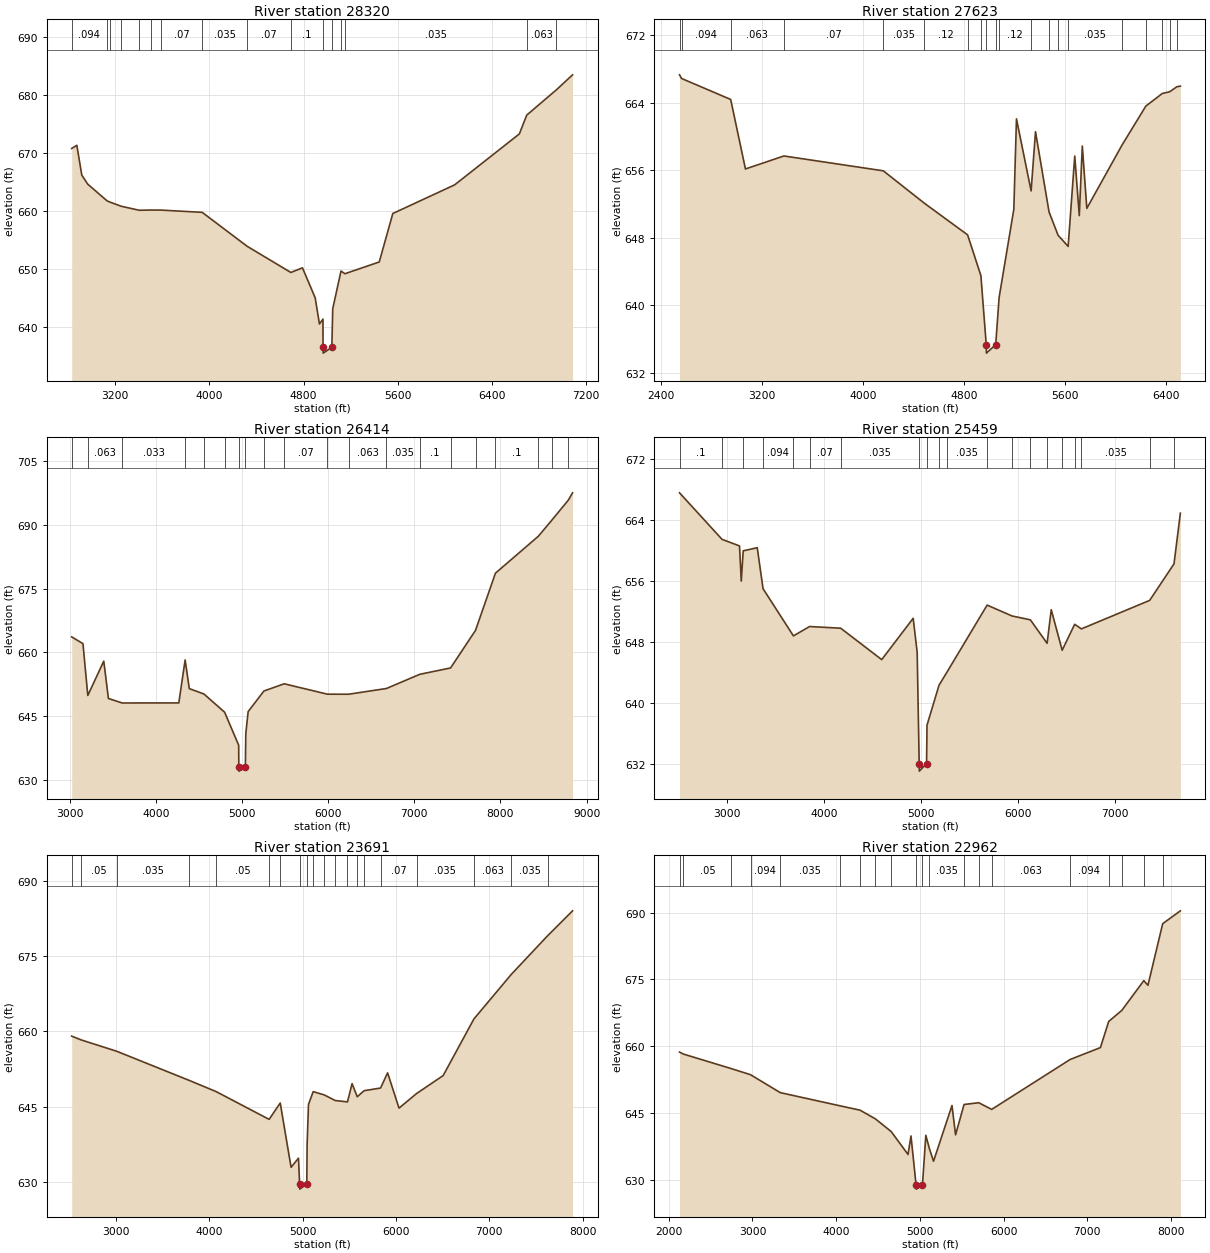
Type RM Length L Ch R = 1 ,28320   ,697,697,697
BEGIN DESCRIPTION:
Dry Comal Creek 26.0
END DESCRIPTION:
XS GIS Cut Line= 3
      2227225.04     13792624.97        2229025.       13791425.
      2229841.39     13789499.18
#Sta/Elev= 30
  2829.8  670.76  2873.3  671.31  2915.4  666.16  2966.5  664.59  3130.6  661.71
  3155.9  661.49  3251.4  660.78  3403.9  660.09  3505.7  660.13  3588.6  660.12
  3938.4  659.73  4320.3  653.87  4691.6  649.35  4790.3  650.15  4898.4  644.97
  4934.5  640.45  4964.5   641.3  4964.8  636.42  4966.3  635.42  5039.7  636.42
  5047.4  643.08  5117.7   649.6  5150.8  649.13  5442.6  651.16  5557.9  659.53
  6083.3  664.48  6633.2  673.28  6695.4  676.52    6948   680.9  7084.8  683.48
#Mann= 16 ,-1 , 0
  2829.8    .094       0  3130.6    .035       0  3155.9     .07       0
  3251.4    .035       0  3403.9     .07       0  3505.7    .035       0
  3588.6     .07       0  3938.4    .035       0  4320.3     .07       0
  4691.6      .1       0  4964.8     .05       0  5039.7      .1       0
  5117.7     .12       0  5150.8    .035       0  6695.4    .063       0
    6948    .035       0
Bank Sta=4964.8,5039.7
XS Rating Curve= 0 ,0
Exp/Cntr=0.3,0.1

Type RM Length L Ch R = 1 ,27623   ,1209,1209,1209
BEGIN DESCRIPTION:
X18920
END DESCRIPTION:
XS GIS Cut Line= 3
      2227462.53       13793255.      2229476.54     13791940.16
      2230332.21     13790635.78
#Sta/Elev= 30
  2548.4  667.29  2564.3  666.86  2953.4  664.37  3070.3  656.13  3374.7  657.67
  4161.9  655.91  4484.9  652.09  4829.2  648.32  4934.4  643.48  4976.7   635.3
  4978.2   634.3  5051.6   635.3  5078.5  640.88    5195  651.34    5216  662.07
  5331.9  653.53  5366.7  660.55  5474.1  651.03  5545.6  648.27  5625.1  646.95
  5677.4  657.66  5713.3   650.6  5737.2  658.85    5773  651.46  6052.4  658.98
  6240.5  663.59  6370.9  665.08  6428.7  665.28  6486.4  665.88  6513.6  665.95
#Mann= 20 ,-1 , 0
  2548.4      .1       0  2564.3    .094       0  2953.4    .063       0
  3374.7     .07       0  4161.9    .035       0  4484.9     .12       0
  4829.2     .07       0  4934.4      .1       0  4976.7     .05       0
  5051.6      .1       0  5078.5     .12       0  5331.9     .07       0
  5474.1    .035       0  5545.6     .07       0  5625.1    .035       0
  6052.4    .035       0  6240.5    .094       0  6370.9    .035       0
  6428.7    .094       0  6486.4    .063       0
Bank Sta=4976.7,5051.6
XS Rating Curve= 0 ,0
Exp/Cntr=0.3,0.1

Type RM Length L Ch R = 1 ,26414   ,955,955,955
BEGIN DESCRIPTION:
Dry Comal Creek 25.0
END DESCRIPTION:
XS GIS Cut Line= 3
      2228524.99       13793425.        2230325.       13792625.
      2233325.03     13790224.97
#Sta/Elev= 30
  3025.4  663.65    3156  662.06  3212.2  649.85  3397.5  657.94  3451.5  649.14
  3610.6  648.08  4268.1  648.09  4341.6  658.22  4389.9  651.46  4560.1  650.19
  4799.9   645.9    4963  638.12  4964.3  633.02  4965.8  632.02  5040.4  633.02
  5045.6  640.87  5072.8  646.04  5255.8   650.9  5490.9   652.6  5992.9  650.15
  6238.6  650.14  6677.4  651.49  7065.1  654.84  7421.7  656.33  7711.2  665.19
  7942.2  678.66  8440.3  687.37  8594.1  691.09  8788.5  695.89  8837.1   697.6
#Mann= 20 ,-1 , 0
  3025.4      .1       0  3212.2    .063       0  3610.6    .033       0
  4341.6     .07       0  4560.1    .035       0  4799.9      .1       0
  4964.3     .05       0  5040.4      .1       0  5255.8    .035       0
  5490.9     .07       0  5992.9    .035       0  6238.6    .063       0
  6677.4    .035       0  7065.1      .1       0  7421.7    .063       0
  7711.2    .035       0  7942.2      .1       0  8440.3    .094       0
  8594.1      .1       0  8788.5      .1       0
Bank Sta=4964.3,5040.4
XS Rating Curve= 0 ,0
Exp/Cntr=0.3,0.1

Type RM Length L Ch R = 1 ,25459   ,1768,1768,1768
BEGIN DESCRIPTION:
Dry Comal Creek 24.0
END DESCRIPTION:
XS GIS Cut Line= 3
      2228474.95     13793875.01        2230875.       13793275.
      2232674.98     13791275.03
#Sta/Elev= 30
  2508.6  667.55  2946.7  661.45  3127.1  660.58  3145.2  655.97  3165.3  659.94
  3310.1  660.35  3369.9  654.97  3683.2  648.78  3849.4  650.01  4170.4  649.79
  4593.4  645.67  4918.1  651.09  4959.3  646.61  4979.9  632.04  4981.4  631.04
  5056.1  632.04  5060.6  637.07  5184.8  642.32  5264.2  643.98  5680.7  652.82
  5938.5  651.39    6126  650.89    6299  647.81  6341.7  652.21  6454.3   646.9
  6583.2   650.3  6652.3   649.7  7356.9  653.44  7607.5  658.23  7673.2  664.88
#Mann= 20 ,-1 , 0
  2508.6      .1       0  2946.7    .094       0  3165.3    .035       0
  3369.9    .094       0  3683.2    .063       0  3849.4     .07       0
  4170.4    .035       0  4979.9     .05       0  5056.1      .1       0
  5184.8     .12       0  5264.2    .035       0  5680.7     .07       0
  5938.5    .035       0    6126     .07       0    6299    .035       0
  6454.3     .12       0  6583.2     .07       0  6652.3    .035       0
  7356.9    .094       0  7607.5    .035       0
Bank Sta=4979.9,5056.1
XS Rating Curve= 0 ,0
Exp/Cntr=0.3,0.1

Type RM Length L Ch R = 1 ,23691   ,729,729,729
BEGIN DESCRIPTION:
X18919
END DESCRIPTION:
XS GIS Cut Line= 3
      2230499.17       13794956.      2232168.86     13794037.67
      2234160.88     13791211.29
#Sta/Elev= 30
    2528  659.05  2627.8  658.31  3012.1  656.02  3789.3  650.19  4075.5  647.97
  4642.3  642.43    4761   645.7  4877.3  632.86  4956.5  634.68  4968.7   629.5
  4970.2   628.5  5045.4   629.5  5048.9  637.34  5063.7  645.42    5114  647.97
  5231.9  647.32  5349.9   646.2  5481.1  645.92  5530.5  649.57  5585.7  646.95
  5659.7  648.16  5835.3  648.69    5911  651.72    6033  644.68  6221.9   647.6
  6505.9  651.18  6834.9  662.48  7236.6  671.41  7623.8  679.09  7891.4  684.08
#Mann= 20 ,-1 , 0
    2528     .05       0  2627.8     .05       0  3012.1    .035       0
  3789.3    .063       0  4075.5     .05       0  4642.3     .12       0
    4761      .1       0  4968.7     .05       0  5045.4      .1       0
    5114     .12       0  5231.9      .1       0  5349.9      .1       0
  5481.1    .035       0  5585.7    .063       0  5659.7    .035       0
  5835.3     .07       0  6221.9    .035       0  6834.9    .063       0
  7236.6    .035       0  7623.8    .094       0
Bank Sta=4968.7,5045.4
XS Rating Curve= 0 ,0
Exp/Cntr=0.3,0.1

Type RM Length L Ch R = 1 ,22962   ,1034,1034,1034
BEGIN DESCRIPTION:
X18918
END DESCRIPTION:
XS GIS Cut Line= 3
      2230572.21     13794997.73      2232596.71     13794507.26
      2235131.26     13791545.06
#Sta/Elev= 30
    2129  658.64  2176.3  658.19  2748.3  654.92  2976.6  653.56  3332.1  649.53
  4046.7  646.56  4284.7  645.59  4469.2  643.62  4656.2  640.79  4858.2  635.63
  4893.4  639.79  4953.8  628.84  4955.3  627.84  5030.6  628.84  5070.5  639.94
  5113.4  636.94  5162.6  634.11    5383  646.63  5425.8  640.04  5527.2  646.86
  5702.3  647.26  5857.1  645.76  6794.3  656.98  7155.8  659.65  7254.6  665.53
  7411.6  668.02  7674.1   674.7  7723.3  673.65  7899.6   687.5  8110.6  690.39
#Mann= 20 ,-1 , 0
    2129     .05       0  2176.3     .05       0  2748.3    .035       0
  2976.6    .094       0  3332.1    .035       0  4046.7     .07       0
  4284.7    .035       0  4469.2     .05       0  4656.2     .07       0
  4953.8     .05       0  5030.6      .1       0  5113.4    .035       0
  5527.2    .063       0  5702.3    .035       0  5857.1    .063       0
  6794.3    .094       0  7254.6    .094       0  7411.6      .1       0
  7674.1      .1       0  7899.6    .035       0
Bank Sta=4953.8,5030.6
XS Rating Curve= 0 ,0
Exp/Cntr=0.3,0.1