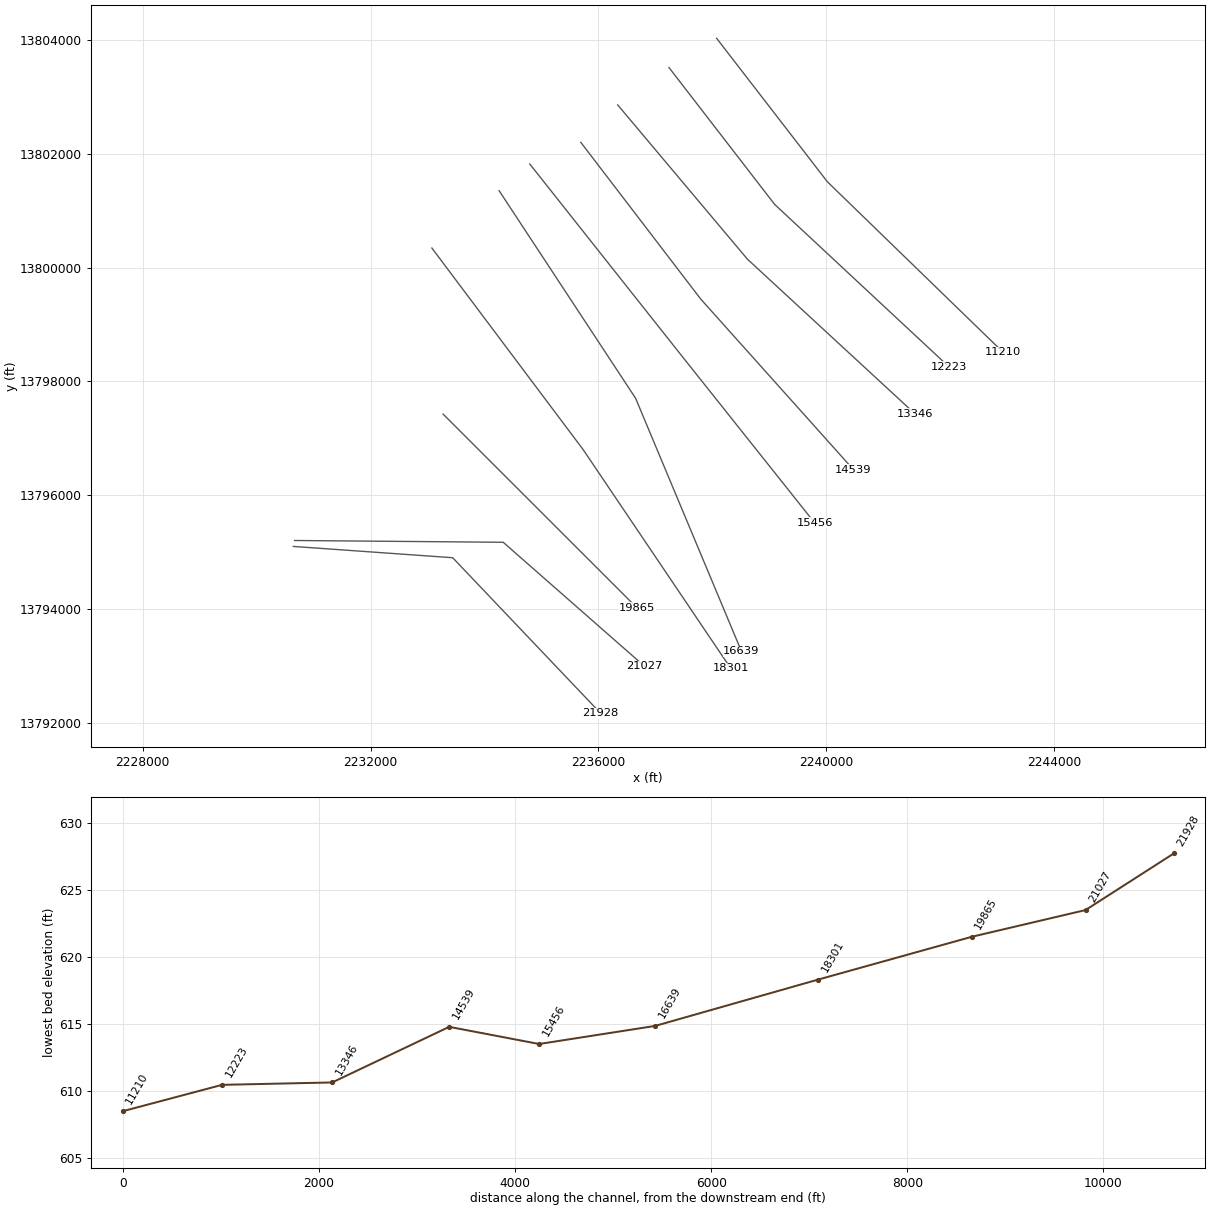
HEC-RAS study Dry Comal Creek.prj: Dry Comal Creek Base Level Engineering

--- Dry Comal Creek.g01 (geometry) --- (continued)

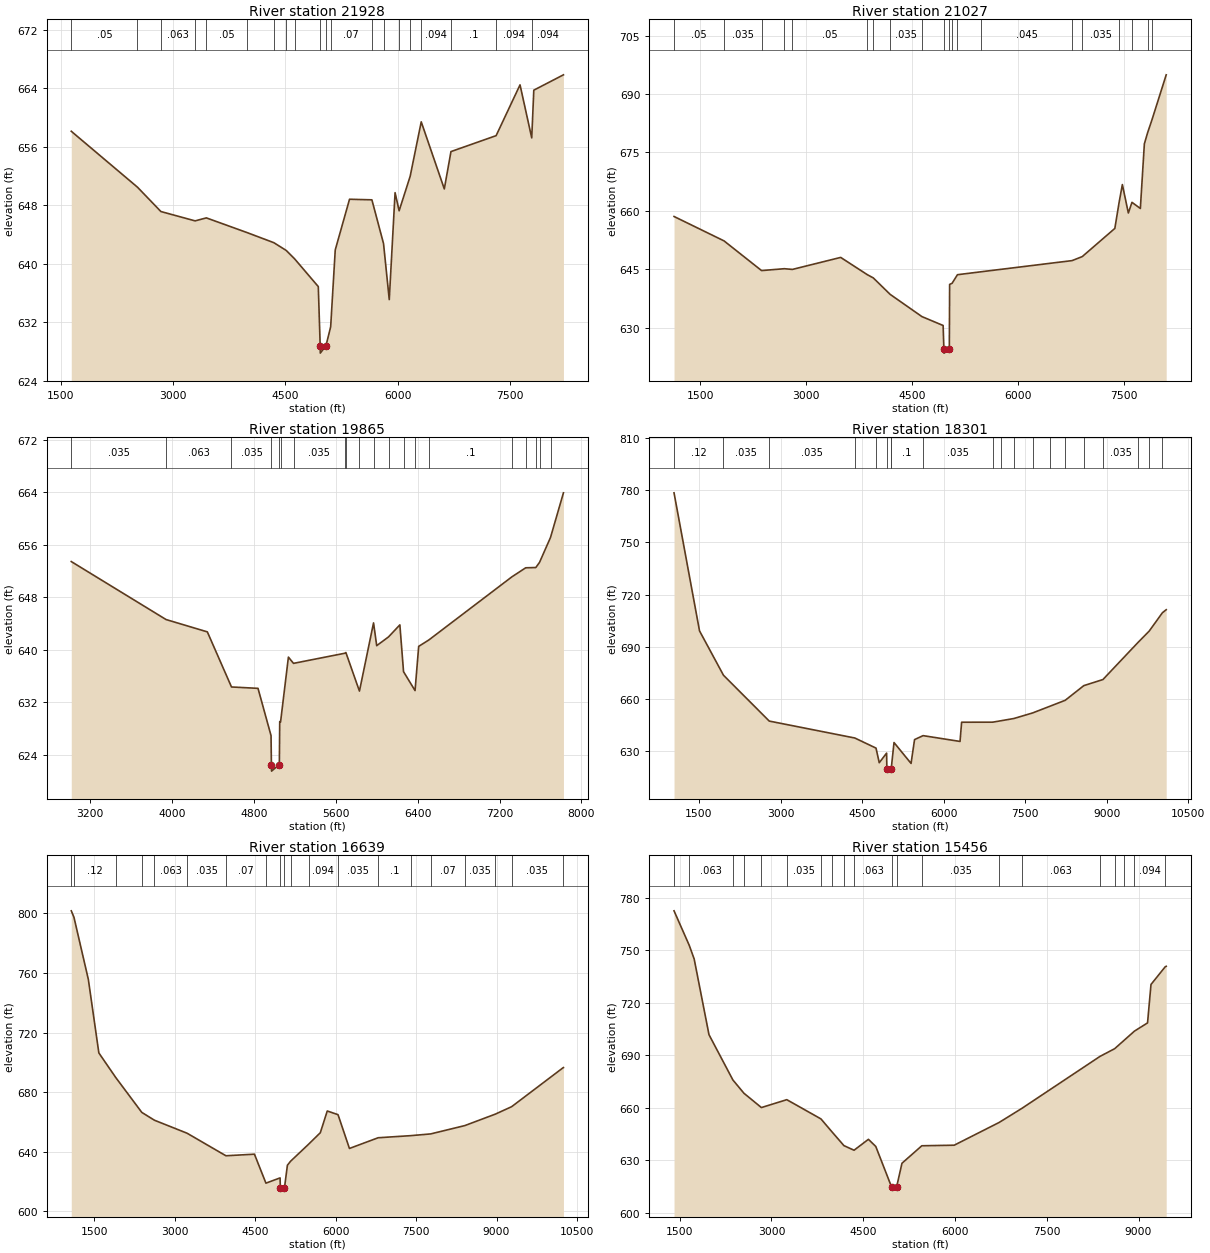
Type RM Length L Ch R = 1 ,21928   ,901,901,901
BEGIN DESCRIPTION:
X18917
END DESCRIPTION:
XS GIS Cut Line= 3
      2230645.29     13795102.08      2233441.97      13794903.8
      2236040.07     13792170.07
#Sta/Elev= 30
  1640.2   658.1  2524.6  650.45  2837.4  647.12  3294.6  645.84  3444.8  646.25
  3985.8  644.25    4346  642.86  4511.2   641.8  4623.6  640.65  4940.2  636.85
  4965.6  628.75  4967.1  627.75  5042.5  628.75  5105.6  631.35  5166.7  641.87
  5357.6   648.8  5656.4  648.72  5811.9  642.73  5888.3  635.07    5966   649.7
  6020.2  647.22  6167.8  651.95  6315.5  659.39  6623.7  650.21  6712.6  655.32
    7316   657.5  7635.3  664.45  7791.7  657.19  7819.3  663.72  8215.3  665.82
#Mann= 20 ,-1 , 0
  1640.2     .05       0  2524.6    .035       0  2837.4    .063       0
  3294.6    .035       0  3444.8     .05       0  3985.8    .035       0
    4346     .07       0  4511.2    .035       0  4623.6     .07       0
  4965.6     .05       0  5042.5      .1       0  5105.6     .07       0
  5656.4     .07       0  5811.9    .035       0  6020.2    .035       0
  6167.8    .063       0  6315.5    .094       0  6712.6      .1       0
    7316    .094       0  7791.7    .094       0
Bank Sta=4965.6,5042.5
XS Rating Curve= 0 ,0
Exp/Cntr=0.3,0.1

Type RM Length L Ch R = 1 ,21027   ,1162,1162,1162
BEGIN DESCRIPTION:
X18916
END DESCRIPTION:
XS GIS Cut Line= 3
      2230666.14     13795206.43      2234328.98     13795175.12
      2236811.33     13792995.24
#Sta/Elev= 30
  1126.9  658.58  1834.6  652.32    2366   644.7  2687.7  645.18  2802.8     645
  3485.8  648.08  3862.7  643.65  3947.9  642.81  4185.9   638.6  4636.1  632.89
  4935.8  630.61  4946.7  624.52  4948.2  623.52  5023.6  624.52  5027.9  641.15
  5062.6  641.44  5138.5  643.64  5471.9  644.39  6761.8  647.26  6905.3  648.29
  7366.4  655.52    7427  662.21  7472.9  666.77  7557.6  659.48  7608.9  662.21
  7727.5  660.64  7784.4  677.23  7830.9  680.11  7890.7  683.32  8093.5  694.93
#Mann= 20 ,-1 , 0
  1126.9     .05       0  1834.6    .035       0    2366    .063       0
  2687.7    .035       0  2802.8     .05       0  3862.7    .035       0
  3947.9     .07       0  4185.9    .035       0  4636.1      .1       0
  4946.7     .05       0  5023.6      .1       0  5062.6     .07       0
  5138.5    .035       0  5471.9    .045       0  6761.8    .045       0
  6905.3    .035       0    7427    .094       0  7608.9      .1       0
  7830.9    .063       0  7890.7      .1       0
Bank Sta=4946.7,5023.6
XS Rating Curve= 0 ,0
Exp/Cntr=0.3,0.1

Type RM Length L Ch R = 1 ,19865   ,1564,1564,1564
BEGIN DESCRIPTION:
Dry Comal Creek 20.0
END DESCRIPTION:
XS GIS Cut Line= 3
      2233274.97     13797425.03        2234675.       13796025.
      2236675.02     13794024.98
#Sta/Elev= 30
  3015.4  653.47  3941.4  644.63  4344.8  642.75  4580.7  634.35  4839.8  634.14
  4967.1  626.93  4970.6  622.52  4972.1  621.52  5048.3  622.52  5051.9  629.07
  5059.9  628.99  5136.8   638.9  5186.7  637.95  5687.2  639.49  5698.3   639.6
  5830.8  633.72  5968.5  644.12  5999.4  640.65  6114.7  641.98  6225.7  643.82
  6261.6  636.68    6374   633.8  6409.6  640.54  6509.1  641.52    7320  651.14
  7455.1  652.52  7553.9  652.56  7590.3  653.35  7697.5  657.15  7823.8  663.95
#Mann= 20 ,-1 , 0
  3015.4    .035       0  3941.4    .063       0  4580.7    .035       0
  4970.6    .035       0  5048.3    .035       0  5059.9      .1       0
  5186.7    .035       0  5687.2     .07       0  5698.3     .12       0
  5830.8      .1       0  5968.5    .035       0  6114.7    .035       0
  6261.6    .063       0    6374    .094       0  6509.1      .1       0
    7320    .094       0  7455.1    .035       0  7553.9    .094       0
  7590.3    .035       0  7697.5    .063       0
Bank Sta=4970.6,5048.3
XS Rating Curve= 0 ,0
Exp/Cntr=0.3,0.1

Type RM Length L Ch R = 1 ,18301   ,1662,1662,1662
BEGIN DESCRIPTION:
X18915
END DESCRIPTION:
XS GIS Cut Line= 3
      2233076.74     13800342.63      2235732.96     13796800.99
      2238319.76     13792964.21
#Sta/Elev= 30
  1040.6  778.53  1509.5  699.06  1949.9  673.54  2792.2  647.14    4366   637.4
  4756.5  631.58  4815.8  623.17  4951.2  628.69  4956.1  619.33  4957.6  618.33
  5033.8  619.33  5038.2  620.33  5087.6  634.78  5401.2  622.76  5465.2  636.48
  5622.7  638.76  6302.1  635.42  6331.2  646.48  6903.5  646.51  7062.8  647.37
  7290.5   648.6  7639.2  651.84  7960.7  655.74  8236.4  659.09  8579.6  667.55
  8930.8  671.05  9581.1  692.56  9782.4  698.95   10025   709.5   10095  711.24
#Mann= 20 ,-1 , 0
  1040.6     .12       0  1949.9    .035       0  2792.2    .035       0
    4366     .07       0  4756.5      .1       0  4956.1     .05       0
  5033.8     .07       0  5038.2      .1       0  5622.7    .035       0
  6903.5    .063       0  7062.8    .035       0  7290.5    .063       0
  7639.2    .035       0  7960.7      .1       0  8236.4    .094       0
  8579.6      .1       0  8930.8    .035       0  9581.1    .063       0
  9782.4    .094       0   10025    .063       0
Bank Sta=4956.1,5033.8
XS Rating Curve= 0 ,0
Exp/Cntr=0.3,0.1

Type RM Length L Ch R = 1 ,16639   ,1183,1183,1183
BEGIN DESCRIPTION:
X18914
END DESCRIPTION:
XS GIS Cut Line= 3
      2234257.27     13801349.61       2236653.1     13797703.77
      2238510.23     13793260.55
#Sta/Elev= 30
  1069.9   801.7  1119.6  797.44  1388.5  755.61  1584.3   706.3  1899.3   689.8
  2385.2  666.38  2621.1  661.12  3229.7   652.4  3953.6  637.27  4485.8  638.33
    4700  618.88  4964.3  622.41    4968  615.87  4969.5  614.87  5046.2  615.87
  5100.5  630.93  5161.1  633.64  5494.4  644.98    5714  652.73  5843.9  667.33
  6044.6  664.85  6257.3  642.17  6793.2  649.36  7398.1  650.76  7773.1  651.94
  8409.4  657.53  8978.4  665.22  9282.4  670.22 10242.7  696.39 10248.2  696.47
#Mann= 20 ,-1 , 0
  1069.9    .063       0  1119.6     .12       0  1899.3    .035       0
  2385.2     .12       0  2621.1    .063       0  3229.7    .035       0
  3953.6     .07       0    4700      .1       0    4968     .05       0
  5046.2      .1       0  5161.1    .035       0  5494.4    .094       0
  6044.6    .035       0  6793.2      .1       0  7398.1    .063       0
  7773.1     .07       0  8409.4    .035       0  8978.4    .094       0
  9282.4    .035       0 10242.7    .063       0
Bank Sta=4968,5046.2
XS Rating Curve= 0 ,0
Exp/Cntr=0.3,0.1

Type RM Length L Ch R = 1 ,15456   ,917,917,917
BEGIN DESCRIPTION:
X18913
END DESCRIPTION:
XS GIS Cut Line= 3
      2234795.44     13801818.38      2237434.35     13798485.02
      2239795.48     13795516.25
#Sta/Elev= 30
  1407.9  772.43  1656.8  752.71  1737.4  744.88  1979.4   701.7  2370.1  675.84
  2550.7  668.26    2836  660.09  3250.9   664.6    3809  653.62  3986.6  646.35
  4184.3  638.37  4350.3  635.73  4585.4  641.96  4705.5  637.88  4966.1  614.52
  4967.6  613.52  5044.5  614.52  5133.5   628.3  5458.1  638.28  5987.5   638.6
  6722.7   651.6  7096.9  659.71  8370.2  689.31  8609.8   693.7    8763  698.45
    8933  703.73  9147.6  708.44  9203.9  730.38  9437.1  740.51  9452.6  740.75
#Mann= 20 ,-1 , 0
  1407.9    .035       0  1656.8    .063       0  2370.1    .035       0
  2550.7    .063       0    2836    .063       0  3250.9    .035       0
    3809    .094       0  3986.6    .063       0  4184.3    .035       0
  4350.3    .063       0  4966.1     .05       0  5044.5      .1       0
  5458.1    .035       0  6722.7    .094       0  7096.9    .063       0
  8370.2    .063       0  8609.8    .035       0    8763    .063       0
    8933    .094       0  9437.1    .035       0
Bank Sta=4966.1,5044.5
XS Rating Curve= 0 ,0
Exp/Cntr=0.3,0.1

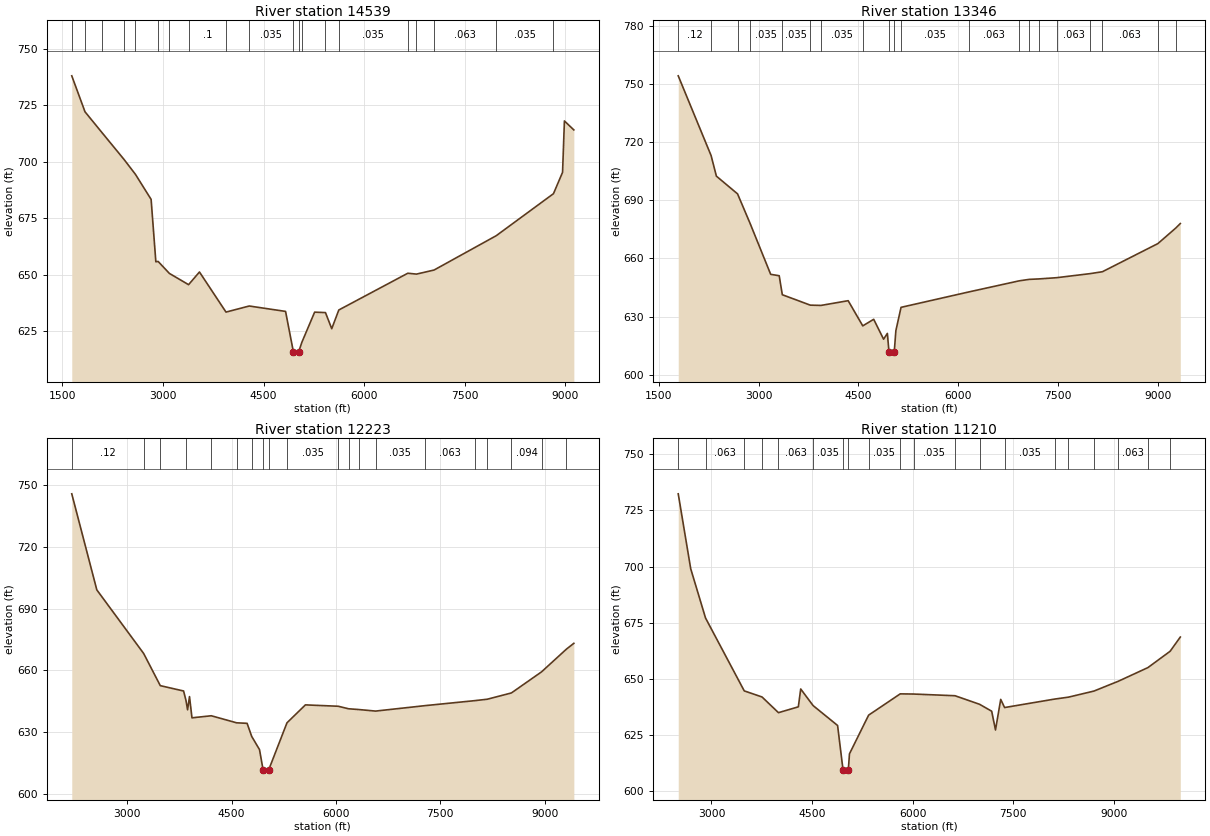
Type RM Length L Ch R = 1 ,14539   ,1193,1193,1193
BEGIN DESCRIPTION:
X18912
END DESCRIPTION:
XS GIS Cut Line= 3
      2235690.83     13802199.31      2237796.45      13799445.8
      2240477.67     13796449.67
#Sta/Elev= 30
  1640.7  738.06    1838  722.13  2084.3  713.17  2421.8  700.96  2590.5  694.41
  2823.9  683.34  2894.6   655.7  2928.1  655.86  3096.8  650.54  3382.5  645.56
  3544.8  651.18  3940.6  633.42  4287.3  636.11  4828.9  633.72  4945.6   615.8
  4947.1   614.8    5024   615.8  5070.9  619.97  5262.4   633.4  5424.1  633.19
  5517.3  626.06    5623  634.35    6652  650.63  6780.7  650.24  7043.9  652.05
  7969.9  667.24  8823.8  685.86  8959.5  695.32  8987.1  718.08  9127.7   714.1
#Mann= 20 ,-1 , 0
  1640.7    .063       0    1838    .063       0  2084.3    .063       0
  2421.8    .035       0  2590.5    .035       0  2928.1    .063       0
  3096.8    .035       0  3382.5      .1       0  3940.6    .035       0
  4287.3    .035       0  4945.6     .05       0    5024      .1       0
  5070.9     .12       0  5424.1      .1       0    5623    .035       0
    6652    .063       0  6780.7    .094       0  7043.9    .063       0
  7969.9    .035       0  8823.8    .094       0
Bank Sta=4945.6,5024
XS Rating Curve= 0 ,0
Exp/Cntr=0.3,0.1

Type RM Length L Ch R = 1 ,13346   ,1123,1123,1123
BEGIN DESCRIPTION:
X18911
END DESCRIPTION:
XS GIS Cut Line= 3
      2236338.67     13802856.26      2238615.32     13800147.68
      2241557.81     13797430.15
#Sta/Elev= 30
  1793.7  754.24  2287.4  713.11  2367.2  702.47  2685.1  693.33    2875  677.96
  3182.8  651.82  3310.7   651.1  3357.5   641.3  3778.1  635.92  3939.2  635.78
  4346.9  638.22  4566.2  625.23  4730.6  628.62  4878.9  618.36  4936.1  621.34
  4960.5  611.65    4962  610.65  5039.2  611.65  5063.6  622.73  5141.5  634.79
  6160.2  642.74  6915.1  648.45    7064  649.21  7210.2  649.45  7477.7  650.08
  7986.9   652.2  8167.1  653.16  9000.4  667.68  9270.2  675.73  9337.4  678.03
#Mann= 20 ,-1 , 0
  1793.7     .12       0  2287.4    .063       0  2685.1    .063       0
    2875    .035       0  3357.5    .035       0  3778.1     .12       0
  3939.2    .035       0  4566.2      .1       0  4960.5     .05       0
  5039.2      .1       0  5141.5    .035       0  6160.2    .063       0
  6915.1    .094       0    7064    .063       0  7210.2    .094       0
  7477.7    .063       0  7986.9    .035       0  8167.1    .063       0
  9000.4    .063       0  9270.2    .094       0
Bank Sta=4960.5,5039.2
XS Rating Curve= 0 ,0
Exp/Cntr=0.3,0.1

Type RM Length L Ch R = 1 ,12223   ,1013,1013,1013
BEGIN DESCRIPTION:
X18910
END DESCRIPTION:
XS GIS Cut Line= 3
      2237238.53     13803513.15      2239092.24     13801110.52
      2242151.73       13798258.
#Sta/Elev= 30
  2201.9  745.92    2562  699.17  3235.7   668.2  3474.5  652.56  3809.3  649.96
  3843.2  645.45  3866.8   640.8  3894.4  647.23  3929.9   636.9  4207.7   637.9
  4572.2  634.47  4722.3  634.22  4788.9  627.83  4900.8  621.44  4952.8  611.47
  4954.3  610.47  5031.7  611.47  5295.6  634.47  5560.7   643.2  6032.6  642.53
  6181.3   641.3  6328.4  640.93  6569.5  640.18  7275.4  642.81  7998.3  645.27
  8174.9  645.95  8522.2  649.01  8954.7  659.26  9313.1  670.34  9419.5  673.16
#Mann= 20 ,-1 , 0
  2201.9     .12       0  3235.7     .07       0  3474.5    .035       0
  3843.2    .035       0  4207.7     .07       0  4572.2    .035       0
  4788.9      .1       0  4952.8     .05       0  5031.7      .1       0
  5295.6    .035       0  6032.6    .063       0  6181.3    .094       0
  6328.4    .063       0  6569.5    .035       0  7275.4    .063       0
  7998.3    .035       0  8174.9    .063       0  8522.2    .094       0
  8954.7    .063       0  9313.1    .035       0
Bank Sta=4952.8,5031.7
XS Rating Curve= 0 ,0
Exp/Cntr=0.3,0.1

Type RM Length L Ch R = 1 ,11210   ,1150,1150,1150
BEGIN DESCRIPTION:
X18909
END DESCRIPTION:
XS GIS Cut Line= 3
      2238075.39     13804026.06      2240019.09     13801506.46
      2243105.58     13798509.95
#Sta/Elev= 30
  2504.8  732.36  2690.9     699  2912.2  677.07  3488.7  644.66  3753.7  641.95
    3999  634.96  4295.1  637.56  4330.4   645.5  4515.2  638.12  4880.2  629.26
  4961.2   609.5  4962.7   608.5  5040.1   609.5  5057.4  616.65  5342.8  633.86
  5813.8  643.33  6013.6  643.25  6630.4   642.5  6995.9   638.7  7177.3  635.61
  7233.8  627.25  7311.8  640.87  7369.5  637.24  8115.2  641.01  8321.7  641.87
  8700.9  644.57  9065.7  648.96  9505.6  655.02  9836.7  662.28  9988.8  668.62
#Mann= 20 ,-1 , 0
  2504.8    .063       0  2912.2    .063       0  3488.7      .1       0
  3753.7    .094       0    3999    .063       0  4515.2    .035       0
  4961.2     .05       0  5040.1      .1       0  5342.8    .035       0
  5813.8    .063       0  6013.6    .035       0  6630.4    .035       0
  6995.9    .035       0  7369.5    .035       0  8115.2    .035       0
  8321.7    .063       0  8700.9      .1       0  9065.7    .063       0
  9505.6    .063       0  9836.7    .035       0
Bank Sta=4961.2,5040.1
XS Rating Curve= 0 ,0
Exp/Cntr=0.3,0.1