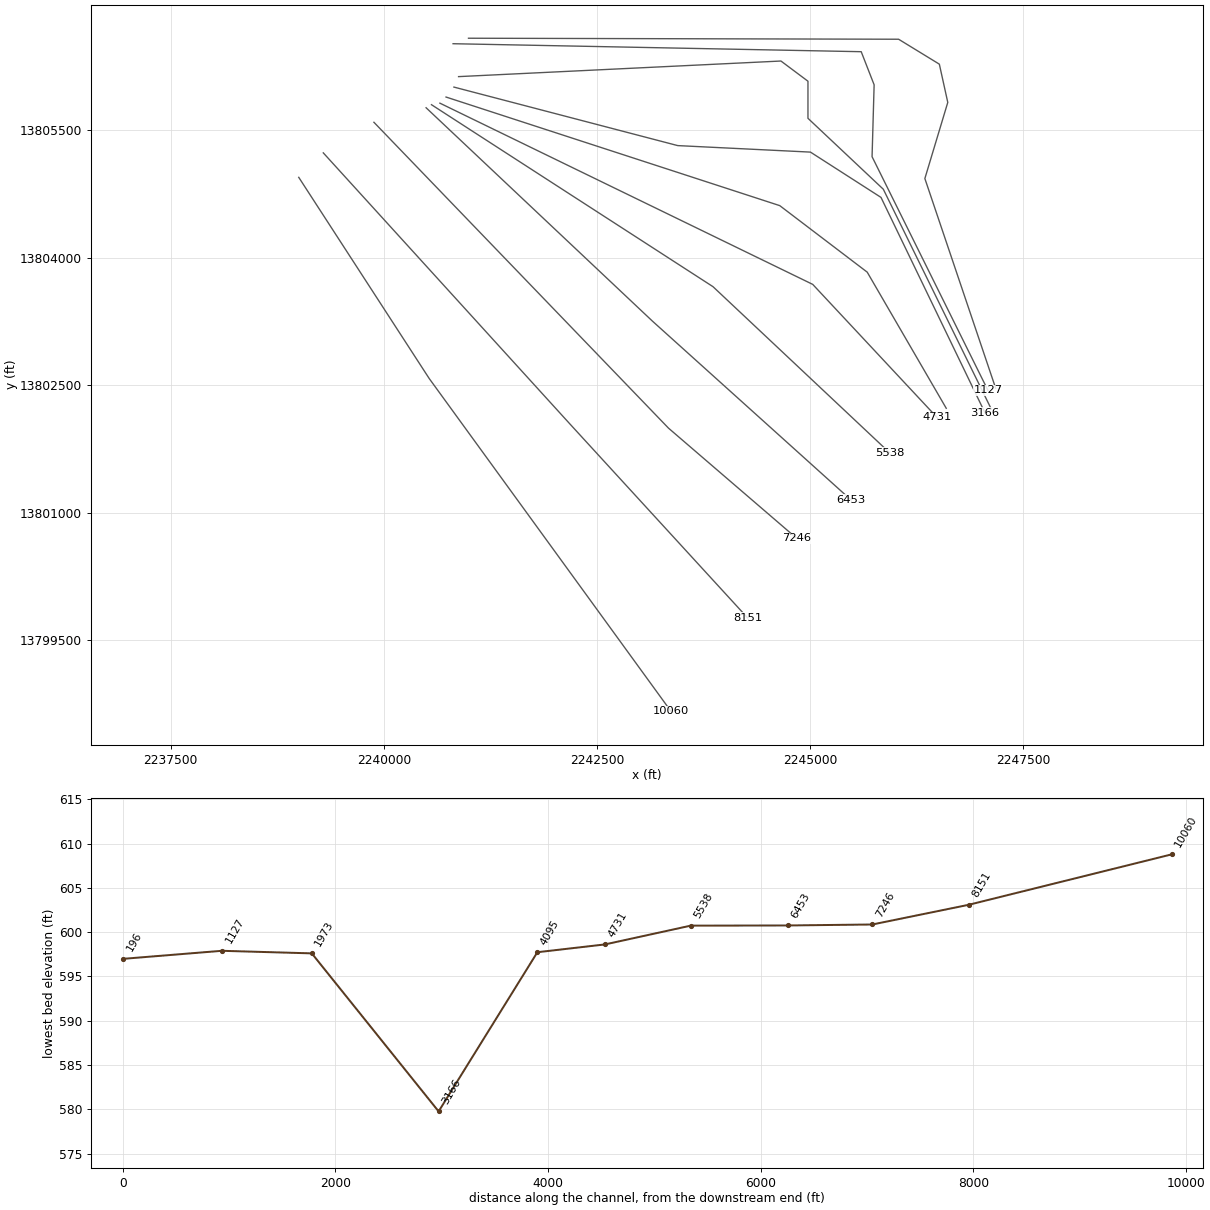
HEC-RAS study Dry Comal Creek.prj: Dry Comal Creek Base Level Engineering

--- Dry Comal Creek.g01 (geometry) --- (continued)

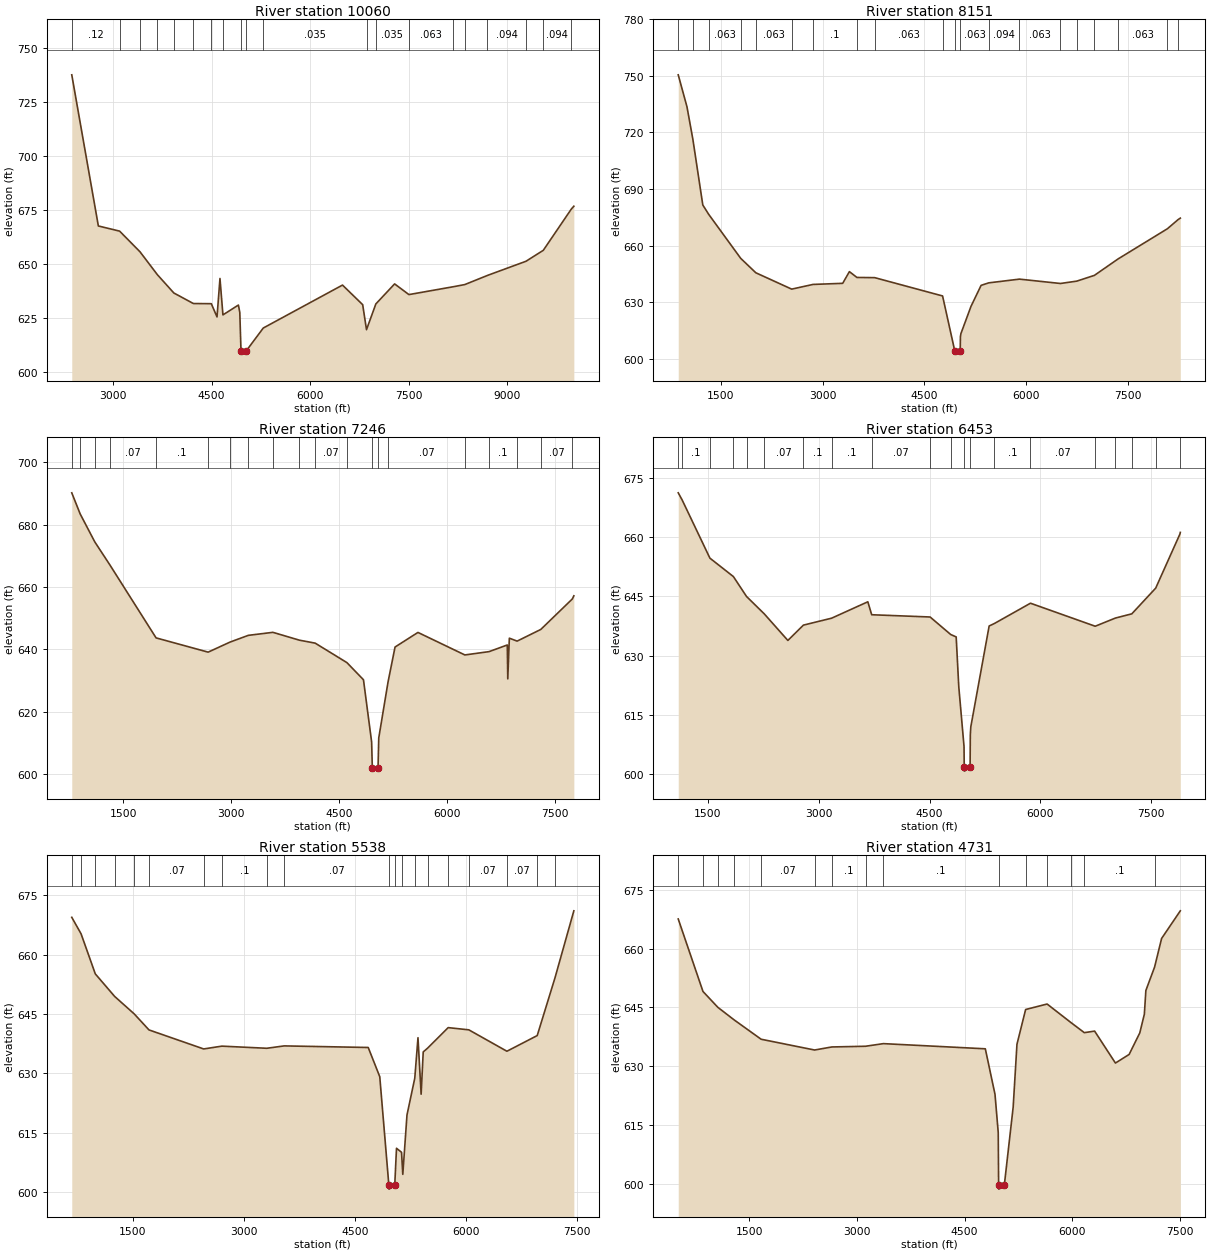
Type RM Length L Ch R = 1 ,10060   ,1909,1909,1909
BEGIN DESCRIPTION:
X18908
END DESCRIPTION:
XS GIS Cut Line= 3
      2239002.26     13804943.88        2240532.     13802577.28
      2243366.51     13798662.96
#Sta/Elev= 30
  2368.3  737.57  2773.6  667.62  3097.4  665.24  3407.9  655.68  3673.1  645.07
  3923.8  636.61  4221.6  631.73  4494.6  631.66  4581.7  625.54  4626.7  643.32
  4671.8  626.47  4907.7  631.03  4928.8  627.59  4947.1  609.78  4948.6  608.78
  5026.1  609.78  5286.6   620.4  6493.7  640.27  6801.4   631.2  6859.6  619.63
  7001.9  631.54    7288  640.81  7506.1  635.87  8177.7  639.48    8357   640.5
  8703.1  644.74  9289.7  651.29  9553.4  656.35  9979.8  675.41 10019.1  676.76
#Mann= 20 ,-1 , 0
  2368.3     .12       0  3097.4    .035       0  3407.9    .063       0
  3673.1    .094       0  3923.8      .1       0  4221.6    .094       0
  4494.6    .063       0  4671.8      .1       0  4947.1     .05       0
  5026.1      .1       0  5286.6    .035       0  6859.6     .12       0
  7001.9    .035       0  7506.1    .063       0  8177.7    .063       0
    8357    .094       0  8703.1    .094       0  9289.7    .063       0
  9553.4    .094       0  9979.8    .063       0
Bank Sta=4947.1,5026.1
XS Rating Curve= 0 ,0
Exp/Cntr=0.3,0.1

Type RM Length L Ch R = 1 ,8151    ,905,905,905
BEGIN DESCRIPTION:
X18907
END DESCRIPTION:
XS GIS Cut Line= 3
      2239290.24     13805231.81      2242178.73     13802046.37
      2244266.39     13799760.74
#Sta/Elev= 30
     873  750.55  1001.8  733.61  1088.7  716.36  1234.9  681.58  1321.7  676.63
  1793.6  653.29  2016.3  645.66  2544.2     637  2858.4  639.49  3295.5  640.07
  3394.1  646.27  3505.1  643.19  3767.3  643.08  4766.9  633.38  4947.4  604.09
  4948.9  603.09  5026.7  604.09  5029.6  611.81  5037.1  613.45  5185.7  627.89
  5334.3  638.99  5446.2  640.32    5899   642.3    6503  639.99  6743.7  641.24
  7003.2  644.29  7352.1     653  8078.4  668.99  8235.4  673.82  8268.6  674.63
#Mann= 20 ,-1 , 0
     873     .12       0  1088.7    .035       0  1321.7    .063       0
  1793.6    .035       0  2016.3    .063       0  2544.2    .063       0
  2858.4      .1       0  3505.1    .035       0  3767.3    .063       0
  4766.9    .063       0  4947.4     .05       0  5026.7    .063       0
  5446.2    .094       0    5899    .063       0    6503    .063       0
  6743.7    .035       0  7003.2    .094       0  7352.1    .063       0
  8078.4    .063       0  8235.4    .035       0
Bank Sta=4947.4,5026.7
XS Rating Curve= 0 ,0
Exp/Cntr=0.3,0.1

Type RM Length L Ch R = 1 ,7246    ,793,793,793
BEGIN DESCRIPTION:
X18906
END DESCRIPTION:
XS GIS Cut Line= 3
      2239884.08     13805591.82      2243339.54     13801992.38
      2244841.17     13800697.56
#Sta/Elev= 30
   786.1  690.22   902.7  683.45  1105.5  674.48  1314.9  667.09  1956.8  643.65
  2679.9  639.07  2985.1  642.31  3237.8  644.46  3579.4  645.43  3946.1  642.92
  4166.6  641.96    4607  635.71  4837.1   630.2  4950.3  610.23    4960  601.87
  4961.5  600.87  5039.3  601.87  5049.3  611.52    5178  629.46  5275.5  640.71
  5593.7   645.4  6244.9  638.17  6581.9  639.24  6834.3  641.37  6840.9  630.51
  6862.8  643.55  6970.8  642.61  7299.6  646.36  7737.7  656.15  7758.5  657.15
#Mann= 20 ,-1 , 0
   786.1     .07       0   902.7     .07       0  1105.5     .07       0
  1314.9     .07       0  1956.8      .1       0  2679.9      .1       0
  2985.1      .1       0  3237.8     .07       0  3579.4      .1       0
  3946.1      .1       0  4166.6     .07       0    4607     .12       0
    4960     .05       0  5039.3      .1       0    5178     .07       0
  6244.9     .07       0  6581.9      .1       0  6970.8     .07       0
  7299.6     .07       0  7737.7     .07       0
Bank Sta=4960,5039.3
XS Rating Curve= 0 ,0
Exp/Cntr=0.3,0.1

Type RM Length L Ch R = 1 ,6453    ,915,915,915
BEGIN DESCRIPTION:
X18905
END DESCRIPTION:
XS GIS Cut Line= 3
        2240496.     13805762.76      2243150.57     13803252.17
      2245480.61     13801147.05
#Sta/Elev= 30
  1098.1  671.25  1150.7  669.46  1526.9   654.7  1844.9  650.03  2022.1     645
  2263.9  640.56  2581.5  633.86  2791.9  637.74    3174   639.5  3663.6  643.65
  3715.9  640.37  4506.4   639.8  4784.5  635.37  4859.2  634.75  4894.3  622.15
  4965.3  607.01  4968.2  601.76  4969.7  600.76  5047.5  601.76  5050.5  609.99
  5057.2  611.99  5305.3  637.52  5376.1  638.15  5864.5  643.29  6740.4  637.46
  7013.8  639.53  7235.9   640.6  7558.9  647.11  7887.1  660.82    7892  661.23
#Mann= 20 ,-1 , 0
  1098.1     .07       0  1150.7      .1       0  1526.9      .1       0
  1844.9     .07       0  2022.1      .1       0  2263.9     .07       0
  2791.9      .1       0    3174      .1       0  3715.9     .07       0
  4506.4      .1       0  4784.5      .1       0  4968.2     .05       0
  5047.5      .1       0  5376.1      .1       0  5864.5     .07       0
  6740.4      .1       0  7013.8      .1       0  7235.9     .07       0
  7558.9     .07       0  7887.1     .07       0
Bank Sta=4968.2,5047.5
XS Rating Curve= 0 ,0
Exp/Cntr=0.3,0.1

Type RM Length L Ch R = 1 ,5538    ,807,807,807
BEGIN DESCRIPTION:
X18904
END DESCRIPTION:
XS GIS Cut Line= 3
      2240558.99     13805798.76      2243861.46      13803657.1
      2245930.58     13801704.93
#Sta/Elev= 30
   678.3  669.44   803.7  665.28   996.3  655.14  1257.1  649.45    1521  645.04
  1721.2  640.98    2460  636.17  2705.7  636.88  3312.7  636.34  3547.2  636.94
  4682.1  636.54  4837.9  629.16  4960.8  601.74  4962.3  600.74  5040.2  601.74
    5064  611.06    5132  610.05    5149  604.47  5205.6  619.48  5310.8  628.78
  5354.1  639.01  5396.6  624.73  5424.9  635.42  5483.3  636.36    5762  641.56
  6040.7     641  6555.2  635.59  6964.4  639.55  7203.5  654.08  7459.1  671.08
#Mann= 20 ,-1 , 0
   678.3     .07       0   803.7      .1       0   996.3      .1       0
  1257.1      .1       0    1521     .07       0  1721.2     .07       0
    2460     .07       0  2705.7      .1       0  3312.7      .1       0
  3547.2     .07       0  4960.8     .05       0  5040.2     .07       0
    5132     .07       0  5310.8      .1       0  5483.3      .1       0
    5762      .1       0  6040.7     .07       0  6555.2     .07       0
  6964.4     .07       0  7203.5     .07       0
Bank Sta=4960.8,5040.2
XS Rating Curve= 0 ,0
Exp/Cntr=0.3,0.1

Type RM Length L Ch R = 1 ,4731    ,636,636,636
BEGIN DESCRIPTION:
X18903
END DESCRIPTION:
XS GIS Cut Line= 3
      2240658.01     13805816.74      2245031.26      13803684.1
      2246488.24      13802119.2
#Sta/Elev= 30
   506.5  667.58   851.5  649.08  1059.5  645.02  1286.4  641.82  1662.9  636.88
  2408.4  634.13  2649.2  634.91  3119.5  635.09  3368.4  635.76  4790.2  634.44
  4925.4  622.81  4970.4  613.05  4975.8  599.62  4977.3  598.62  5055.2  599.62
  5178.8  619.58  5231.6   635.6  5352.5  644.47  5652.1  645.87  5986.7  641.11
  6171.2  638.56  6314.9  638.96  6605.1   630.8  6796.2     633  6944.7  638.49
  7008.7  643.28  7029.7  649.32  7151.5  655.31  7249.1   662.6  7510.2  669.66
#Mann= 15 ,-1 , 0
   506.5     .07       0   851.5      .1       0  1059.5     .07       0
  1286.4      .1       0  1662.9     .07       0  2408.4      .1       0
  2649.2      .1       0  3119.5      .1       0  3368.4      .1       0
  4975.8     .05       0  5352.5      .1       0  5652.1      .1       0
  5986.7      .1       0  6171.2      .1       0  7151.5      .1       0
Bank Sta=4975.8,5055.2
XS Rating Curve= 0 ,0
Exp/Cntr=0.3,0.1

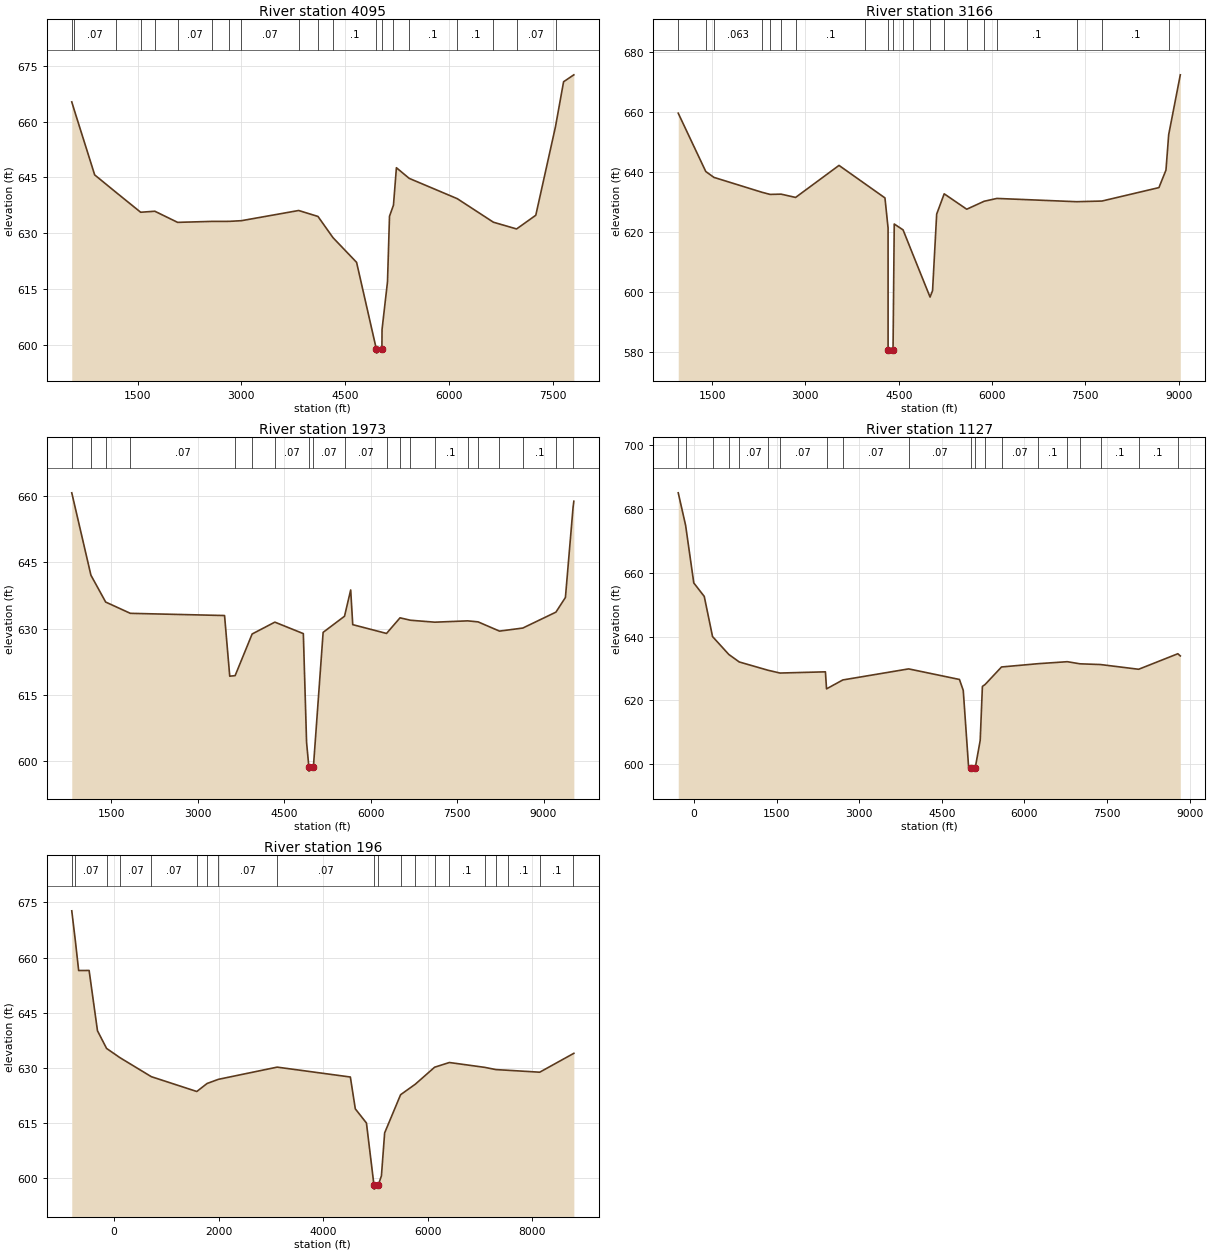
Type RM Length L Ch R = 1 ,4095    ,929,929,929
BEGIN DESCRIPTION:
X18902
END DESCRIPTION:
XS GIS Cut Line= 4
      2240729.94     13805888.75      2244644.33     13804610.95
      2245670.16     13803828.08      2246597.02     13802226.31
#Sta/Elev= 30
   549.7  665.29   586.3  663.07   881.1  645.66  1183.7  641.06  1545.7  635.62
  1750.7  635.89  2080.1   632.9  2574.4  633.16  2828.5  633.17  3002.7  633.35
  3830.1  636.09  4109.2  634.49  4326.2  628.79  4667.4  622.15  4954.1  598.74
  4955.6  597.74  5033.5  598.74  5035.4  604.09  5114.4  616.95  5143.4  634.56
  5200.7  637.52  5243.2  647.59  5427.9  644.73  6122.9  639.27  6645.3  632.94
  6980.6  631.13  7258.2  634.81  7543.4  658.67  7660.1  670.71  7808.4  672.57
#Mann= 20 ,-1 , 0
   549.7    .094       0   586.3     .07       0  1183.7     .07       0
  1545.7     .07       0  1750.7     .07       0  2080.1     .07       0
  2574.4     .07       0  2828.5      .1       0  3002.7     .07       0
  3830.1     .07       0  4109.2     .07       0  4326.2      .1       0
  4954.1     .05       0  5033.5     .12       0  5200.7      .1       0
  5427.9      .1       0  6122.9      .1       0  6645.3      .1       0
  6980.6     .07       0  7543.4      .1       0
Bank Sta=4954.1,5033.5
XS Rating Curve= 0 ,0
Exp/Cntr=0.3,0.1

Type RM Length L Ch R = 1 ,3166    ,1193,1193,1193
BEGIN DESCRIPTION:
X18901
END DESCRIPTION:
XS GIS Cut Line= 5
      2240822.44     13806005.93      2243447.39     13805317.41
      2245004.27     13805240.84      2245831.69     13804707.79
      2247050.82     13802174.22
#Sta/Elev= 30
     957  659.55  1399.5  640.16  1530.2  638.21  2303.9  633.25  2432.4  632.55
  2611.3  632.63    2843  631.54  3540.7  642.19  3960.7  636.04  4279.1  631.38
  4329.2  621.35  4329.5  580.77    4331  579.77  4408.9  580.77  4428.3   622.7
  4570.2  620.75  4723.3  612.82  5003.8  598.41  5044.1  600.56  5110.1  625.99
    5231  632.74  5593.2  627.62  5873.5  630.27  6078.1  631.21  7358.7  630.12
  7766.5  630.34  8681.8  634.81    8795  640.63  8838.6  652.41  9025.4  672.31
#Mann= 20 ,-1 , 0
     957    .063       0  1399.5    .063       0  1530.2    .063       0
  2303.9     .07       0  2432.4    .063       0  2611.3     .07       0
    2843      .1       0  3960.7      .1       0  4329.5     .05       0
  4408.9     .07       0  4570.2      .1       0  4723.3     .07       0
  5003.8     .07       0    5231      .1       0  5593.2      .1       0
  5873.5      .1       0  6078.1      .1       0  7358.7      .1       0
  7766.5      .1       0  8838.6     .07       0
Bank Sta=4329.5,4408.9
XS Rating Curve= 0 ,0
Exp/Cntr=0.3,0.1

Type RM Length L Ch R = 1 ,1973    ,846,846,846
BEGIN DESCRIPTION:
Dry Comal Creek 1.0
END DESCRIPTION:
XS GIS Cut Line= 6
      2240877.01     13806129.06      2244658.19     13806312.61
        2244975.       13806075.        2244975.     13805638.53
      2245859.07     13804803.66       2247124.3      13802218.9
#Sta/Elev= 30
   814.1  660.82  1146.5  642.11  1402.5  636.01  1830.2  633.45  3465.2  632.95
  3555.3  619.17  3648.6   619.3    3944  628.76  4337.9  631.45  4832.2  628.84
  4888.5  604.11  4927.9  598.61  4929.4  597.61  5007.3  598.61  5175.7  629.13
  5546.8  632.79  5653.9  638.76  5689.5  630.88  6275.8  628.88  6510.1  632.43
  6690.5  631.88  7114.1  631.44  7683.1  631.74  7864.4  631.51  8235.7  629.41
  8641.1  630.11    9215  633.72  9379.9  637.05  9512.6  657.52    9526  658.91
#Mann= 20 ,-1 , 0
   814.1    .063       0  1146.5    .063       0  1402.5    .094       0
  1830.2     .07       0  3648.6    .094       0    3944      .1       0
  4337.9     .07       0  4927.9     .05       0  5007.3     .07       0
  5546.8     .07       0  6275.8      .1       0  6510.1      .1       0
  6690.5      .1       0  7114.1      .1       0  7683.1      .1       0
  7864.4      .1       0  8235.7      .1       0  8641.1      .1       0
    9215      .1       0  9512.6     .07       0
Bank Sta=4927.9,5007.3
XS Rating Curve= 0 ,0
Exp/Cntr=0.3,0.1

Type RM Length L Ch R = 1 ,1127    ,931,931,931
BEGIN DESCRIPTION:
X18900
END DESCRIPTION:
XS GIS Cut Line= 5
      2240812.51     13806516.33      2245599.63     13806422.31
      2245751.15     13806032.71      2245726.98     13805186.83
      2247085.46     13802438.55
#Sta/Elev= 30
  -287.9  684.98  -154.2  674.83    -5.4  656.78   184.7  652.56   335.2     640
   630.9   634.4   821.2  632.05  1343.3  629.46  1560.9  628.59  2385.1  628.97
  2405.4  623.64  2701.1  626.43  3896.5  629.89  4819.1  626.58  4888.2  623.16
  4985.9  599.02  5026.2   598.9  5027.7   597.9  5105.6   598.9    5196  607.51
    5236  624.41    5285  625.01  5583.3  630.49  6249.6  631.52  6777.5  632.14
  7006.5  631.48  7380.7  631.25  8073.7  629.77  8785.1  634.63  8830.1  633.94
#Mann= 20 ,-1 , 0
  -287.9    .063       0  -154.2     .07       0   335.2    .063       0
   630.9    .094       0   821.2     .07       0  1343.3      .1       0
  1560.9     .07       0  2405.4      .1       0  2701.1     .07       0
  3896.5     .07       0  5026.2     .05       0  5105.6     .07       0
    5285     .07       0  5583.3     .07       0  6249.6      .1       0
  6777.5      .1       0  7006.5      .1       0  7380.7      .1       0
  8073.7      .1       0  8785.1      .1       0
Bank Sta=5026.2,5105.6
XS Rating Curve= 0 ,0
Exp/Cntr=0.3,0.1

Type RM Length L Ch R = 1 ,196     ,0,0,0
BEGIN DESCRIPTION:
X18899
END DESCRIPTION:
XS GIS Cut Line= 6
      2240993.21     13806580.87      2246038.26     13806569.04
      2246516.02     13806275.67        2246615.     13805825.75
      2246346.22     13804929.79      2247176.51     13802462.97
#Sta/Elev= 30
  -811.3  672.73  -742.2  664.51  -679.5  656.48  -479.5   656.5  -319.5  640.09
  -145.4  635.28     110  632.77   711.2  627.59  1580.6  623.56  1777.1  625.74
    1993  626.87  3118.7  630.19    4518   627.5  4612.7  618.84  4825.8  614.98
  4970.4  597.99  4971.9  596.99  5049.9  597.99  5112.5  600.62  5173.9  612.29
  5479.3  622.69  5759.8  625.54    6130  630.17  6412.1  631.45  7087.5  630.13
  7302.7  629.52  7526.6  629.34  8140.2  628.81  8775.3  633.81  8793.3  633.95
#Mann= 20 ,-1 , 0
  -811.3    .063       0  -742.2     .07       0  -145.4    .063       0
     110     .07       0   711.2     .07       0  1580.6      .1       0
  1777.1      .1       0    1993     .07       0  3118.7     .07       0
  4970.4     .05       0  5049.9     .07       0  5479.3     .07       0
  5759.8     .07       0    6130     .07       0  6412.1      .1       0
  7087.5      .1       0  7302.7      .1       0  7526.6      .1       0
  8140.2      .1       0  8775.3      .1       0
Bank Sta=4970.4,5049.9
XS Rating Curve= 0 ,0
Exp/Cntr=0.3,0.1

Chan Stop Cuts=-1
Use User Specified Reach Order=0
Composite Channel Slope=5