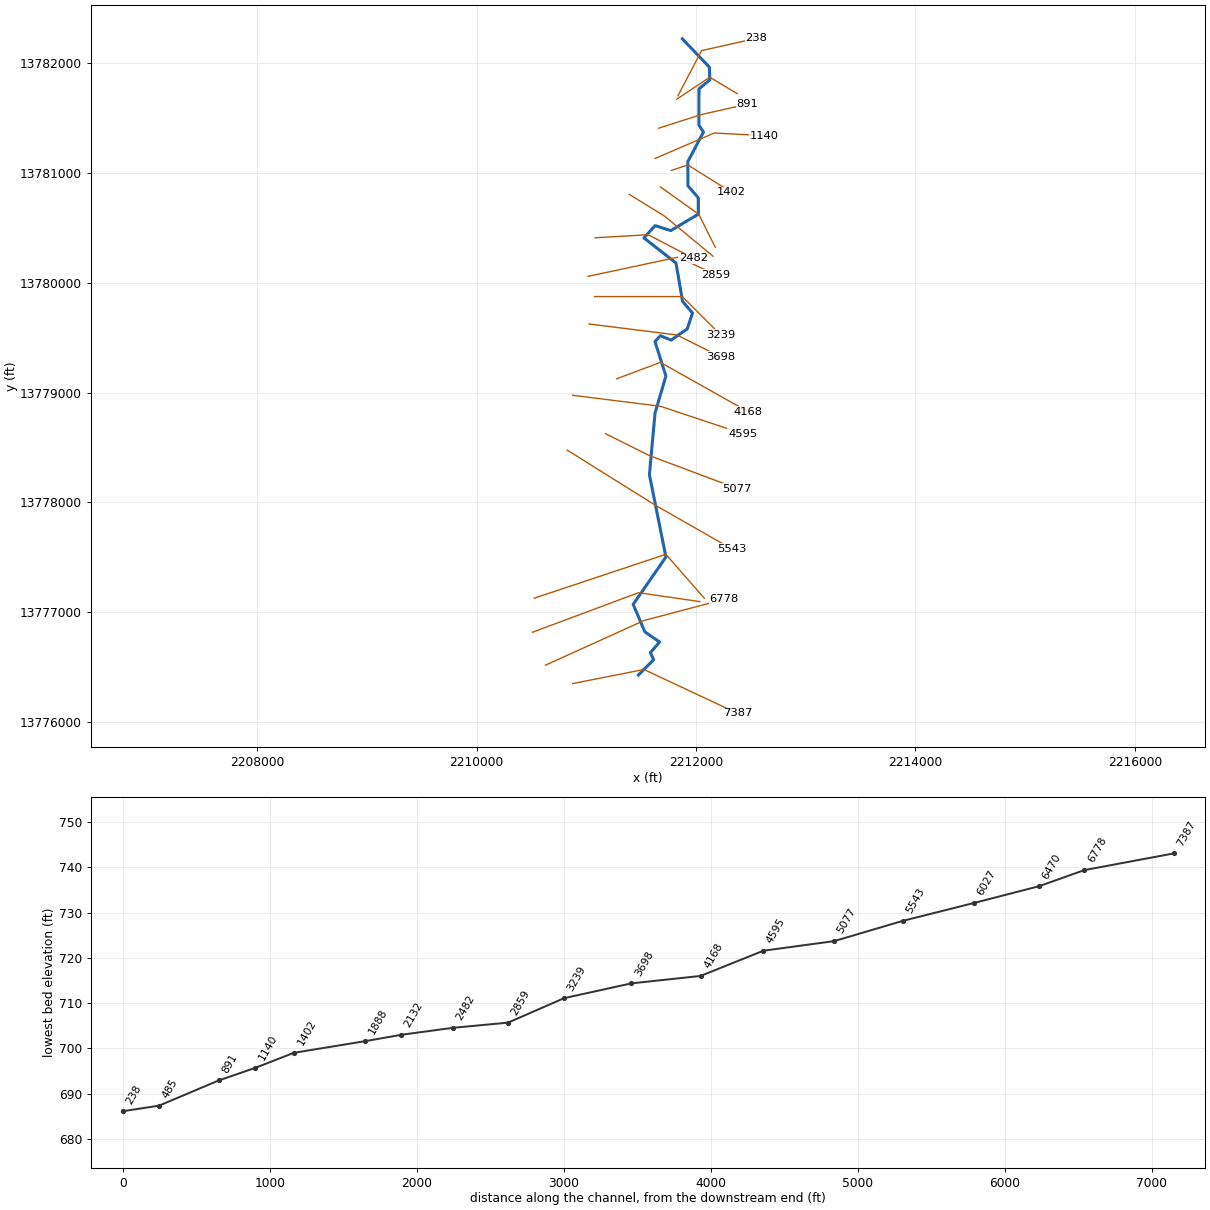
--- Dry Comal Tributary 11.prj (project) ---

Proj Title=Dry Comal Tributary 11 Base Level Engineering
Current Plan=p01
Default Exp/Contr=0.3,0.1
English Units
Geom File=g01
Flow File=f01
Plan File=p01
BEGIN DESCRIPTION:
Dry Comal Tributary 11
END DESCRIPTION:

--- Dry Comal Tributary 11.p01 (plan) ---

Plan Title=Multiple Run
Short Identifier=Multiple
Geom File=g01
Flow File=f01
Subcritical Flow
K Sum by GR= 0
Std Step Tol= 0.01
Critical Tol= 0.01
Num of Std Step Trials= 20
Max Error Tol= 0.3
Flow Tol Ratio= 0.001
Split Flow NTrial= 30
Split Flow Tol= 0.02
Split Flow Ratio= 0.02
Log Output Level= 0
Friction Slope Method= 1
Unsteady Friction Slope Method= 2
Unsteady Bridges Friction Slope Method= 1
Parabolic Critical Depth
Global Vel Dist=  1 , 1 , 1
Global Log Level= 0
CheckData=True
Encroach Param= -1, 0, 0, 0
BEGIN DESCRIPTION:
Multiple Run
END DESCRIPTION:

--- Dry Comal Tributary 11.f01 (steady flow) ---

Flow Title=Multiple
Number of Profiles=7
Profile Names=10-year,25-year,50-year,1pct_min,100-year,1pct_plu,500-year
River Rch & RM= Dry Comal Tribut,Reach-1,7387
    1142    1921    2656    1775    3542    7067    6240
River Rch & RM= Dry Comal Tribut,Reach-1,5077
    1264    2134    2955    1978    3947    7875    6973
Boundary for River Rch & Prof#=Dry Comal Tribut,Reach-1,1
Up Type=0
Dn Type=3
Dn Slope=0.005
Boundary for River Rch & Prof#=Dry Comal Tribut,Reach-1,2
Up Type=0
Dn Type=3
Dn Slope=0.005
Boundary for River Rch & Prof#=Dry Comal Tribut,Reach-1,3
Up Type=0
Dn Type=3
Dn Slope=0.005
Boundary for River Rch & Prof#=Dry Comal Tribut,Reach-1,4
Up Type=0
Dn Type=3
Dn Slope=0.005
Boundary for River Rch & Prof#=Dry Comal Tribut,Reach-1,5
Up Type=0
Dn Type=3
Dn Slope=0.005
Boundary for River Rch & Prof#=Dry Comal Tribut,Reach-1,6
Up Type=0
Dn Type=3
Dn Slope=0.005
Boundary for River Rch & Prof#=Dry Comal Tribut,Reach-1,7
Up Type=0
Dn Type=3
Dn Slope=0.005

--- Dry Comal Tributary 11.g01 (geometry) ---

Geom Title=Existing Conditions

River Reach=Dry Comal Tribut,Reach-1
Reach XY= 30
      2211475.00     13776425.00      2211613.77     13776565.00
      2211583.03     13776628.33      2211667.99     13776725.21
      2211532.75     13776818.55      2211426.76     13777068.88
      2211725.50     13777499.96      2211574.80     13778249.92
      2211626.22     13778814.50      2211725.40     13779150.00
      2211625.59     13779464.71      2211674.64     13779517.74
      2211773.35     13779478.17      2211919.75     13779580.47
      2211967.68     13779725.09      2211877.08     13779830.86
      2211817.18     13780181.19      2211524.86     13780409.58
      2211626.62     13780521.87      2211768.96     13780476.63
      2212021.57     13780626.23      2212021.46     13780773.53
      2211926.06     13780885.44      2211925.06     13781104.97
      2212067.47     13781374.99      2212025.66     13781440.16
      2212027.01     13781769.32      2212125.35     13781849.83
      2212121.61     13781966.55      2211875.00     13782225.00

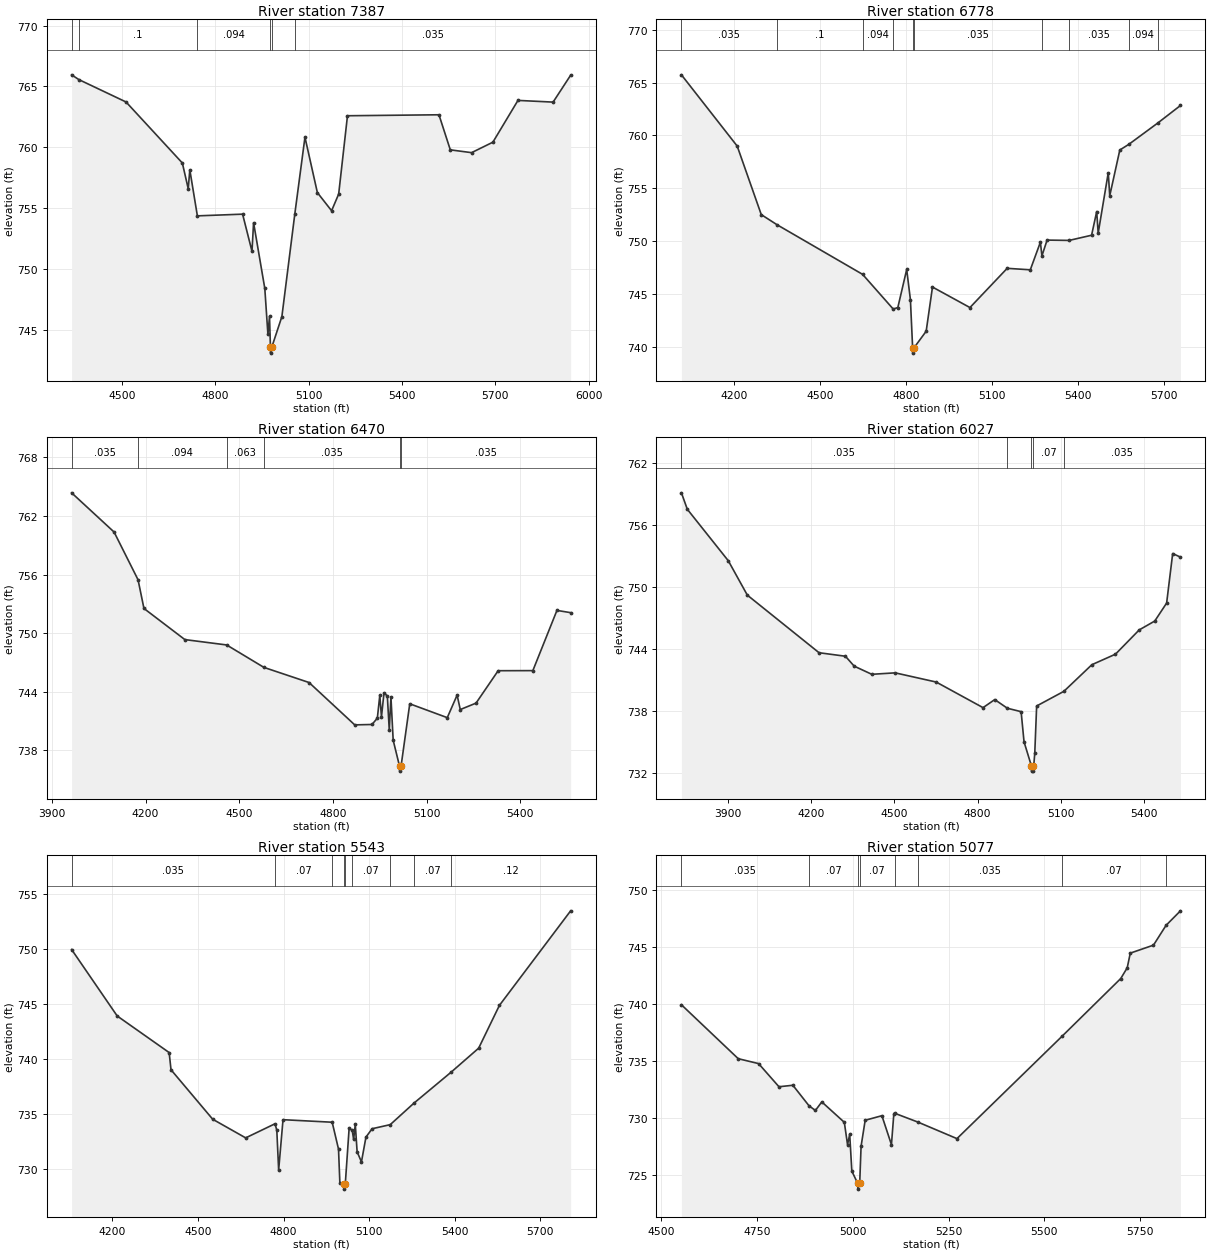
Type RM Length L Ch R = 1,7387,609,609,609
BEGIN DESCRIPTION:
Dry Comal Tributary 11 16.0
END DESCRIPTION:
XS GIS Cut Line= 3
      2210875.75     13776346.55      2211525.00     13776475.00
      2212378.38     13776074.80
#Sta/Elev= 30
  4338.1  765.95  4361.3  765.56  4513.1  763.72  4694.1  758.71  4713.0  756.60
  4718.1  758.15  4742.4  754.37  4887.8  754.51  4918.0  751.46  4923.1  753.81
  4959.2  748.41  4969.2  744.64  4974.3  746.11  4977.3  743.60  4977.6  743.10
  4981.8  743.60  5014.1  746.10  5055.7  754.53  5088.3  760.83  5128.2  756.28
  5173.9  754.79  5196.7  756.16  5225.0  762.59  5519.1  762.67  5555.6  759.79
  5624.0  759.56  5692.5  760.42  5773.1  763.85  5886.1  763.71  5942.5  765.92
#Mann=6,-1,0
  4338.1   0.094       0  4361.3     0.1       0  4742.4   0.094       0
  4977.3    0.05       0  4981.8   0.094       0  5055.7   0.035       0
Bank Sta=4977.3,4981.8
Exp/Cntr=0.3,0.1

Type RM Length L Ch R = 1,6778,308,308,308
BEGIN DESCRIPTION:
Dry Comal Tributary 11 15.0
END DESCRIPTION:
XS GIS Cut Line= 3
      2210627.98     13776514.42      2211527.16     13776922.05
      2212254.53     13777113.88
#Sta/Elev= 30
  4017.8  765.73  4212.2  758.99  4296.1  752.51  4350.6  751.56  4649.3  746.86
  4756.0  743.58  4772.1  743.72  4803.0  747.32  4816.0  744.46  4823.7  739.91
  4824.0  739.41  4828.4  739.91  4870.9  741.48  4892.9  745.66  5023.5  743.72
  5153.3  747.43  5233.9  747.29  5269.0  749.90  5274.4  748.61  5292.4  750.10
  5369.3  750.07  5447.5  750.56  5465.3  752.80  5470.5  750.76  5505.6  756.47
  5510.8  754.30  5545.9  758.62  5577.5  759.16  5678.6  761.18  5757.3  762.83
#Mann=10,-1,0
  4017.8   0.035       0  4350.6     0.1       0  4649.3   0.094       0
  4756.0   0.035       0  4823.7   0.035       0  4828.4   0.035       0
  5274.4     0.1       0  5369.3   0.035       0  5577.5   0.094       0
  5678.6     0.1       0
Bank Sta=4823.7,4828.4
Exp/Cntr=0.3,0.1

Type RM Length L Ch R = 1,6470,443,443,443
BEGIN DESCRIPTION:
Dry Comal Tributary 11 14.0
END DESCRIPTION:
XS GIS Cut Line= 3
      2210508.02     13776814.13      2211475.00     13777175.00
      2212034.73     13777093.90
#Sta/Elev= 30
  3963.4  764.37  4099.4  760.35  4176.1  755.46  4195.0  752.52  4325.9  749.33
  4459.8  748.78  4579.1  746.48  4723.6  744.93  4869.8  740.59  4925.1  740.63
  4942.2  741.28  4950.1  743.62  4955.4  741.41  4963.5  743.87  4974.2  743.55
  4980.4  740.07  4985.7  743.46  4992.9  739.02  5013.3  736.35  5013.7  735.85
  5018.1  736.35  5046.0  742.75  5166.1  741.33  5197.6  743.64  5207.7  742.16
  5258.2  742.82  5329.0  746.14  5440.1  746.15  5517.2  752.32  5561.1  752.09
#Mann=6,-1,0
  3963.4   0.035       0  4176.1   0.094       0  4459.8   0.063       0
  4579.1   0.035       0  5013.3   0.035       0  5018.1   0.035       0
Bank Sta=5013.3,5018.1
Exp/Cntr=0.3,0.1

Type RM Length L Ch R = 1,6027,484,484,484
BEGIN DESCRIPTION:
Dry Comal Tributary 11 13.0
END DESCRIPTION:
XS GIS Cut Line= 3
      2210524.99     13777125.00      2211725.00     13777525.00
      2212074.98     13777125.02
#Sta/Elev= 30
  3733.8  759.10  3754.9  757.51  3902.5  752.52  3971.0  749.19  4229.2  743.61
  4324.1  743.27  4355.7  742.31  4419.0  741.52  4503.3  741.66  4650.9  740.77
  4819.5  738.29  4861.7  739.07  4907.2  738.23  4956.6  737.90  4967.1  734.98
  4993.7  732.64  4994.0  732.14  4998.1  732.14  4998.5  732.64  5002.0  732.64
  5005.8  733.91  5012.5  738.45  5110.5  739.87  5211.3  742.45  5296.3  743.47
  5381.7  745.82  5437.7  746.68  5480.4  748.42  5502.2  753.22  5530.2  752.87
#Mann=5,-1,0
  3733.8   0.035       0  4907.2    0.07       0  4993.7    0.05       0
  4998.5    0.07       0  5110.5   0.035       0
Bank Sta=4993.7,4998.5
Exp/Cntr=0.3,0.1

Type RM Length L Ch R = 1,5543,466,466,466
BEGIN DESCRIPTION:
Dry Comal Tributary 11 12.0
END DESCRIPTION:
XS GIS Cut Line= 3
      2210824.96     13778475.03      2211625.00     13777975.00
      2212325.02     13777574.99
#Sta/Elev= 30
  4057.0  749.93  4216.8  743.90  4399.0  740.58  4405.5  739.02  4551.7  734.53
  4667.3  732.84  4770.1  734.12  4776.4  733.54  4782.9  729.92  4798.2  734.49
  4970.6  734.26  4992.8  731.82  4997.5  728.77  5011.7  728.69  5012.0  728.19
  5016.6  728.69  5030.0  733.70  5040.8  733.54  5045.8  732.70  5051.6  734.07
  5058.0  731.58  5073.2  730.66  5089.0  732.91  5110.6  733.67  5174.1  734.04
  5257.6  736.00  5387.1  738.79  5484.2  740.98  5556.9  744.86  5806.7  753.44
#Mann=9,-1,0
  4057.0   0.035       0  4770.1    0.07       0  4970.6    0.12       0
  5011.7    0.05       0  5016.6    0.12       0  5040.8    0.07       0
  5174.1    0.12       0  5257.6    0.07       0  5387.1    0.12       0
Bank Sta=5011.7,5016.6
Exp/Cntr=0.3,0.1

Type RM Length L Ch R = 1,5077,482,482,482
BEGIN DESCRIPTION:
Dry Comal Tributary 11 11.0
END DESCRIPTION:
XS GIS Cut Line= 3
      2211174.97     13778625.02      2211575.00     13778425.00
      2212375.05     13778124.98
#Sta/Elev= 30
  4553.2  739.89  4701.4  735.16  4754.5  734.73  4807.6  732.70  4843.9  732.83
  4886.0  731.03  4902.6  730.62  4919.4  731.37  4978.1  729.58  4986.5  727.62
  4992.1  728.53  4997.7  725.30  5013.0  724.22  5013.4  723.72  5018.2  724.22
  5021.8  727.48  5032.5  729.76  5076.1  730.16  5101.0  727.62  5107.3  730.35
  5109.1  730.38  5170.8  729.59  5271.9  728.15  5546.4  737.14  5699.1  742.19
  5716.0  743.13  5724.0  744.42  5784.5  745.12  5817.4  746.86  5854.9  748.13
#Mann=8,-1,0
  4553.2   0.035       0  4886.0    0.07       0  5013.0    0.05       0
  5018.2    0.07       0  5109.1    0.12       0  5170.8   0.035       0
  5546.4    0.07       0  5817.4   0.035       0
Bank Sta=5013,5018.2
Exp/Cntr=0.3,0.1

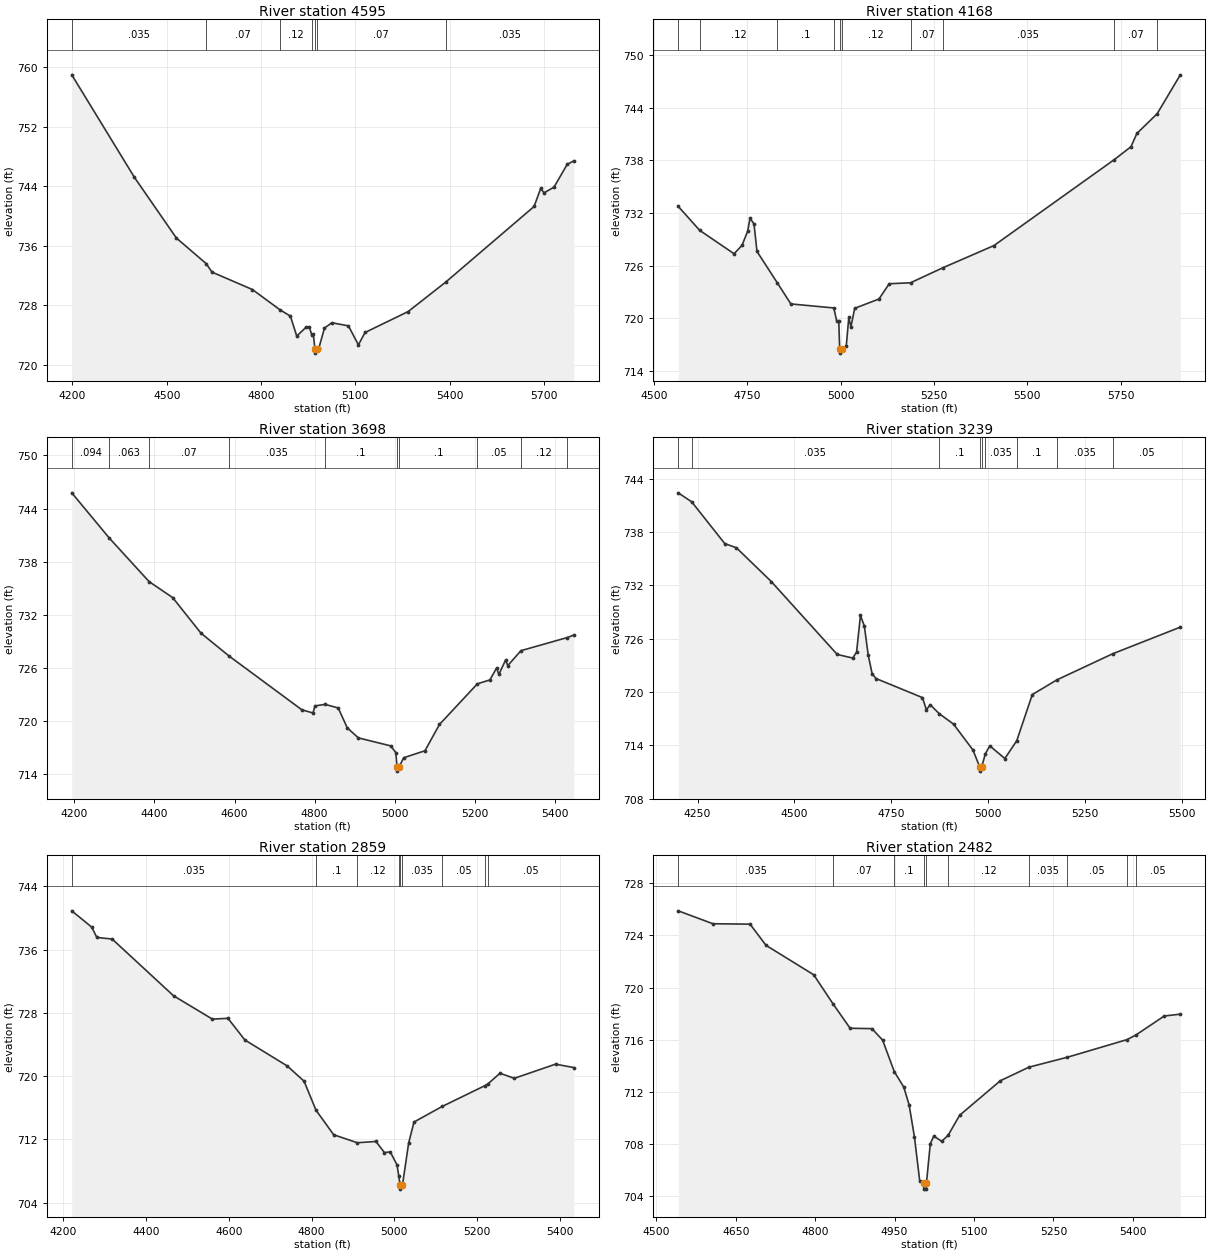
Type RM Length L Ch R = 1,4595,427,427,427
BEGIN DESCRIPTION:
Dry Comal Tributary 11 10.0
END DESCRIPTION:
XS GIS Cut Line= 3
      2210874.99     13778975.00      2211675.00     13778875.00
      2212425.00     13778625.00
#Sta/Elev= 30
  4198.1  758.96  4397.1  745.21  4530.7  737.05  4625.3  733.62  4644.1  732.47
  4772.5  730.13  4861.6  727.37  4893.5  726.56  4913.6  723.88  4943.9  725.09
  4953.9  725.07  4961.2  724.05  4966.5  724.12  4971.5  722.09  4971.9  721.59
  4976.7  722.09  4984.2  722.30  5001.8  724.96  5025.4  725.67  5078.1  725.25
  5109.7  722.70  5130.8  724.36  5267.9  727.17  5387.5  731.13  5668.4  741.28
  5689.5  743.70  5700.0  743.11  5731.7  743.87  5773.8  746.94  5794.9  747.41
#Mann=7,-1,0
  4198.1   0.035       0  4625.3    0.07       0  4861.6    0.12       0
  4961.2    0.07       0  4971.5    0.05       0  4976.7    0.07       0
  5387.5   0.035       0
Bank Sta=4971.5,4976.7
Exp/Cntr=0.3,0.1

Type RM Length L Ch R = 1,4168,470,470,470
BEGIN DESCRIPTION:
Dry Comal Tributary 11 9.0
END DESCRIPTION:
XS GIS Cut Line= 3
      2211274.97     13779124.99      2211675.00     13779275.00
      2212474.99     13778825.00
#Sta/Elev= 30
  4565.0  732.75  4622.5  730.02  4714.6  727.35  4735.9  728.31  4751.0  729.92
  4757.3  731.40  4768.0  730.75  4776.0  727.61  4830.5  724.03  4866.7  721.63
  4981.8  721.17  4989.6  719.67  4995.1  719.67  4997.5  716.52  4997.9  716.02
  5002.8  716.52  5015.2  716.84  5021.9  720.09  5027.6  719.02  5037.8  721.13
  5102.8  722.19  5130.2  723.93  5187.3  724.04  5273.3  725.74  5410.7  728.28
  5733.1  738.08  5777.8  739.55  5793.8  741.07  5848.0  743.31  5910.1  747.75
#Mann=10,-1,0
  4565.0   0.035       0  4622.5    0.12       0  4830.5     0.1       0
  4981.8    0.12       0  4997.5    0.05       0  5002.8    0.12       0
  5187.3    0.07       0  5273.3   0.035       0  5733.1    0.07       0
  5848.0    0.12       0
Bank Sta=4997.5,5002.8
Exp/Cntr=0.3,0.1

Type RM Length L Ch R = 1,3698,459,459,459
BEGIN DESCRIPTION:
Dry Comal Tributary 11 8.0
END DESCRIPTION:
XS GIS Cut Line= 3
      2211025.01     13779625.00      2211825.00     13779525.00
      2212224.98     13779325.01
#Sta/Elev= 30
  4193.7  745.78  4287.1  740.69  4386.8  735.76  4445.6  733.96  4516.2  729.95
  4586.0  727.38  4768.1  721.30  4795.8  720.94  4800.9  721.74  4826.2  721.91
  4858.8  721.51  4881.5  719.26  4909.2  718.13  4989.8  717.23  5002.7  716.47
  5005.6  714.88  5006.0  714.38  5011.0  714.88  5022.3  715.89  5075.4  716.68
  5111.7  719.65  5206.3  724.23  5237.5  724.67  5254.3  726.02  5259.9  725.29
  5276.6  726.91  5282.2  726.29  5315.0  727.97  5429.8  729.44  5447.1  729.73
#Mann=10,-1,0
  4193.7   0.094       0  4287.1   0.063       0  4386.8    0.07       0
  4586.0   0.035       0  4826.2     0.1       0  5005.6    0.05       0
  5011.0     0.1       0  5206.3    0.05       0  5315.0    0.12       0
  5429.8    0.07       0
Bank Sta=5005.6,5011
Exp/Cntr=0.3,0.1

Type RM Length L Ch R = 1,3239,380,380,380
BEGIN DESCRIPTION:
Dry Comal Tributary 11 7.0
END DESCRIPTION:
XS GIS Cut Line= 3
      2211074.95     13779875.00      2211875.00     13779875.00
      2212224.99     13779525.01
#Sta/Elev= 30
  4200.3  742.41  4235.2  741.39  4320.3  736.70  4350.3  736.23  4440.3  732.43
  4610.3  724.23  4650.3  723.82  4660.3  724.49  4670.3  728.61  4680.3  727.43
  4690.3  724.17  4700.3  722.08  4710.3  721.52  4830.3  719.37  4840.3  718.00
  4850.3  718.57  4873.1  717.58  4910.3  716.39  4960.3  713.49  4977.6  711.60
  4978.0  711.10  4983.1  711.60  4992.6  713.07  5003.9  713.94  5042.8  712.52
  5073.5  714.53  5113.5  719.71  5177.1  721.37  5320.7  724.30  5495.3  727.30
#Mann=9,-1,0
  4200.3    0.07       0  4235.2   0.035       0  4873.1     0.1       0
  4977.6   0.035       0  4983.1     0.1       0  4992.6   0.035       0
  5073.5     0.1       0  5177.1   0.035       0  5320.7    0.05       0
Bank Sta=4977.6,4983.1
Exp/Cntr=0.3,0.1

Type RM Length L Ch R = 1,2859,377,377,377
BEGIN DESCRIPTION:
Dry Comal Tributary 11 6.0
END DESCRIPTION:
XS GIS Cut Line= 3
      2211015.61     13780059.33      2211838.89     13780235.18
      2212175.02     13780074.99
#Sta/Elev= 30
  4220.2  740.91  4268.4  738.85  4280.9  737.54  4317.9  737.34  4466.4  730.16
  4560.3  727.21  4597.9  727.31  4638.8  724.57  4741.1  721.29  4782.0  719.36
  4810.7  715.70  4853.6  712.58  4910.7  711.57  4955.8  711.73  4976.3  710.33
  4990.5  710.41  5006.9  708.75  5010.8  707.42  5014.4  706.20  5014.9  705.70
  5019.9  706.20  5034.9  711.53  5047.8  714.19  5116.0  716.16  5218.9  718.78
  5226.7  719.02  5255.8  720.36  5290.4  719.72  5390.1  721.51  5434.4  721.08
#Mann=9,-1,0
  4220.2   0.035       0  4810.7     0.1       0  4910.7    0.12       0
  5010.8   0.035       0  5014.4    0.05       0  5019.9   0.035       0
  5116.0    0.05       0  5218.9   0.035       0  5226.7    0.05       0
Bank Sta=5014.4,5019.9
Exp/Cntr=0.3,0.1

Type RM Length L Ch R = 1,2482,350,350,350
BEGIN DESCRIPTION:
Dry Comal Tributary 11 5.0
END DESCRIPTION:
XS GIS Cut Line= 3
      2211079.57     13780411.03      2211563.13     13780439.00
      2211974.99     13780225.01
#Sta/Elev= 30
  4541.3  725.88  4606.8  724.89  4677.0  724.86  4707.0  723.24  4797.2  720.98
  4834.4  718.71  4866.0  716.88  4907.3  716.85  4927.4  715.97  4949.4  713.56
  4967.4  712.37  4977.5  711.00  4987.5  708.56  4997.5  705.18  5004.8  705.05
  5005.2  704.55  5009.8  704.55  5010.3  705.05  5017.5  708.03  5024.1  708.61
  5039.0  708.22  5051.1  708.67  5072.9  710.21  5149.9  712.86  5204.0  713.90
  5276.6  714.66  5389.3  716.01  5405.8  716.36  5459.5  717.82  5489.8  717.96
#Mann=10,-1,0
  4541.3   0.035       0  4834.4    0.07       0  4949.4     0.1       0
  5004.8    0.05       0  5010.3     0.1       0  5051.1    0.12       0
  5204.0   0.035       0  5276.6    0.05       0  5389.3   0.035       0
  5405.8    0.05       0
Bank Sta=5004.8,5010.3
Exp/Cntr=0.3,0.1

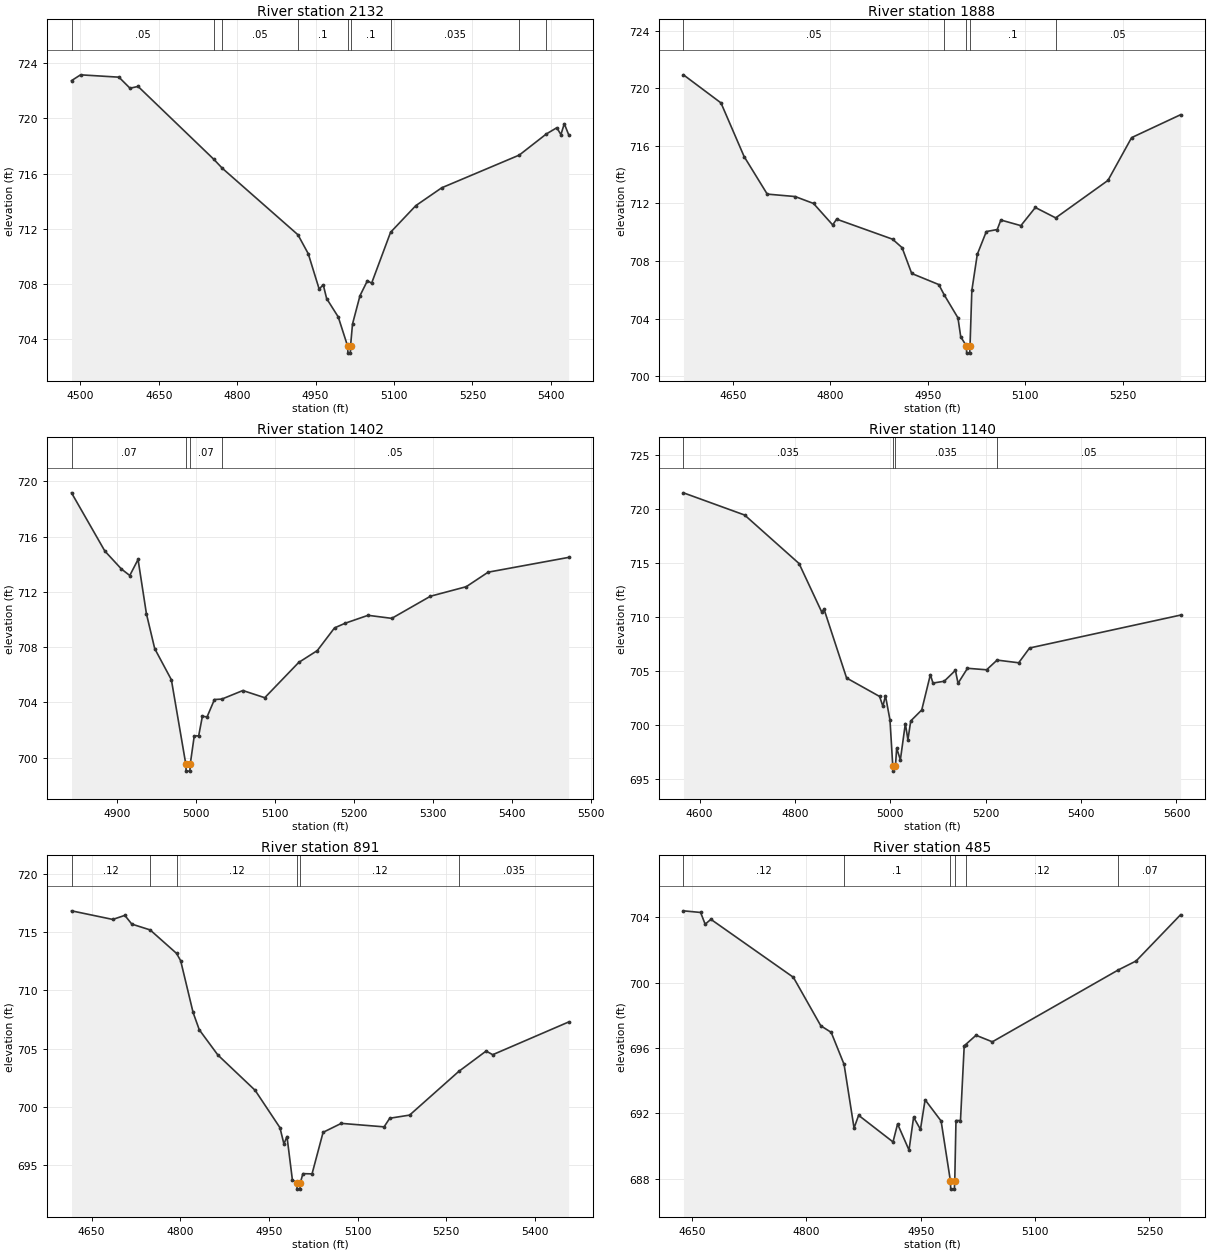
Type RM Length L Ch R = 1,2132,244,244,244
BEGIN DESCRIPTION:
X19053
END DESCRIPTION:
XS GIS Cut Line= 3
      2211391.31     13780806.66      2211715.00     13780606.86
      2212154.58     13780243.20
#Sta/Elev= 30
  4483.2  722.74  4500.5  723.16  4573.9  722.99  4595.1  722.19  4610.5  722.32
  4755.2  717.05  4771.5  716.40  4916.3  711.58  4936.0  710.21  4956.9  707.65
  4964.7  707.96  4971.2  706.96  4993.4  705.63  5011.4  703.51  5011.9  703.01
  5016.5  703.01  5016.9  703.51  5020.7  705.12  5035.0  707.17  5049.3  708.26
  5057.2  708.07  5093.5  711.76  5141.8  713.69  5191.3  714.98  5339.7  717.35
  5391.5  718.88  5411.5  719.33  5419.3  718.83  5425.8  719.62  5434.1  718.83
#Mann=9,-1,0
  4483.2    0.05       0  4755.2    0.07       0  4771.5    0.05       0
  4916.3     0.1       0  5011.4    0.05       0  5016.9     0.1       0
  5093.5   0.035       0  5339.7    0.05       0  5391.5   0.035       0
Bank Sta=5011.4,5016.9
Exp/Cntr=0.3,0.1

Type RM Length L Ch R = 1,1888,486,486,486
BEGIN DESCRIPTION:
Dry Comal Tributary 11 4.0
END DESCRIPTION:
XS GIS Cut Line= 3
      2211675.01     13780875.00      2212025.00     13780625.00
      2212174.99     13780325.02
#Sta/Elev= 30
  4573.7  720.93  4631.5  718.98  4667.1  715.26  4702.7  712.65  4745.7  712.48
  4774.0  712.00  4803.5  710.51  4809.6  710.91  4895.7  709.52  4910.4  708.93
  4925.2  707.14  4966.9  706.37  4975.3  705.65  4996.4  704.06  5000.7  702.74
  5009.4  702.11  5009.8  701.61  5014.5  701.61  5015.0  702.11  5017.8  705.96
  5026.2  708.47  5040.1  710.05  5056.9  710.19  5062.5  710.85  5093.3  710.46
  5115.6  711.72  5146.9  711.00  5227.4  713.60  5263.8  716.57  5339.2  718.16
#Mann=5,-1,0
  4573.7    0.05       0  4975.3     0.1       0  5009.4    0.05       0
  5015.0     0.1       0  5146.9    0.05       0
Bank Sta=5009.4,5015
Exp/Cntr=0.3,0.1

Type RM Length L Ch R = 1,1402,262,262,262
BEGIN DESCRIPTION:
Dry Comal Tributary 11 3.0
END DESCRIPTION:
XS GIS Cut Line= 3
      2211775.01     13781025.00      2211925.00     13781075.00
      2212325.00     13780825.00
#Sta/Elev= 30
  4842.3  719.16  4884.5  714.95  4905.5  713.65  4916.1  713.18  4926.6  714.34
  4937.2  710.41  4947.7  707.89  4968.8  705.64  4987.1  699.53  4987.5  699.03
  4992.2  699.03  4992.7  699.53  4997.8  701.58  5003.4  701.58  5008.1  703.00
  5014.0  702.95  5023.4  704.21  5032.7  704.24  5059.4  704.86  5087.1  704.34
  5130.1  706.89  5153.7  707.75  5175.5  709.39  5189.1  709.73  5218.0  710.30
  5248.0  710.08  5297.0  711.68  5342.4  712.37  5370.1  713.42  5472.1  714.49
#Mann=4,-1,0
  4842.3    0.07       0  4987.1    0.05       0  4992.7    0.07       0
  5032.7    0.05       0
Bank Sta=4987.1,4992.7
Exp/Cntr=0.3,0.1

Type RM Length L Ch R = 1,1140,249,249,249
BEGIN DESCRIPTION:
X19052
END DESCRIPTION:
XS GIS Cut Line= 3
      2211627.06     13781134.40      2212166.61     13781366.20
      2212621.15     13781342.28
#Sta/Elev= 30
  4566.2  721.50  4694.6  719.44  4808.6  714.95  4855.7  710.50  4861.2  710.69
  4908.3  704.34  4977.5  702.63  4984.4  701.72  4989.8  702.70  4999.3  700.44
  5005.1  696.21  5005.6  695.71  5010.8  696.21  5013.3  697.83  5021.1  696.76
  5031.5  700.12  5036.9  698.62  5042.8  700.36  5065.9  701.38  5084.0  704.65
  5089.4  703.87  5113.0  704.04  5136.5  705.05  5142.0  703.85  5161.8  705.24
  5201.9  705.10  5223.9  706.00  5269.2  705.75  5292.0  707.12  5608.6  710.17
#Mann=4,-1,0
  4566.2   0.035       0  5005.1   0.035       0  5010.8   0.035       0
  5223.9    0.05       0
Bank Sta=5005.1,5010.8
Exp/Cntr=0.3,0.1

Type RM Length L Ch R = 1,891,406,406,406
BEGIN DESCRIPTION:
Dry Comal Tributary 11 2.0
END DESCRIPTION:
XS GIS Cut Line= 3
      2211659.06     13781410.17      2212046.71     13781534.06
      2212470.22     13781629.95
#Sta/Elev= 30
  4615.9  716.83  4685.7  716.09  4706.1  716.44  4717.9  715.69  4748.9  715.19
  4793.7  713.17  4800.6  712.54  4821.6  708.10  4832.1  706.61  4863.6  704.44
  4926.6  701.41  4968.6  698.20  4975.3  696.80  4980.5  697.44  4989.6  693.73
  4997.2  693.42  4997.7  692.92  5002.5  692.92  5002.9  693.42  5007.4  694.25
  5022.9  694.23  5041.6  697.80  5072.4  698.57  5144.8  698.27  5154.4  699.01
  5188.0  699.28  5271.1  703.03  5317.4  704.78  5328.7  704.47  5457.1  707.28
#Mann=6,-1,0
  4615.9    0.12       0  4748.9     0.1       0  4793.7    0.12       0
  4997.2    0.05       0  5002.9    0.12       0  5271.1   0.035       0
Bank Sta=4997.2,5002.9
Exp/Cntr=0.3,0.1

Type RM Length L Ch R = 1,485,247,247,247
BEGIN DESCRIPTION:
Dry Comal Tributary 11 1.0
END DESCRIPTION:
XS GIS Cut Line= 3
      2211825.03     13781675.02      2212125.00     13781875.00
      2212375.03     13781724.98
#Sta/Elev= 30
  4638.7  704.39  4661.2  704.29  4667.2  703.57  4674.7  703.87  4782.9  700.32
  4818.9  697.35  4832.5  696.95  4849.4  694.99  4862.5  691.09  4868.5  691.87
  4913.6  690.24  4919.6  691.34  4934.6  689.74  4940.6  691.75  4949.6  691.01
  4955.7  692.82  4976.7  691.52  4988.9  687.85  4989.3  687.35  4994.1  687.35
  4994.6  687.85  4996.2  691.55  5002.1  691.55  5007.0  696.12  5008.8  696.20
  5022.5  696.77  5043.9  696.37  5209.1  700.77  5232.5  701.32  5290.8  704.15
#Mann=6,-1,0
  4638.7    0.12       0  4849.4     0.1       0  4988.9    0.05       0
  4994.6     0.1       0  5008.8    0.12       0  5209.1    0.07       0
Bank Sta=4988.9,4994.6
Exp/Cntr=0.3,0.1

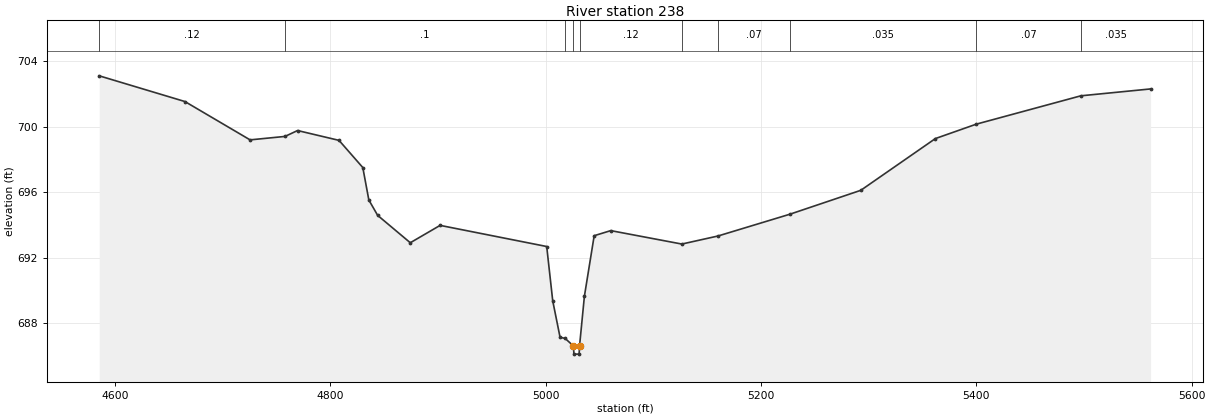
Type RM Length L Ch R = 1,238,0,0,0
BEGIN DESCRIPTION:
X19051
END DESCRIPTION:
XS GIS Cut Line= 3
      2211834.92     13781705.95      2212050.71     13782117.55
      2212550.09     13782229.41
#Sta/Elev= 30
  4585.4  703.11  4665.0  701.54  4725.5  699.20  4757.9  699.41  4769.6  699.77
  4808.1  699.17  4830.2  697.51  4835.8  695.53  4844.0  694.59  4874.3  692.92
  4902.0  693.98  5001.0  692.69  5006.6  689.37  5013.4  687.15  5018.1  687.08
  5025.8  686.62  5026.3  686.12  5031.1  686.12  5031.5  686.62  5036.0  689.65
  5045.1  693.35  5060.5  693.66  5126.5  692.84  5160.0  693.33  5226.8  694.66
  5292.7  696.12  5362.0  699.28  5400.0  700.16  5497.1  701.89  5561.9  702.31
#Mann=10,-1,0
  4585.4    0.12       0  4757.9     0.1       0  5018.1    0.12       0
  5025.8    0.05       0  5031.5    0.12       0  5126.5   0.035       0
  5160.0    0.07       0  5226.8   0.035       0  5400.0    0.07       0
  5497.1   0.035       0
Bank Sta=5025.8,5031.5
Exp/Cntr=0.3,0.1

Chan Stop Cuts=-1