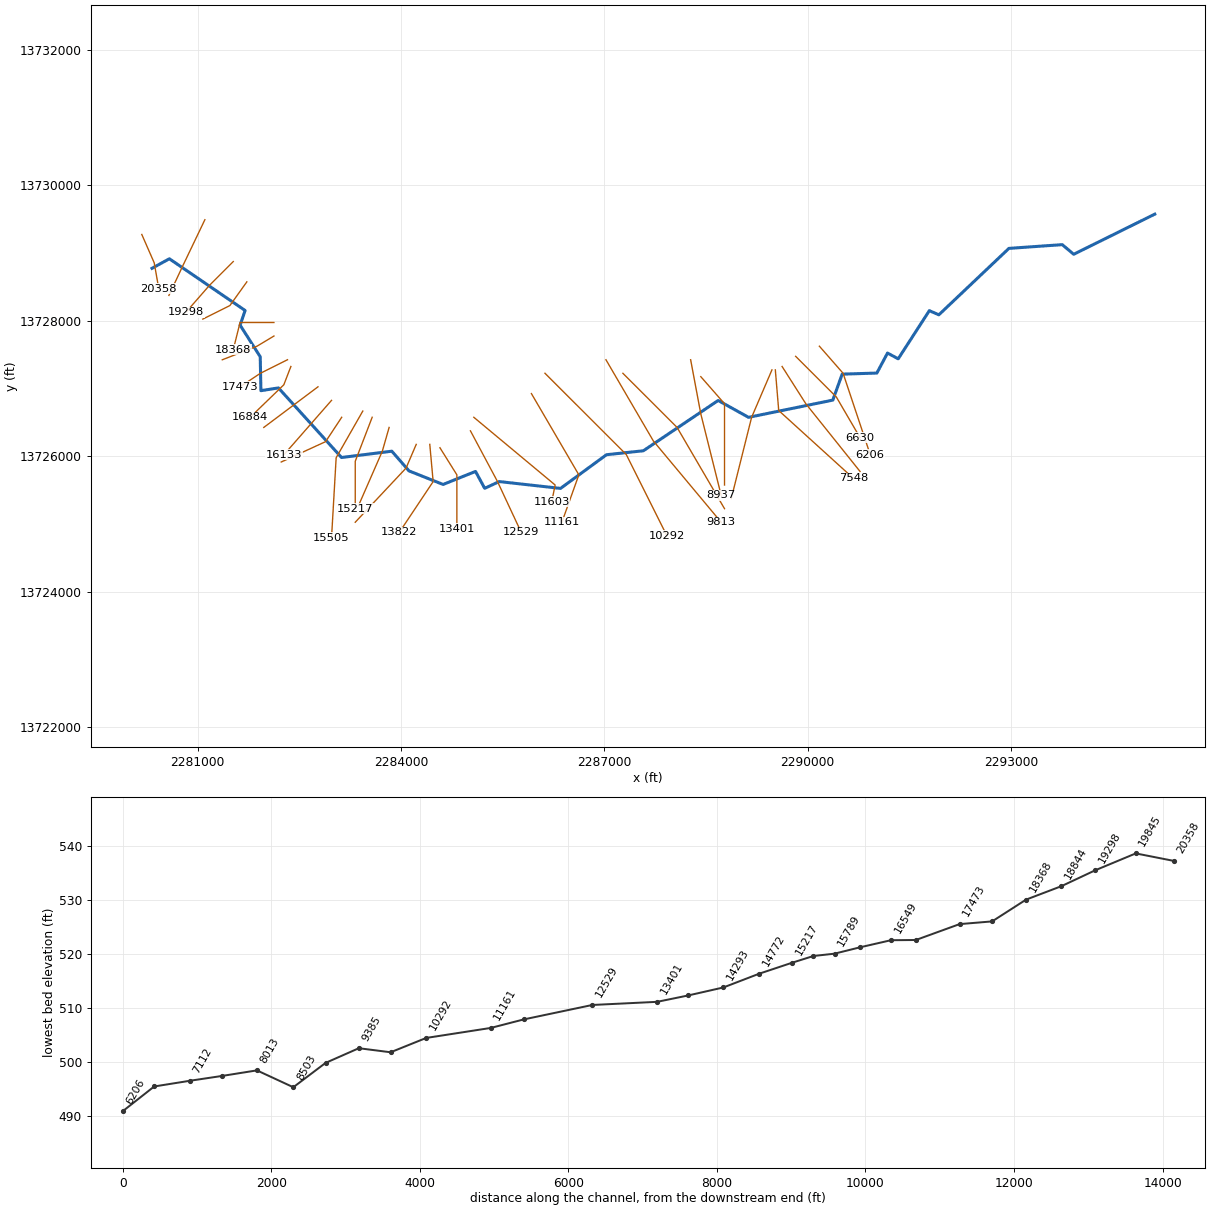
--- ELM CREEK NORTH.prj (project) ---

Proj Title=ELM CREEK NORTH Base Level Engineering
Current Plan=p01
Default Exp/Contr=0.3,0.1
English Units
Geom File=g01
Flow File=f01
Plan File=p01
Y Axis Title=Elevation
X Axis Title(PF)=Main Channel Distance
X Axis Title(XS)=Station
BEGIN DESCRIPTION:
ELM CREEK NORTH
END DESCRIPTION:
DSS Export Rating Curves= 0
DSS Export Rating Curve Sorted= 0
DSS Export Volume Flow Curves= 0
DXF OffsetX= 0
DXF OffsetY= 0
DXF ScaleX= 1
DXF ScaleY= 10

--- ELM CREEK NORTH.p01 (plan) ---

Plan Title=Multiple Run
Short Identifier=Multiple
Geom File=g01
Flow File=f01
Subcritical Flow
K Sum by GR= 0
Std Step Tol= 0.01
Critical Tol= 0.01
Num of Std Step Trials= 20
Max Error Tol= 0.3
Flow Tol Ratio= 0.001
Split Flow NTrial= 30
Split Flow Tol= 0.02
Split Flow Ratio= 0.02
Log Output Level= 0
Friction Slope Method= 1
Unsteady Friction Slope Method= 2
Unsteady Bridges Friction Slope Method= 1
Parabolic Critical Depth
Global Vel Dist=  1 , 1 , 1
Global Log Level= 0
CheckData=True
Encroach Param= -1, 0, 0, 0
BEGIN DESCRIPTION:
Multiple Run
END DESCRIPTION:

--- ELM CREEK NORTH.f01 (steady flow) ---

Flow Title=Multiple
Number of Profiles=7
Profile Names=10-year,25-year,50-year,1pct_min,100-year,1pct_plu,500-year
River Rch & RM= ELM CREEK NORTH,Reach-1,20358
     750    1226    1660    1089    2172    4334    3679
River Rch & RM= ELM CREEK NORTH,Reach-1,19845
    1068    1769    2417    1596    3184    6353    5472
River Rch & RM= ELM CREEK NORTH,Reach-1,15505
    1360    2274    3126    2074    4137    8255    7180
River Rch & RM= ELM CREEK NORTH,Reach-1,11161
    1459    2447    3371    2240    4470    8918    7788
River Rch & RM= ELM CREEK NORTH,Reach-1,10292
    1754    2952    4076    2714    5415   10803    9477
River Rch & RM= ELM CREEK NORTH,Reach-1,4391
    1806    3042    4202    2799    5584   11141    9781
River Rch & RM= ELM CREEK NORTH,Reach-1,1032
    2958    5087    7127    4808    9592   19139   17239
Boundary for River Rch & Prof#=ELM CREEK NORTH,Reach-1,1
Up Type=0
Dn Type=3
Dn Slope=0.005
Boundary for River Rch & Prof#=ELM CREEK NORTH,Reach-1,2
Up Type=0
Dn Type=3
Dn Slope=0.005
Boundary for River Rch & Prof#=ELM CREEK NORTH,Reach-1,3
Up Type=0
Dn Type=3
Dn Slope=0.005
Boundary for River Rch & Prof#=ELM CREEK NORTH,Reach-1,4
Up Type=0
Dn Type=3
Dn Slope=0.005
Boundary for River Rch & Prof#=ELM CREEK NORTH,Reach-1,5
Up Type=0
Dn Type=3
Dn Slope=0.005
Boundary for River Rch & Prof#=ELM CREEK NORTH,Reach-1,6
Up Type=0
Dn Type=3
Dn Slope=0.005
Boundary for River Rch & Prof#=ELM CREEK NORTH,Reach-1,7
Up Type=0
Dn Type=3
Dn Slope=0.005

--- ELM CREEK NORTH.g01 (geometry) ---

Geom Title=Existing Conditions
Program Version=4.10

River Reach=ELM CREEK NORTH ,Reach-1
Reach XY= 30
        2280325.       13728775.      2280581.69     13728916.05
      2281699.53     13728152.14      2281625.88     13727935.34
      2281922.73     13727469.06       2281932.8     13726968.16
      2282191.71     13727008.71      2283122.69     13725980.82
      2283864.71     13726074.03      2284118.83     13725782.86
      2284621.78     13725582.87      2285100.22      13725775.5
      2285235.48     13725525.93      2285449.96     13725625.49
      2286354.84     13725524.68      2287033.18     13726022.15
      2287577.45     13726080.46      2288681.11     13726823.21
      2289130.03     13726574.19      2290373.54     13726828.54
       2290511.3     13727212.04      2291023.38     13727228.12
      2291180.84     13727523.51      2291338.34     13727438.41
      2291797.88     13728149.52      2291938.33     13728088.42
      2292972.55     13729069.53      2293759.84     13729124.62
      2293928.58     13728982.46        2295125.       13729575.

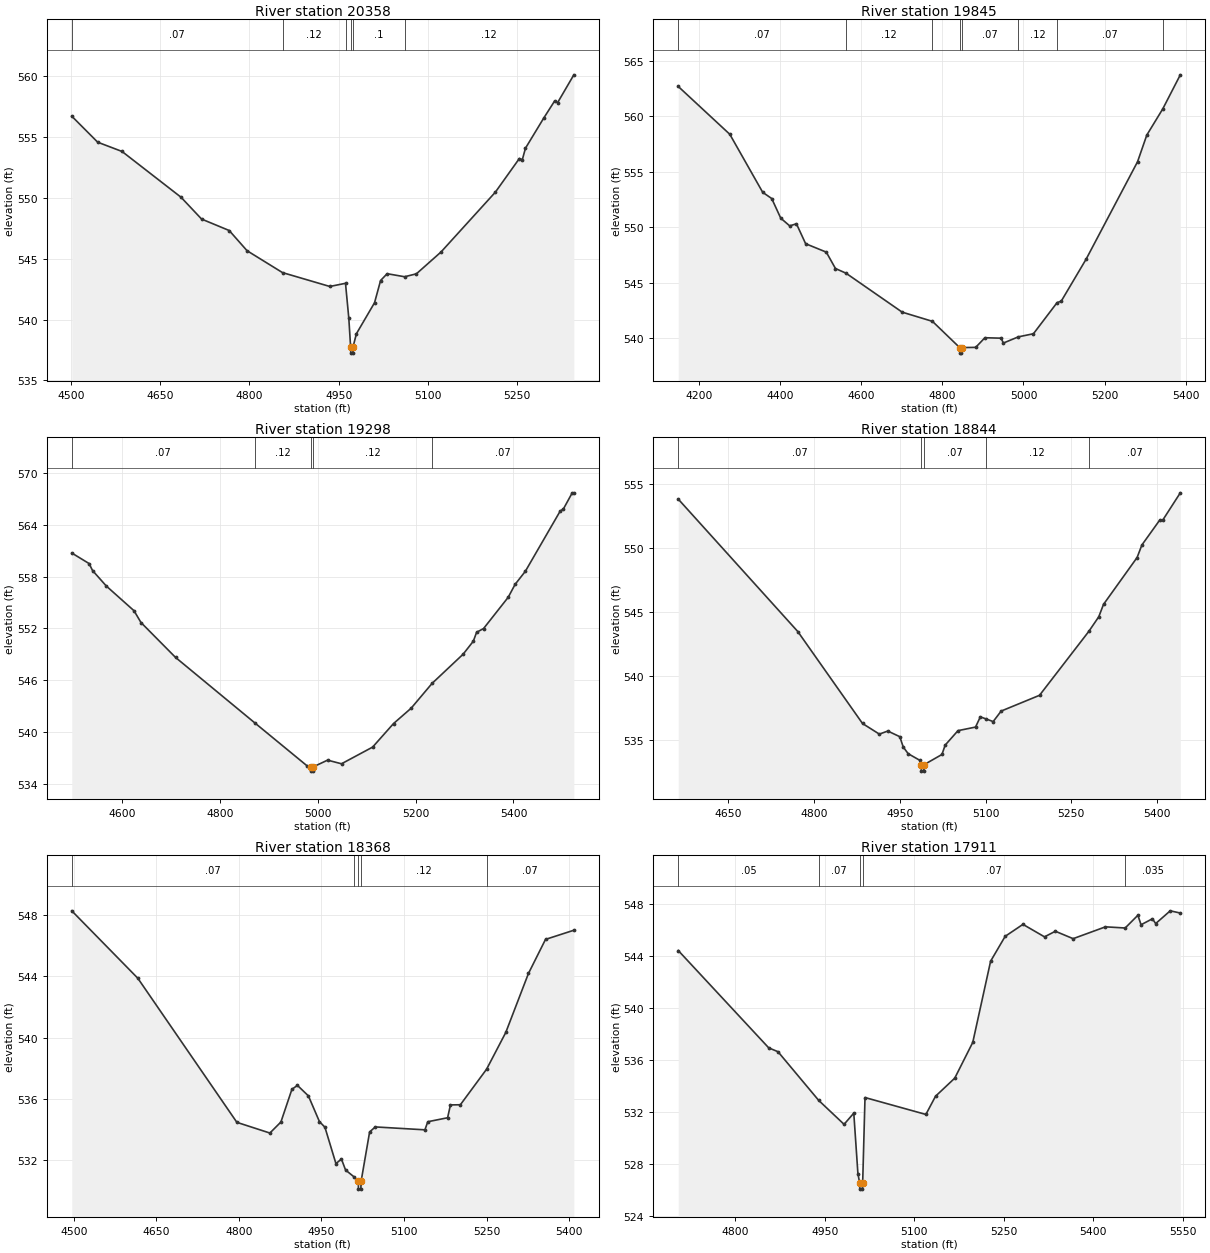
Type RM Length L Ch R = 1 ,20358   ,513,513,513
BEGIN DESCRIPTION:
ELM CREEK NORTH 39.0
END DESCRIPTION:
XS GIS Cut Line= 3
      2280175.02     13729274.96      2280357.98     13728856.75
      2280425.01     13728474.97
#Sta/Elev= 30
  4501.2  556.72  4544.8  554.58  4585.7  553.82  4684.8  550.06  4719.5  548.26
  4765.9  547.32  4795.9  545.66  4855.5  543.86    4935  542.72  4961.4  542.98
    4967  540.09    4970  537.74  4970.3  537.24  4973.8  537.24    4974  537.74
  4979.8  538.84  5010.2  541.38  5020.4  543.21  5031.4  543.77  5060.8  543.52
  5080.6  543.76  5121.9  545.55  5213.3  550.47  5253.7  553.24  5258.7  553.15
    5264  554.09  5294.5  556.55    5313  557.97  5318.1  557.84  5345.3  560.12
#Mann= 6 ,-1 , 0
  4501.2     .07       0  4855.5     .12       0  4961.4      .1       0
    4970     .05       0    4974      .1       0  5060.8     .12       0
Bank Sta=4970,4974
XS Rating Curve= 0 ,0
Exp/Cntr=0.3,0.1

Type RM Length L Ch R = 1 ,19845   ,547,547,547
BEGIN DESCRIPTION:
ELM CREEK NORTH 38.0
END DESCRIPTION:
XS GIS Cut Line= 3
      2281105.74     13729492.82      2280780.42     13728813.05
      2280575.01     13728375.02
#Sta/Elev= 30
  4149.2  562.71  4276.3  558.39  4357.4  553.15  4379.6  552.59  4401.8  550.82
  4423.9  550.12  4440.5  550.31  4463.2  548.51  4514.1  547.75  4536.7  546.27
  4562.6  545.85  4701.1  542.33  4775.7   541.5  4842.9  539.13  4843.2  538.63
  4847.2  538.63  4847.6  539.13  4882.3  539.15    4905  540.02  4944.8  539.98
  4950.6  539.54  4987.4   540.1  5024.6  540.38  5082.9  543.19  5093.1  543.32
  5154.7  547.13  5281.2  555.91    5304  558.32  5343.3  560.68  5386.6  563.76
#Mann= 8 ,-1 , 0
  4149.2     .07       0  4562.6     .12       0  4775.7     .07       0
  4842.9     .05       0  4847.6     .07       0  4987.4     .12       0
  5082.9     .07       0  5343.3     .12       0
Bank Sta=4842.9,4847.6
XS Rating Curve= 0 ,0
Exp/Cntr=0.3,0.1

Type RM Length L Ch R = 1 ,19298   ,454,454,454
BEGIN DESCRIPTION:
ELM CREEK NORTH 37.0
END DESCRIPTION:
XS GIS Cut Line= 3
      2281525.03     13728875.03        2281175.       13728525.
      2280825.02     13728125.02
#Sta/Elev= 30
  4496.9  560.73  4532.3  559.51  4539.4   558.7  4567.7   556.9  4624.2  554.05
  4638.4  552.69  4709.1  548.65  4870.9  541.09  4977.8  536.12    4986     536
  4986.3   535.5  4990.4   535.5  4990.8     536  5019.9  536.77  5048.4  536.35
    5112  538.28  5154.7     541  5190.8  542.78  5233.6  545.65  5297.1  549.03
  5317.9  550.53  5324.6  551.56  5338.8  551.99  5389.1   555.6  5403.4  557.11
  5424.2  558.61  5495.4  565.57  5502.1  565.83  5520.1  567.69  5523.4  567.69
#Mann= 5 ,-1 , 0
  4496.9     .07       0  4870.9     .12       0    4986     .05       0
  4990.8     .12       0  5233.6     .07       0
Bank Sta=4986,4990.8
XS Rating Curve= 0 ,0
Exp/Cntr=0.3,0.1

Type RM Length L Ch R = 1 ,18844   ,476,476,476
BEGIN DESCRIPTION:
ELM CREEK NORTH 36.0
END DESCRIPTION:
XS GIS Cut Line= 3
      2281724.99     13728574.98        2281475.       13728225.
      2281075.01       13728025.
#Sta/Elev= 30
  4563.1  553.81    4772  543.47  4885.1  536.29  4914.5  535.46  4929.3   535.7
  4950.2  535.26  4956.3  534.45  4964.9  533.93  4985.8   533.4  4987.7  533.07
  4988.1  532.57  4992.2  532.57  4992.5  533.07  5023.9  533.87  5029.5   534.6
  5051.9  535.73  5082.6  536.01    5091  536.81  5100.6  536.65  5113.4  536.44
  5127.4  537.26  5194.4  538.49  5280.5  543.48  5297.9  544.62  5306.2  545.59
  5364.9  549.25  5373.3  550.23  5404.1  552.15  5409.7  552.17  5440.4   554.3
#Mann= 5 ,-1 , 0
  4563.1     .07       0  4987.7     .05       0  4992.5     .07       0
  5100.6     .12       0  5280.5     .07       0
Bank Sta=4987.7,4992.5
XS Rating Curve= 0 ,0
Exp/Cntr=0.3,0.1

Type RM Length L Ch R = 1 ,18368   ,457,457,457
BEGIN DESCRIPTION:
ELM CREEK NORTH 35.0
END DESCRIPTION:
XS GIS Cut Line= 3
      2282124.98       13727975.        2281625.       13727975.
        2281525.       13727575.
#Sta/Elev= 30
  4496.4  548.29  4616.4  543.88  4796.4  534.45  4856.4  533.75  4876.4  534.47
  4896.4  536.61  4906.4  536.87  4926.4  536.18  4946.4   534.5  4956.4  534.13
  4976.4  531.75  4986.4  532.05  4993.9  531.33  5009.7  530.87    5017  530.58
  5017.4  530.08  5021.7  530.08  5022.1  530.58  5037.6  533.82  5047.9  534.15
  5138.1  533.96  5143.3  534.49  5179.3  534.75  5184.5  535.59  5202.5   535.6
  5250.2  537.93    5285  540.33  5326.2  544.19  5357.2  546.42  5408.7  547.02
#Mann= 5 ,-1 , 0
  4496.4     .07       0  5009.7     .12       0    5017     .05       0
  5022.1     .12       0  5250.2     .07       0
Bank Sta=5017,5022.1
XS Rating Curve= 0 ,0
Exp/Cntr=0.3,0.1

Type RM Length L Ch R = 1 ,17911   ,438,438,438
BEGIN DESCRIPTION:
ELM CREEK NORTH 34.0
END DESCRIPTION:
XS GIS Cut Line= 3
      2282125.01       13727775.        2281875.       13727625.
      2281363.09     13727424.31
#Sta/Elev= 30
  4704.3  544.39  4855.9  536.91  4871.5  536.61  4939.7  532.87  4982.2  531.03
  4998.5  531.89  5005.4  527.25  5008.2  526.55  5008.6  526.05    5013  526.05
  5013.4  526.55  5017.3  533.09  5119.3  531.79  5135.5  533.19  5167.7  534.58
  5197.9  537.33  5227.8  543.57  5252.2  545.48    5282   546.4  5318.1  545.44
  5336.3  545.87  5366.1   545.3  5420.3  546.21  5453.3  546.12  5474.6   547.1
  5479.9  546.37    5499  546.83  5504.4  546.46  5528.8  547.44  5545.7  547.27
#Mann= 5 ,-1 , 0
  4704.3     .05       0  4939.7     .07       0  5008.2     .05       0
  5013.4     .07       0  5453.3    .035       0
Bank Sta=5008.2,5013.4
XS Rating Curve= 0 ,0
Exp/Cntr=0.3,0.1

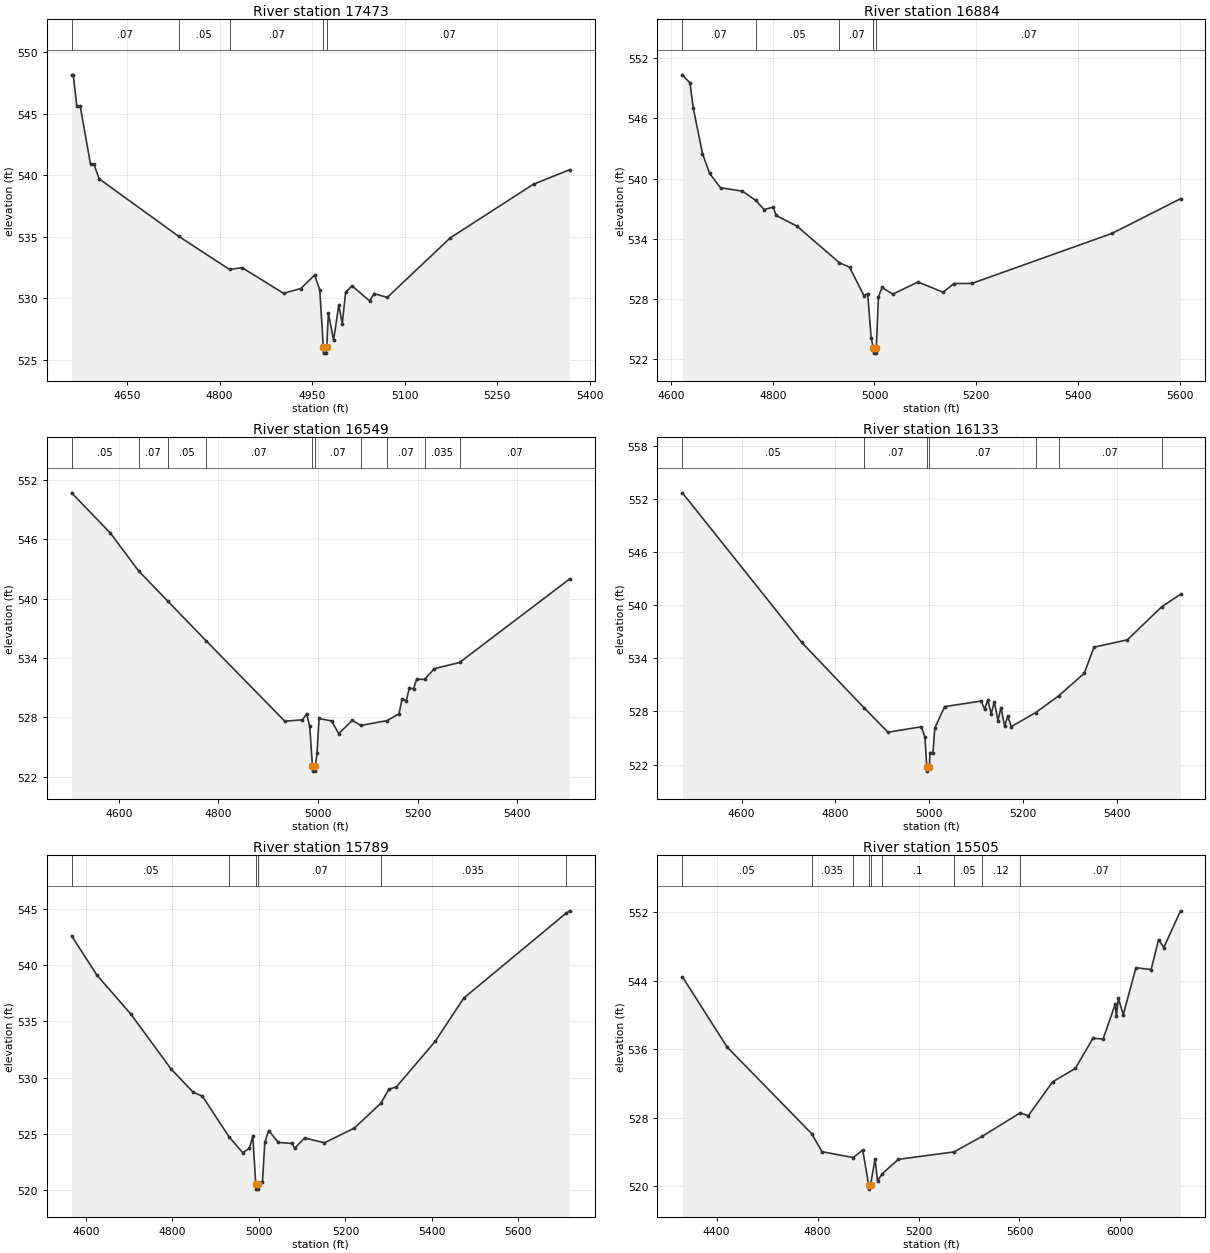
Type RM Length L Ch R = 1 ,17473   ,589,589,589
BEGIN DESCRIPTION:
ELM CREEK NORTH 33.0
END DESCRIPTION:
XS GIS Cut Line= 3
      2282325.02     13727425.01        2281925.       13727225.
      2281624.99       13727025.
#Sta/Elev= 30
  4560.1  548.16  4562.9  548.16  4568.5  545.65  4574.1  545.62  4590.9  540.88
  4596.5  540.88  4604.8  539.71  4733.5  535.05  4816.2  532.35  4836.8  532.49
  4903.9  530.41  4931.9   530.8  4954.2  531.89  4962.6  530.68  4968.3  526.05
  4968.7  525.55  4973.3  525.55  4973.8  526.05  4976.6   528.8    4985  526.59
  4993.4  529.49    4999  527.93  5004.5  530.49  5014.8  531.02  5043.4  529.79
  5050.9  530.39  5071.9  530.07  5174.1  534.91  5309.3  539.28  5367.9  540.45
#Mann= 5 ,-1 , 0
  4560.1     .07       0  4733.5     .05       0  4816.2     .07       0
  4968.3     .05       0  4973.8     .07       0
Bank Sta=4968.3,4973.8
XS Rating Curve= 0 ,0
Exp/Cntr=0.3,0.1

Type RM Length L Ch R = 1 ,16884   ,335,335,335
BEGIN DESCRIPTION:
ELM CREEK NORTH 32.0
END DESCRIPTION:
XS GIS Cut Line= 3
      2282375.01     13727325.03      2282271.12     13727055.28
      2281774.98     13726574.98
#Sta/Elev= 30
  4622.2  550.35  4637.2  549.54  4643.7  547.04  4661.8  542.49  4675.8  540.52
  4697.2  539.09  4740.1  538.76  4766.6  537.83    4783  536.92  4801.1  537.17
  4806.4  536.33  4847.3  535.28    4931  531.62  4951.1  531.17  4979.4  528.32
  4986.6  528.55  4993.5  524.11  4997.9  523.11  4998.3  522.61  5003.1  522.61
  5003.6  523.11  5007.7   528.2  5014.9  529.16    5036  528.49  5085.6   529.7
    5135  528.68  5156.3  529.55  5191.6  529.56  5467.4  534.55  5601.8     538
#Mann= 5 ,-1 , 0
  4622.2     .07       0  4766.6     .05       0    4931     .07       0
  4997.9     .05       0  5003.6     .07       0
Bank Sta=4997.9,5003.6
XS Rating Curve= 0 ,0
Exp/Cntr=0.3,0.1

Type RM Length L Ch R = 1 ,16549   ,416,416,416
BEGIN DESCRIPTION:
ELM CREEK NORTH 31.0
END DESCRIPTION:
XS GIS Cut Line= 3
      2282774.96     13727024.97        2282375.       13726725.
      2281974.96     13726424.97
#Sta/Elev= 30
  4505.1  550.69  4583.2  546.61  4639.7   542.8  4697.9  539.76  4775.2  535.74
  4933.2  527.61  4968.6  527.76  4976.9  528.37  4983.2  527.09  4988.7  523.07
  4989.1  522.57  4993.9  522.57  4994.4  523.07  4997.8  524.36  5001.9  527.89
  5026.9  527.64  5041.5  526.36  5068.6   527.7  5085.9  527.19    5138  527.67
  5162.3  528.35  5168.6  529.87  5176.9  529.68  5183.2  530.97  5191.5  530.89
  5197.8  531.85  5213.9  531.84  5233.2  532.92    5284  533.55  5505.1  541.99
#Mann= 10 ,-1 , 0
  4505.1     .05       0  4639.7     .07       0  4697.9     .05       0
  4775.2     .07       0  4988.7     .05       0  4994.4     .07       0
  5085.9    .035       0    5138     .07       0  5213.9    .035       0
    5284     .07       0
Bank Sta=4988.7,4994.4
XS Rating Curve= 0 ,0
Exp/Cntr=0.3,0.1

Type RM Length L Ch R = 1 ,16133   ,344,344,344
BEGIN DESCRIPTION:
ELM CREEK NORTH 30.0
END DESCRIPTION:
XS GIS Cut Line= 3
      2282974.99     13726824.99        2282625.       13726425.
        2282275.       13726025.
#Sta/Elev= 30
  4473.5  552.67  4728.3  535.78    4861  528.42  4912.4  525.65  4983.6  526.27
  4991.2  525.08    4995  521.76  4995.5  521.26  5000.8  521.76  5001.7  523.35
  5008.3  523.35  5012.1   526.1    5033  528.54  5111.3  529.17  5118.4  528.26
  5125.1  529.26  5132.6  527.76  5139.3  529.08  5146.9  526.96  5153.5  528.44
  5161.1  526.32  5167.8  527.46  5175.4  526.28  5227.4  527.87  5276.4  529.75
    5331   532.3  5351.9  535.25  5423.1  536.08    5496  539.79  5536.5  541.22
#Mann= 7 ,-1 , 0
  4473.5     .05       0    4861     .07       0    4995     .05       0
  5000.8     .07       0  5227.4    .035       0  5276.4     .07       0
    5496    .035       0
Bank Sta=4995,5000.8
XS Rating Curve= 0 ,0
Exp/Cntr=0.3,0.1

Type RM Length L Ch R = 1 ,15789   ,284,284,284
BEGIN DESCRIPTION:
ELM CREEK NORTH 29.0
END DESCRIPTION:
XS GIS Cut Line= 3
        2283125.     13726574.99       2282887.8     13726215.25
      2282232.24     13725914.17
#Sta/Elev= 30
  4566.6  542.61  4625.3  539.11  4703.6  535.65  4796.9  530.76  4848.1  528.69
  4869.2  528.35  4930.9  524.73  4962.5  523.32  4977.6   523.7  4985.8  524.79
  4992.6  520.58  4993.1  520.08    4998  520.08  4998.4  520.58  5008.1   520.7
  5013.6  524.23  5022.6  525.29  5044.6  524.24    5077  524.14  5082.5   523.7
  5105.5  524.63  5151.5   524.2  5220.4   525.5  5282.4  527.73  5300.4  528.97
  5317.9  529.17  5407.7  533.22  5473.8  537.07  5709.9   544.6  5718.9  544.83
#Mann= 6 ,-1 , 0
  4566.6     .05       0  4930.9     .07       0  4992.6     .05       0
  4998.4     .07       0  5282.4    .035       0  5709.9     .07       0
Bank Sta=4992.6,4998.4
XS Rating Curve= 0 ,0
Exp/Cntr=0.3,0.1

Type RM Length L Ch R = 1 ,15505   ,288,288,288
BEGIN DESCRIPTION:
X19143
END DESCRIPTION:
XS GIS Cut Line= 3
       2283436.5     13726666.84      2283043.18     13725977.32
      2282975.28     13724798.68
#Sta/Elev= 30
    4264  544.45  4441.6  536.23  4776.1  526.14  4817.5  524.02  4940.6  523.34
  4978.8  524.21  5002.5  520.15    5003  519.65  5009.8  520.15  5027.8  523.19
  5037.5  520.59  5055.9  521.44  5120.2  523.13    5341     524  5451.3   525.8
  5603.3  528.56  5635.4  528.23  5731.2  532.17  5821.4  533.74  5891.5  537.27
  5931.6  537.18  5979.5  541.23  5984.5  539.84  5991.7  541.96  6011.7  540.03
  6061.8  545.51  6121.9  545.29  6151.6  548.79    6172  547.85  6238.4  552.15
#Mann= 9 ,-1 , 0
    4264     .05       0  4776.1    .035       0  4940.6     .12       0
  5002.5     .05       0  5009.8     .12       0  5055.9      .1       0
    5341     .05       0  5451.3     .12       0  5603.3     .07       0
Bank Sta=5002.5,5009.8
XS Rating Curve= 0 ,0
Exp/Cntr=0.3,0.1

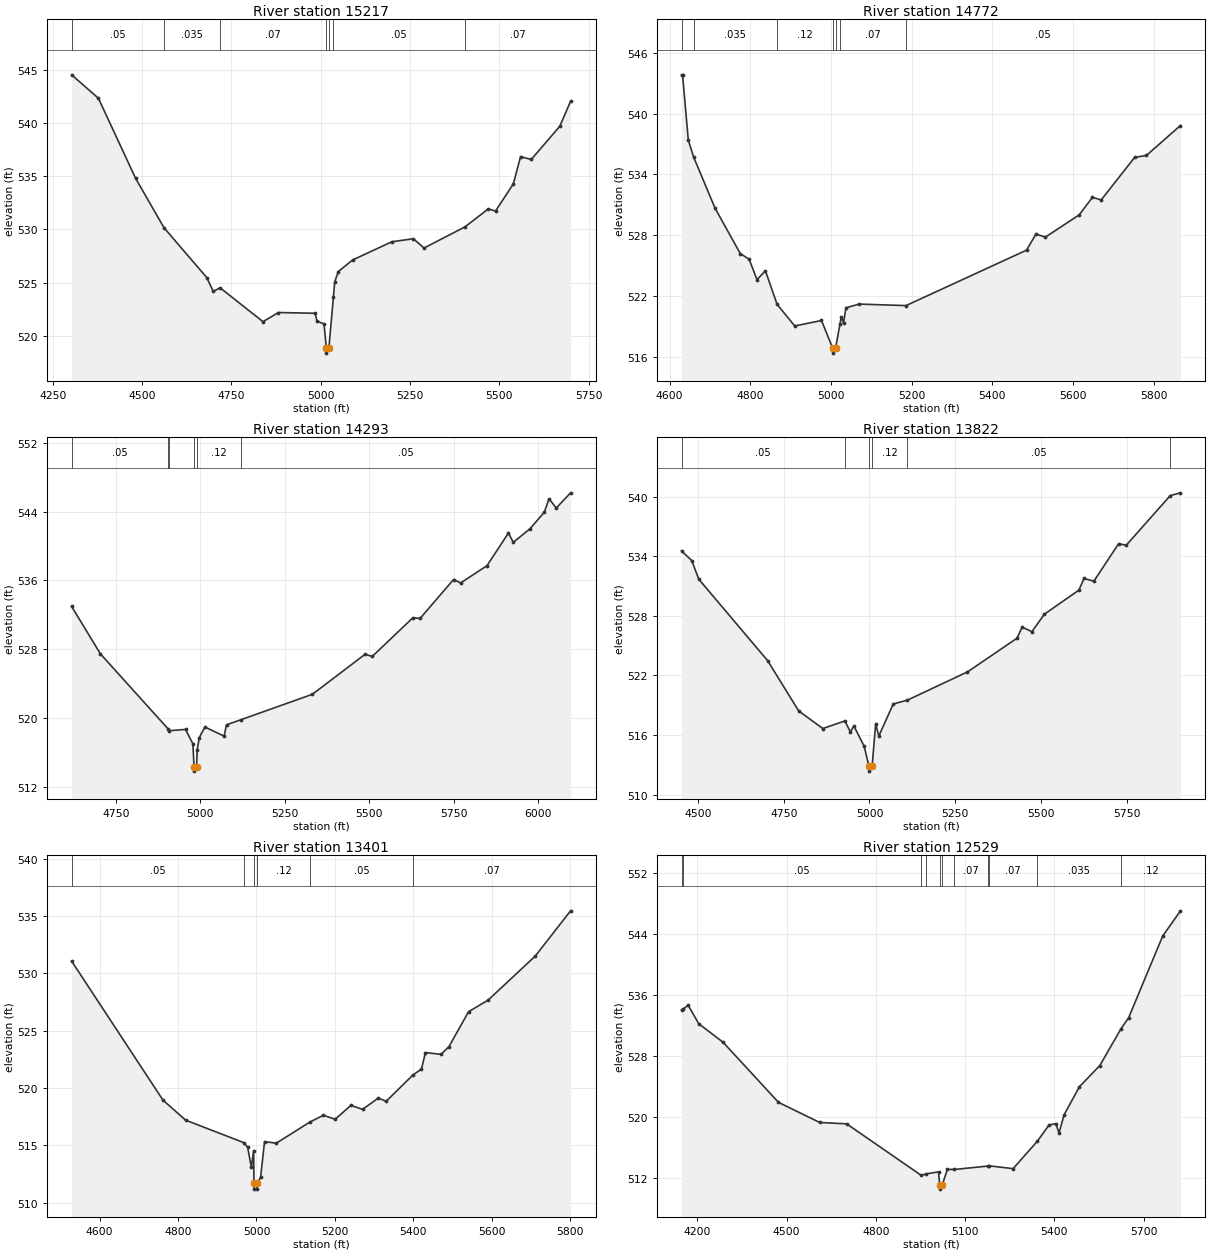
Type RM Length L Ch R = 1 ,15217   ,445,445,445
BEGIN DESCRIPTION:
ELM CREEK NORTH 28.0
END DESCRIPTION:
XS GIS Cut Line= 3
        2283575.       13726575.        2283325.       13725925.
        2283325.     13725225.02
#Sta/Elev= 30
  4303.1  544.51  4378.1  542.31    4482  534.81  4561.7  530.16  4681.3  525.49
  4699.5  524.19  4718.6  524.53  4838.8  521.35  4881.7  522.21  4984.5  522.14
  4989.9   521.4  5009.5  521.14  5015.9   518.9  5016.4   518.4  5023.2   518.9
  5035.7  523.65  5039.5   525.1  5049.5  526.05  5089.5  527.14  5199.5  528.85
  5259.5  529.13  5289.5  528.26  5404.2  530.25  5469.5  531.94  5489.5  531.73
  5539.5  534.29  5559.5  536.83  5589.5  536.57  5669.5  539.69  5699.5  542.03
#Mann= 7 ,-1 , 0
  4303.1     .05       0  4561.7    .035       0  4718.6     .07       0
  5015.9     .05       0  5023.2     .07       0  5035.7     .05       0
  5404.2     .07       0
Bank Sta=5015.9,5023.2
XS Rating Curve= 0 ,0
Exp/Cntr=0.3,0.1

Type RM Length L Ch R = 1 ,14772   ,479,479,479
BEGIN DESCRIPTION:
ELM CREEK NORTH 27.0
END DESCRIPTION:
XS GIS Cut Line= 3
      2283824.99     13726424.95        2283725.       13726075.
      2283374.99     13725274.97
#Sta/Elev= 30
  4629.6  543.82  4632.2  543.82  4646.5  537.36    4660  535.67  4712.8  530.66
  4775.2  526.19  4797.3  525.62  4816.8  523.61  4837.6  524.49  4866.6  521.17
  4910.4  519.04  4976.7  519.58  5004.3  516.86  5004.8  516.36  5011.7  516.86
  5022.7  519.27  5025.9  519.94  5031.4  519.34  5037.2  520.83    5070   521.2
  5186.3  521.05  5485.1  526.52  5508.5  528.11  5531.9  527.81  5615.7     530
  5648.5  531.73  5670.3  531.48  5753.3  535.68  5782.2  535.86  5866.8  538.82
#Mann= 7 ,-1 , 0
  4629.6     .07       0    4660    .035       0  4866.6     .12       0
  5004.3     .05       0  5011.7     .12       0  5022.7     .07       0
  5186.3     .05       0
Bank Sta=5004.3,5011.7
XS Rating Curve= 0 ,0
Exp/Cntr=0.3,0.1

Type RM Length L Ch R = 1 ,14293   ,471,471,471
BEGIN DESCRIPTION:
ELM CREEK NORTH 26.0
END DESCRIPTION:
XS GIS Cut Line= 3
      2284224.98     13726174.96        2284075.       13725825.
      2283325.02     13725025.02
#Sta/Elev= 30
    4619  532.98  4704.2  527.47  4905.4  518.71  4907.8  518.53  4956.2  518.68
    4978  517.01  4981.5  514.33    4982  513.83    4989  514.33  4990.7  516.28
    4997  517.73  5013.7  518.96  5070.3   517.9  5077.6  519.22  5120.7  519.81
  5332.1  522.77    5488  527.42    5509  527.16  5629.6  531.67  5650.6  531.58
  5749.8  536.11  5770.8  535.71  5848.9  537.72  5912.4  541.52  5926.6  540.43
  5975.9     542  6018.4  543.93  6032.6  545.49  6054.1  544.43  6096.3  546.19
#Mann= 6 ,-1 , 0
    4619     .05       0  4905.4     .07       0  4907.8     .12       0
  4981.5     .05       0    4989     .12       0  5120.7     .05       0
Bank Sta=4981.5,4989
XS Rating Curve= 0 ,0
Exp/Cntr=0.3,0.1

Type RM Length L Ch R = 1 ,13822   ,421,421,421
BEGIN DESCRIPTION:
ELM CREEK NORTH 25.0
END DESCRIPTION:
XS GIS Cut Line= 3
        2284425.     13726175.01        2284475.       13725625.
      2283974.98     13724874.97
#Sta/Elev= 30
  4452.3  534.54  4482.4  533.55  4502.5  531.69  4703.3  523.48  4793.7  518.42
    4864  516.65  4928.2  517.41  4944.3  516.31  4954.4  516.91  4984.5  514.86
  4998.3  512.86  4998.8  512.36  5005.9  512.86  5007.6  512.86  5018.1  517.14
  5027.1  515.89  5069.2  519.12  5110.5  519.51  5285.5  522.35  5429.7  525.74
  5444.8  526.86  5473.3   526.4  5509.4  528.16    5610  530.58    5625  531.76
  5653.6  531.48  5725.7  535.25  5748.2  535.11  5876.2   540.1    5906  540.38
#Mann= 6 ,-1 , 0
  4452.3     .05       0  4928.2     .12       0  4998.3     .05       0
  5005.9     .12       0  5110.5     .05       0  5876.2     .07       0
Bank Sta=4998.3,5005.9
XS Rating Curve= 0 ,0
Exp/Cntr=0.3,0.1

Type RM Length L Ch R = 1 ,13401   ,872,872,872
BEGIN DESCRIPTION:
ELM CREEK NORTH 24.0
END DESCRIPTION:
XS GIS Cut Line= 3
      2284574.99     13726125.01        2284825.       13725725.
        2284825.     13724925.01
#Sta/Elev= 30
  4528.8  531.08  4761.7  518.94  4819.5  517.19  4967.6  515.23  4977.5  514.82
  4986.9  513.08  4992.8  514.54  4993.6  511.67  4994.1  511.17    5001  511.17
  5001.5  511.67  5010.5   512.2  5020.5  515.32  5050.5  515.18  5136.2  517.03
  5170.5  517.62  5200.5  517.27  5240.5  518.48  5270.5  518.14  5310.5  519.12
  5330.5  518.84  5398.9  521.14  5420.5  521.65  5430.5  523.09  5470.5  522.94
  5490.5  523.61  5540.5  526.66  5590.5  527.68  5710.5  531.52  5800.5  535.47
#Mann= 6 ,-1 , 0
  4528.8     .05       0  4967.6     .12       0  4993.6     .05       0
  5001.5     .12       0  5136.2     .05       0  5398.9     .07       0
Bank Sta=4993.6,5001.5
XS Rating Curve= 0 ,0
Exp/Cntr=0.3,0.1

Type RM Length L Ch R = 1 ,12529   ,926,926,926
BEGIN DESCRIPTION:
ELM CREEK NORTH 23.0
END DESCRIPTION:
XS GIS Cut Line= 3
      2285025.02     13726374.96        2285425.       13725625.
        2285775.       13724875.
#Sta/Elev= 30
  4146.5  534.05  4152.7  534.18  4169.1  534.64  4204.2  532.24  4286.4   529.8
  4472.6  521.94  4611.1  519.31  4701.8  519.13  4952.6  512.39  4969.9  512.59
  5010.6  512.85  5014.5  511.09    5015  510.59  5022.6  511.09  5040.6  513.18
  5063.5  513.16  5177.4  513.61  5180.7  513.64  5261.3  513.27  5343.3  516.87
  5381.9  518.97  5404.8  519.16  5415.8  517.96  5433.1  520.33  5484.4  523.99
    5553  526.76    5624  531.56  5649.9  533.02  5764.2  543.69  5824.1     547
#Mann= 11 ,-1 , 0
  4146.5    .035       0  4152.7     .05       0  4952.6     .07       0
  4969.9     .12       0  5014.5     .05       0  5022.6     .12       0
  5063.5     .07       0  5177.4     .05       0  5180.7     .07       0
  5343.3    .035       0    5624     .12       0
Bank Sta=5014.5,5022.6
XS Rating Curve= 0 ,0
Exp/Cntr=0.3,0.1

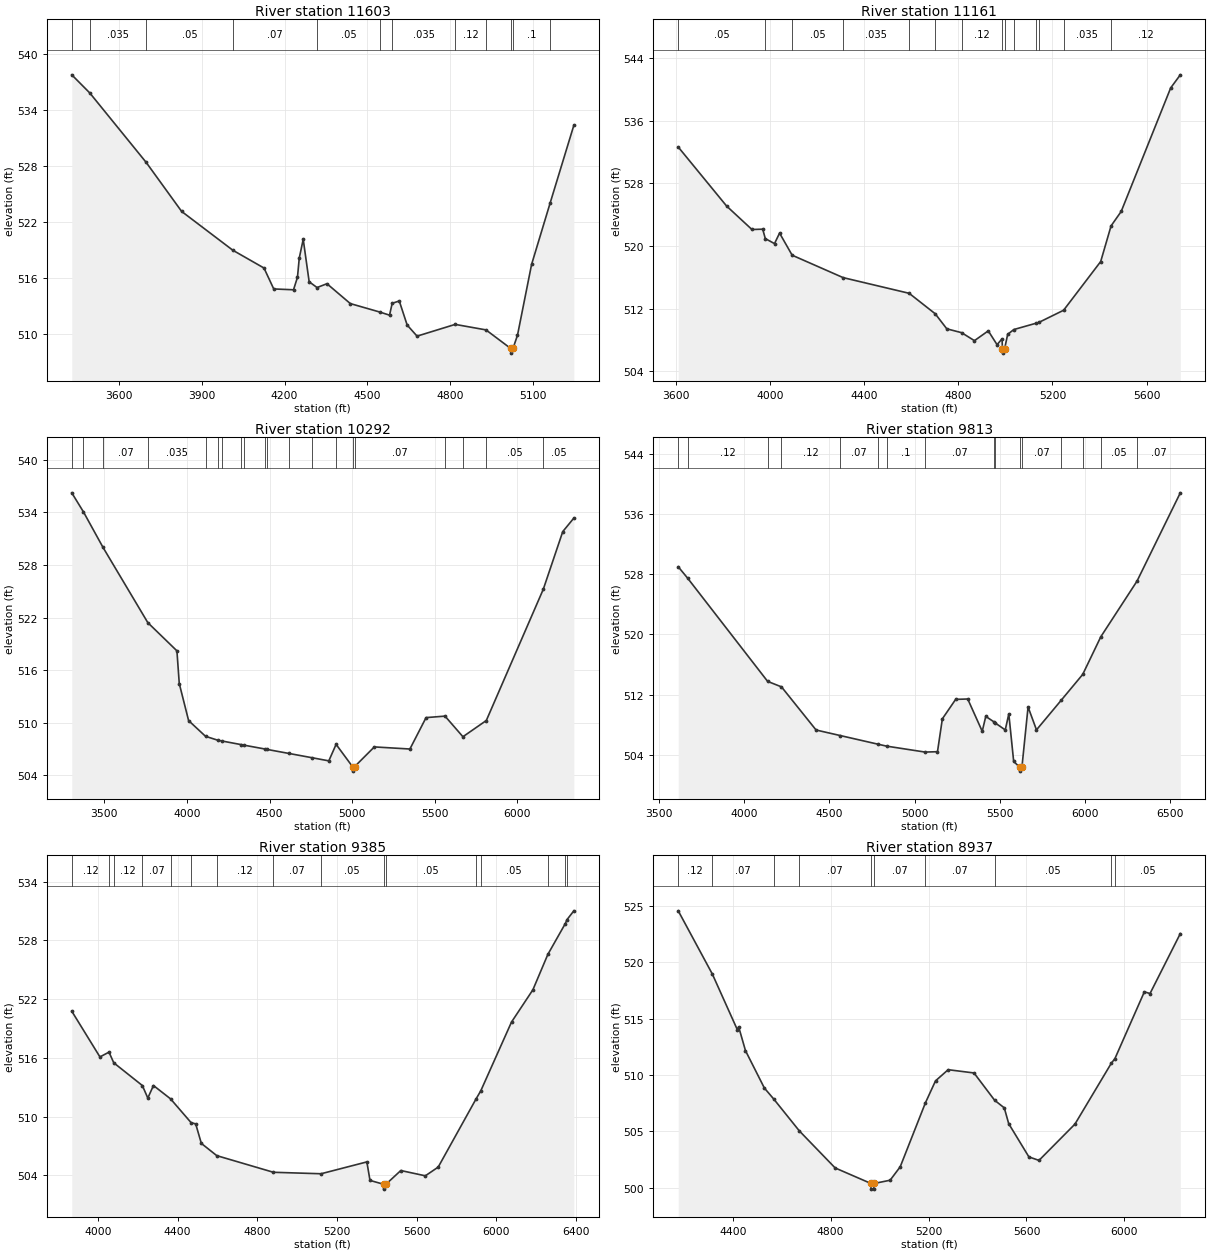
Type RM Length L Ch R = 1 ,11603   ,442,442,442
BEGIN DESCRIPTION:
ELM CREEK NORTH 21.0
END DESCRIPTION:
XS GIS Cut Line= 3
      2285075.04     13726574.97        2286275.       13725575.
      2286224.99     13725324.95
#Sta/Elev= 30
    3430  537.74  3495.1   535.8  3699.1  528.36  3827.6   523.1  4012.8  518.94
  4125.7  517.03  4160.9  514.79  4232.5   514.7  4246.8  516.04  4253.3   518.1
  4267.6  520.11  4289.1  515.56  4317.6  514.94  4353.5  515.35  4438.1  513.22
  4545.1  512.31    4580  511.98  4589.6  513.25  4615.2   513.5  4643.8  510.92
  4679.6  509.73  4817.6  510.99    4929   510.4  5018.5  508.41    5019  507.91
  5026.7  508.41    5043  509.82    5094  517.41  5160.9  523.97    5247  532.33
#Mann= 12 ,-1 , 0
    3430     .07       0  3495.1    .035       0  3699.1     .05       0
  4012.8     .07       0  4317.6     .05       0  4545.1     .07       0
  4589.6    .035       0  4817.6     .12       0    4929      .1       0
  5018.5     .05       0  5026.7      .1       0  5160.9     .12       0
Bank Sta=5018.5,5026.7
XS Rating Curve= 0 ,0
Exp/Cntr=0.3,0.1

Type RM Length L Ch R = 1 ,11161   ,869,869,869
BEGIN DESCRIPTION:
ELM CREEK NORTH 20.0
END DESCRIPTION:
XS GIS Cut Line= 3
      2285925.02     13726924.96        2286625.       13725725.
        2286375.     13725025.01
#Sta/Elev= 30
  3610.8  532.63  3816.3   525.1  3923.8  522.11  3969.6  522.15  3980.6  520.95
  4019.7  520.31  4041.2  521.65  4094.7  518.83  4311.3  515.97  4591.7  513.97
  4702.3  511.36  4751.5  509.44  4814.3  508.95  4868.9  507.93  4927.6  509.18
  4964.9  507.42  4986.4  508.17  4987.7  506.84  4988.2  506.34  4996.6  506.84
  5010.1  508.74  5036.3  509.35  5129.1  510.14  5141.9  510.25  5247.6  511.81
  5405.1  518.02  5449.2  522.57  5492.2  524.41  5702.4  540.17  5743.3  541.84
#Mann= 14 ,-1 , 0
  3610.8     .05       0  3980.6    .035       0  4094.7     .05       0
  4311.3    .035       0  4591.7     .12       0  4702.3     .07       0
  4814.3     .12       0  4987.7     .05       0  4996.6     .12       0
  5036.3     .07       0  5129.1     .12       0  5141.9     .07       0
  5247.6    .035       0  5449.2     .12       0
Bank Sta=4987.7,4996.6
XS Rating Curve= 0 ,0
Exp/Cntr=0.3,0.1

Type RM Length L Ch R = 1 ,10292   ,479,479,479
BEGIN DESCRIPTION:
ELM CREEK NORTH 19.0
END DESCRIPTION:
XS GIS Cut Line= 3
      2286124.98     13727225.02        2287325.       13726025.
      2287924.99     13724825.02
#Sta/Elev= 30
  3302.9  536.21  3373.2  534.05  3492.3  529.98  3763.3  521.41  3939.3   518.2
  3953.5  514.47    4010  510.25  4112.4  508.46  4185.4  508.02  4212.9  507.92
  4328.8  507.51  4348.1  507.44  4472.3  507.01  4483.3  506.97  4618.6   506.5
  4759.3  506.01  4858.6  505.66  4902.7  507.54  5002.5  504.99    5003  504.49
  5014.2  504.99  5134.1  507.25  5349.4  507.01  5447.2  510.59  5561.8  510.76
  5670.3  508.41  5811.9  510.26  6156.9  525.23  6274.5  531.79  6341.6  533.33
#Mann= 20 ,-1 , 0
  3302.9     .07       0  3373.2     .05       0  3492.3     .07       0
  3763.3    .035       0  4112.4     .12       0  4185.4    .035       0
  4212.9     .12       0  4328.8    .035       0  4348.1     .12       0
  4472.3    .035       0  4483.3     .12       0  4618.6     .12       0
  4759.3     .12       0  4902.7     .07       0  5002.5     .05       0
  5014.2     .07       0  5561.8     .05       0  5670.3     .07       0
  5811.9     .05       0  6156.9     .05       0
Bank Sta=5002.5,5014.2
XS Rating Curve= 0 ,0
Exp/Cntr=0.3,0.1

Type RM Length L Ch R = 1 ,9813    ,428,428,428
BEGIN DESCRIPTION:
ELM CREEK NORTH 18.0
END DESCRIPTION:
XS GIS Cut Line= 3
      2287025.02     13727424.96        2287725.       13726225.
      2288724.97     13725025.03
#Sta/Elev= 30
  3611.1  528.98  3665.9  527.48  4136.5  513.76    4218  513.03  4421.4   507.3
  4562.3  506.57  4786.4  505.41  4835.5  505.16  5062.1  504.37    5135  504.42
  5163.7  508.79  5241.8  511.37  5312.7  511.42    5398  507.13  5418.8  509.11
  5468.9  508.35  5472.3  508.27  5533.3  507.31  5554.2  509.44  5582.8  503.13
  5619.1  502.34  5619.6  501.84  5631.2  502.34  5667.4  510.36  5716.9  507.32
    5861  511.22  5988.8  514.69  6094.9  519.68  6307.7  527.07  6562.3   538.8
#Mann= 16 ,-1 , 0
  3611.1     .07       0  3665.9     .12       0  4136.5     .07       0
    4218     .12       0  4562.3     .07       0  4786.4     .12       0
  4835.5      .1       0  5062.1     .07       0  5468.9     .05       0
  5472.3     .07       0  5619.1     .05       0  5631.2     .07       0
    5861     .05       0  5988.8    .035       0  6094.9     .05       0
  6307.7     .07       0
Bank Sta=5619.1,5631.2
XS Rating Curve= 0 ,0
Exp/Cntr=0.3,0.1

Type RM Length L Ch R = 1 ,9385    ,448,448,448
BEGIN DESCRIPTION:
ELM CREEK NORTH 17.0
END DESCRIPTION:
XS GIS Cut Line= 3
      2287275.03     13727224.97        2288075.       13726425.
      2288775.02     13725224.97
#Sta/Elev= 30
  3868.7  520.76  4010.1  516.09  4055.6  516.58  4079.5  515.49    4223  513.17
  4250.5  511.89  4278.8  513.17  4364.6  511.81  4467.7  509.38  4490.9  509.25
  4519.2  507.26  4596.6  506.01  4881.1  504.31  5120.3  504.16  5350.2  505.37
  5365.9  503.48  5433.8  503.09  5434.3  502.59  5446.1  503.09  5520.6  504.49
  5643.8  503.95  5708.3  504.84  5898.3   511.8  5921.9  512.62  6076.3  519.65
  6183.8  522.95  6258.8  526.56  6346.5  529.71  6355.3  530.12  6389.3  531.01
#Mann= 16 ,-1 , 0
  3868.7     .12       0  4055.6     .07       0  4079.5     .12       0
    4223     .07       0  4364.6     .12       0  4467.7     .07       0
  4596.6     .12       0  4881.1     .07       0  5120.3     .05       0
  5433.8     .05       0  5446.1     .05       0  5898.3    .035       0
  5921.9     .05       0  6258.8     .07       0  6346.5     .05       0
  6355.3     .12       0
Bank Sta=5433.8,5446.1
XS Rating Curve= 0 ,0
Exp/Cntr=0.3,0.1

Type RM Length L Ch R = 1 ,8937    ,434,434,434
BEGIN DESCRIPTION:
ELM CREEK NORTH 16.0
END DESCRIPTION:
XS GIS Cut Line= 3
        2288275.     13727424.99        2288425.       13726625.
      2288725.01     13725424.97
#Sta/Elev= 30
  4177.5  524.57    4317  518.95  4419.1  514.01  4424.2  514.28  4452.2  512.16
  4529.4  508.84  4567.5  507.87  4672.1  505.04  4818.5  501.75  4964.9  500.37
  4965.4  499.87  4976.7  499.87  4977.2  500.37    5043  500.66  5084.2  501.85
  5187.2  507.53  5228.5  509.48  5280.1  510.47  5385.7  510.18  5469.8  507.76
  5509.4  507.08  5527.4  505.68  5609.9  502.73  5651.1  502.42    5798  505.64
  5947.3  511.07    5961  511.44  6081.5  517.38  6104.7  517.23  6228.4  522.55
#Mann= 10 ,-1 , 0
  4177.5     .12       0    4317     .07       0  4567.5     .12       0
  4672.1     .07       0  4964.9     .05       0  4977.2     .07       0
  5187.2     .07       0  5469.8     .05       0  5947.3    .035       0
    5961     .05       0
Bank Sta=4964.9,4977.2
XS Rating Curve= 0 ,0
Exp/Cntr=0.3,0.1

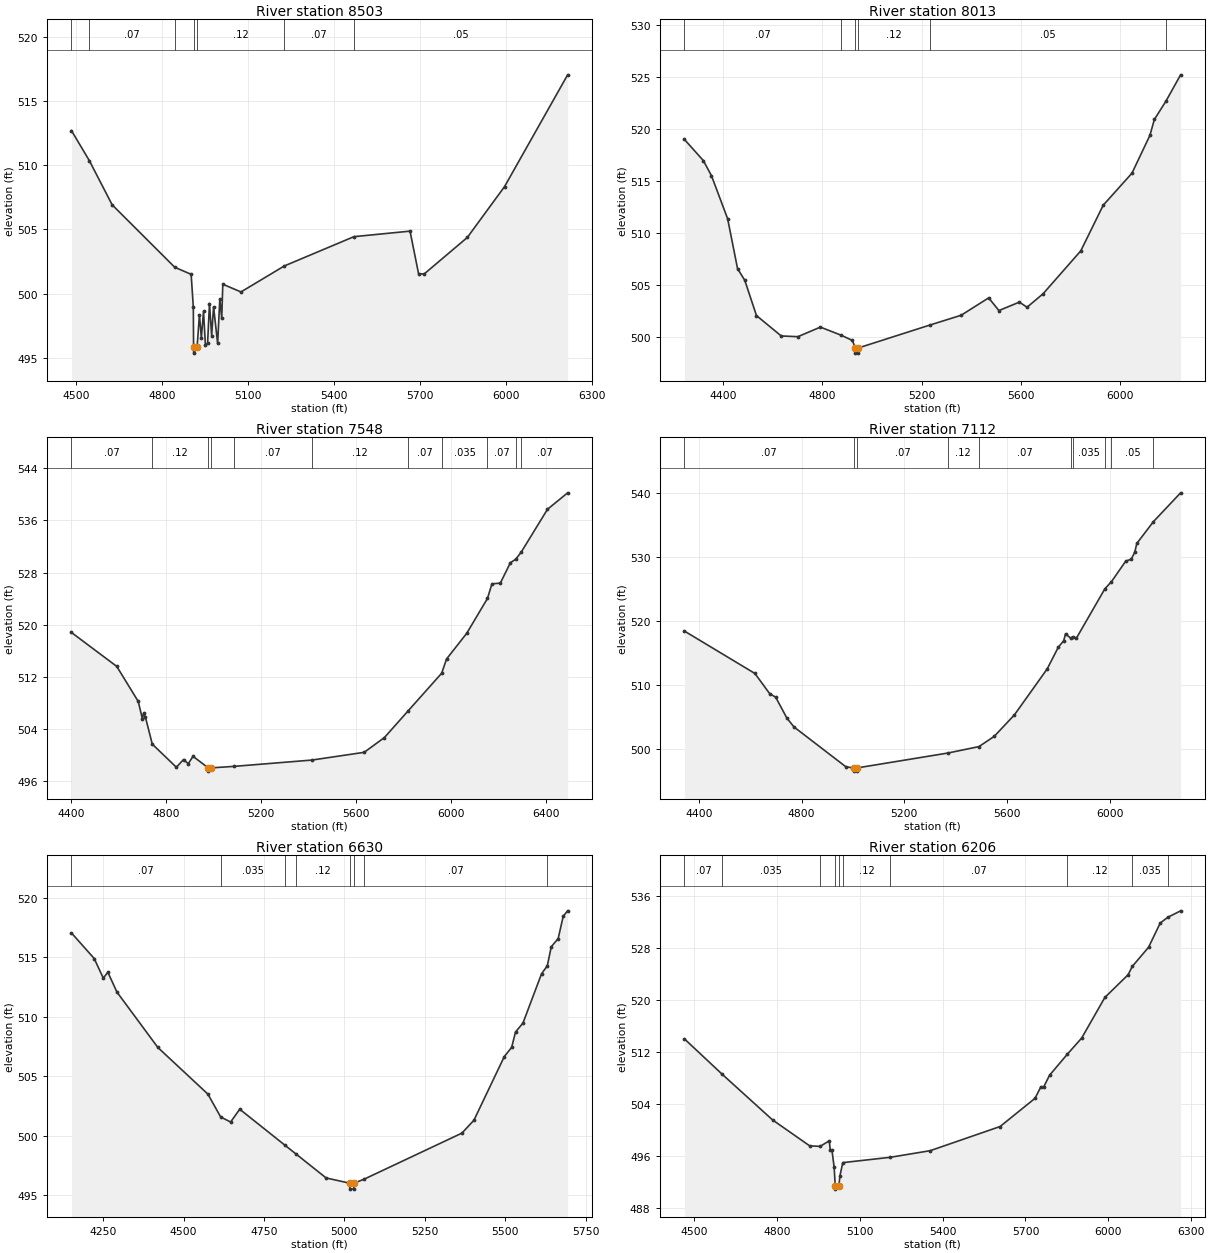
Type RM Length L Ch R = 1 ,8503    ,490,490,490
BEGIN DESCRIPTION:
ELM CREEK NORTH 15.0
END DESCRIPTION:
XS GIS Cut Line= 3
      2288425.02     13727174.97        2288775.       13726775.
        2288775.     13725574.97
#Sta/Elev= 30
  4484.5  512.68    4547  510.34  4626.4  506.91  4844.9  502.05  4902.1   501.5
  4909.7  498.97  4910.6  495.87  4911.1  495.37    4923  495.87    4931  498.36
  4937.7  496.56  4945.3  498.61  4951.9  496.01  4959.5  496.13  4966.1  499.23
  4973.7  496.74  4980.4  498.98  4994.6  496.12  5002.2   499.6  5008.9  498.07
  5012.6  500.73    5076  500.13  5227.2  502.15  5470.3  504.43    5666  504.86
    5696  501.53    5716  501.54    5866  504.37    5996  508.33    6216  517.02
#Mann= 7 ,-1 , 0
  4484.5     .12       0    4547     .07       0  4844.9     .12       0
  4910.6     .05       0    4923     .12       0  5227.2     .07       0
  5470.3     .05       0
Bank Sta=4910.6,4923
XS Rating Curve= 0 ,0
Exp/Cntr=0.3,0.1

Type RM Length L Ch R = 1 ,8013    ,465,465,465
BEGIN DESCRIPTION:
ELM CREEK NORTH 14.0
END DESCRIPTION:
XS GIS Cut Line= 3
      2289474.98     13727274.96        2289175.       13726575.
      2288874.99     13725374.97
#Sta/Elev= 30
  4244.7  519.02  4320.8  516.99  4353.5  515.54  4418.7   511.4  4458.6  506.61
  4487.6  505.49  4534.8   502.1  4634.5  500.14  4701.6  500.07  4792.3  500.99
  4875.1  500.22    4921  499.71  4932.9  498.99  4933.4  498.49  4944.8  498.49
  4945.3  498.99  5232.2  501.18  5359.3  502.13  5470.1   503.8  5511.3  502.58
  5593.8  503.39  5624.7   502.9  5689.1  504.19  5841.2  508.32  5931.4   512.7
  6047.3  515.78  6119.5  519.41  6137.5  520.94  6184.1   522.7  6243.2  525.23
#Mann= 6 ,-1 , 0
  4244.7     .07       0  4875.1     .12       0  4932.9     .05       0
  4945.3     .12       0  5232.2     .05       0  6184.1     .07       0
Bank Sta=4932.9,4945.3
XS Rating Curve= 0 ,0
Exp/Cntr=0.3,0.1

Type RM Length L Ch R = 1 ,7548    ,436,436,436
BEGIN DESCRIPTION:
ELM CREEK NORTH 13.0
END DESCRIPTION:
XS GIS Cut Line= 3
        2289525.     13727274.95        2289575.       13726675.
      2290674.97     13725675.02
#Sta/Elev= 30
  4402.7  518.78  4593.3  513.57  4683.6  508.19  4701.2  505.52  4706.2  506.35
  4713.7  505.82  4742.8  501.62  4844.2  498.07  4874.3  499.25  4894.3  498.61
  4914.4  499.75  4978.2  497.97  4978.7  497.47  4991.1  497.97    5087   498.2
  5414.6  499.17  5634.8  500.36    5720  502.63  5819.8  506.73  5961.1  512.52
  5981.5   514.7  6066.6  518.66  6153.7  524.01  6172.7  526.26  6207.9  526.37
  6250.4  529.51  6272.7  530.04  6295.4  531.11  6406.5  537.72  6491.3  540.25
#Mann= 11 ,-1 , 0
  4402.7     .07       0  4742.8     .12       0  4978.2     .05       0
  4991.1     .12       0    5087     .07       0  5414.6     .12       0
  5819.8     .07       0  5961.1    .035       0  6153.7     .07       0
  6272.7     .05       0  6295.4     .07       0
Bank Sta=4978.2,4991.1
XS Rating Curve= 0 ,0
Exp/Cntr=0.3,0.1

Type RM Length L Ch R = 1 ,7112    ,482,482,482
BEGIN DESCRIPTION:
ELM CREEK NORTH 12.0
END DESCRIPTION:
XS GIS Cut Line= 3
      2289624.98     13727325.03        2289975.       13726775.
      2290775.01     13725774.99
#Sta/Elev= 30
  4343.7  518.45  4618.1  511.83  4675.6  508.68  4699.3  508.11  4742.5  504.87
  4770.4  503.47  4972.8  497.24  5002.8  497.07  5003.3  496.57  5015.3  496.57
  5015.8  497.07  5368.9  499.39  5490.6   500.4  5550.3     502  5628.8  505.35
  5756.8  512.55    5800  515.94  5820.9  516.94  5828.1  518.03  5849.3   517.3
  5855.7  517.55  5870.5  517.35  5981.1  525.04  6007.1  526.18  6062.6  529.38
  6084.2  529.68  6097.8  530.79  6105.8  532.15  6170.7  535.56  6276.3  540.05
#Mann= 10 ,-1 , 0
  4343.7     .07       0  5002.8     .05       0  5015.8     .07       0
  5368.9     .12       0  5490.6     .07       0  5849.3     .12       0
  5855.7    .035       0  5981.1     .07       0  6007.1     .05       0
  6170.7     .07       0
Bank Sta=5002.8,5015.8
XS Rating Curve= 0 ,0
Exp/Cntr=0.3,0.1

Type RM Length L Ch R = 1 ,6630    ,424,424,424
BEGIN DESCRIPTION:
ELM CREEK NORTH 11.0
END DESCRIPTION:
XS GIS Cut Line= 3
        2289825.       13727475.        2290425.       13726875.
      2290775.02     13726274.96
#Sta/Elev= 30
  4151.2  517.05  4221.9   514.9  4250.2  513.25  4264.3  513.75  4292.6  512.08
  4419.9  507.42  4575.5   503.5  4615.2  501.58  4646.2  501.15  4674.5  502.23
  4814.3  499.22  4848.4  498.49  4943.2  496.45  5016.4  496.01  5016.9  495.51
  5028.9  495.51  5029.4  496.01  5060.1  496.33  5365.6  500.22  5402.9   501.3
  5497.5  506.66  5520.3  507.43  5532.3  508.72  5555.4  509.47  5613.3  513.62
  5631.1  514.28  5643.5  515.89    5665  516.58  5680.7  518.46  5694.4  518.91
#Mann= 8 ,-1 , 0
  4151.2     .07       0  4615.2    .035       0  4814.3     .07       0
  4848.4     .12       0  5016.4     .05       0  5029.4     .12       0
  5060.1     .07       0  5631.1     .12       0
Bank Sta=5016.4,5029.4
XS Rating Curve= 0 ,0
Exp/Cntr=0.3,0.1

Type RM Length L Ch R = 1 ,6206    ,455,455,455
BEGIN DESCRIPTION:
ELM CREEK NORTH 10.0
END DESCRIPTION:
XS GIS Cut Line= 3
      2290175.03     13727624.97        2290525.       13727225.
      2290925.01     13726024.98
#Sta/Elev= 30
  4465.2  514.06  4602.3   508.6  4784.1  501.59  4918.4   497.6  4956.5  497.51
  4989.5  498.37  4993.3  496.91  4999.3  496.91  5007.2  494.31  5011.2  491.43
  5011.7  490.93  5024.3  491.43  5028.3     493  5038.4  495.01  5210.2  495.83
  5355.1  496.85    5608  500.57  5734.5  504.91  5755.6  506.69  5766.2  506.69
  5787.2  508.47  5851.6  511.71  5903.2  514.18  5987.5  520.45  6071.8  523.95
  6086.6  525.22  6145.6  528.17  6187.8   531.9    6215  532.78  6261.6  533.78
#Mann= 10 ,-1 , 0
  4465.2     .07       0  4602.3    .035       0  4956.5     .07       0
  5011.2     .05       0  5024.3     .07       0  5038.4     .12       0
  5210.2     .07       0  5851.6     .12       0  6086.6    .035       0
    6215     .05       0
Bank Sta=5011.2,5024.3
XS Rating Curve= 0 ,0
Exp/Cntr=0.3,0.1