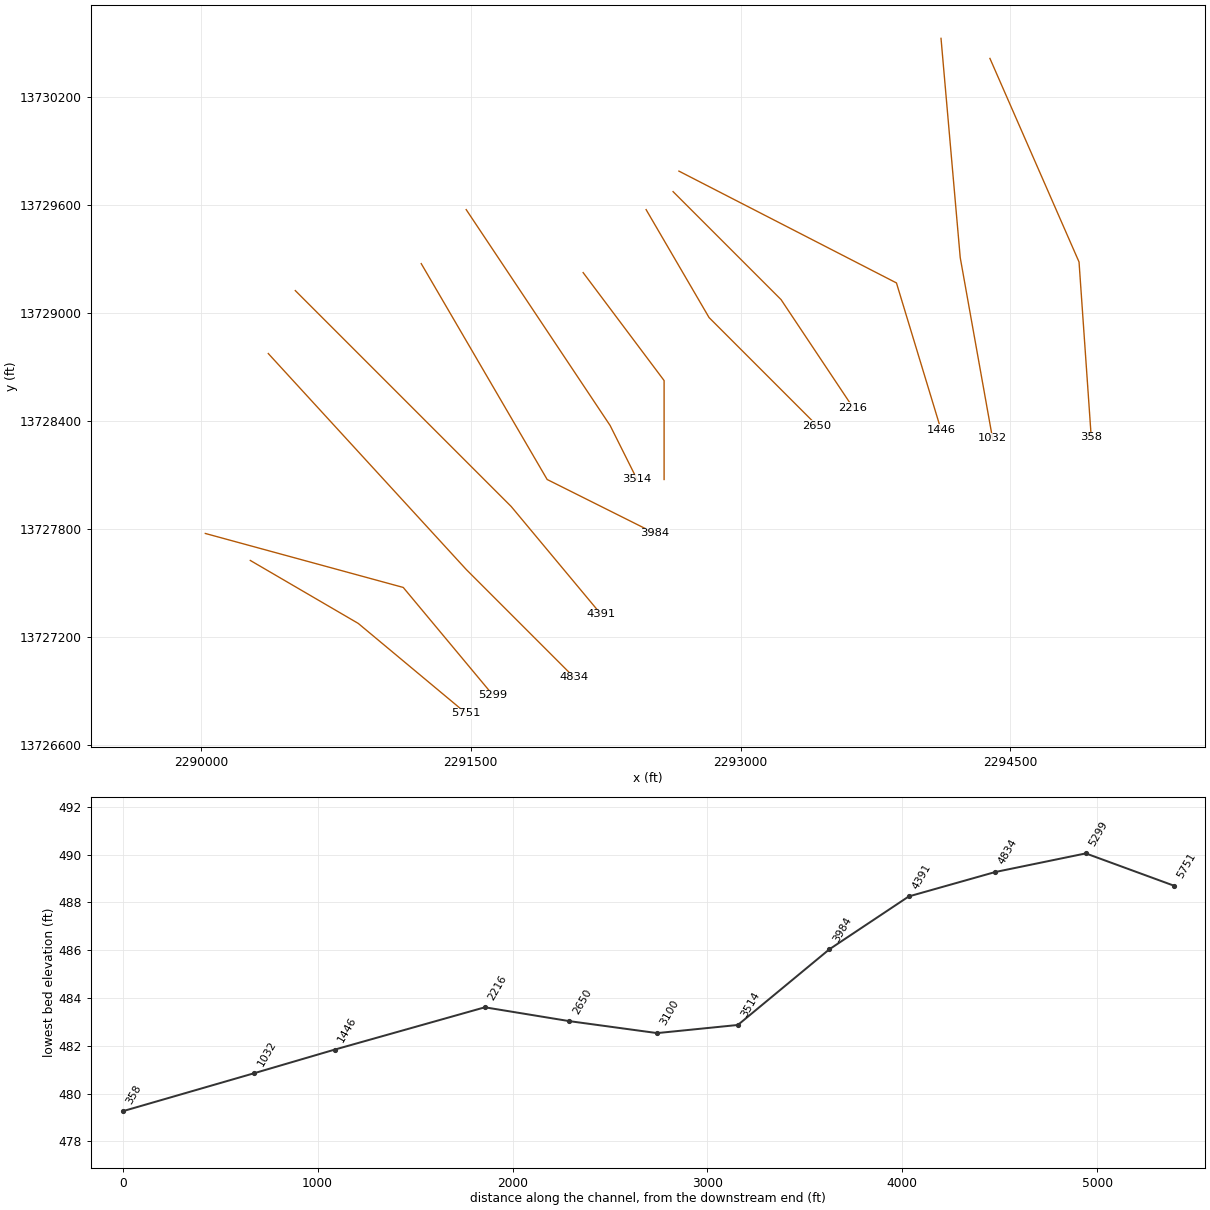
HEC-RAS study ELM CREEK NORTH.prj: ELM CREEK NORTH Base Level Engineering

--- ELM CREEK NORTH.g01 (geometry) --- (continued)

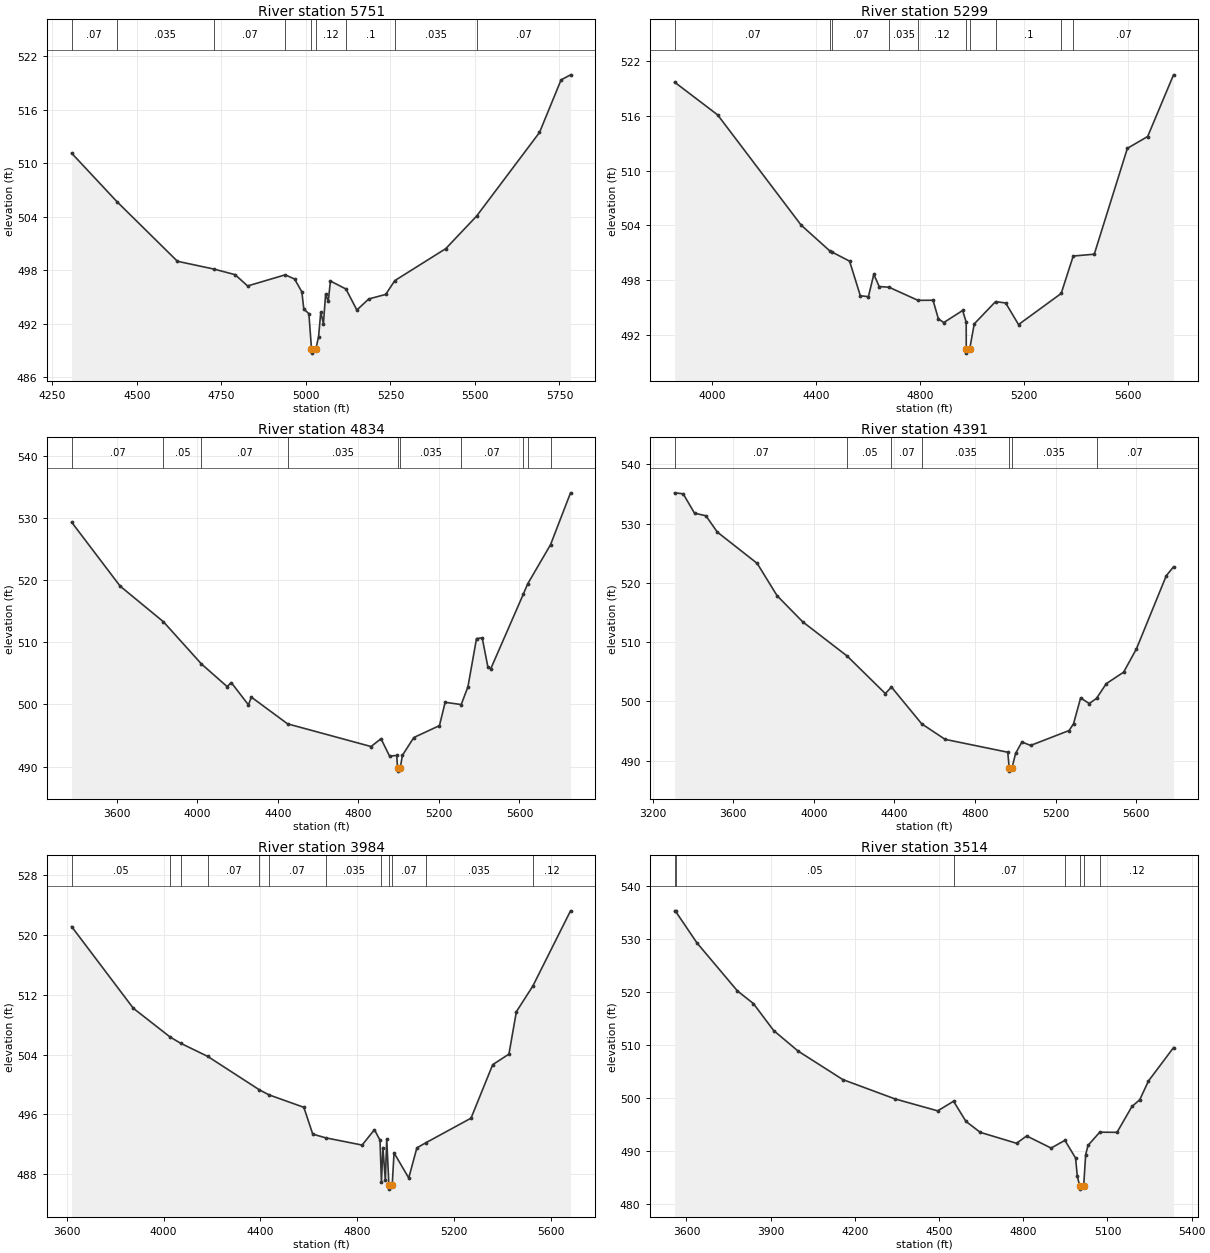
Type RM Length L Ch R = 1 ,5751    ,452,452,452
BEGIN DESCRIPTION:
ELM CREEK NORTH 9.0
END DESCRIPTION:
XS GIS Cut Line= 3
      2290274.97     13727625.02        2290875.       13727275.
      2291475.01     13726774.99
#Sta/Elev= 30
    4307  511.15  4441.2   505.7    4620  499.01  4727.4  498.14  4790.4  497.51
  4827.6  496.24  4938.8  497.49  4966.5  497.02    4988  495.58  4993.8  493.65
  5008.8  493.13  5016.5   489.2    5017   488.7  5029.7   489.2  5037.5  490.56
    5044   493.3  5051.8  492.02  5058.3   495.3  5066.1  494.54  5072.6  496.79
  5118.4   495.9  5150.7  493.54  5185.9  494.78    5236  495.29  5262.9  496.84
  5413.7  500.43    5505  504.09  5690.9  513.47  5754.7  519.37  5782.7  519.94
#Mann= 9 ,-1 , 0
    4307     .07       0  4441.2    .035       0  4727.4     .07       0
  4938.8     .12       0  5016.5     .05       0  5029.7     .12       0
  5118.4      .1       0  5262.9    .035       0    5505     .07       0
Bank Sta=5016.5,5029.7
XS Rating Curve= 0 ,0
Exp/Cntr=0.3,0.1

Type RM Length L Ch R = 1 ,5299    ,465,465,465
BEGIN DESCRIPTION:
ELM CREEK NORTH 8.0
END DESCRIPTION:
XS GIS Cut Line= 3
      2290024.98       13727775.        2291125.       13727475.
      2291624.99     13726875.01
#Sta/Elev= 30
  3855.5  519.66  4021.4  516.08  4342.7  504.04  4454.3  501.19  4461.4   501.1
  4529.3   500.1  4570.7  496.32  4601.8  496.22  4622.5  498.66  4643.3  497.33
  4681.2  497.25  4792.6  495.82  4850.6  495.83  4871.3  493.79    4892  493.39
  4964.6  494.71  4978.4  493.43  4978.6  490.55  4979.1  490.05    4992  490.55
  5009.4  493.25  5091.4  495.68  5130.4  495.53  5179.9  493.17  5344.1  496.57
  5390.5  500.66  5471.5  500.86    5599  512.43  5677.1  513.72  5776.7  520.46
#Mann= 10 ,-1 , 0
  3855.5     .07       0  4454.3    .035       0  4461.4     .07       0
  4681.2    .035       0  4792.6     .12       0  4978.6     .05       0
    4992     .12       0  5091.4      .1       0  5344.1    .035       0
  5390.5     .07       0
Bank Sta=4978.6,4992
XS Rating Curve= 0 ,0
Exp/Cntr=0.3,0.1

Type RM Length L Ch R = 1 ,4834    ,443,443,443
BEGIN DESCRIPTION:
ELM CREEK NORTH 7.0
END DESCRIPTION:
XS GIS Cut Line= 3
      2290374.97     13728775.03        2291475.       13727575.
      2292075.03     13726974.97
#Sta/Elev= 30
    3377  529.36  3617.8  519.06  3832.8  513.32  4021.3  506.53  4148.7  502.89
  4169.7  503.52  4254.8  499.94    4269  501.19  4449.2  496.88  4863.4  493.23
  4912.7  494.49  4955.3  491.69    4991  491.79  4994.8  489.77  4995.3  489.27
  5008.2  489.77  5019.1  491.82  5075.6  494.68  5202.9   496.6  5231.2  500.35
  5310.9  499.99  5344.3  502.85  5386.8  510.61    5415  510.74  5443.3  506.04
  5457.5  505.75  5618.8  517.74  5640.6  519.41  5754.4  525.74  5853.5  534.08
#Mann= 10 ,-1 , 0
    3377     .07       0  3832.8     .05       0  4021.3     .07       0
  4449.2    .035       0  4994.8    .035       0  5008.2    .035       0
  5310.9     .07       0  5618.8     .05       0  5640.6     .07       0
  5754.4     .05       0
Bank Sta=4994.8,5008.2
XS Rating Curve= 0 ,0
Exp/Cntr=0.3,0.1

Type RM Length L Ch R = 1 ,4391    ,407,407,407
BEGIN DESCRIPTION:
ELM CREEK NORTH 6.0
END DESCRIPTION:
XS GIS Cut Line= 3
      2290525.03     13729124.97        2291725.       13727925.
      2292224.98     13727325.03
#Sta/Elev= 30
    3308   535.2  3350.4  535.04  3406.9  531.77  3463.5  531.33  3520.1  528.58
  3718.1   523.3  3817.1  517.84  3944.3  513.44  4165.2  507.66  4354.5  501.34
  4385.1  502.43  4535.3  496.23  4651.5  493.61  4962.6  491.44    4970  488.75
  4970.5  488.25  4983.5  488.75  5001.5  491.23    5033  493.17    5076  492.58
  5267.3   495.1  5289.4  496.24  5324.6   500.6  5367.5  499.65  5403.6  500.53
  5452.1  503.01  5538.1  504.94  5601.8  508.88  5750.2  521.23    5786  522.72
#Mann= 7 ,-1 , 0
    3308     .07       0  4165.2     .05       0  4385.1     .07       0
  4535.3    .035       0    4970    .035       0  4983.5    .035       0
  5403.6     .07       0
Bank Sta=4970,4983.5
XS Rating Curve= 0 ,0
Exp/Cntr=0.3,0.1

Type RM Length L Ch R = 1 ,3984    ,470,470,470
BEGIN DESCRIPTION:
ELM CREEK NORTH 5.0
END DESCRIPTION:
XS GIS Cut Line= 3
      2291225.01     13729274.98        2291925.       13728075.
      2292524.97     13727775.02
#Sta/Elev= 30
  3620.3  521.08    3875  510.18  4027.4  506.33  4070.4  505.51  4182.4  503.75
  4395.7  499.29  4435.3  498.62  4579.1  496.96  4615.9  493.38    4669  492.89
  4819.7  491.92  4870.6  493.97  4893.7  492.57  4899.5  486.99  4905.7  491.58
  4915.7  487.23  4921.4  492.74  4930.4  486.54  4930.9  486.04  4943.9  486.54
  4951.6  490.88  5012.3  487.53  5045.9  491.55  5081.9  492.21  5269.5  495.51
  5358.9  502.65    5426  504.06  5456.7  509.72  5524.6  513.14  5680.3  523.18
#Mann= 12 ,-1 , 0
  3620.3     .05       0  4027.4     .07       0  4070.4     .05       0
  4182.4     .07       0  4395.7     .05       0  4435.3     .07       0
    4669    .035       0  4899.5     .07       0  4930.4     .05       0
  4943.9     .07       0  5081.9    .035       0  5524.6     .12       0
Bank Sta=4930.4,4943.9
XS Rating Curve= 0 ,0
Exp/Cntr=0.3,0.1

Type RM Length L Ch R = 1 ,3514    ,414,414,414
BEGIN DESCRIPTION:
ELM CREEK NORTH 4.0
END DESCRIPTION:
XS GIS Cut Line= 3
      2291475.02     13729574.96        2292275.       13728375.
      2292425.01     13728074.99
#Sta/Elev= 30
  3557.8  535.31  3561.4  535.21  3637.4  529.27  3781.6  520.22  3838.7  517.83
  3910.8  512.75  3997.9  508.88  4157.2  503.51  4343.5  499.86  4495.2  497.62
  4551.7  499.43  4595.9  495.63  4646.9  493.57  4776.1  491.51  4812.2  492.89
  4899.3  490.61  4948.4  492.06  4986.5  488.72  4992.5  485.34  5001.5  483.37
    5002  482.87  5015.2  483.37  5022.3  489.33  5030.7  491.11  5072.6   493.6
  5134.1  493.57  5187.2  498.44  5215.2  499.72  5245.9  503.23  5335.4  509.54
#Mann= 7 ,-1 , 0
  3557.8     .07       0  3561.4     .05       0  4551.7     .07       0
  4948.4    .035       0  5001.5    .035       0  5015.2    .035       0
  5072.6     .12       0
Bank Sta=5001.5,5015.2
XS Rating Curve= 0 ,0
Exp/Cntr=0.3,0.1

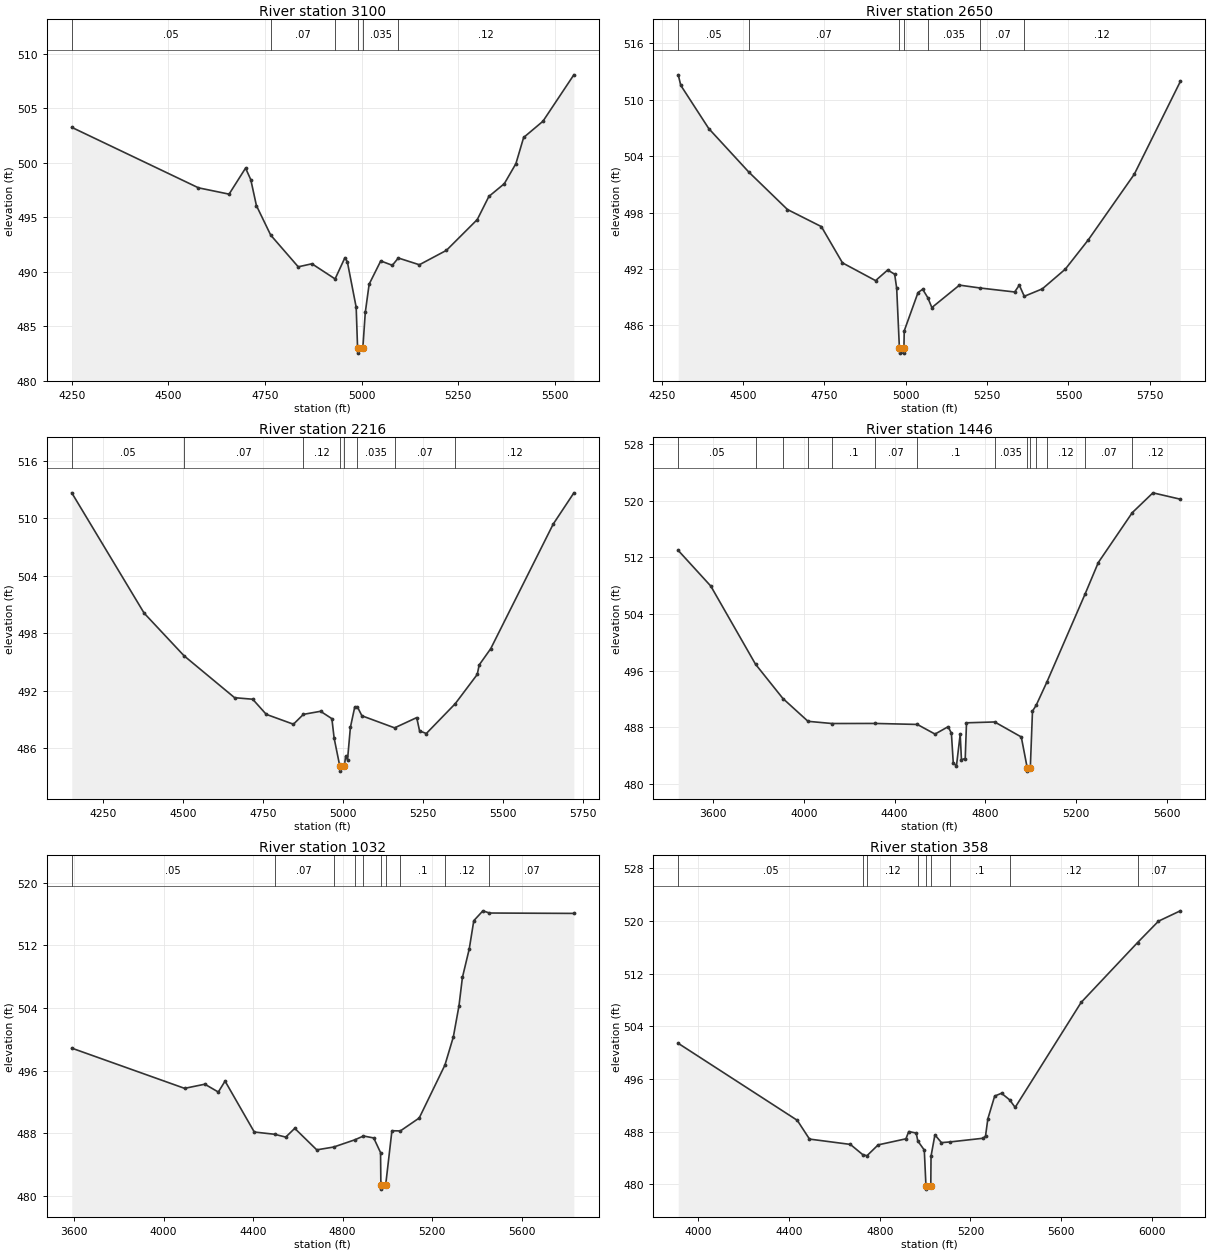
Type RM Length L Ch R = 1 ,3100    ,450,450,450
BEGIN DESCRIPTION:
ELM CREEK NORTH 3.0
END DESCRIPTION:
XS GIS Cut Line= 3
      2292125.02     13729224.98        2292575.       13728625.
        2292575.     13728074.97
#Sta/Elev= 30
  4249.7  503.25  4577.8   497.7    4657  497.12  4699.7  499.51  4713.2  498.45
  4727.8  496.07  4764.8  493.36  4836.1  490.45  4871.5  490.73  4931.5  489.34
    4957  491.29  4963.2  490.92  4986.1  486.74  4989.7  483.03  4990.2  482.53
  5003.4  483.03  5009.7  486.27  5019.7  488.86  5049.7  490.99  5079.7  490.59
  5095.2  491.26  5149.7  490.64  5219.7  491.96  5299.7  494.79  5329.7  496.91
  5369.7  498.08  5399.7  499.92  5419.7  502.32  5469.7  503.81  5549.7  508.07
#Mann= 6 ,-1 , 0
  4249.7     .05       0  4764.8     .07       0  4931.5    .035       0
  4989.7    .035       0  5003.4    .035       0  5095.2     .12       0
Bank Sta=4989.7,5003.4
XS Rating Curve= 0 ,0
Exp/Cntr=0.3,0.1

Type RM Length L Ch R = 1 ,2650    ,434,434,434
BEGIN DESCRIPTION:
ELM CREEK NORTH 2.0
END DESCRIPTION:
XS GIS Cut Line= 3
      2292475.01     13729574.98        2292825.       13728975.
      2293424.98     13728375.02
#Sta/Elev= 30
  4300.6  512.66  4308.4  511.54  4394.4  506.94  4517.7   502.3  4636.3  498.32
  4740.5   496.5  4805.4  492.64  4907.1  490.75  4944.3  491.88  4965.8  491.43
    4972  489.93  4980.4  483.53  4980.9  483.03  4993.7  483.03  4994.2  483.53
  4995.2   485.4  5037.6  489.48  5051.8  489.83  5067.5  488.94  5080.1  487.88
  5164.9  490.27  5229.3  489.96  5334.6  489.54  5348.8  490.27  5364.2  489.08
  5419.5  489.87  5490.2  491.97  5560.9  495.09  5702.3  502.08  5843.7  511.95
#Mann= 7 ,-1 , 0
  4300.6     .05       0  4517.7     .07       0  4980.4     .05       0
  4994.2     .07       0  5067.5    .035       0  5229.3     .07       0
  5364.2     .12       0
Bank Sta=4980.4,4994.2
XS Rating Curve= 0 ,0
Exp/Cntr=0.3,0.1

Type RM Length L Ch R = 1 ,2216    ,770,770,770
BEGIN DESCRIPTION:
ELM CREEK NORTH 1.0
END DESCRIPTION:
XS GIS Cut Line= 3
      2292624.98     13729675.02        2293225.       13729075.
      2293625.02     13728474.97
#Sta/Elev= 30
  4151.4  512.68  4377.7  500.11  4502.4  495.66  4660.5  491.28  4717.1  491.12
  4759.5  489.54  4844.4  488.51  4875.6  489.54  4929.2  489.86  4964.6  489.09
  4971.7  487.05  4989.5  484.11    4990  483.61  5003.4  484.11  5007.5  485.15
  5013.5  484.79  5022.5  488.18    5036  490.29  5044.6  490.31  5058.5  489.39
  5160.7  488.13  5229.8   489.2  5238.8  487.81  5259.9  487.54  5350.2  490.65
  5419.1  493.71  5425.1   494.7  5461.2   496.4  5656.5  509.41  5721.1  512.67
#Mann= 8 ,-1 , 0
  4151.4     .05       0  4502.4     .07       0  4875.6     .12       0
  4989.5     .05       0  5003.4     .12       0  5044.6    .035       0
  5160.7     .07       0  5350.2     .12       0
Bank Sta=4989.5,5003.4
XS Rating Curve= 0 ,0
Exp/Cntr=0.3,0.1

Type RM Length L Ch R = 1 ,1446    ,414,414,414
BEGIN DESCRIPTION:
X19142
END DESCRIPTION:
XS GIS Cut Line= 3
      2292657.45     13729789.06      2293866.54     13729167.51
      2294114.18     13728351.77
#Sta/Elev= 30
    3447  512.99  3590.4  507.96  3787.5  496.93  3908.2  492.09  4018.8  488.87
  4124.7  488.56  4314.4  488.57  4500.3  488.43  4578.3  487.07  4636.1  488.11
  4650.5  487.19  4658.6  483.03  4672.6  482.54  4689.2  487.03  4694.8  483.45
  4711.4  483.62    4717  488.66  4841.2  488.78  4958.4  486.66  4984.3  482.34
  4984.8  481.84  4998.2  482.34  5007.7  490.31  5023.9  491.13  5071.1  494.41
  5239.1  506.81  5297.7  511.28  5447.3  518.32  5538.4  521.12    5659  520.22
#Mann= 14 ,-1 , 0
    3447     .05       0  3787.5    .035       0  3908.2     .07       0
  4018.8     .12       0  4124.7      .1       0  4314.4     .07       0
  4500.3      .1       0  4841.2    .035       0  4984.3    .035       0
  4998.2    .035       0  5023.9     .07       0  5071.1     .12       0
  5239.1     .07       0  5447.3     .12       0
Bank Sta=4984.3,4998.2
XS Rating Curve= 0 ,0
Exp/Cntr=0.3,0.1

Type RM Length L Ch R = 1 ,1032    ,674,674,674
BEGIN DESCRIPTION:
X19141
END DESCRIPTION:
XS GIS Cut Line= 3
      2294114.18     13730527.12      2294221.01     13729308.33
      2294400.33     13728305.09
#Sta/Elev= 30
  3590.2  498.87  4094.2  493.73  4184.6  494.26  4244.8  493.26  4274.9  494.66
  4405.4  488.15  4496.3  487.86    4546   487.5  4586.1  488.62  4684.5  485.87
    4760  486.23  4855.1  487.16  4893.2  487.64  4938.9  487.39  4969.4  485.52
  4970.9  481.35  4971.4  480.85  4992.2  481.35  5020.2  488.31    5058  488.29
  5142.1  489.94    5257  496.71  5294.5   500.3  5319.7  504.27  5335.1  507.91
  5365.6  511.55  5385.9  515.16  5426.6  516.42  5455.9  516.14  5832.8  516.09
#Mann= 10 ,-1 , 0
  3590.2     .05       0  4496.3     .07       0    4760     .12       0
  4855.1      .1       0  4893.2    .035       0  4970.9    .035       0
  4992.2    .035       0    5058      .1       0    5257     .12       0
  5455.9     .07       0
Bank Sta=4970.9,4992.2
XS Rating Curve= 0 ,0
Exp/Cntr=0.3,0.1

Type RM Length L Ch R = 1 ,358     ,0,0,0
BEGIN DESCRIPTION:
X19140
END DESCRIPTION:
XS GIS Cut Line= 3
      2294386.09     13730415.46      2294881.39     13729284.05
       2294949.3     13728308.98
#Sta/Elev= 30
  3912.2   501.4  4436.7  489.71  4490.6  486.86  4670.7  486.05  4725.2   484.5
  4743.8  484.33  4793.1  485.98  4915.5   486.9  4927.9     488  4960.7  487.78
  4968.1  486.56  4996.5  485.19  5003.8  479.76  5004.3  479.26  5025.1  479.76
  5026.2  484.26  5043.3   487.5  5072.1  486.32  5111.2  486.43  5256.6  486.99
  5266.4  487.34  5276.6  489.94  5306.7  493.39  5336.8  493.82  5372.8  492.81
  5396.9  491.67  5687.6  507.61  5936.3   516.7  6028.5  519.95  6124.7  521.52
#Mann= 9 ,-1 , 0
  3912.2     .05       0  4725.2     .07       0  4743.8     .12       0
  4968.1    .035       0  5003.8    .035       0  5025.1    .035       0
  5111.2      .1       0  5372.8     .12       0  5936.3     .07       0
Bank Sta=5003.8,5025.1
XS Rating Curve= 0 ,0
Exp/Cntr=0.3,0.1

Chan Stop Cuts=-1
Use User Specified Reach Order=0
Composite Channel Slope=5