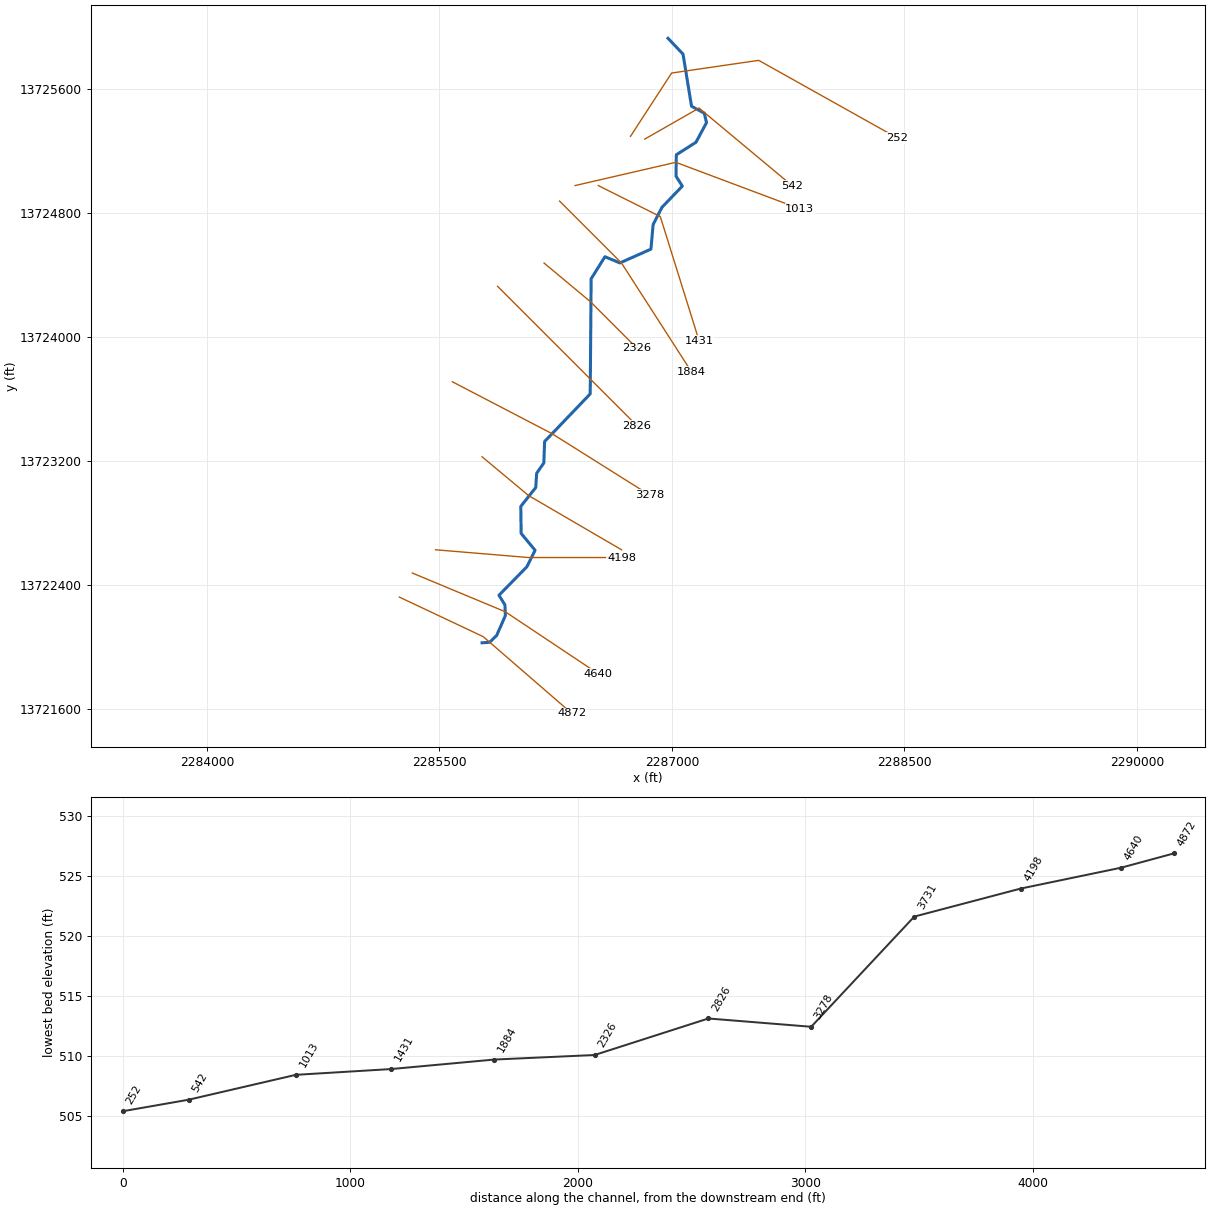
--- ELM TRIBUTARY 1.prj (project) ---

Proj Title=ELM TRIBUTARY 1 Base Level Engineering
Current Plan=p01
Default Exp/Contr=0.3,0.1
English Units
Geom File=g01
Flow File=f01
Plan File=p01
BEGIN DESCRIPTION:
ELM TRIBUTARY 1
END DESCRIPTION:

--- ELM TRIBUTARY 1.p01 (plan) ---

Plan Title=Multiple Run
Short Identifier=Multiple
Geom File=g01
Flow File=f01
Subcritical Flow
K Sum by GR= 0
Std Step Tol= 0.01
Critical Tol= 0.01
Num of Std Step Trials= 20
Max Error Tol= 0.3
Flow Tol Ratio= 0.001
Split Flow NTrial= 30
Split Flow Tol= 0.02
Split Flow Ratio= 0.02
Log Output Level= 0
Friction Slope Method= 1
Unsteady Friction Slope Method= 2
Unsteady Bridges Friction Slope Method= 1
Parabolic Critical Depth
Global Vel Dist=  1 , 1 , 1
Global Log Level= 0
CheckData=True
Encroach Param= -1, 0, 0, 0
BEGIN DESCRIPTION:
Multiple Run
END DESCRIPTION:

--- ELM TRIBUTARY 1.f01 (steady flow) ---

Flow Title=Multiple
Number of Profiles=7
Profile Names=10-year,25-year,50-year,1pct_min,100-year,1pct_plu,500-year
River Rch & RM= ELM TRIBUTARY 1,Reach-1,4872
     730    1182    1590    1035    2064    4119    3444
Boundary for River Rch & Prof#=ELM TRIBUTARY 1,Reach-1,1
Up Type=0
Dn Type=3
Dn Slope=0.005
Boundary for River Rch & Prof#=ELM TRIBUTARY 1,Reach-1,2
Up Type=0
Dn Type=3
Dn Slope=0.005
Boundary for River Rch & Prof#=ELM TRIBUTARY 1,Reach-1,3
Up Type=0
Dn Type=3
Dn Slope=0.005
Boundary for River Rch & Prof#=ELM TRIBUTARY 1,Reach-1,4
Up Type=0
Dn Type=3
Dn Slope=0.005
Boundary for River Rch & Prof#=ELM TRIBUTARY 1,Reach-1,5
Up Type=0
Dn Type=3
Dn Slope=0.005
Boundary for River Rch & Prof#=ELM TRIBUTARY 1,Reach-1,6
Up Type=0
Dn Type=3
Dn Slope=0.005
Boundary for River Rch & Prof#=ELM TRIBUTARY 1,Reach-1,7
Up Type=0
Dn Type=3
Dn Slope=0.005

--- ELM TRIBUTARY 1.g01 (geometry) ---

Geom Title=Existing Conditions

River Reach=ELM TRIBUTARY 1,Reach-1
Reach XY= 30
      2285775.00     13722025.00      2285823.97     13722028.14
      2285869.32     13722072.48      2285925.40     13722200.00
      2285922.63     13722269.11      2285884.13     13722331.74
      2286064.25     13722515.32      2286117.16     13722621.77
      2286027.07     13722730.85      2286024.96     13722905.01
      2286121.38     13723026.50      2286127.36     13723119.02
      2286173.77     13723185.51      2286178.54     13723323.53
      2286472.94     13723630.85      2286478.75     13724373.45
      2286567.98     13724515.97      2286664.29     13724475.82
      2286864.67     13724564.83      2286878.76     13724723.44
      2286935.76     13724834.68      2287067.21     13724971.58
      2287026.38     13725035.44      2287028.44     13725173.75
      2287155.37     13725254.53      2287223.25     13725381.16
      2287208.85     13725442.01      2287126.66     13725486.84
      2287071.51     13725823.55      2286975.00     13725925.00

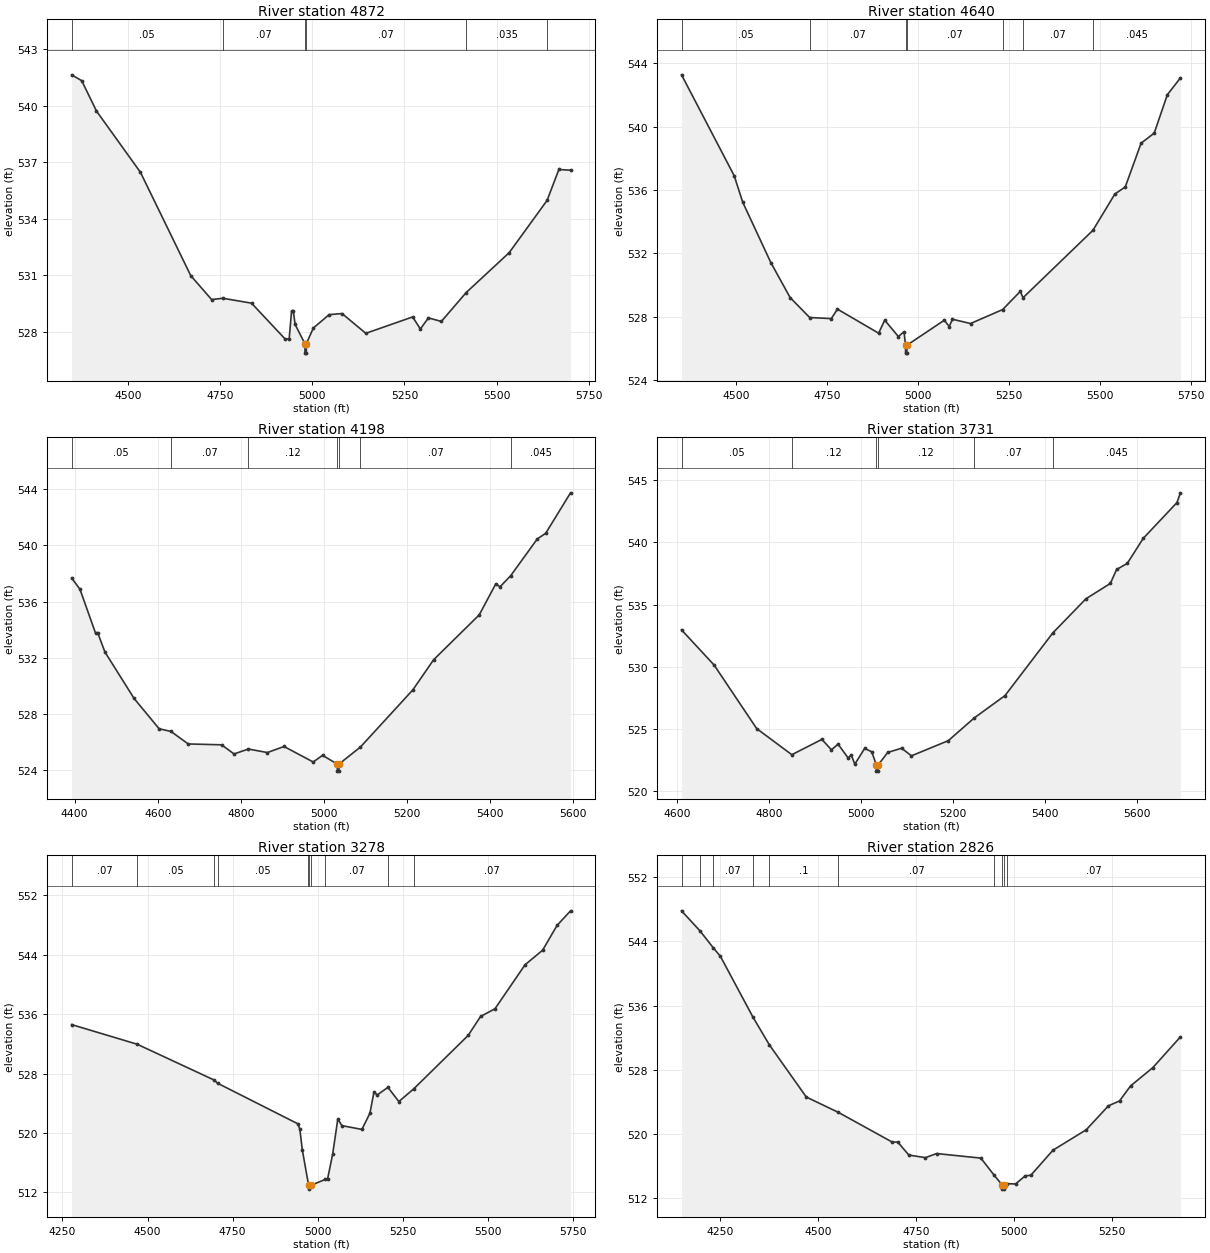
Type RM Length L Ch R = 1,4872,232,232,232
BEGIN DESCRIPTION:
X19154
END DESCRIPTION:
XS GIS Cut Line= 3
      2285241.17     13722319.80      2285782.61     13722064.40
      2286354.11     13721569.44
#Sta/Elev= 30
  4346.2  541.64  4373.6  541.33  4413.7  539.72  4533.1  536.47  4669.7  530.99
  4726.4  529.72  4756.6  529.79  4834.7  529.53  4925.4  527.64  4936.9  527.63
  4943.4  529.10  4948.2  529.10  4953.1  528.40  4979.6  527.38  4979.9  526.88
  4983.4  526.88  4983.6  527.38  5002.5  528.21  5045.2  528.92  5080.4  528.98
  5145.0  527.93  5272.2  528.80  5293.1  528.16  5315.0  528.75  5350.1  528.56
  5417.4  530.09  5534.4  532.21  5637.2  534.98  5669.2  536.62  5700.9  536.58
#Mann=6,-1,0
  4346.2    0.05       0  4756.6    0.07       0  4979.6    0.05       0
  4983.6    0.07       0  5417.4   0.035       0  5637.2   0.045       0
Bank Sta=4979.6,4983.6
Exp/Cntr=0.3,0.1

Type RM Length L Ch R = 1,4640,442,442,442
BEGIN DESCRIPTION:
ELM TRIBUTARY 1 10.0
END DESCRIPTION:
XS GIS Cut Line= 3
      2285325.02     13722474.99      2285925.00     13722225.00
      2286525.01     13721824.99
#Sta/Elev= 30
  4349.1  543.27  4493.7  536.90  4517.5  535.21  4594.5  531.41  4647.5  529.20
  4701.2  527.94  4760.7  527.87  4777.5  528.47  4890.7  526.95  4907.5  527.77
  4944.9  526.74  4960.6  527.04  4964.6  526.19  4964.8  525.69  4968.3  525.69
  4968.6  526.19  5071.2  527.77  5084.7  527.37  5093.7  527.83  5143.3  527.56
  5231.4  528.44  5280.0  529.59  5287.6  529.19  5479.7  533.45  5539.9  535.74
  5568.5  536.19  5612.0  538.95  5648.1  539.59  5684.1  542.01  5720.2  543.08
#Mann=7,-1,0
  4349.1    0.05       0  4701.2    0.07       0  4964.6    0.05       0
  4968.6    0.07       0  5231.4    0.12       0  5287.6    0.07       0
  5479.7   0.045       0
Bank Sta=4964.6,4968.6
Exp/Cntr=0.3,0.1

Type RM Length L Ch R = 1,4198,467,467,467
BEGIN DESCRIPTION:
ELM TRIBUTARY 1 9.0
END DESCRIPTION:
XS GIS Cut Line= 3
      2285474.97     13722625.00      2286075.00     13722575.00
      2286674.99     13722575.00
#Sta/Elev= 30
  4392.6  537.67  4412.7  536.87  4450.3  533.75  4455.3  533.79  4472.9  532.41
  4543.2  529.11  4603.4  526.96  4631.9  526.77  4673.6  525.88  4753.9  525.82
  4784.0  525.17  4818.5  525.52  4864.3  525.27  4904.4  525.70  4974.6  524.60
  4997.2  525.07  5032.7  524.45  5033.0  523.95  5036.5  523.95  5036.7  524.45
  5088.4  525.66  5214.7  529.72  5264.7  531.86  5374.7  535.05  5414.7  537.26
  5424.7  537.04  5450.4  537.83  5514.7  540.45  5534.7  540.84  5594.7  543.72
#Mann=7,-1,0
  4392.6    0.05       0  4631.9    0.07       0  4818.5    0.12       0
  5032.7    0.05       0  5036.7    0.12       0  5088.4    0.07       0
  5450.4   0.045       0
Bank Sta=5032.7,5036.7
Exp/Cntr=0.3,0.1

Type RM Length L Ch R = 1,3731,453,453,453
BEGIN DESCRIPTION:
ELM TRIBUTARY 1 8.0
END DESCRIPTION:
XS GIS Cut Line= 3
      2285775.00     13723225.00      2286075.00     13722975.00
      2286674.97     13722625.02
#Sta/Elev= 30
  4609.5  532.97  4680.4  530.14  4772.9  525.04  4849.4  522.94  4914.7  524.17
  4935.6  523.33  4949.9  523.79  4972.0  522.67  4978.5  522.93  4986.3  522.18
  5007.9  523.45  5023.2  523.17  5033.2  522.12  5033.4  521.62  5036.9  521.62
  5037.2  522.12  5057.9  523.12  5088.1  523.46  5109.6  522.85  5189.8  524.07
  5246.0  525.89  5313.0  527.69  5416.9  532.72  5489.1  535.47  5542.1  536.70
  5555.7  537.82  5578.9  538.31  5613.6  540.32  5686.8  543.19  5694.6  543.98
#Mann=6,-1,0
  4609.5    0.05       0  4849.4    0.12       0  5033.2    0.05       0
  5037.2    0.12       0  5246.0    0.07       0  5416.9   0.045       0
Bank Sta=5033.2,5037.2
Exp/Cntr=0.3,0.1

Type RM Length L Ch R = 1,3278,452,452,452
BEGIN DESCRIPTION:
ELM TRIBUTARY 1 7.0
END DESCRIPTION:
XS GIS Cut Line= 3
      2285583.42     13723709.12      2286225.00     13723375.00
      2286854.19     13722979.38
#Sta/Elev= 30
  4276.9  534.58  4469.5  531.94  4695.0  527.14  4706.5  526.68  4942.2  521.23
  4947.8  520.50  4955.2  517.68  4972.8  513.16  4975.7  512.95  4976.0  512.45
  4979.7  512.95  5022.2  513.75  5029.1  513.77  5044.4  517.19  5059.3  521.86
  5071.5  520.99  5130.2  520.48  5153.8  522.66  5165.7  525.53  5175.1  525.11
  5206.7  526.14  5238.8  524.23  5282.6  525.94  5442.5  533.12  5479.0  535.67
  5521.4  536.71  5609.7  542.62  5661.5  544.59  5703.9  547.92  5743.5  549.88
#Mann=10,-1,0
  4276.9    0.07       0  4469.5    0.05       0  4695.0    0.07       0
  4706.5    0.05       0  4972.8    0.12       0  4975.7    0.05       0
  4979.7    0.12       0  5022.2    0.07       0  5206.7    0.05       0
  5282.6    0.07       0
Bank Sta=4975.7,4979.7
Exp/Cntr=0.3,0.1

Type RM Length L Ch R = 1,2826,500,500,500
BEGIN DESCRIPTION:
ELM TRIBUTARY 1 6.0
END DESCRIPTION:
XS GIS Cut Line= 3
      2285874.98     13724325.02      2286475.00     13723725.00
      2286774.98     13723425.02
#Sta/Elev= 30
  4151.3  547.79  4198.6  545.28  4231.9  543.21  4250.3  542.14  4333.8  534.53
  4375.4  531.10  4469.5  524.61  4551.6  522.69  4688.7  519.00  4702.9  519.00
  4731.2  517.38  4773.6  517.06  4801.9  517.57  4915.0  517.00  4949.3  514.84
  4969.6  513.64  4969.8  513.14  4973.3  513.14  4973.6  513.64  4982.3  513.82
  5003.4  513.78  5028.1  514.80  5042.3  514.86  5098.9  517.99  5183.7  520.53
  5240.3  523.51  5268.6  524.12  5296.8  525.99  5353.4  528.26  5424.1  532.10
#Mann=10,-1,0
  4151.3    0.07       0  4198.6   0.035       0  4231.9    0.07       0
  4333.8   0.035       0  4375.4     0.1       0  4551.6    0.07       0
  4949.3    0.12       0  4969.6    0.05       0  4973.6    0.12       0
  4982.3    0.07       0
Bank Sta=4969.6,4973.6
Exp/Cntr=0.3,0.1

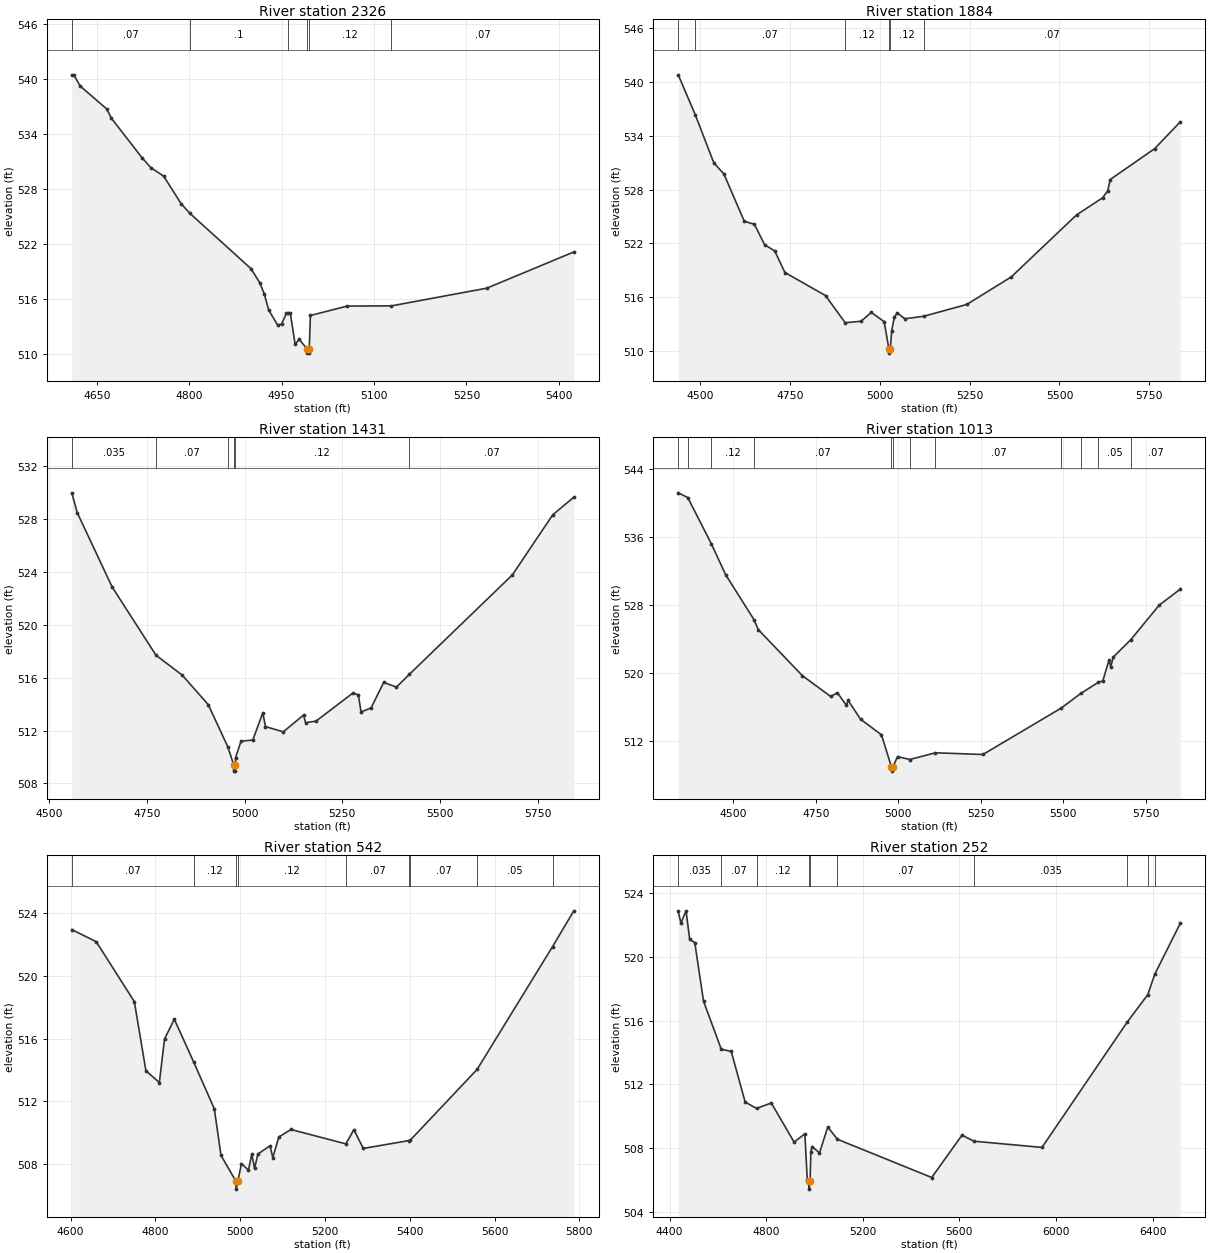
Type RM Length L Ch R = 1,2326,442,442,442
BEGIN DESCRIPTION:
ELM TRIBUTARY 1 5.0
END DESCRIPTION:
XS GIS Cut Line= 3
      2286175.00     13724475.00      2286475.00     13724225.00
      2286775.01     13723924.99
#Sta/Elev= 30
  4609.5  540.49  4612.8  540.49  4623.2  539.26  4666.1  536.77  4673.9  535.74
  4723.4  531.45  4737.7  530.36  4758.6  529.43  4787.2  526.40  4800.9  525.38
  4900.4  519.32  4914.8  517.76  4921.9  516.56  4929.1  514.80  4943.4  513.19
  4949.9  513.25  4957.7  514.44  4961.1  514.45  4964.2  514.45  4972.0  511.05
  4978.5  511.61  4990.9  510.60  4991.1  510.10  4994.6  510.10  4994.9  510.60
  4996.8  514.21  5056.6  515.24  5128.3  515.26  5282.9  517.19  5424.3  521.15
#Mann=6,-1,0
  4609.5    0.07       0  4800.9     0.1       0  4961.1    0.12       0
  4990.9    0.05       0  4994.9    0.12       0  5128.3    0.07       0
Bank Sta=4990.9,4994.9
Exp/Cntr=0.3,0.1

Type RM Length L Ch R = 1,1884,453,453,453
BEGIN DESCRIPTION:
ELM TRIBUTARY 1 4.0
END DESCRIPTION:
XS GIS Cut Line= 3
      2286274.99     13724875.01      2286675.00     13724475.00
      2287125.02     13723774.97
#Sta/Elev= 30
  4438.5  540.82  4486.3  536.32  4537.5  530.99  4565.8  529.73  4622.4  524.45
  4650.6  524.12  4678.9  521.84  4707.2  521.14  4735.5  518.73  4848.6  516.15
  4903.2  513.12  4947.6  513.28  4975.9  514.27  5011.8  513.24  5025.0  510.22
  5025.2  509.72  5029.0  510.22  5032.9  512.23  5039.9  513.71  5048.1  514.22
  5069.3  513.56  5122.1  513.84  5242.0  515.16  5365.8  518.24  5547.4  525.16
  5620.1  527.08  5634.3  527.85  5641.2  529.12  5765.0  532.57  5836.4  535.57
#Mann=6,-1,0
  4438.5     0.1       0  4486.3    0.07       0  4903.2    0.12       0
  5025.0    0.05       0  5029.0    0.12       0  5122.1    0.07       0
Bank Sta=5025,5029
Exp/Cntr=0.3,0.1

Type RM Length L Ch R = 1,1431,418,418,418
BEGIN DESCRIPTION:
ELM TRIBUTARY 1 3.0
END DESCRIPTION:
XS GIS Cut Line= 3
      2286525.01     13724974.99      2286925.00     13724775.00
      2287175.01     13723974.96
#Sta/Elev= 30
  4557.4  529.97  4571.4  528.47  4660.8  522.85  4773.1  517.69  4839.7  516.20
  4906.8  513.96  4957.0  510.76  4971.7  509.43  4972.0  508.93  4975.8  508.93
  4976.1  509.43  4976.7  509.94  4990.6  511.19  5020.8  511.28  5046.5  513.34
  5053.3  512.30  5098.9  511.90  5150.8  513.17  5156.0  512.59  5182.7  512.71
  5277.0  514.83  5291.1  514.70  5298.0  513.40  5323.6  513.71  5356.1  515.64
  5388.6  515.28  5421.7  516.25  5685.6  523.77  5788.8  528.31  5842.8  529.64
#Mann=6,-1,0
  4557.4   0.035       0  4773.1    0.07       0  4957.0    0.12       0
  4971.7    0.05       0  4976.1    0.12       0  5421.7    0.07       0
Bank Sta=4971.7,4976.1
Exp/Cntr=0.3,0.1

Type RM Length L Ch R = 1,1013,471,471,471
BEGIN DESCRIPTION:
ELM TRIBUTARY 1 2.0
END DESCRIPTION:
XS GIS Cut Line= 3
      2286374.96     13724974.99      2287025.00     13725125.00
      2287824.97     13724825.01
#Sta/Elev= 30
  4333.4  541.25  4362.3  540.69  4433.5  535.26  4477.1  531.60  4563.0  526.30
  4576.3  525.11  4709.7  519.70  4795.3  517.25  4815.8  517.68  4843.2  516.20
  4848.3  516.78  4885.9  514.57  4949.2  512.73  4979.5  508.95  4979.8  508.45
  4983.9  508.95  4998.0  510.16  5035.2  509.82  5112.9  510.61  5256.8  510.41
  5493.9  515.88  5553.8  517.62  5606.2  518.91  5620.0  519.08  5638.7  521.52
  5644.0  520.77  5652.0  521.90  5704.6  523.93  5790.8  528.01  5854.9  529.90
#Mann=12,-1,0
  4333.4     0.1       0  4362.3   0.035       0  4433.5    0.12       0
  4563.0    0.07       0  4979.5    0.05       0  4983.9    0.07       0
  5035.2    0.12       0  5112.9    0.07       0  5493.9    0.05       0
  5553.8    0.07       0  5606.2    0.05       0  5704.6    0.07       0
Bank Sta=4979.5,4983.9
Exp/Cntr=0.3,0.1

Type RM Length L Ch R = 1,542,290,290,290
BEGIN DESCRIPTION:
ELM TRIBUTARY 1 1.0
END DESCRIPTION:
XS GIS Cut Line= 3
      2286824.99     13725274.99      2287175.00     13725475.00
      2287775.03     13724974.97
#Sta/Elev= 30
  4602.9  522.96  4660.5  522.19  4750.5  518.36  4777.8  513.94  4809.5  513.19
  4821.7  515.98  4844.8  517.23  4890.8  514.48  4939.1  511.51  4954.9  508.53
  4990.2  506.88  4990.5  506.38  4994.6  506.88  5003.2  508.01  5019.7  507.59
  5027.5  508.62  5034.0  507.70  5041.8  508.62  5070.5  509.15  5077.0  508.39
  5091.3  509.71  5119.9  510.19  5249.4  509.27  5268.3  510.18  5290.5  508.98
  5397.9  509.48  5401.7  509.52  5559.0  514.03  5737.0  521.88  5787.1  524.16
#Mann=9,-1,0
  4602.9    0.07       0  4890.8    0.12       0  4990.2    0.05       0
  4994.6    0.12       0  5249.4    0.07       0  5397.9    0.05       0
  5401.7    0.07       0  5559.0    0.05       0  5737.0    0.07       0
Bank Sta=4990.2,4994.6
Exp/Cntr=0.3,0.1

Type RM Length L Ch R = 1,252,0,0,0
BEGIN DESCRIPTION:
X19153
END DESCRIPTION:
XS GIS Cut Line= 4
      2286732.68     13725292.56      2286998.28     13725701.18
      2287560.14     13725782.91      2288454.00     13725282.35
#Sta/Elev= 30
  4435.5  522.86  4446.7  522.13  4467.8  522.90  4482.9  521.11  4504.0  520.91
  4540.2  517.23  4613.7  514.21  4654.9  514.07  4712.7  510.89  4759.7  510.49
  4821.0  510.83  4915.5  508.37  4960.0  508.90  4970.1  505.98  4977.4  505.92
  4977.7  505.42  4981.8  505.92  4984.7  507.78  4990.3  508.09  5020.6  507.69
  5054.8  509.32  5095.0  508.55  5485.4  506.15  5610.8  508.81  5660.4  508.43
  5942.2  508.04  6294.6  515.90  6380.6  517.64  6409.3  518.92  6515.1  522.12
#Mann=10,-1,0
  4435.5   0.035       0  4613.7    0.07       0  4759.7    0.12       0
  4977.4    0.05       0  4981.8    0.12       0  5095.0    0.07       0
  5660.4   0.035       0  6294.6    0.05       0  6380.6   0.035       0
  6409.3    0.05       0
Bank Sta=4977.4,4981.8
Exp/Cntr=0.3,0.1

Chan Stop Cuts=-1