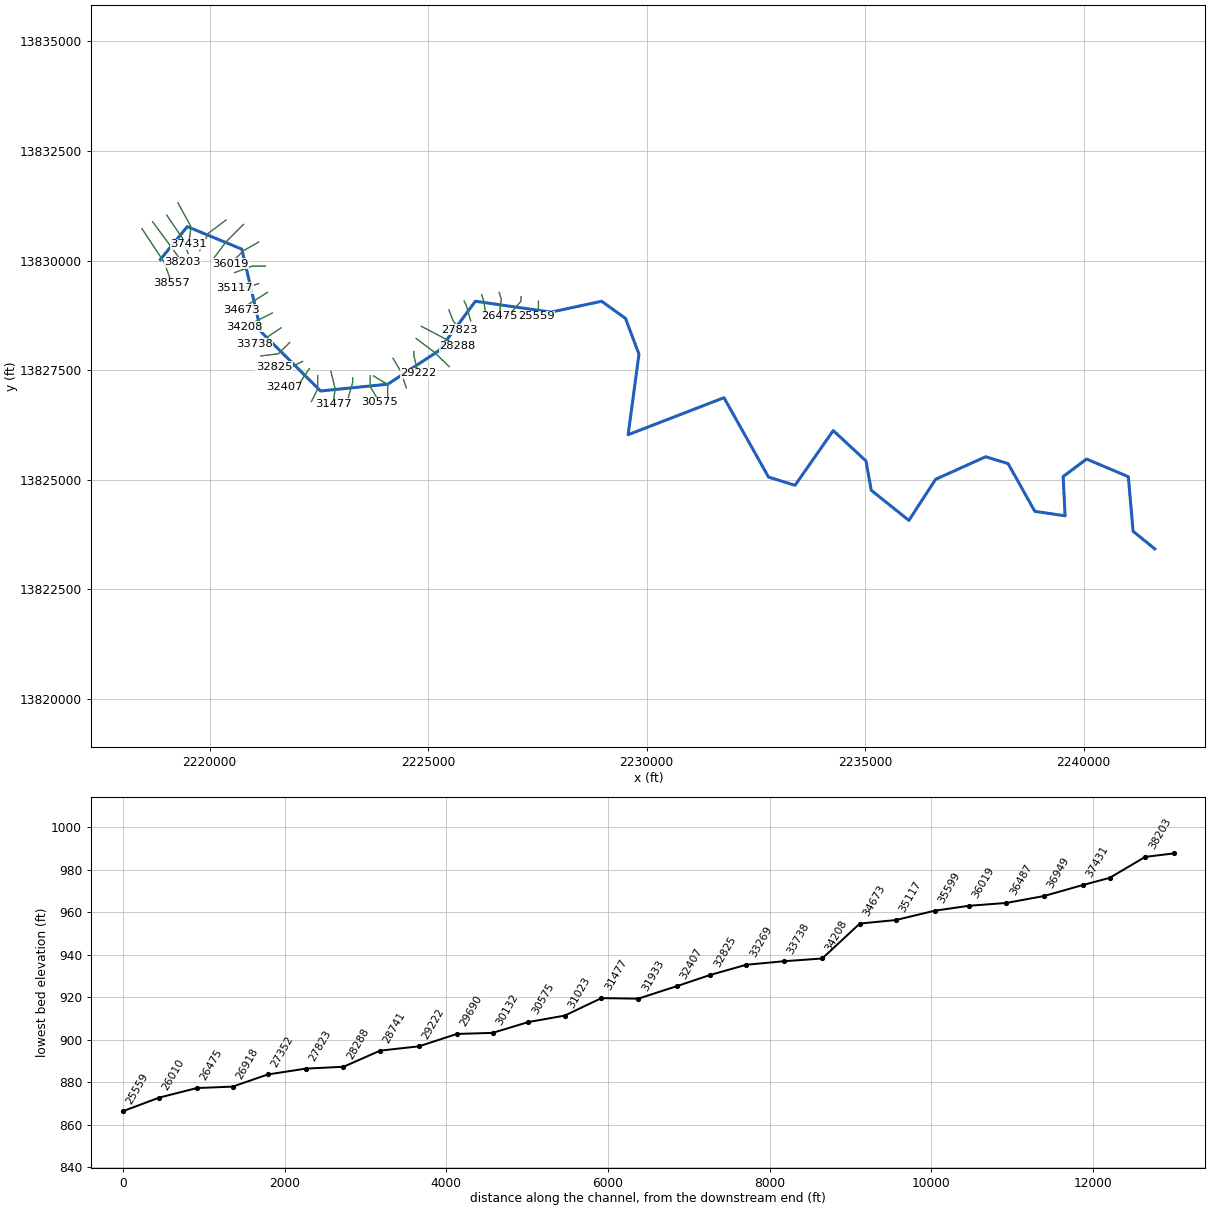
--- Elm Creek 2.prj (project) ---

Proj Title=Elm Creek 2 Base Level Engineering
Current Plan=p01
Default Exp/Contr=0.3,0.1
English Units
Geom File=g01
Flow File=f01
Plan File=p01
Y Axis Title=Elevation
X Axis Title(PF)=Main Channel Distance
X Axis Title(XS)=Station
BEGIN DESCRIPTION:
Elm Creek 2
END DESCRIPTION:
DSS Export Rating Curves= 0
DSS Export Rating Curve Sorted= 0
DSS Export Volume Flow Curves= 0
DXF OffsetX= 0
DXF OffsetY= 0
DXF ScaleX= 1
DXF ScaleY= 10

--- Elm Creek 2.p01 (plan) ---

Plan Title=Multiple Run
Short Identifier=Multiple
Geom File=g01
Flow File=f01
Subcritical Flow
K Sum by GR= 0
Std Step Tol= 0.01
Critical Tol= 0.01
Num of Std Step Trials= 20
Max Error Tol= 0.3
Flow Tol Ratio= 0.001
Split Flow NTrial= 30
Split Flow Tol= 0.02
Split Flow Ratio= 0.02
Log Output Level= 0
Friction Slope Method= 1
Unsteady Friction Slope Method= 2
Unsteady Bridges Friction Slope Method= 1
Parabolic Critical Depth
Global Vel Dist=  1 , 1 , 1
Global Log Level= 0
CheckData=True
Encroach Param= -1, 0, 0, 0
BEGIN DESCRIPTION:
Multiple Run
END DESCRIPTION:

--- Elm Creek 2.f01 (steady flow) ---

Flow Title=Multiple
Number of Profiles=7
Profile Names=10-year,25-year,50-year,1pct_min,100-year,1pct_plu,500-year
River Rch & RM= Elm Creek 2,Reach-1,38557
    1025    1717    2367    1580    3153    6292    5537
River Rch & RM= Elm Creek 2,Reach-1,36949
    1563    2676    3744    2532    5051   10078    9105
River Rch & RM= Elm Creek 2,Reach-1,34673
    1961    3390    4772    3244    6473   12915   11796
River Rch & RM= Elm Creek 2,Reach-1,27823
    2317    4025    5684    3873    7729   15421   14154
River Rch & RM= Elm Creek 2,Reach-1,20949
    2609    4543    6425    4382    8743   17445   16041
River Rch & RM= Elm Creek 2,Reach-1,12370
    2874    5033    7146    4892    9761   19475   18041
Boundary for River Rch & Prof#=Elm Creek 2,Reach-1,1
Up Type=0
Dn Type=3
Dn Slope=0.005
Boundary for River Rch & Prof#=Elm Creek 2,Reach-1,2
Up Type=0
Dn Type=3
Dn Slope=0.005
Boundary for River Rch & Prof#=Elm Creek 2,Reach-1,3
Up Type=0
Dn Type=3
Dn Slope=0.005
Boundary for River Rch & Prof#=Elm Creek 2,Reach-1,4
Up Type=0
Dn Type=3
Dn Slope=0.005
Boundary for River Rch & Prof#=Elm Creek 2,Reach-1,5
Up Type=0
Dn Type=3
Dn Slope=0.005
Boundary for River Rch & Prof#=Elm Creek 2,Reach-1,6
Up Type=0
Dn Type=3
Dn Slope=0.005
Boundary for River Rch & Prof#=Elm Creek 2,Reach-1,7
Up Type=0
Dn Type=3
Dn Slope=0.005

--- Elm Creek 2.g01 (geometry) ---

Geom Title=Existing Conditions
Program Version=4.10

River Reach=Elm Creek 2     ,Reach-1
Reach XY= 30
        2218875.       13830025.      2219490.16     13830774.61
      2220738.31      13830261.6      2221180.54     13828372.58
      2222540.22     13827025.52       2224077.3     13827180.83
       2225245.2     13827944.59      2226080.94     13829072.74
      2227814.81     13828824.54      2228969.07     13829072.76
      2229516.86     13828681.06      2229824.19     13827864.29
       2229576.5     13826028.61      2231769.14     13826872.94
      2232788.61     13825061.76      2233395.14      13824874.6
      2234269.03     13826122.86      2235017.52     13825431.06
      2235138.33     13824761.67      2235999.88     13824074.68
      2236611.78     13825011.38      2237754.92     13825525.67
      2238269.38     13825369.38      2238880.76     13824280.95
      2239573.55     13824178.53      2239528.75     13825073.45
       2240064.5     13825473.78      2241020.41     13825069.83
      2241128.61      13823826.5        2241625.       13823425.

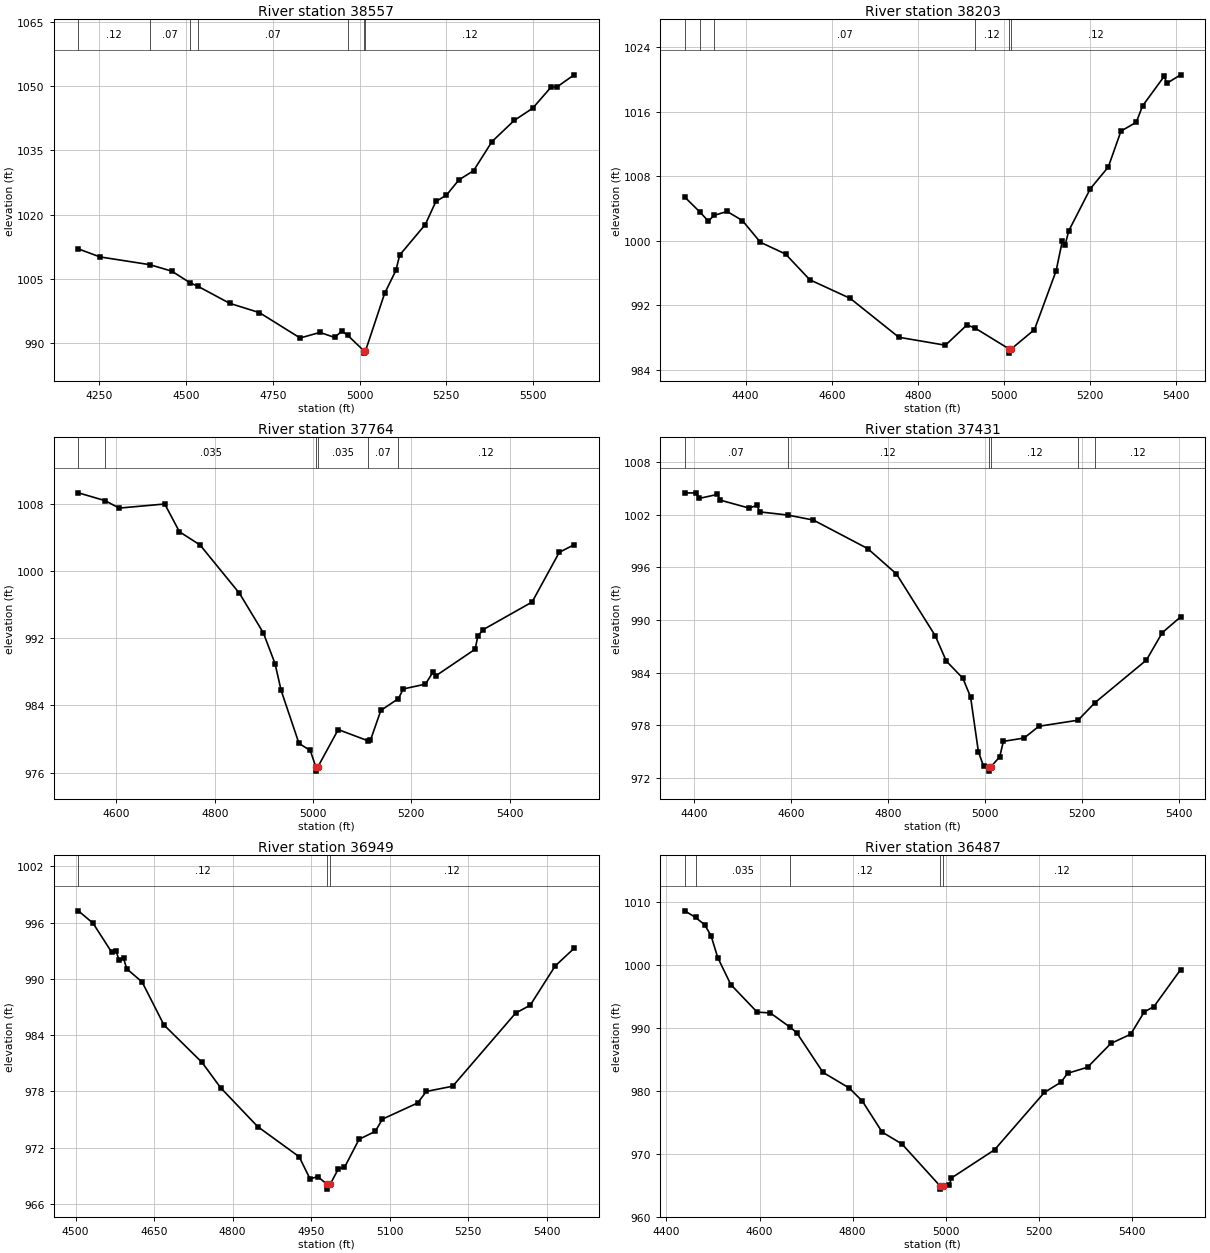
Type RM Length L Ch R = 1 ,38557   ,354,354,354
BEGIN DESCRIPTION:
X19135
END DESCRIPTION:
XS GIS Cut Line= 3
      2218453.06     13830728.13       2218958.6     13829967.21
       2219135.8     13829482.54
#Sta/Elev= 30
    4189 1011.98  4251.3 1010.11  4395.2  1008.3  4458.7 1006.78    4511 1004.08
  4534.1 1003.25    4625   999.3  4711.3  997.11  4828.5   991.2  4885.7   992.5
  4927.7  991.34  4949.1   992.8    4966   991.8  5012.9  988.17  5013.2  987.67
  5016.9  988.17  5072.1  1001.6  5104.6 1006.95  5115.6 1010.55  5189.4 1017.66
  5219.9 1023.04  5250.4 1024.52  5286.3 1028.08  5328.5 1030.21  5381.7 1037.01
  5445.6 1041.93  5498.9 1044.78  5552.1 1049.72  5570.3 1049.82  5618.6 1052.58
#Mann= 7 ,-1 , 0
    4189     .12       0  4395.2     .07       0    4511    .035       0
  4534.1     .07       0    4966     .12       0  5012.9     .05       0
  5016.9     .12       0
Bank Sta=5012.9,5016.9
XS Rating Curve= 0 ,0
Exp/Cntr=0.3,0.1

Type RM Length L Ch R = 1 ,38203   ,439,439,439
BEGIN DESCRIPTION:
Elm Creek 2 84.0
END DESCRIPTION:
XS GIS Cut Line= 3
      2218698.02      13830884.5      2219114.96     13830321.63
      2219380.79     13829956.77
#Sta/Elev= 30
  4258.7 1005.39    4294 1003.53  4313.3 1002.42  4326.8 1003.13  4357.1 1003.61
  4392.6 1002.48  4434.3  999.79  4492.8  998.33  4549.1  995.14    4643  992.83
  4755.9  988.01  4864.2  987.02  4914.3  989.54  4933.6  989.13  5012.7  986.54
  5012.9  986.04  5016.7  986.54  5071.1  988.96  5121.3  996.24    5136 1000.01
  5142.2  999.44  5150.7 1001.21  5200.9 1006.44  5242.6 1009.13    5272 1013.58
  5307.5 1014.67  5322.2 1016.71  5372.4 1020.37  5378.6 1019.51  5410.6 1020.56
#Mann= 6 ,-1 , 0
  4258.7     .07       0    4294     .12       0  4326.8     .07       0
  4933.6     .12       0  5012.7     .05       0  5016.7     .12       0
Bank Sta=5012.7,5016.7
XS Rating Curve= 0 ,0
Exp/Cntr=0.3,0.1

Type RM Length L Ch R = 1 ,37764   ,333,333,333
BEGIN DESCRIPTION:
Elm Creek 2 83.0
END DESCRIPTION:
XS GIS Cut Line= 3
      2219021.14     13831035.67      2219380.77     13830509.26
      2219510.53     13830161.51
#Sta/Elev= 30
  4522.5 1009.32  4576.9 1008.39  4605.6  1007.5  4698.3 1007.99  4728.2 1004.68
  4770.1 1003.11  4850.3  997.35  4898.8  992.65  4922.6  988.99  4935.1  985.78
  4971.4  979.47  4994.3  978.63  5005.7  976.67  5005.9  976.17  5009.8  976.67
  5051.2  981.12    5111   979.8  5116.7  979.83  5137.9   983.4  5173.8  984.81
  5183.5  985.96  5228.6  986.53  5244.1  987.97    5250  987.53  5329.7  990.69
  5335.4  992.28    5346  993.02  5445.6  996.31  5500.9 1002.23  5531.2 1003.14
#Mann= 6 ,-1 , 0
  4522.5     .07       0  4576.9    .035       0  5005.7    .035       0
  5009.8    .035       0    5111     .07       0  5173.8     .12       0
Bank Sta=5005.7,5009.8
XS Rating Curve= 0 ,0
Exp/Cntr=0.3,0.1

Type RM Length L Ch R = 1 ,37431   ,482,482,482
BEGIN DESCRIPTION:
Elm Creek 2 82.0
END DESCRIPTION:
XS GIS Cut Line= 3
      2219276.55     13831317.07        2219575.       13830775.
        2219525.     13830375.01
#Sta/Elev= 30
  4381.3 1004.47    4405 1004.49  4410.7 1003.85  4448.6 1004.31  4454.3 1003.66
  4513.9 1002.75    4530 1003.07  4535.7 1002.32  4593.2 1001.96  4646.2 1001.39
  4758.2  998.14  4817.5  995.25  4897.4  988.22  4920.2  985.33  4954.4  983.37
  4970.3  981.23  4986.4     975  4997.2  973.33  5008.1  973.29  5008.4  972.79
  5012.3  973.29  5030.3  974.42  5037.9  976.18  5080.7  976.56    5111   977.9
  5191.8  978.59  5226.7  980.59  5332.7  985.44  5365.4  988.56  5403.2  990.36
#Mann= 6 ,-1 , 0
  4381.3     .07       0  4593.2     .12       0  5008.1     .05       0
  5012.3     .12       0  5191.8     .07       0  5226.7     .12       0
Bank Sta=5008.1,5012.3
XS Rating Curve= 0 ,0
Exp/Cntr=0.3,0.1

Type RM Length L Ch R = 1 ,36949   ,462,462,462
BEGIN DESCRIPTION:
Elm Creek 2 81.0
END DESCRIPTION:
XS GIS Cut Line= 3
      2220374.99     13830924.99        2219975.       13830625.
        2219775.       13830225.
#Sta/Elev= 30
  4505.2  997.25  4533.3  995.93  4568.7  992.85  4577.1  992.97  4583.3  991.96
  4591.6  992.17  4597.9  991.06  4627.1  989.66  4668.7  985.09  4741.6  981.09
  4777.1  978.39  4847.9  974.25  4927.1  971.04  4947.9  968.67  4962.5  968.93
  4980.5  968.09    4981  967.59  4986.2  968.09  5002.1  969.77  5013.6   969.9
  5041.5   972.9  5072.3  973.74  5086.2  975.05  5153.3  976.77  5170.1     978
  5220.4  978.56  5340.6  986.35  5368.5  987.19  5416.1  991.37  5452.4  993.26
#Mann= 3 ,-1 , 0
  4505.2     .12       0  4980.5     .05       0  4986.2     .12       0
Bank Sta=4980.5,4986.2
XS Rating Curve= 0 ,0
Exp/Cntr=0.3,0.1

Type RM Length L Ch R = 1 ,36487   ,468,468,468
BEGIN DESCRIPTION:
Elm Creek 2 80.0
END DESCRIPTION:
XS GIS Cut Line= 3
      2220774.98     13830824.98        2220375.       13830425.
      2220074.97     13830024.96
#Sta/Elev= 30
  4439.4 1008.54  4462.5 1007.49  4481.8 1006.35  4495.9 1004.58  4510.1 1001.13
  4538.4  996.82  4594.9  992.46  4623.2  992.33  4665.2  990.09  4679.8  989.21
  4736.4  982.89  4792.9  980.41  4821.2  978.31  4863.6  973.41  4906.1  971.53
  4988.1  964.86  4988.5  964.36  4993.8  964.86  5008.2  965.09  5012.3  966.12
  5105.1   970.6  5212.3  979.71  5247.8  981.33  5262.3  982.75  5305.1  983.71
  5355.1  987.48  5397.8  988.95  5426.9  992.49  5447.8  993.34  5505.1  999.21
#Mann= 5 ,-1 , 0
  4439.4     .07       0  4462.5    .035       0  4665.2     .12       0
  4988.1     .05       0  4993.8     .12       0
Bank Sta=4988.1,4993.8
XS Rating Curve= 0 ,0
Exp/Cntr=0.3,0.1

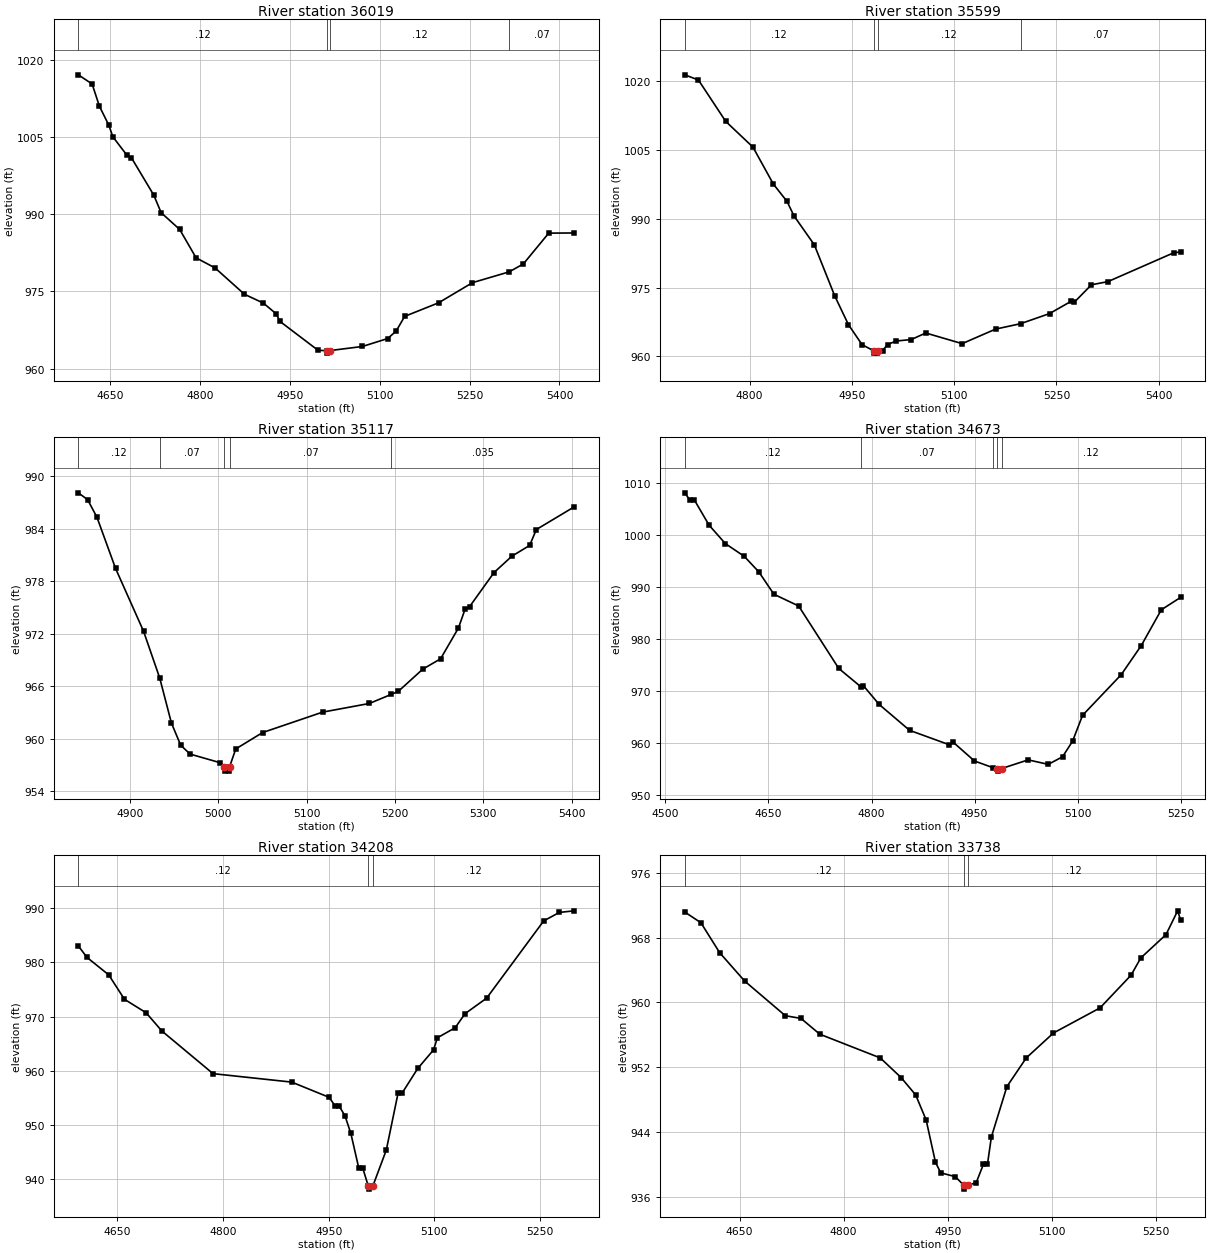
Type RM Length L Ch R = 1 ,36019   ,420,420,420
BEGIN DESCRIPTION:
Elm Creek 2 79.0
END DESCRIPTION:
XS GIS Cut Line= 3
      2221124.96     13830424.98        2220775.       13830225.
      2220475.02     13829925.02
#Sta/Elev= 30
  4597.2 1017.15  4620.2 1015.37  4632.4 1011.03  4648.3  1007.3  4654.7 1005.11
  4677.8 1001.58  4685.7 1001.03  4723.1  993.74  4735.4  990.32  4766.3  987.07
  4793.7  981.54  4825.3  979.58  4874.3  974.46    4906  972.73  4927.6  970.62
  4933.3   969.2  4997.4  963.53  5011.5   963.5    5012     963  5017.3   963.5
    5071  964.29  5113.4  965.84  5127.5  967.29  5141.7  970.15  5198.3  972.79
  5254.8  976.71    5316  978.81  5339.7  980.35  5382.1  986.35  5424.5  986.38
#Mann= 4 ,-1 , 0
  4597.2     .12       0  5011.5     .05       0  5017.3     .12       0
    5316     .07       0
Bank Sta=5011.5,5017.3
XS Rating Curve= 0 ,0
Exp/Cntr=0.3,0.1

Type RM Length L Ch R = 1 ,35599   ,482,482,482
BEGIN DESCRIPTION:
Elm Creek 2 78.0
END DESCRIPTION:
XS GIS Cut Line= 3
      2221275.05       13829875.        2220975.       13829875.
      2220575.04     13829725.02
#Sta/Elev= 30
    4705  1021.4    4725 1020.27    4765 1011.25    4805 1005.62    4835  997.54
    4855  993.78    4865  990.66    4895  984.31    4925  973.14    4945   966.9
    4965  962.54  4982.1  961.19  4982.6  960.69  4987.5  960.69    4988  961.19
    4995  961.26  5002.5  962.56  5014.8  963.33  5037.1  963.65  5058.4  965.08
  5111.8  962.76  5160.8  965.93  5197.4  967.11    5240  969.32  5271.2  971.96
  5276.5  971.83  5301.4   975.6  5325.4  976.28  5422.5  982.61  5432.2  982.74
#Mann= 4 ,-1 , 0
    4705     .12       0  4982.1     .05       0    4988     .12       0
  5197.4     .07       0
Bank Sta=4982.1,4988
XS Rating Curve= 0 ,0
Exp/Cntr=0.3,0.1

Type RM Length L Ch R = 1 ,35117   ,444,444,444
BEGIN DESCRIPTION:
Elm Creek 2 77.0
END DESCRIPTION:
XS GIS Cut Line= 3
      2221124.97     13829474.99        2220975.       13829425.
        2220575.       13829375.
#Sta/Elev= 30
  4841.6  988.13  4852.1  987.35  4862.7  985.33  4883.7  979.49  4915.4   972.3
  4933.7  966.95    4947  961.78  4957.5  959.25  4968.1  958.24  5002.2  957.25
  5006.8  956.79  5007.3  956.29  5012.3  956.29  5012.8  956.79  5019.8  958.83
  5050.1   960.7  5118.1  963.04    5171  964.03  5195.8  965.07  5203.8  965.42
  5231.5  967.96  5251.6  969.14  5271.8  972.66  5279.3  974.81  5284.4   975.1
  5312.1  979.01  5332.3  980.88  5352.4  982.11    5360  983.93  5402.8  986.52
#Mann= 5 ,-1 , 0
  4841.6     .12       0  4933.7     .07       0  5006.8     .05       0
  5012.8     .07       0  5195.8    .035       0
Bank Sta=5006.8,5012.8
XS Rating Curve= 0 ,0
Exp/Cntr=0.3,0.1

Type RM Length L Ch R = 1 ,34673   ,465,465,465
BEGIN DESCRIPTION:
Elm Creek 2 76.0
END DESCRIPTION:
XS GIS Cut Line= 3
      2221325.01       13829275.        2220925.       13829025.
      2220725.01       13828875.
#Sta/Elev= 30
  4528.2 1008.07  4535.9  1006.6  4541.8 1006.77  4563.6 1001.85  4587.2  998.33
  4614.9  995.86  4636.1  992.87  4657.9   988.6  4693.9  986.35  4752.3  974.36
  4784.2  970.87  4788.2  971.04  4811.2  967.44  4855.4  962.48  4913.2  959.71
  4919.1  960.17  4949.8   956.6  4976.9   955.3  4983.3  955.15  4983.8  954.65
  4989.4  955.15    5028  956.81  5057.2  955.95    5078   957.4  5092.6  960.39
  5107.2  965.37  5163.4  973.16  5192.6  978.75  5221.8  985.62  5249.9     988
#Mann= 5 ,-1 , 0
  4528.2     .12       0  4784.2     .07       0  4976.9     .12       0
  4983.3     .05       0  4989.4     .12       0
Bank Sta=4983.3,4989.4
XS Rating Curve= 0 ,0
Exp/Cntr=0.3,0.1

Type RM Length L Ch R = 1 ,34208   ,470,470,470
BEGIN DESCRIPTION:
Elm Creek 2 75.0
END DESCRIPTION:
XS GIS Cut Line= 5
       2221433.6      13828804.3        2221175.       13828675.
        2221075.       13828625.        2220975.       13828575.
      2220803.84     13828489.42
#Sta/Elev= 30
  4594.5  983.04  4606.9  980.91  4637.7   977.7    4660   973.2  4690.8  970.71
  4713.1  967.36  4785.8  959.49  4897.6  957.93  4950.7  955.12  4959.1  953.54
  4964.7  953.55  4973.1  951.73  4981.5  948.47  4992.6  942.16  4998.2  942.16
  5006.4   938.7  5006.9   938.2  5012.5   938.7  5031.8  945.39  5048.5  955.87
  5054.1  955.87  5076.5  960.45  5098.9  963.87  5104.4  966.11  5129.6  967.95
  5143.6  970.54  5174.3  973.41  5255.4  987.66  5277.7  989.22  5298.6  989.51
#Mann= 3 ,-1 , 0
  4594.5     .12       0  5006.4     .05       0  5012.5     .12       0
Bank Sta=5006.4,5012.5
XS Rating Curve= 0 ,0
Exp/Cntr=0.3,0.1

Type RM Length L Ch R = 1 ,33738   ,469,469,469
BEGIN DESCRIPTION:
Elm Creek 2 74.0
END DESCRIPTION:
XS GIS Cut Line= 5
      2221635.57     13828465.38        2221425.       13828325.
        2221275.       13828225.        2221175.       13828175.
      2221023.62     13828099.31
#Sta/Elev= 30
  4571.1  971.15  4594.3  969.83  4621.4  966.12  4657.4  962.62    4716  958.34
  4738.5  958.01  4765.6  956.06  4852.7  953.13  4882.8   950.7  4903.8  948.55
  4918.8  945.47  4932.3  940.23  4939.9  938.93  4960.9  938.46  4972.8  937.42
  4973.3  936.92    4979  937.42  4990.9   937.7  5001.4     940  5007.2     940
  5012.8  943.35  5035.2  949.59  5063.1  953.13  5102.3  956.21  5169.4  959.31
  5214.1  963.35  5228.1  965.48  5264.4  968.36  5281.2   971.3  5285.5  970.17
#Mann= 3 ,-1 , 0
  4571.1     .12       0  4972.8     .05       0    4979     .12       0
Bank Sta=4972.8,4979
XS Rating Curve= 0 ,0
Exp/Cntr=0.3,0.1

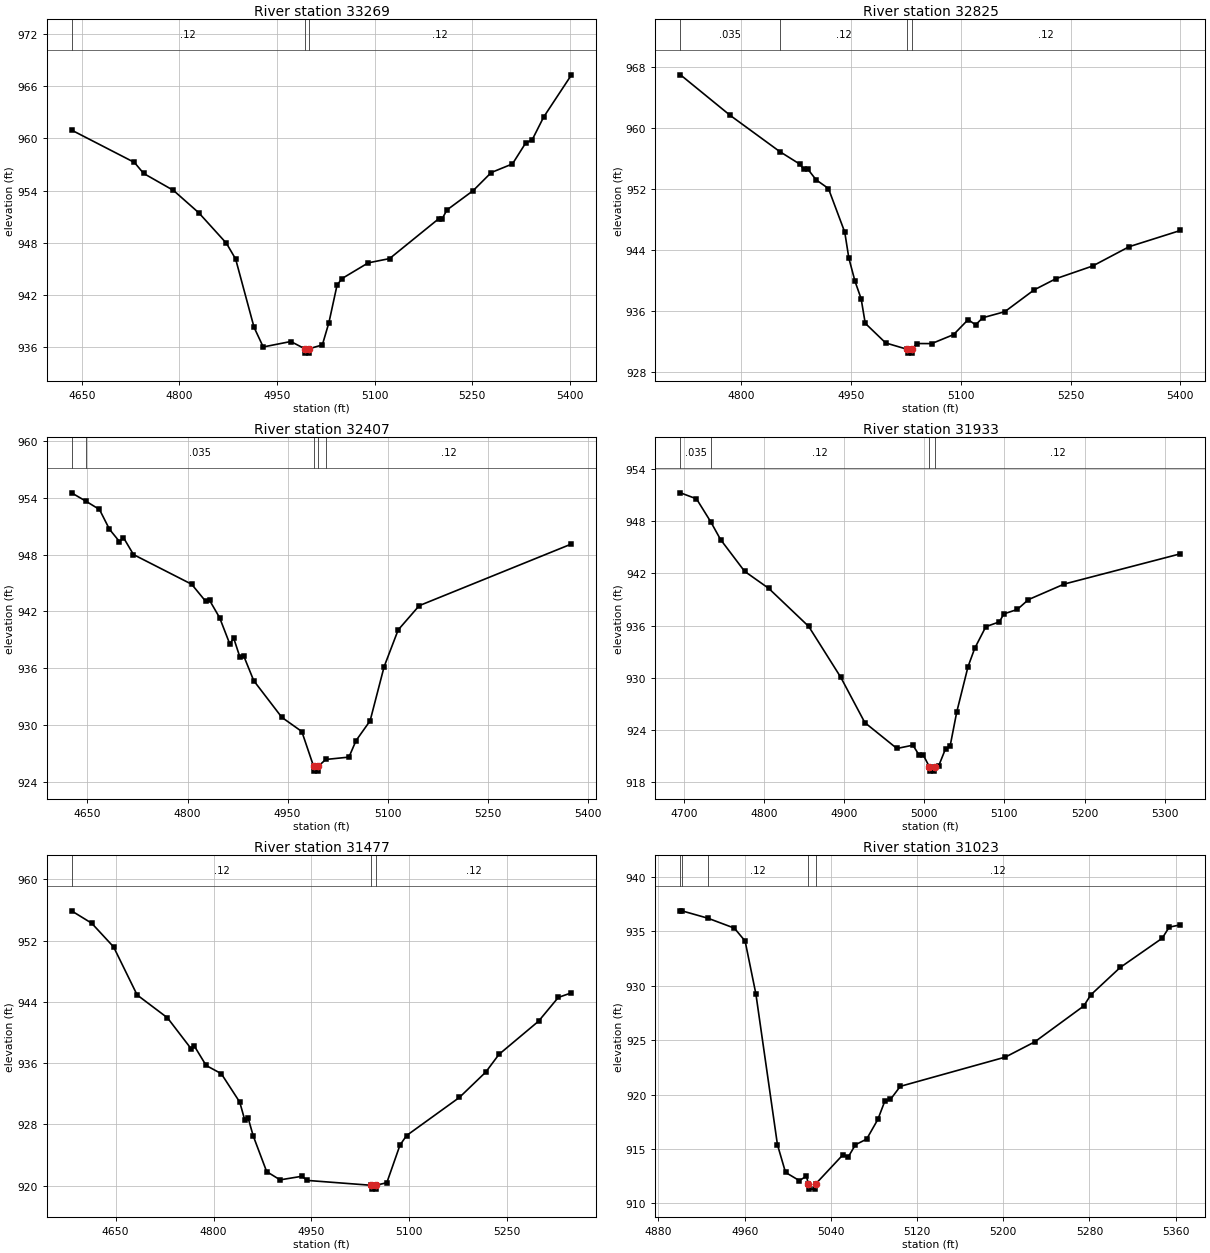
Type RM Length L Ch R = 1 ,33269   ,444,444,444
BEGIN DESCRIPTION:
Elm Creek 2 73.0
END DESCRIPTION:
XS GIS Cut Line= 4
      2221833.32     13828133.32        2221725.       13828025.
        2221575.       13827875.      2221175.03       13827825.
#Sta/Elev= 30
  4634.1  960.97  4730.7  957.24  4744.9  955.97  4790.8  954.01  4829.7  951.43
  4872.1  947.92  4886.3   946.1  4914.6  938.23  4928.7  935.96  4971.1  936.59
  4992.7  935.75  4993.2  935.25  4998.5  935.25    4999  935.75  5019.6   936.2
  5029.7  938.78  5042.2   943.1  5049.8  943.85  5090.1  945.66  5122.9  946.15
  5198.5  950.75  5203.5  950.72  5211.1  951.76  5251.4  953.99  5279.1  956.07
  5311.8  957.07    5332  959.47  5342.1  959.85  5359.7  962.47  5402.5  967.34
#Mann= 3 ,-1 , 0
  4634.1     .12       0  4992.7     .05       0    4999     .12       0
Bank Sta=4992.7,4999
XS Rating Curve= 0 ,0
Exp/Cntr=0.3,0.1

Type RM Length L Ch R = 1 ,32825   ,418,418,418
BEGIN DESCRIPTION:
Elm Creek 2 72.0
END DESCRIPTION:
XS GIS Cut Line= 4
      2222128.34     13827701.67        2221975.       13827625.
        2221875.       13827575.      2221475.04       13827575.
#Sta/Elev= 30
    4717  967.03    4785   961.7  4852.7  956.95  4880.1   955.3  4885.6  954.62
  4891.2  954.62  4902.4  953.24  4919.2   952.1  4941.5  946.37  4947.1  942.96
  4955.5  939.92  4963.9  937.62  4969.5   934.4  4997.4  931.82  5026.9  930.98
  5027.4  930.48  5033.1  930.48  5033.6  930.98  5040.2  931.74  5060.2  931.73
  5090.2  932.91  5110.2  934.89  5120.2  934.19  5130.2  935.13  5160.2  935.92
  5200.2  938.78  5230.2  940.26  5280.2  941.92  5330.2  944.46  5400.2  946.59
#Mann= 4 ,-1 , 0
    4717    .035       0  4852.7     .12       0  5026.9     .05       0
  5033.6     .12       0
Bank Sta=5026.9,5033.6
XS Rating Curve= 0 ,0
Exp/Cntr=0.3,0.1

Type RM Length L Ch R = 1 ,32407   ,474,474,474
BEGIN DESCRIPTION:
Elm Creek 2 71.0
END DESCRIPTION:
XS GIS Cut Line= 5
      2222282.39     13827536.08        2222175.       13827375.
        2222075.       13827225.        2221925.       13827175.
      2221718.46     13827106.15
#Sta/Elev= 30
  4626.1  954.52  4647.1  953.66    4668  952.76    4683  950.67    4698  949.37
    4704  949.79    4719     948  4806.2  944.87  4827.2  943.07  4833.2  943.16
  4848.2  941.33  4863.3  938.58  4869.3  939.17  4878.3  937.23  4884.3   937.3
  4899.3  934.69  4941.4  930.82  4971.4  929.32  4989.1  925.64  4989.6  925.14
  4995.4  925.14  4995.9  925.64  5007.3  926.37  5042.1  926.62  5052.7  928.36
  5073.8  930.45  5094.8  936.16  5115.9  940.05  5147.5  942.61  5375.8  949.12
#Mann= 5 ,-1 , 0
  4626.1     .12       0  4647.1    .035       0  4989.1    .035       0
  4995.9    .035       0  5007.3     .12       0
Bank Sta=4989.1,4995.9
XS Rating Curve= 0 ,0
Exp/Cntr=0.3,0.1

Type RM Length L Ch R = 1 ,31933   ,456,456,456
BEGIN DESCRIPTION:
Elm Creek 2 70.0
END DESCRIPTION:
XS GIS Cut Line= 4
        2222475.     13827374.98        2222475.       13827075.
        2222425.       13826975.      2222330.23     13826785.46
#Sta/Elev= 30
  4695.9  951.24  4715.9  950.55  4733.7  947.91  4745.9  945.88  4775.9  942.23
  4805.9  940.28  4855.9   935.9  4895.9  930.06  4925.9  924.86  4965.9  921.89
  4985.9  922.27  4993.4  921.16  4998.7  921.16  5006.4  919.79  5006.9  919.29
  5012.8  919.29  5013.3  919.79  5018.2  919.93  5026.6  921.86  5032.2  922.12
  5040.6  926.09  5054.6  931.27    5063  933.39  5076.9  935.88  5093.7  936.42
  5099.3  937.34  5116.1  937.85    5130  938.98  5174.8  940.77  5319.6  944.24
#Mann= 4 ,-1 , 0
  4695.9    .035       0  4733.7     .12       0  5006.4     .05       0
  5013.3     .12       0
Bank Sta=5006.4,5013.3
XS Rating Curve= 0 ,0
Exp/Cntr=0.3,0.1

Type RM Length L Ch R = 1 ,31477   ,454,454,454
BEGIN DESCRIPTION:
Elm Creek 2 69.0
END DESCRIPTION:
XS GIS Cut Line= 3
        2222775.       13827475.        2222875.       13827075.
        2222825.     13826724.97
#Sta/Elev= 30
  4582.5  955.89  4613.4  954.27  4646.9  951.18    4683   944.9  4729.4  941.92
  4765.5   937.9  4770.6  938.23  4788.7  935.69  4811.9  934.62  4840.2   930.9
  4847.9  928.55  4853.1  928.81  4860.8   926.5  4881.4  921.83    4902  920.75
  4935.5  921.22  4943.3  920.68  5041.8  920.04  5042.3  919.54  5048.3  919.54
  5048.8  920.04  5065.5  920.38  5085.7   925.3  5095.8  926.54  5176.6  931.51
    5217  934.82  5237.3  937.14  5297.9  941.47  5328.2  944.58  5348.4  945.18
#Mann= 3 ,-1 , 0
  4582.5     .12       0  5041.8     .05       0  5048.8     .12       0
Bank Sta=5041.8,5048.8
XS Rating Curve= 0 ,0
Exp/Cntr=0.3,0.1

Type RM Length L Ch R = 1 ,31023   ,448,448,448
BEGIN DESCRIPTION:
Elm Creek 2 68.0
END DESCRIPTION:
XS GIS Cut Line= 3
        2223275.     13827325.01        2223275.       13827225.
      2223175.01     13826875.02
#Sta/Elev= 30
  4900.4   936.9  4901.7   936.9  4925.9  936.22  4950.4  935.31  4960.4  934.12
  4970.4  929.26  4990.4   915.4  4997.9  912.85  5010.8  912.09  5017.3  912.51
    5019  911.81  5019.5  911.31  5025.6  911.31  5026.1  911.81  5051.1  914.46
  5056.3   914.3  5062.8  915.39  5073.2  915.91  5083.6  917.72  5090.1  919.41
  5095.3  919.56  5104.4  920.76  5201.9  923.45  5229.2  924.85  5274.7  928.15
  5281.2  929.17  5308.5  931.69  5347.5  934.38    5354   935.4  5364.4  935.61
#Mann= 5 ,-1 , 0
  4900.4     .12       0  4901.7     .07       0  4925.9     .12       0
    5019     .05       0  5026.1     .12       0
Bank Sta=5019,5026.1
XS Rating Curve= 0 ,0
Exp/Cntr=0.3,0.1

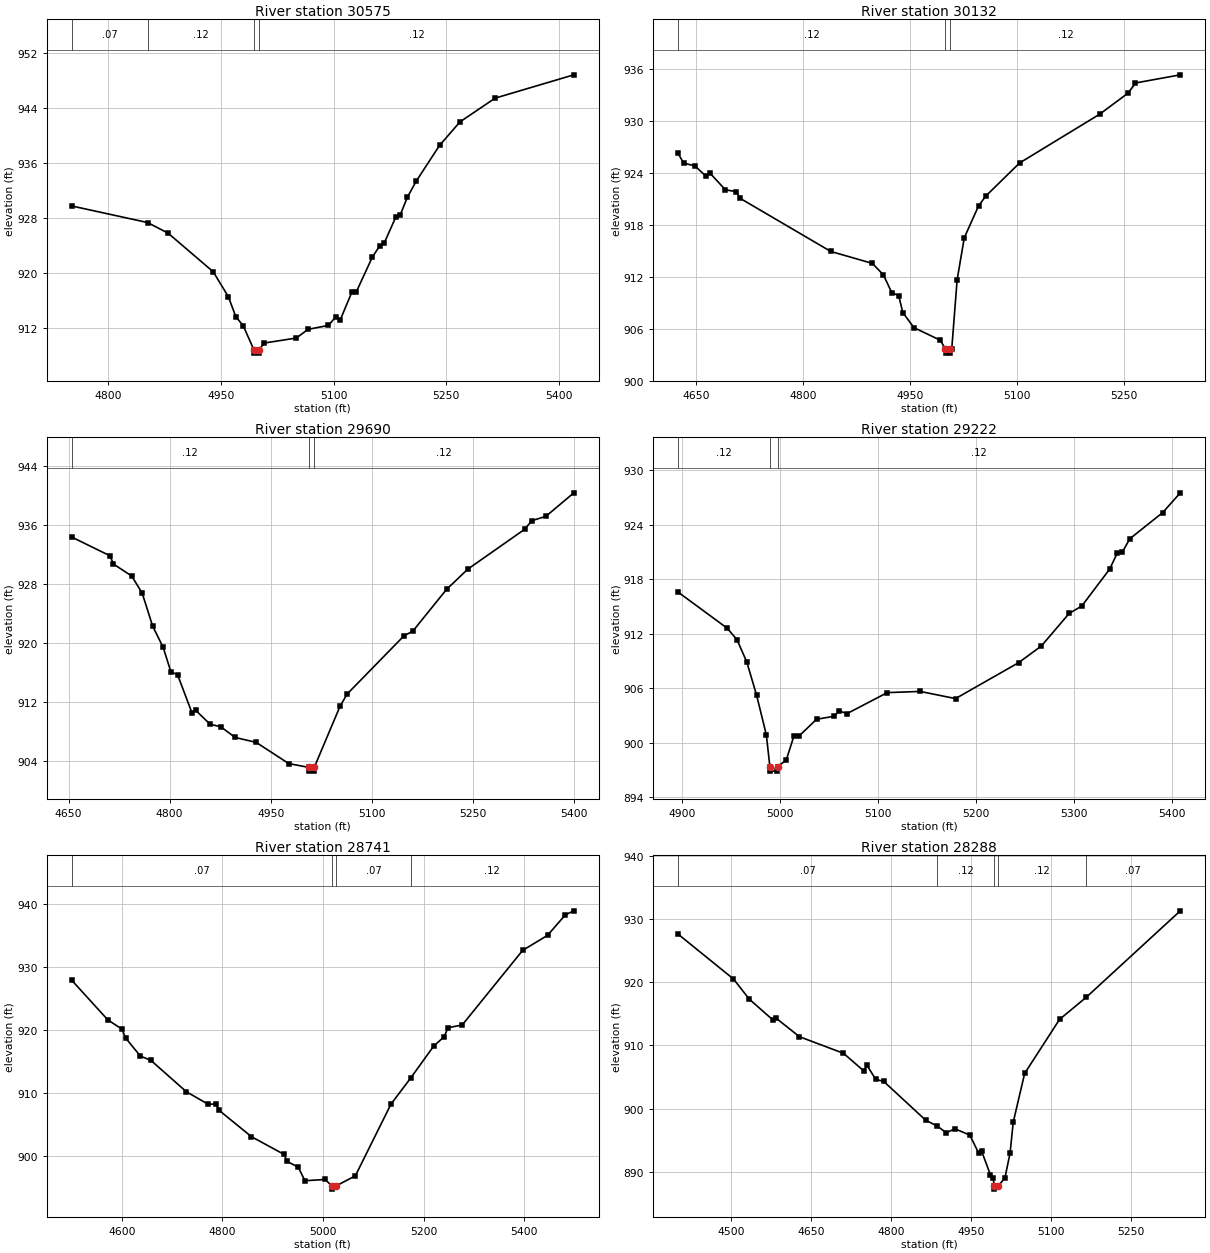
Type RM Length L Ch R = 1 ,30575   ,443,443,443
BEGIN DESCRIPTION:
Elm Creek 2 67.0
END DESCRIPTION:
XS GIS Cut Line= 5
        2223675.      13827373.3        2223675.       13827275.
        2223675.       13827125.        2223825.       13826875.
      2223890.88      13826765.2
#Sta/Elev= 30
  4751.7  929.75  4852.7  927.33    4880  925.78    4940  920.15    4960  916.54
    4970  913.62    4980  912.26    4994  908.79  4994.5  908.29  5000.6  908.29
  5001.1  908.79  5007.8  909.76  5050.5  910.49  5066.1  911.76  5093.3  912.33
    5103  913.59  5108.8   913.1  5124.4  917.19  5130.2   917.2  5151.6  922.29
  5161.3  923.91  5167.2  924.29  5182.7  928.11  5188.5  928.39  5198.3  931.04
  5209.9  933.35    5241  938.58  5268.2  942.01  5314.9  945.47  5419.6  948.87
#Mann= 4 ,-1 , 0
  4751.7     .07       0  4852.7     .12       0    4994     .05       0
  5001.1     .12       0
Bank Sta=4994,5001.1
XS Rating Curve= 0 ,0
Exp/Cntr=0.3,0.1

Type RM Length L Ch R = 1 ,30132   ,442,442,442
BEGIN DESCRIPTION:
Elm Creek 2 66.0
END DESCRIPTION:
XS GIS Cut Line= 5
      2223748.27     13827371.04        2223825.       13827325.
        2224075.       13827175.        2224075.       13827075.
        2224075.     13826852.23
#Sta/Elev= 30
  4624.6  926.22  4632.4  925.11    4648  924.79  4663.5  923.61  4669.4  923.94
  4690.8  922.03  4706.3  921.81  4711.2  921.06  4838.5  914.92  4896.8  913.54
  4912.3  912.22    4924  910.17  4933.7  909.83  4939.5  907.87  4955.1  906.13
    4992  904.68  4999.1  903.69  4999.6  903.19  5005.8  903.19  5006.3  903.69
  5008.1  903.69  5015.6  911.62  5025.6  916.49  5045.6  920.16  5055.6  921.29
  5103.1  925.12  5215.6  930.76  5255.6  933.21  5265.6  934.35  5328.4  935.29
#Mann= 3 ,-1 , 0
  4624.6     .12       0  4999.1     .05       0  5006.3     .12       0
Bank Sta=4999.1,5006.3
XS Rating Curve= 0 ,0
Exp/Cntr=0.3,0.1

Type RM Length L Ch R = 1 ,29690   ,468,468,468
BEGIN DESCRIPTION:
Elm Creek 2 65.0
END DESCRIPTION:
XS GIS Cut Line= 5
      2224197.14     13827771.43        2224225.       13827725.
        2224375.       13827475.        2224425.       13827325.
      2224501.43     13827095.71
#Sta/Elev= 30
  4654.5   934.4  4711.6  931.85  4716.4  930.75  4743.6  929.12  4759.2   926.8
  4774.7  922.34  4790.3  919.46  4801.9  916.12  4811.7  915.75    4833   910.6
  4838.9   910.9  4860.2  909.02  4875.8   908.7  4897.2  907.24  4928.3  906.58
  4976.9   903.7  5006.9  903.18  5007.4  902.68  5014.1  902.68  5014.6  903.18
  5052.9  911.46  5063.4  913.12  5147.8  921.01  5160.9  921.64    5211   927.3
  5242.6  930.05    5327  935.45  5337.5  936.61  5358.6  937.21    5400  940.39
#Mann= 3 ,-1 , 0
  4654.5     .12       0  5006.9     .05       0  5014.6     .12       0
Bank Sta=5006.9,5014.6
XS Rating Curve= 0 ,0
Exp/Cntr=0.3,0.1

Type RM Length L Ch R = 1 ,29222   ,481,481,481
BEGIN DESCRIPTION:
Elm Creek 2 64.0
END DESCRIPTION:
XS GIS Cut Line= 3
        2224675.       13827925.        2224675.       13827825.
        2224775.     13827425.01
#Sta/Elev= 30
  4896.1  916.58  4946.1  912.61  4956.1  911.35  4966.1   908.9  4976.1  905.25
  4986.1  900.85  4989.7  897.36  4990.2  896.86    4997  896.86  4997.5  897.36
  5006.4  898.07  5014.1  900.68  5019.3  900.71  5037.3  902.57  5055.4  902.91
  5060.5   903.5  5068.3  903.19  5109.5  905.51    5143  905.64  5179.1  904.85
  5243.5  908.81  5266.7  910.65    5295  914.23  5307.9  915.05  5336.3  919.11
    5344  920.86  5349.1  920.96  5356.9  922.46  5390.4  925.34  5408.4  927.52
#Mann= 3 ,-1 , 0
  4896.1     .12       0  4989.7     .05       0  4997.5     .12       0
Bank Sta=4989.7,4997.5
XS Rating Curve= 0 ,0
Exp/Cntr=0.3,0.1

Type RM Length L Ch R = 1 ,28741   ,453,453,453
BEGIN DESCRIPTION:
Elm Creek 2 63.0
END DESCRIPTION:
XS GIS Cut Line= 3
      2224724.98     13828225.01        2225125.       13827925.
      2225483.96     13827580.13
#Sta/Elev= 30
  4500.5  927.95  4572.4  921.65  4600.5  920.18  4607.8  918.77    4637  915.92
  4657.8  915.24  4728.6  910.25  4772.4  908.25    4787  908.35  4793.2  907.33
  4857.8  903.13  4922.4  900.33  4928.6  899.21  4950.5  898.31  4964.1  896.15
    5004  896.35  5017.7  895.32  5018.2  894.82  5025.7  895.32  5064.2  896.93
    5135   908.3  5174.1  912.43  5219.9   917.5  5240.9     919  5248.2  920.41
  5276.5  920.84  5396.6  932.67    5446  935.05  5481.5  938.31  5498.3  938.94
#Mann= 4 ,-1 , 0
  4500.5     .07       0  5017.7     .05       0  5025.7     .07       0
  5174.1     .12       0
Bank Sta=5017.7,5025.7
XS Rating Curve= 0 ,0
Exp/Cntr=0.3,0.1

Type RM Length L Ch R = 1 ,28288   ,465,465,465
BEGIN DESCRIPTION:
Elm Creek 2 62.0
END DESCRIPTION:
XS GIS Cut Line= 3
      2224842.83     13828502.68        2225375.       13828225.
       2225670.1     13828050.09
#Sta/Elev= 30
  4400.1  927.65  4504.1  920.54  4533.9  917.34  4578.1  914.05  4583.7  914.36
  4628.1  911.39  4710.6  908.77  4749.2  905.95  4754.8  906.88  4771.3  904.61
    4786  904.33  4865.2  898.15  4886.1  897.26  4903.8  896.18  4920.2  896.79
    4948   895.8  4964.4  892.97    4970   893.3  4986.5  889.54  4992.1  889.06
  4993.5  887.73    4994  887.23  5001.6  887.73    5014  889.03  5023.6  892.93
  5029.6  897.85    5051  905.57  5116.6  914.14  5166.7  917.64  5343.4  931.35
#Mann= 5 ,-1 , 0
  4400.1     .07       0  4886.1     .12       0  4993.5     .05       0
  5001.6     .12       0  5166.7     .07       0
Bank Sta=4993.5,5001.6
XS Rating Curve= 0 ,0
Exp/Cntr=0.3,0.1

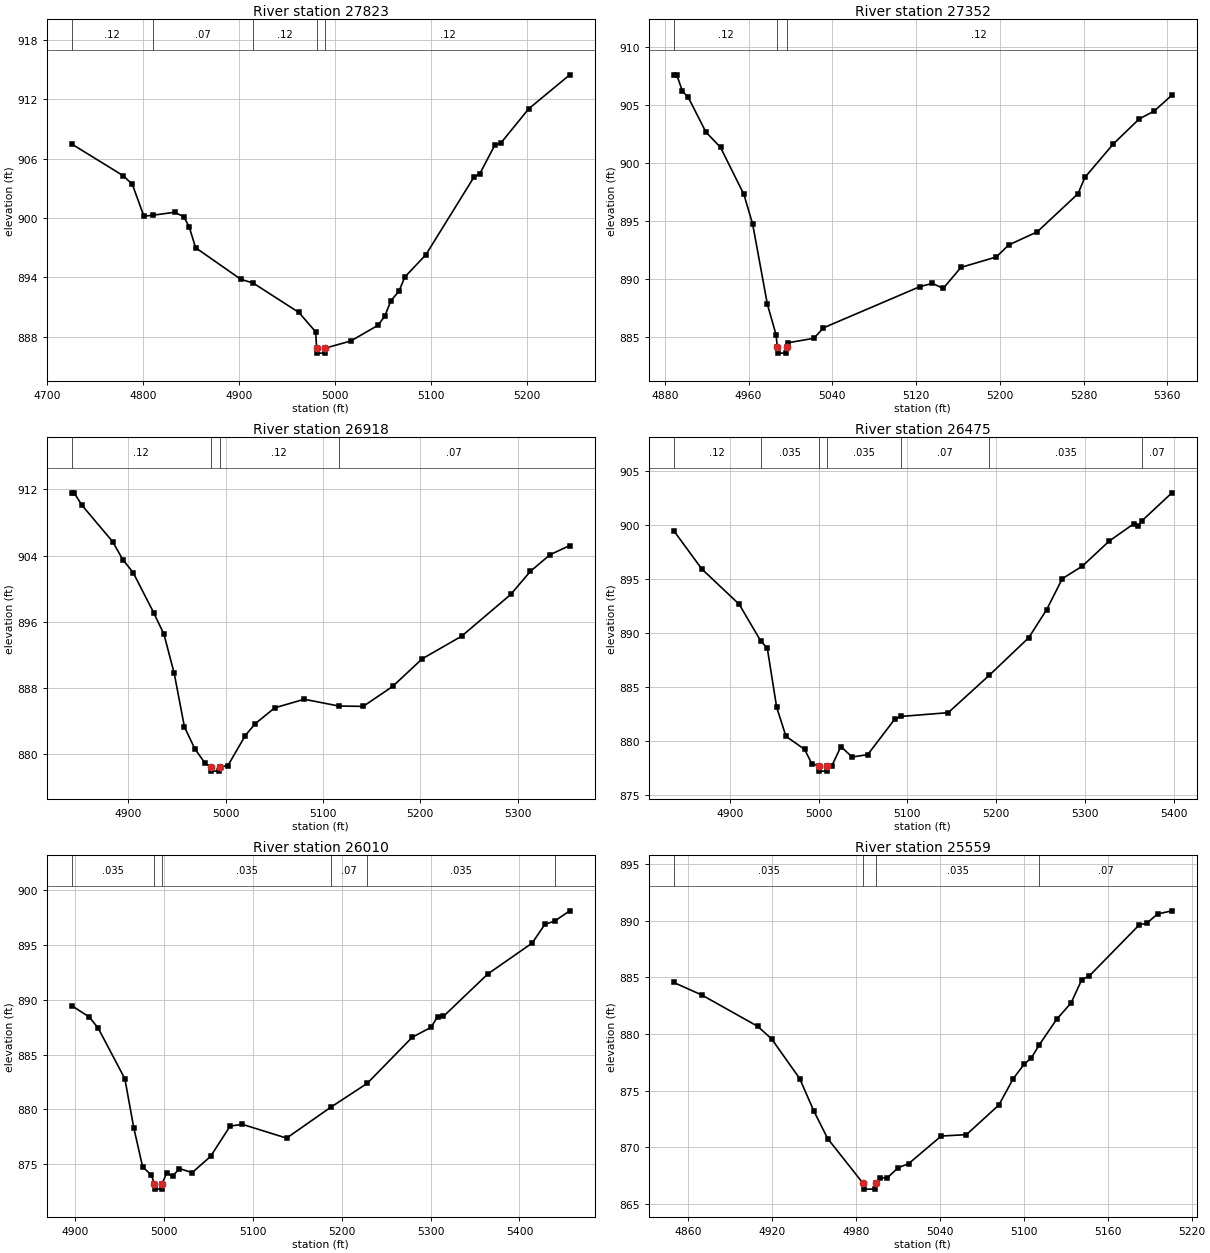
Type RM Length L Ch R = 1 ,27823   ,471,471,471
BEGIN DESCRIPTION:
Elm Creek 2 61.0
END DESCRIPTION:
XS GIS Cut Line= 3
      2225474.98     13828875.04        2225575.       13828625.
        2225725.       13828425.
#Sta/Elev= 30
  4725.5  907.47  4779.4  904.26  4788.8   903.4  4800.9  900.18  4810.2  900.28
  4833.2  900.58  4842.7   900.1  4848.1   899.1  4854.8     897  4901.9  893.82
  4914.9  893.43  4962.5  890.47    4980  888.51  4980.9  886.87  4981.4  886.37
  4989.3  886.37  4989.8  886.87  5016.7   887.6  5044.8  889.17  5052.1  890.11
  5058.3  891.65  5066.7   892.6  5072.9  894.05  5094.8  896.29  5144.8   904.1
  5151.1  904.48  5166.7  907.35  5172.9  907.55  5202.1  911.02  5244.8  914.44
#Mann= 5 ,-1 , 0
  4725.5     .12       0  4810.2     .07       0  4914.9     .12       0
  4980.9     .05       0  4989.8     .12       0
Bank Sta=4980.9,4989.8
XS Rating Curve= 0 ,0
Exp/Cntr=0.3,0.1

Type RM Length L Ch R = 1 ,27352   ,434,434,434
BEGIN DESCRIPTION:
Elm Creek 2 60.0
END DESCRIPTION:
XS GIS Cut Line= 3
      2225825.02     13829074.97        2225875.       13828975.
      2225975.01     13828624.97
#Sta/Elev= 30
  4888.5   907.6  4891.3   907.6  4896.8  906.19  4902.4  905.65  4919.2  902.67
  4933.2  901.34  4955.5  897.29  4963.9  894.72  4977.9  887.83  4986.3  885.17
  4987.4  884.11  4987.9  883.61  4995.8  883.61  4996.3  884.11  4997.5   884.5
  5022.4  884.89  5031.5  885.79  5123.8  889.35  5135.5  889.62  5145.9  889.19
  5162.8     891  5196.6   891.9  5208.3  892.93  5235.6  894.06  5274.6  897.35
  5281.1  898.75  5308.4  901.65  5333.1   903.8  5347.4  904.48  5364.3  905.85
#Mann= 3 ,-1 , 0
  4888.5     .12       0  4987.4     .05       0  4996.3     .12       0
Bank Sta=4987.4,4996.3
XS Rating Curve= 0 ,0
Exp/Cntr=0.3,0.1

Type RM Length L Ch R = 1 ,26918   ,443,443,443
BEGIN DESCRIPTION:
Elm Creek 2 59.0
END DESCRIPTION:
XS GIS Cut Line= 3
      2226225.01     13829224.98        2226275.       13829075.
      2226324.99     13828725.04
#Sta/Elev= 30
  4841.9  911.59  4844.5  911.59  4852.4  910.11    4884  905.69  4894.6  903.49
  4905.1  901.94  4926.2  897.08  4936.7  894.49  4947.3  889.74  4957.8  883.25
  4968.4  880.62  4978.9  878.87    4985   878.4  4985.5   877.9  4993.5   877.9
    4994   878.4  5002.5  878.58  5020.2  882.19  5030.3  883.62  5050.5  885.56
  5080.8   886.6  5116.4  885.78  5141.4  885.74  5171.7  888.16    5202   891.5
  5242.4  894.23  5292.9  899.29  5313.1  902.09  5333.3   904.1  5353.5  905.21
#Mann= 4 ,-1 , 0
  4841.9     .12       0    4985     .05       0    4994     .12       0
  5116.4     .07       0
Bank Sta=4985,4994
XS Rating Curve= 0 ,0
Exp/Cntr=0.3,0.1

Type RM Length L Ch R = 1 ,26475   ,465,465,465
BEGIN DESCRIPTION:
Elm Creek 2 58.0
END DESCRIPTION:
XS GIS Cut Line= 3
      2226625.01     13829274.96        2226675.       13829125.
        2226625.     13828724.98
#Sta/Elev= 30
  4836.8   899.5  4868.4  895.95  4910.5  892.68  4934.6   889.3  4942.2   888.6
  4952.7  883.14  4963.2  880.44  4984.3  879.22  4992.2  877.91  5000.4  877.71
  5000.9  877.21  5008.9  877.21  5009.4  877.71    5015  877.72  5025.1  879.49
  5037.7  878.52  5055.3  878.74  5085.6  882.01  5092.8  882.28    5146  882.63
  5192.3   886.1  5236.7  889.58  5256.9  892.18  5274.5  895.05  5297.2  896.22
  5327.4  898.54  5355.2  900.15  5360.2   899.9  5364.4  900.43    5398  903.01
#Mann= 7 ,-1 , 0
  4836.8     .12       0  4934.6    .035       0  5000.4    .035       0
  5009.4    .035       0  5092.8     .07       0  5192.3    .035       0
  5364.4     .07       0
Bank Sta=5000.4,5009.4
XS Rating Curve= 0 ,0
Exp/Cntr=0.3,0.1

Type RM Length L Ch R = 1 ,26010   ,451,451,451
BEGIN DESCRIPTION:
Elm Creek 2 57.0
END DESCRIPTION:
XS GIS Cut Line= 3
        2227125.       13829175.        2227125.       13829075.
      2226824.99     13828724.98
#Sta/Elev= 30
  4895.6  889.46  4915.6  888.42  4925.6   887.4  4955.6  882.79  4965.6  878.34
  4975.6  874.76  4985.6     874  4988.6  873.23  4989.1  872.73  4997.2  872.73
  4997.7  873.23  5002.7  874.22  5009.3  873.89    5017  874.61  5031.3  874.23
  5052.1  875.71  5074.1  878.47  5087.8  878.64  5137.7  877.38  5187.4  880.19
  5228.5  882.37  5279.3  886.58  5300.2  887.47  5307.9  888.45  5314.4  888.48
  5364.4  892.35  5414.3  895.16  5428.6  896.87  5439.7  897.17  5456.6   898.1
#Mann= 6 ,-1 , 0
  4895.6    .035       0  4988.6    .035       0  4997.7    .035       0
  5187.4     .07       0  5228.5    .035       0  5439.7     .12       0
Bank Sta=4988.6,4997.7
XS Rating Curve= 0 ,0
Exp/Cntr=0.3,0.1

Type RM Length L Ch R = 1 ,25559   ,481,481,481
BEGIN DESCRIPTION:
Elm Creek 2 56.0
END DESCRIPTION:
XS GIS Cut Line= 3
        2227525.     13829074.98        2227525.       13828925.
      2227475.01     13828725.03
#Sta/Elev= 30
  4849.7  884.55  4869.7  883.45  4909.7  880.68  4919.7  879.56  4939.7  876.07
  4949.7  873.24  4959.7  870.77  4985.1   866.8  4985.6   866.3  4993.8   866.3
  4994.3   866.8  4997.2  867.29  5002.3  867.29    5010  868.18  5017.7  868.56
  5040.9  870.99  5058.9  871.11  5082.1  873.73  5092.4  876.06  5100.2  877.34
  5105.3  877.88  5110.9  879.03  5123.4   881.3  5133.7  882.74  5141.4  884.81
  5146.6  885.11  5182.6  889.66  5187.8  889.78  5195.5   890.6  5205.8  890.88
#Mann= 4 ,-1 , 0
  4849.7    .035       0  4985.1    .035       0  4994.3    .035       0
  5110.9     .07       0
Bank Sta=4985.1,4994.3
XS Rating Curve= 0 ,0
Exp/Cntr=0.3,0.1