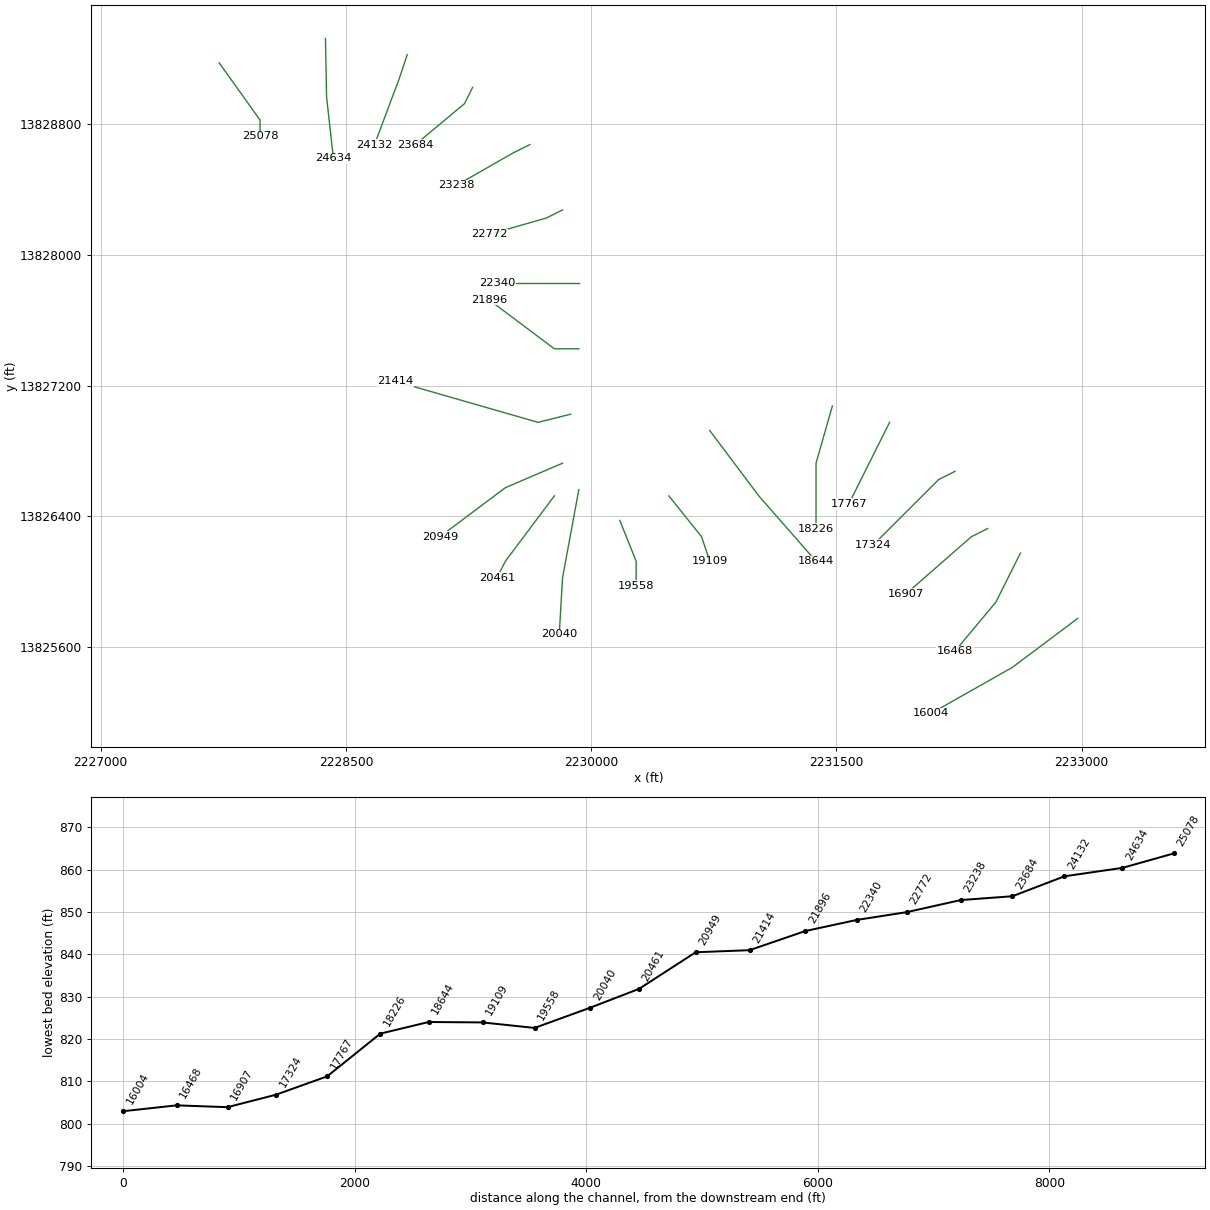
HEC-RAS study Elm Creek 2.prj: Elm Creek 2 Base Level Engineering

--- Elm Creek 2.g01 (geometry) --- (continued)

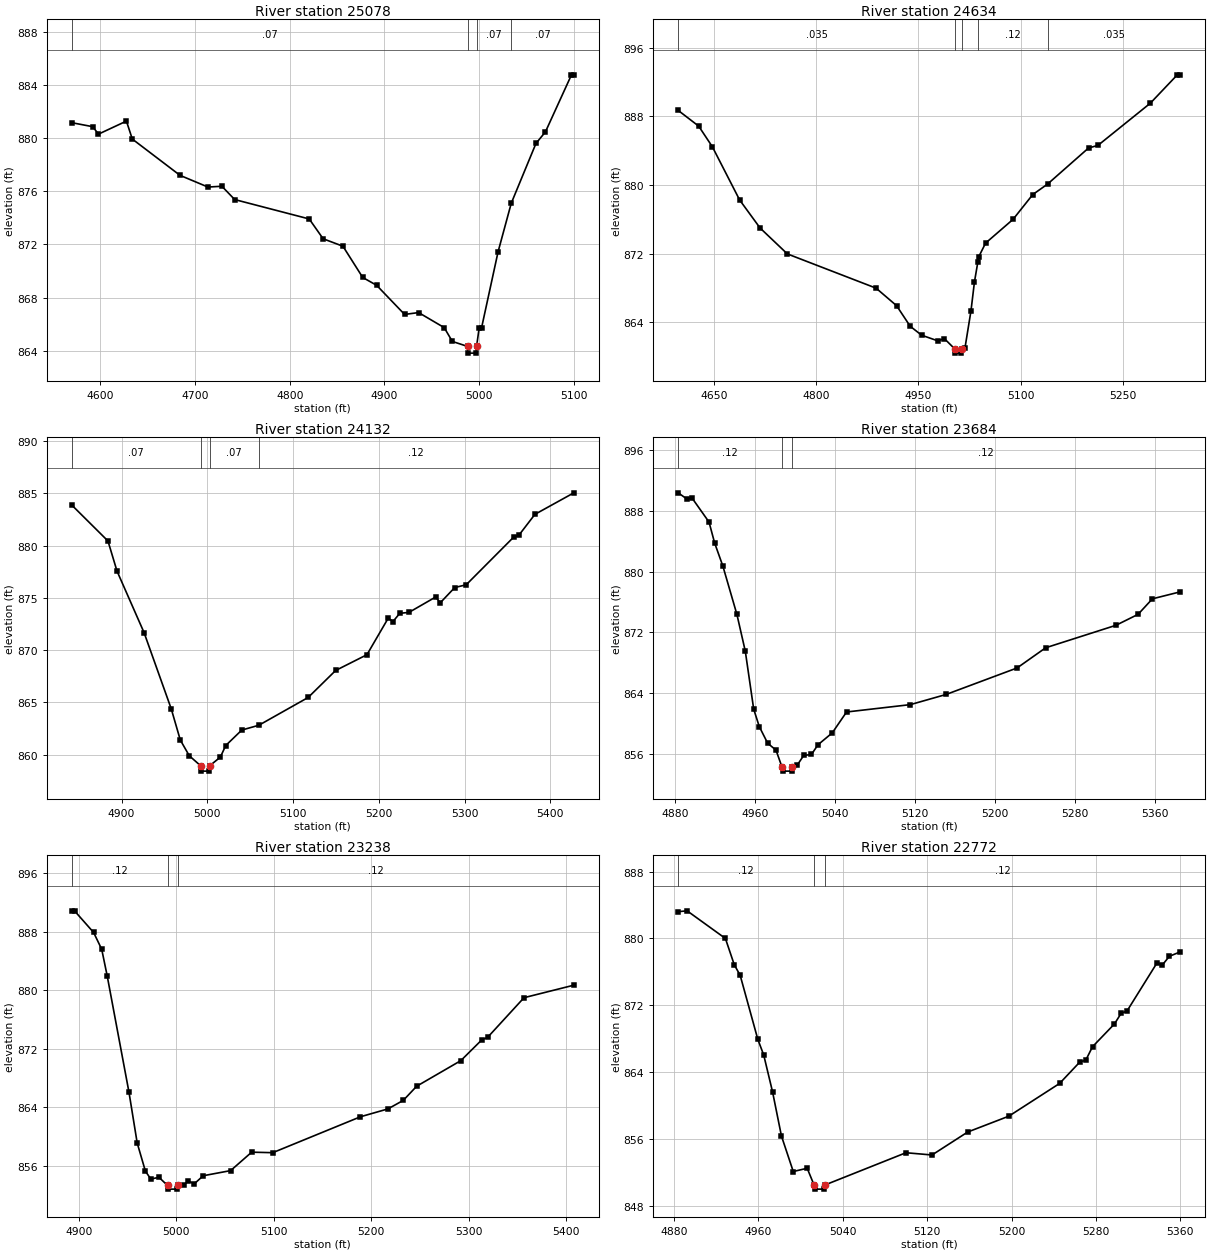
Type RM Length L Ch R = 1 ,25078   ,444,444,444
BEGIN DESCRIPTION:
Elm Creek 2 55.0
END DESCRIPTION:
XS GIS Cut Line= 3
      2227725.02     13829174.98        2227975.       13828825.
        2227975.     13828724.99
#Sta/Elev= 30
  4569.9  881.16    4592  880.86  4598.1   880.3  4627.6  881.28  4633.8  879.93
  4684.2   877.2  4713.7  876.32  4728.4  876.38  4741.9  875.38  4820.6  873.92
  4835.3  872.43  4856.2  871.87  4877.1  869.52  4891.8  868.93  4921.3  866.74
  4936.1  866.88  4963.1  865.75  4971.7  864.71    4988  864.33  4988.5  863.83
  4996.8  863.83  4997.3  864.33    5000  865.71  5002.5  865.71    5020  871.45
  5033.9   875.1    5060   879.6    5070  880.47  5097.5  884.76    5100  884.76
#Mann= 4 ,-1 , 0
  4569.9     .07       0    4988     .05       0  4997.3     .07       0
  5033.9     .07       0
Bank Sta=4988,4997.3
XS Rating Curve= 0 ,0
Exp/Cntr=0.3,0.1

Type RM Length L Ch R = 1 ,24634   ,502,502,502
BEGIN DESCRIPTION:
Elm Creek 2 54.0
END DESCRIPTION:
XS GIS Cut Line= 3
        2228375.       13829325.      2228381.78     13828966.52
      2228423.47     13828591.27
#Sta/Elev= 30
    4598   888.7    4628  886.87    4648  884.47    4688  878.27    4718     875
    4758  871.98  4888.1  867.99  4918.1  865.95  4938.1  863.55  4954.8  862.51
  4978.2  861.86  4988.3   862.1  5003.3  860.92  5003.8  860.42  5012.9  860.42
  5013.4  860.92  5018.4  861.03  5027.2  865.35  5032.3  868.73  5037.3  871.05
  5038.6  871.65  5048.6  873.24  5088.9  876.01  5117.8   878.9  5139.5  880.12
  5199.5  884.32  5213.4  884.63  5290.1  889.54  5329.7  892.85  5334.1  892.85
#Mann= 5 ,-1 , 0
    4598    .035       0  5003.3    .035       0  5013.4    .035       0
  5037.3     .12       0  5139.5    .035       0
Bank Sta=5003.3,5013.4
XS Rating Curve= 0 ,0
Exp/Cntr=0.3,0.1

Type RM Length L Ch R = 1 ,24132   ,448,448,448
BEGIN DESCRIPTION:
Elm Creek 2 53.0
END DESCRIPTION:
XS GIS Cut Line= 3
        2228875.       13829225.        2228825.       13829075.
      2228675.01     13828675.01
#Sta/Elev= 30
    4842  883.88  4884.2  880.44  4894.7  877.57  4926.3  871.67    4958  864.37
  4968.5   861.4    4979  859.89  4992.4  858.92  4992.9  858.42  5002.1  858.42
  5002.6  858.92  5015.2  859.76  5021.5  860.87  5040.2  862.35  5060.1  862.81
  5117.6  865.47  5149.6  868.05  5186.1  869.56    5211  873.07  5216.4  872.73
  5224.4  873.52  5235.1  873.61  5266.2  875.08  5271.6  874.53  5288.5  875.99
  5301.8  876.25    5357   880.8  5363.2  880.99  5381.9  882.99  5427.3  885.05
#Mann= 4 ,-1 , 0
    4842     .07       0  4992.4     .05       0  5002.6     .07       0
  5060.1     .12       0
Bank Sta=4992.4,5002.6
XS Rating Curve= 0 ,0
Exp/Cntr=0.3,0.1

Type RM Length L Ch R = 1 ,23684   ,446,446,446
BEGIN DESCRIPTION:
Elm Creek 2 52.0
END DESCRIPTION:
XS GIS Cut Line= 3
      2229275.01     13829025.02        2229225.       13828925.
      2228925.03     13828675.02
#Sta/Elev= 30
  4883.1  890.38  4891.5  889.59  4897.1  889.66  4913.9  886.53  4919.5  883.78
  4927.8  880.71  4941.8  874.36  4950.2  869.51  4958.6  861.88  4964.2  859.58
  4972.6  857.39  4980.9  856.49    4987  854.22  4987.5  853.72  4996.8  853.72
  4997.3  854.22  5002.1   854.5  5008.6  855.78  5016.4  855.92  5022.9  857.19
  5037.2  858.76  5051.5  861.51  5115.3  862.48  5151.1  863.82  5222.1  867.31
  5250.7  869.97    5321  872.93  5343.1  874.37  5357.5  876.42  5385.4  877.34
#Mann= 3 ,-1 , 0
  4883.1     .12       0    4987     .05       0  4997.3     .12       0
Bank Sta=4987,4997.3
XS Rating Curve= 0 ,0
Exp/Cntr=0.3,0.1

Type RM Length L Ch R = 1 ,23238   ,466,466,466
BEGIN DESCRIPTION:
Elm Creek 2 51.0
END DESCRIPTION:
XS GIS Cut Line= 3
        2229625.       13828675.        2229525.       13828625.
      2229175.01     13828425.01
#Sta/Elev= 30
  4892.8  890.85  4895.6  890.85  4915.2  887.89  4923.5   885.6  4929.1  881.98
  4951.5  866.04  4959.9  859.12  4968.3  855.28  4973.9  854.19  4982.2  854.44
    4991  853.32  4991.5  852.82  5000.9  852.82  5001.4  853.32  5007.5   853.4
  5012.5  853.93  5018.3  853.53  5027.6  854.65  5055.7  855.35  5077.3  857.87
  5098.9   857.8  5188.9  862.71    5217  863.78  5232.8  864.95  5246.5  866.88
  5291.8  870.38  5313.4  873.23  5319.2  873.55  5356.6  878.98  5407.7  880.69
#Mann= 3 ,-1 , 0
  4892.8     .12       0    4991     .05       0  5001.4     .12       0
Bank Sta=4991,5001.4
XS Rating Curve= 0 ,0
Exp/Cntr=0.3,0.1

Type RM Length L Ch R = 1 ,22772   ,432,432,432
BEGIN DESCRIPTION:
Elm Creek 2 50.0
END DESCRIPTION:
XS GIS Cut Line= 3
      2229824.97     13828274.99        2229725.       13828225.
      2229374.98     13828124.99
#Sta/Elev= 30
  4884.1  883.21  4892.5  883.31  4928.8     880  4937.2  876.85  4942.8  875.58
  4959.5  867.92  4965.1  866.04  4973.5  861.61  4981.9  856.34  4993.1  852.08
  5006.3  852.47  5012.8  850.47  5013.3  849.97  5022.7  849.97  5023.2  850.47
  5099.9  854.33  5124.6  854.06  5158.4  856.81  5197.4  858.71  5245.5  862.63
    5265  865.24  5270.2  865.39  5276.7  867.03  5297.5  869.76    5304  871.07
  5309.2  871.27  5337.8  877.07    5343  876.84  5349.5  877.86  5359.9   878.4
#Mann= 3 ,-1 , 0
  4884.1     .12       0  5012.8     .05       0  5023.2     .12       0
Bank Sta=5012.8,5023.2
XS Rating Curve= 0 ,0
Exp/Cntr=0.3,0.1

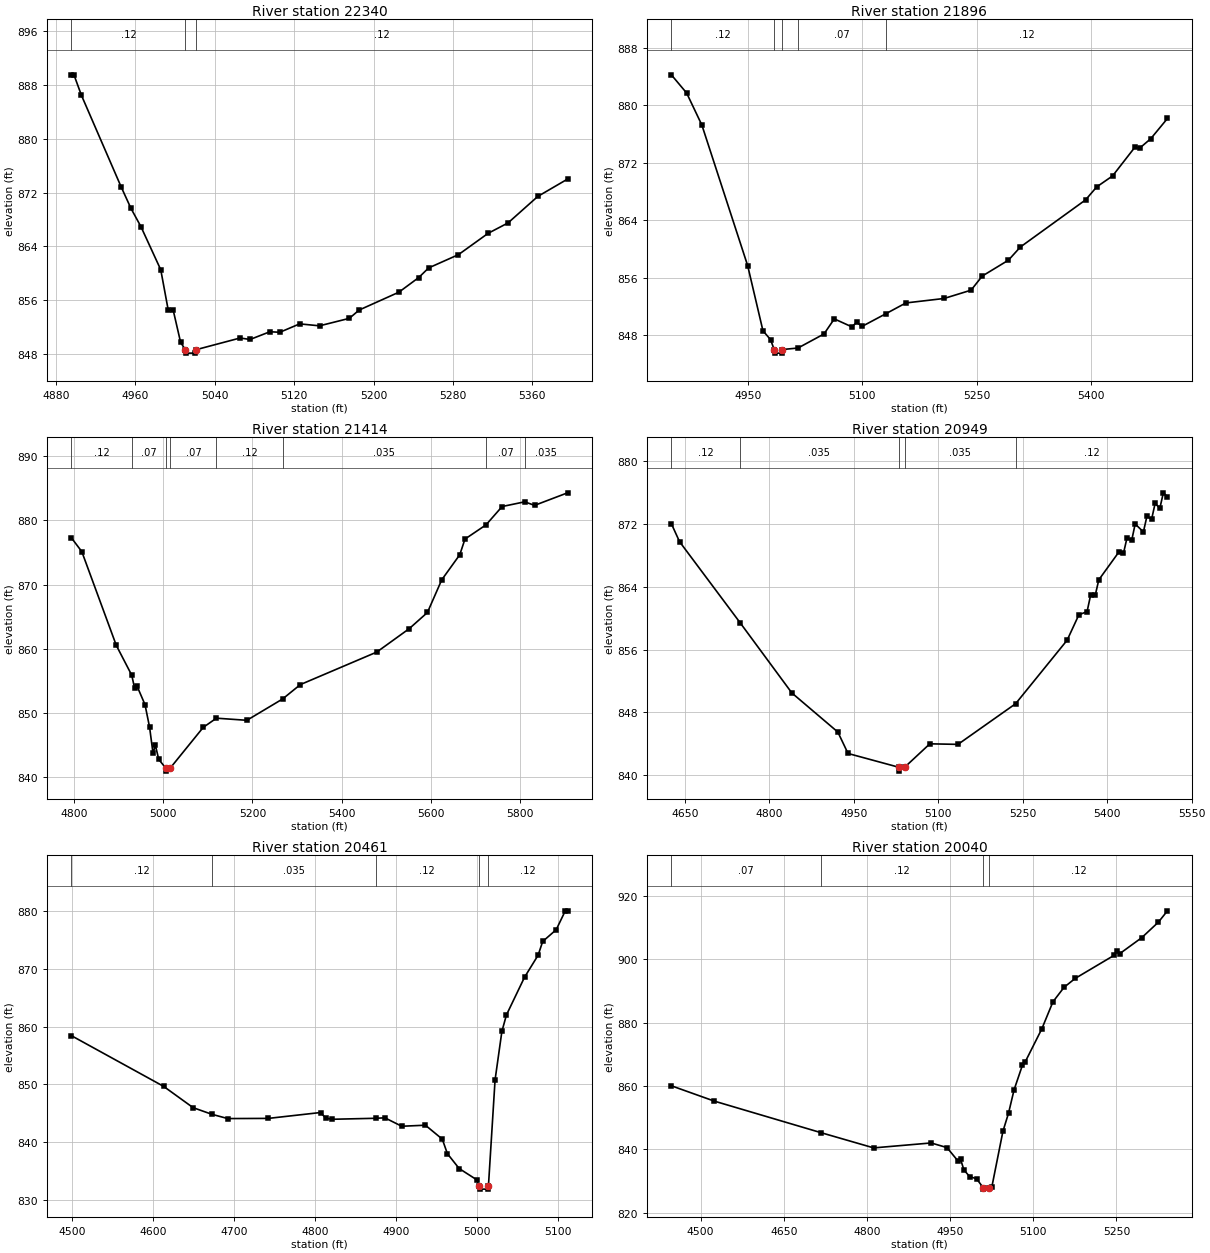
Type RM Length L Ch R = 1 ,22340   ,444,444,444
BEGIN DESCRIPTION:
Elm Creek 2 49.0
END DESCRIPTION:
XS GIS Cut Line= 3
      2229925.04       13827825.        2229825.       13827825.
      2229425.04       13827825.
#Sta/Elev= 30
  4895.5  889.51    4898  889.51  4905.5  886.48  4945.5  872.87  4955.5  869.64
  4965.5  866.94  4985.5  860.52    4993  854.54    4998  854.54  5005.5  849.73
  5010.3  848.63  5010.8  848.13  5020.3  848.13  5020.8  848.63  5065.5  850.38
  5075.5  850.16  5095.5  851.31  5105.5  851.23  5125.5  852.48  5145.5  852.19
  5175.5   853.3  5185.5  854.54  5225.5  857.19  5245.5  859.37  5255.5   860.8
  5285.5  862.77  5315.5  865.95  5335.5  867.49  5365.5  871.43  5395.5  874.01
#Mann= 3 ,-1 , 0
  4895.5     .12       0  5010.3     .05       0  5020.8     .12       0
Bank Sta=5010.3,5020.8
XS Rating Curve= 0 ,0
Exp/Cntr=0.3,0.1

Type RM Length L Ch R = 1 ,21896   ,482,482,482
BEGIN DESCRIPTION:
Elm Creek 2 48.0
END DESCRIPTION:
XS GIS Cut Line= 3
      2229924.99       13827425.        2229775.       13827425.
        2229375.       13827725.
#Sta/Elev= 30
    4850  884.27    4870  881.74    4890  877.27    4950  857.69    4970  848.63
    4980  847.38  4984.7  846.01  4985.2  845.51  4994.7  845.51  4995.2  846.01
  5015.9  846.22    5050  848.18  5063.5  850.28  5086.5  849.17  5092.7  849.79
    5100  849.24  5131.1     851  5157.3   852.5  5207.3  853.12  5242.7  854.28
  5257.3  856.24  5291.7  858.46  5307.3  860.29  5392.7  866.85  5407.3  868.66
  5428.1  870.19  5457.3  874.18  5463.5  874.05  5478.1  875.37    5500  878.19
#Mann= 5 ,-1 , 0
    4850     .12       0  4984.7     .05       0  4995.2     .12       0
  5015.9     .07       0  5131.1     .12       0
Bank Sta=4984.7,4995.2
XS Rating Curve= 0 ,0
Exp/Cntr=0.3,0.1

Type RM Length L Ch R = 1 ,21414   ,465,465,465
BEGIN DESCRIPTION:
Elm Creek 2 47.0
END DESCRIPTION:
XS GIS Cut Line= 3
      2229874.97     13827024.99        2229675.       13826975.
       2228803.9     13827225.75
#Sta/Elev= 30
  4794.2  877.24  4817.4  875.11  4894.7  860.54  4929.4   855.9  4935.9  853.84
  4941.1  854.23  4959.1  851.33  4969.4  847.81  4977.1  843.75  4982.3  845.03
    4990   842.8  5005.4  841.49  5005.9  840.99    5016  841.49  5089.7  847.79
  5119.3  849.22  5187.6  848.89  5267.8  852.21  5307.5  854.44    5479   859.5
  5551.8  863.14  5592.5  865.65  5624.7  870.74  5665.1  874.63  5676.7  877.06
  5723.9  879.27    5760  882.12  5810.7  882.85  5832.8   882.3  5906.8  884.25
#Mann= 8 ,-1 , 0
  4794.2     .12       0  4929.4     .07       0  5005.4     .05       0
    5016     .07       0  5119.3     .12       0  5267.8    .035       0
  5723.9     .07       0  5810.7    .035       0
Bank Sta=5005.4,5016
XS Rating Curve= 0 ,0
Exp/Cntr=0.3,0.1

Type RM Length L Ch R = 1 ,20949   ,488,488,488
BEGIN DESCRIPTION:
Elm Creek 2 46.0
END DESCRIPTION:
XS GIS Cut Line= 3
      2229825.01       13826725.        2229475.       13826575.
        2229075.       13826275.
#Sta/Elev= 30
  4626.2  872.04  4640.7  869.75  4748.2  859.42  4840.2  850.46  4921.8  845.48
  4939.9  842.75  5029.7     841  5030.2   840.5  5040.5     841  5085.1  843.98
  5135.1  843.91  5237.4  849.09  5328.9  857.19  5349.7  860.42  5364.3  860.83
  5370.5   862.9  5378.9  862.95  5385.1  864.88  5420.5   868.4  5428.9  868.25
  5435.1   870.2  5443.5   869.9  5449.7     872  5464.3  870.99  5470.5  872.96
  5478.9  872.61  5485.1  874.62  5493.5     874  5499.7  875.97    5507  875.49
#Mann= 5 ,-1 , 0
  4626.2     .12       0  4748.2    .035       0  5029.7    .035       0
  5040.5    .035       0  5237.4     .12       0
Bank Sta=5029.7,5040.5
XS Rating Curve= 0 ,0
Exp/Cntr=0.3,0.1

Type RM Length L Ch R = 1 ,20461   ,421,421,421
BEGIN DESCRIPTION:
Elm Creek 2 45.0
END DESCRIPTION:
XS GIS Cut Line= 3
      2229775.01     13826525.01        2229475.       13826125.
      2229425.01     13826025.02
#Sta/Elev= 30
  4499.7  858.44  4613.3  849.67  4649.7  845.98  4672.9  844.83  4692.4  844.09
  4742.4  844.12    4807  845.14  4813.3  844.14  4821.6  843.97  4874.7  844.14
  4886.2  844.22    4907  842.76  4936.2  842.94    4957  840.53  4963.3  838.01
  4977.8  835.44  4999.7  833.47  5002.4  832.37  5002.9  831.87  5013.4  831.87
  5013.9  832.37  5022.1  850.79  5030.5  859.18  5036.1  862.03  5058.4  868.56
  5075.2  872.39  5080.8  874.76  5097.5   876.8  5108.7  880.07  5111.5  880.07
#Mann= 5 ,-1 , 0
  4499.7     .12       0  4672.9    .035       0  4874.7     .12       0
  5002.4     .05       0  5013.9     .12       0
Bank Sta=5002.4,5013.9
XS Rating Curve= 0 ,0
Exp/Cntr=0.3,0.1

Type RM Length L Ch R = 1 ,20040   ,482,482,482
BEGIN DESCRIPTION:
Elm Creek 2 44.0
END DESCRIPTION:
XS GIS Cut Line= 3
      2229924.52     13826563.84        2229825.       13826025.
       2229804.7     13825678.85
#Sta/Elev= 30
  4447.3  860.04  4524.8   855.2  4717.5  845.23  4812.2  840.44  4915.8     842
  4944.4  840.54  4963.7  836.42  4968.8  836.89  4974.9  833.51  4985.1  831.41
  4997.8  830.69  5009.5  827.93    5010  827.43    5021  827.93  5025.3  828.12
  5045.3  845.68  5055.4   851.4  5065.4  858.77  5080.5  866.56  5085.5  867.59
  5115.5  878.03  5135.5  886.54  5155.5  891.11  5175.6  893.92  5245.7   901.2
  5251.1  902.68  5256.1  901.75  5295.8   906.8  5325.8   911.7    5342  915.25
#Mann= 4 ,-1 , 0
  4447.3     .07       0  4717.5     .12       0  5009.5     .05       0
    5021     .12       0
Bank Sta=5009.5,5021
XS Rating Curve= 0 ,0
Exp/Cntr=0.3,0.1

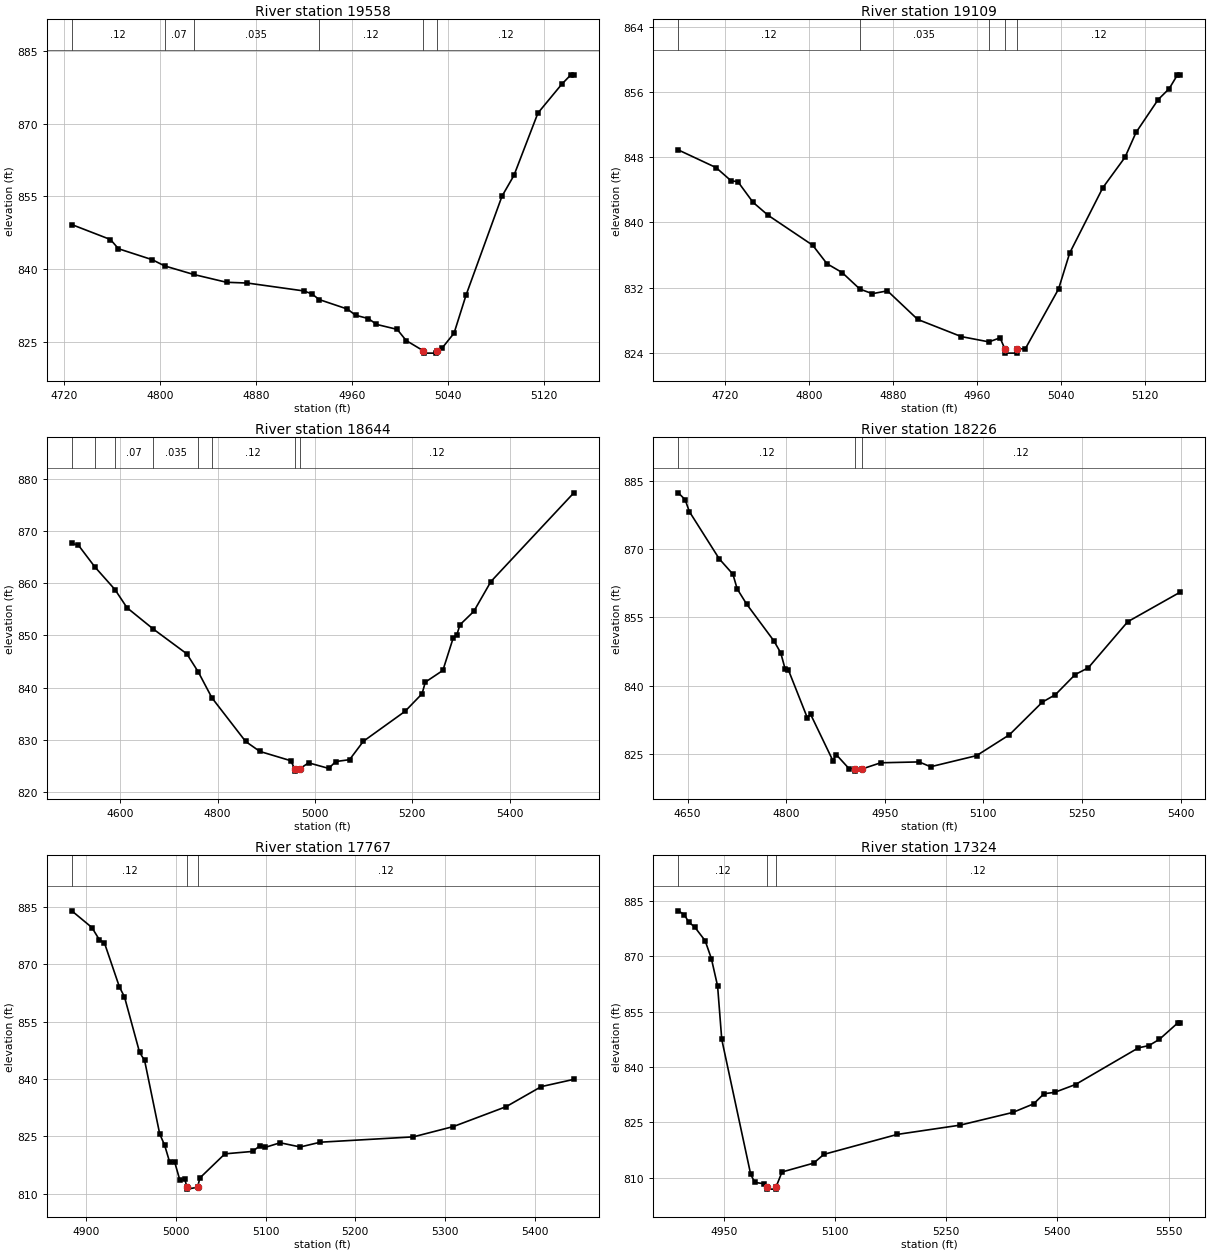
Type RM Length L Ch R = 1 ,19558   ,449,449,449
BEGIN DESCRIPTION:
Elm Creek 2 43.0
END DESCRIPTION:
XS GIS Cut Line= 3
        2230175.     13826374.99        2230275.       13826125.
        2230275.     13825975.05
#Sta/Elev= 30
  4726.1  849.17  4758.4  846.08  4765.1  844.18  4793.4  841.91  4803.6  840.64
  4827.9  838.87  4855.3  837.26  4872.8   837.1    4920  835.47  4926.7  834.85
  4932.6   833.7  4956.3  831.73    4963  830.46  4973.8  829.77  4980.5  828.57
  4997.8  827.54  5005.3  825.24  5019.5  823.14    5020  822.64  5030.6  822.64
  5031.1  823.14  5035.3  823.68  5045.3  826.77  5055.3  834.61  5085.3  855.02
  5095.3  859.32  5115.3  872.18  5135.3  878.16  5142.8  880.07  5145.3  880.07
#Mann= 6 ,-1 , 0
  4726.1     .12       0  4803.6     .07       0  4827.9    .035       0
  4932.6     .12       0  5019.5     .05       0  5031.1     .12       0
Bank Sta=5019.5,5031.1
XS Rating Curve= 0 ,0
Exp/Cntr=0.3,0.1

Type RM Length L Ch R = 1 ,19109   ,465,465,465
BEGIN DESCRIPTION:
Elm Creek 2 42.0
END DESCRIPTION:
XS GIS Cut Line= 3
      2230474.99     13826525.01        2230675.       13826275.
      2230725.01     13826124.98
#Sta/Elev= 30
  4675.3   848.9  4711.3  846.73  4725.7   845.1  4732.1     845  4746.5  842.47
  4760.9  840.87  4803.4  837.19    4817  834.92  4831.4  833.84  4848.3  831.81
  4860.2  831.24  4874.6  831.59  4903.4  828.08    4945  825.97  4971.3  825.32
  4981.9  825.82  4986.5  824.44    4987  823.94  4997.6  823.94  4998.1  824.44
    5006  824.49  5037.6  831.81  5048.2  836.23  5079.8  844.26  5100.9  847.99
  5111.4  851.04  5132.5  855.08    5143  856.42  5150.9  858.12  5153.6  858.12
#Mann= 5 ,-1 , 0
  4675.3     .12       0  4848.3    .035       0  4971.3     .12       0
  4986.5     .05       0  4998.1     .12       0
Bank Sta=4986.5,4998.1
XS Rating Curve= 0 ,0
Exp/Cntr=0.3,0.1

Type RM Length L Ch R = 1 ,18644   ,418,418,418
BEGIN DESCRIPTION:
Elm Creek 2 41.0
END DESCRIPTION:
XS GIS Cut Line= 3
      2230725.03     13826924.96        2231025.       13826525.
      2231375.03     13826124.97
#Sta/Elev= 30
  4500.5  867.59    4514  867.27  4547.9   863.1  4589.4  858.75    4614  855.29
  4668.2   851.2  4736.9  846.47  4760.4  843.01  4788.5  838.05  4857.7  829.71
  4886.9  827.81  4950.5  826.03  4958.1  824.54  4958.6  824.04  4969.9  824.54
  4986.9  825.63  5028.4  824.56  5042.7  825.87  5071.2  826.23  5099.6  829.75
  5185.1  835.47  5220.2  838.84  5226.8  841.06  5262.9   843.3  5283.8  849.41
  5291.4  850.04    5298  852.03  5326.5   854.6  5361.6   860.3    5532  877.27
#Mann= 8 ,-1 , 0
  4500.5     .07       0  4547.9    .035       0  4589.4     .07       0
  4668.2    .035       0  4760.4     .07       0  4788.5     .12       0
  4958.1     .05       0  4969.9     .12       0
Bank Sta=4958.1,4969.9
XS Rating Curve= 0 ,0
Exp/Cntr=0.3,0.1

Type RM Length L Ch R = 1 ,18226   ,459,459,459
BEGIN DESCRIPTION:
Elm Creek 2 40.0
END DESCRIPTION:
XS GIS Cut Line= 3
        2231475.     13827074.99        2231375.       13826725.
        2231375.       13826325.
#Sta/Elev= 30
  4635.7  882.33  4646.1  880.86  4652.6  878.22  4698.1  867.85  4718.9  864.48
  4725.4  861.26  4739.7  857.94  4781.3  849.85  4791.7  847.22  4798.2  843.77
  4803.4  843.45    4832  833.04  4837.2  833.73    4871  823.59  4876.2   824.9
  4895.7  821.82  4904.1  821.79  4904.6  821.29  4915.9  821.79  4943.8  823.12
  5002.2  823.31  5019.7  822.25  5089.7  824.69  5139.7  829.27  5189.7  836.42
  5209.7  838.07  5239.7  842.47  5259.7  843.96  5319.7  854.06  5399.7  860.56
#Mann= 3 ,-1 , 0
  4635.7     .12       0  4904.1     .05       0  4915.9     .12       0
Bank Sta=4904.1,4915.9
XS Rating Curve= 0 ,0
Exp/Cntr=0.3,0.1

Type RM Length L Ch R = 1 ,17767   ,443,443,443
BEGIN DESCRIPTION:
Elm Creek 2 39.0
END DESCRIPTION:
XS GIS Cut Line= 3
      2231825.01     13826975.03        2231775.       13826875.
      2231575.02     13826475.04
#Sta/Elev= 30
  4884.3  883.92  4906.7  879.56  4915.1  876.34  4920.7  875.52  4937.4     864
    4943  861.43  4959.8  846.94  4965.4  844.82  4982.2  825.64  4987.7  822.68
  4993.3  818.26  4998.9  818.26  5004.5  813.67  5010.1  813.79  5012.6  811.71
  5013.1  811.21  5024.4  811.71  5026.9  814.12  5054.8  820.43  5085.6  821.06
    5094  822.58  5099.6  822.12  5116.3  823.32  5138.7  822.22    5161  823.47
  5264.5  824.86  5309.2  827.56  5367.9  832.75    5407  837.99  5443.3  839.89
#Mann= 3 ,-1 , 0
  4884.3     .12       0  5012.6     .05       0  5024.4     .12       0
Bank Sta=5012.6,5024.4
XS Rating Curve= 0 ,0
Exp/Cntr=0.3,0.1

Type RM Length L Ch R = 1 ,17324   ,417,417,417
BEGIN DESCRIPTION:
Elm Creek 2 38.0
END DESCRIPTION:
XS GIS Cut Line= 3
      2232224.96     13826674.98        2232125.       13826625.
      2231725.03     13826225.03
#Sta/Elev= 30
  4888.5  882.39  4896.8  881.34  4902.4  879.38  4910.8  877.97  4924.8  874.28
  4933.2  869.43  4941.6  861.98  4947.2  847.52  4986.3  810.84  4991.9  808.69
  5003.8  808.35  5008.4  807.37  5008.9  806.87  5019.8  806.87  5020.3  807.37
  5028.5  811.52    5071  813.91  5085.1  816.31  5184.1  821.72    5269  824.24
  5339.7  827.67    5368  830.01  5382.1  832.77  5396.2  833.12  5424.5  835.26
  5509.4  845.21  5523.5  845.82  5537.7  847.52  5562.4  851.96  5565.9  851.96
#Mann= 3 ,-1 , 0
  4888.5     .12       0  5008.4     .05       0  5020.3     .12       0
Bank Sta=5008.4,5020.3
XS Rating Curve= 0 ,0
Exp/Cntr=0.3,0.1

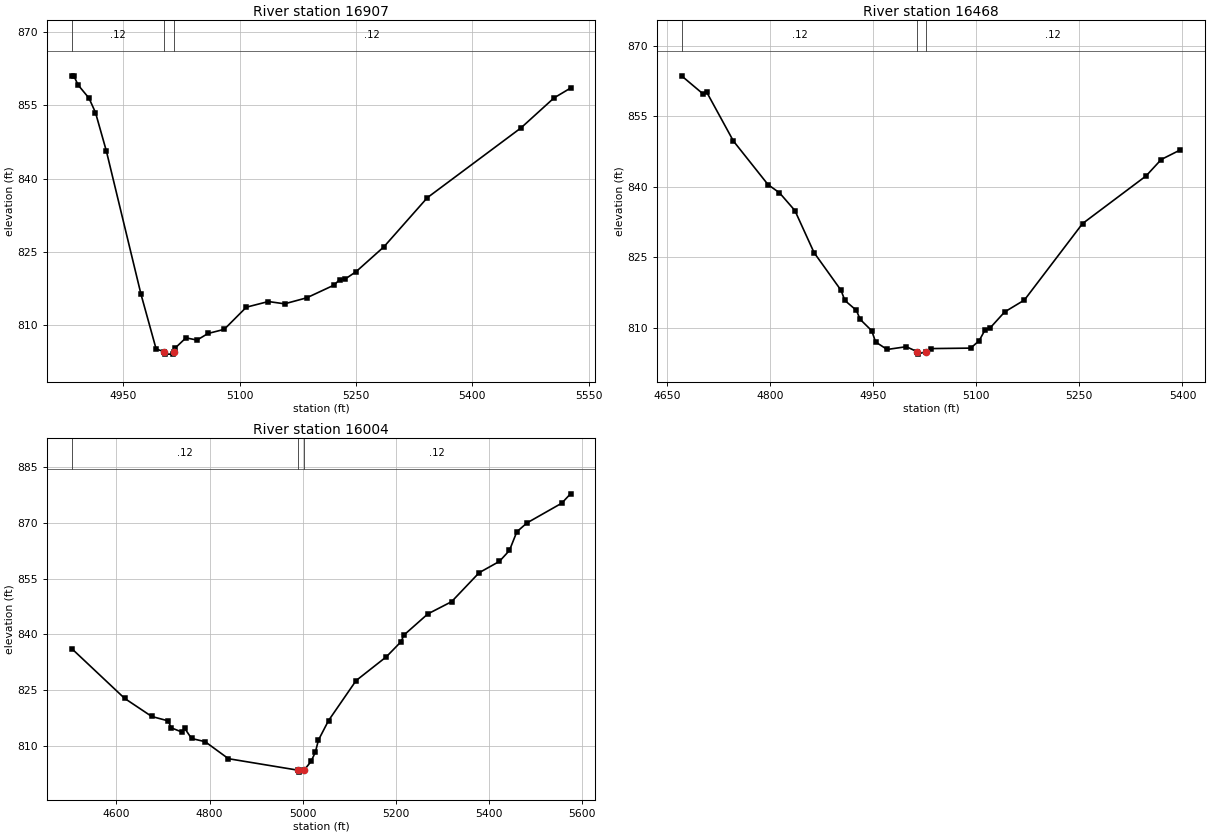
Type RM Length L Ch R = 1 ,16907   ,439,439,439
BEGIN DESCRIPTION:
Elm Creek 2 37.0
END DESCRIPTION:
XS GIS Cut Line= 3
      2232425.03     13826325.01        2232325.       13826275.
      2231925.03     13825925.03
#Sta/Elev= 30
  4883.3  861.09  4886.1  861.09  4891.7   859.2  4905.7  856.51  4914.1  853.54
  4928.1  845.65  4972.8  816.21  4992.3  804.98  5002.9  804.44  5003.4  803.94
  5014.3  803.94  5014.8  804.44  5016.5  805.14  5030.7  807.28    5045  806.83
  5059.2  808.18  5080.1  809.03  5108.6  813.58    5137  814.74  5157.9  814.27
  5186.4   815.5  5221.5   818.1  5229.1  819.26  5235.7  819.33    5250  820.86
    5286  825.98    5342  836.07  5462.6  850.38  5505.3  856.55  5526.6  858.57
#Mann= 3 ,-1 , 0
  4883.3     .12       0  5002.9     .05       0  5014.8     .12       0
Bank Sta=5002.9,5014.8
XS Rating Curve= 0 ,0
Exp/Cntr=0.3,0.1

Type RM Length L Ch R = 1 ,16468   ,464,464,464
BEGIN DESCRIPTION:
Elm Creek 2 36.0
END DESCRIPTION:
XS GIS Cut Line= 3
      2232624.99     13826174.98        2232475.       13825875.
        2232225.       13825575.
#Sta/Elev= 30
  4671.2   863.6  4701.9  859.82  4707.5   860.2  4746.6  849.73    4797  840.45
  4813.7   838.7  4836.1  834.93    4864  825.97  4903.2  817.96  4908.8  815.79
  4925.5   813.7  4931.1  811.76  4947.9  809.35  4953.5  806.96  4970.3  805.36
  4998.2  805.95  5014.3  804.87  5014.8  804.37  5026.3  804.87  5034.6  805.55
  5091.9  805.65  5104.2  807.23  5112.7  809.51  5120.5     810  5141.3  813.35
    5170  815.88  5254.6  832.15    5347  842.29  5369.1  845.79  5397.1  847.85
#Mann= 3 ,-1 , 0
  4671.2     .12       0  5014.3     .05       0  5026.3     .12       0
Bank Sta=5014.3,5026.3
XS Rating Curve= 0 ,0
Exp/Cntr=0.3,0.1

Type RM Length L Ch R = 1 ,16004   ,472,472,472
BEGIN DESCRIPTION:
Elm Creek 2 35.0
END DESCRIPTION:
XS GIS Cut Line= 3
      2232975.01     13825775.01        2232575.       13825475.
      2232078.55     13825193.94
#Sta/Elev= 30
  4504.1  836.23  4617.7  822.83    4676  817.95  4711.4  816.76  4717.7   814.9
  4740.6  813.77  4746.8  814.75  4761.4  812.03  4790.6  811.17  4840.6  806.59
  4990.8  803.48  4991.3  802.98  5002.8  803.48  5017.8  805.85  5027.1  808.34
  5033.7   811.6  5055.3  816.83  5114.5   827.6  5179.4     834    5211  838.06
    5217  839.83  5268.4  845.53  5319.4  848.82  5378.6  856.62  5421.9  859.65
  5443.5  862.59  5459.4  867.62  5481.1     870  5555.7  875.31  5574.6  877.83
#Mann= 3 ,-1 , 0
  4504.1     .12       0  4990.8     .05       0  5002.8     .12       0
Bank Sta=4990.8,5002.8
XS Rating Curve= 0 ,0
Exp/Cntr=0.3,0.1