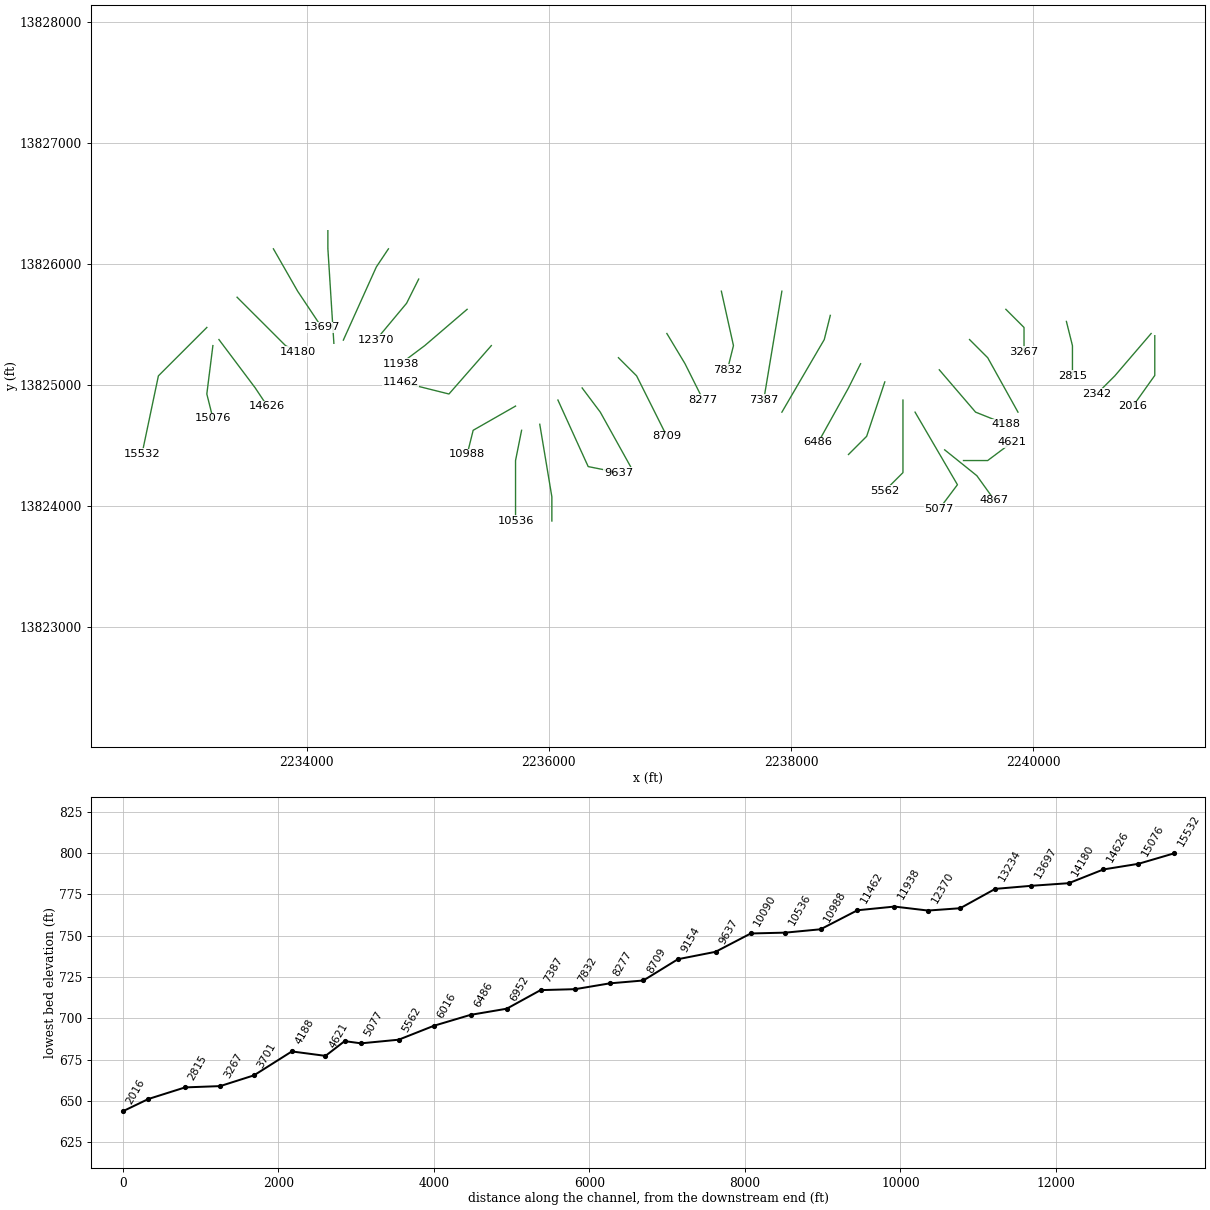
HEC-RAS study Elm Creek 2.prj: Elm Creek 2 Base Level Engineering

--- Elm Creek 2.g01 (geometry) --- (continued)

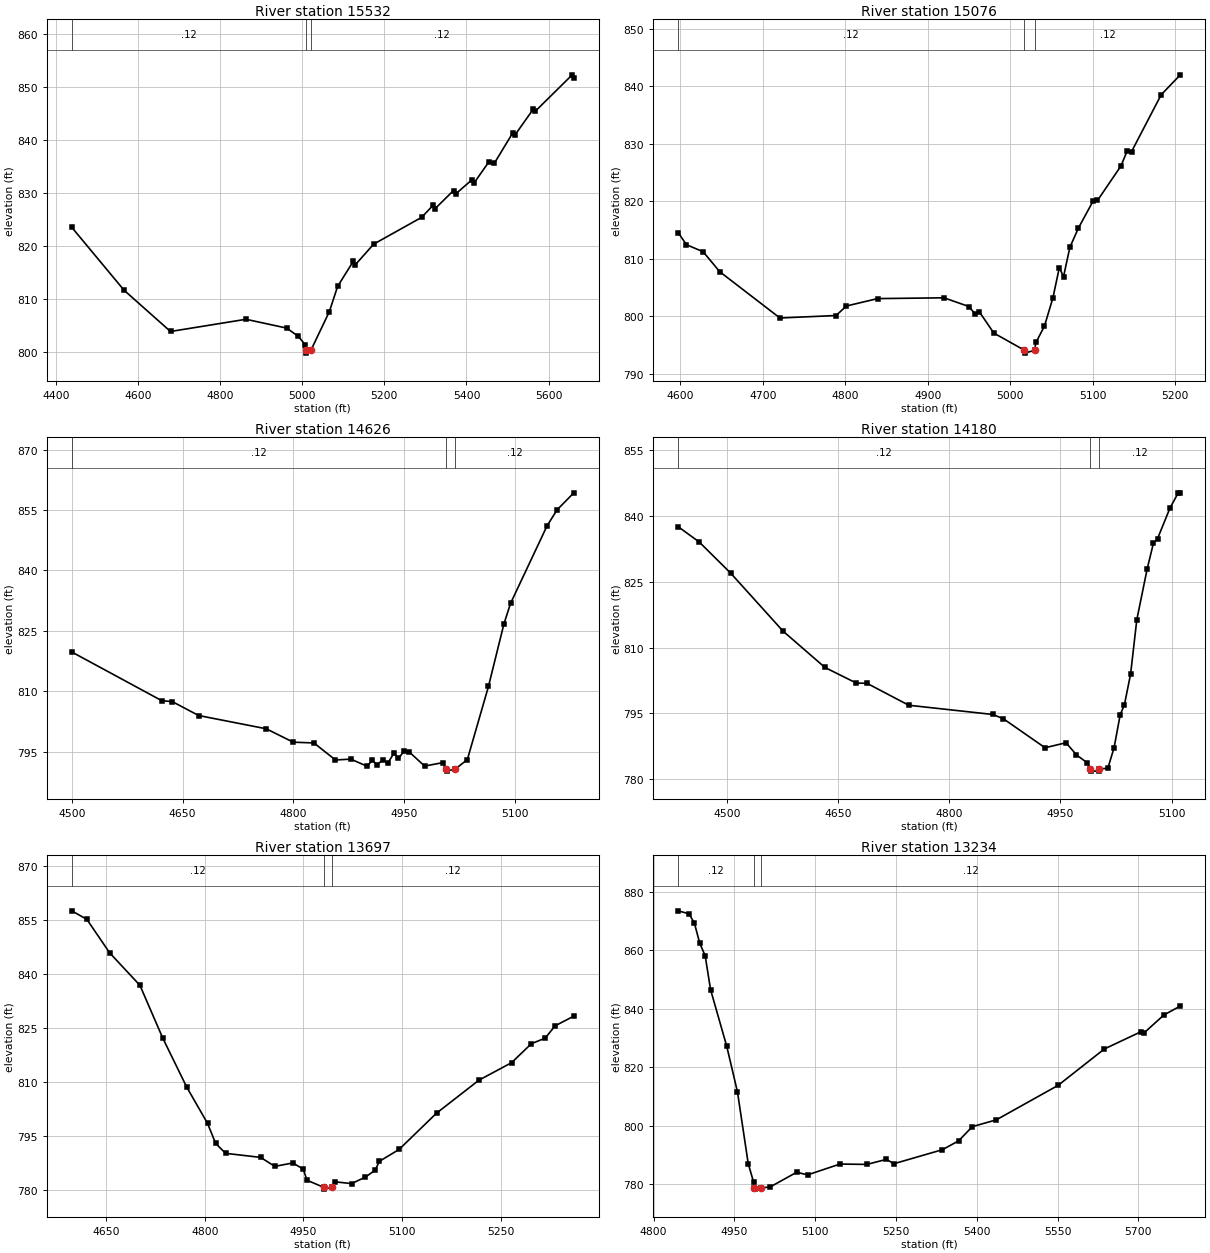
Type RM Length L Ch R = 1 ,15532   ,456,456,456
BEGIN DESCRIPTION:
Elm Creek 2 34.0
END DESCRIPTION:
XS GIS Cut Line= 3
      2233174.98     13825474.98        2232775.       13825075.
      2232639.96     13824432.29
#Sta/Elev= 30
  4439.1  823.58  4566.4  811.72  4679.5  803.94  4863.3  806.24  4962.3  804.58
  4990.6  803.03  5007.3  801.45  5008.9  800.36  5009.4  799.86  5021.1  800.36
  5066.1  807.66  5086.5  812.46  5124.3  817.14  5129.4  816.52  5174.2  820.41
  5290.9  825.46  5318.6  827.71  5323.8  827.11  5368.5  830.51  5373.6  829.86
  5413.3  832.53  5418.4  831.92  5454.4   835.9  5468.2  835.69    5513  841.42
  5518.1  840.98  5562.9  845.88    5568  845.49  5657.5  852.33  5661.5  851.69
#Mann= 3 ,-1 , 0
  4439.1     .12       0  5008.9     .05       0  5021.1     .12       0
Bank Sta=5008.9,5021.1
XS Rating Curve= 0 ,0
Exp/Cntr=0.3,0.1

Type RM Length L Ch R = 1 ,15076   ,450,450,450
BEGIN DESCRIPTION:
Elm Creek 2 33.0
END DESCRIPTION:
XS GIS Cut Line= 3
        2233225.     13825324.97        2233175.       13824925.
      2233224.99     13824725.04
#Sta/Elev= 30
  4597.3   814.5  4607.3  812.41  4627.5  811.19  4647.7  807.71  4720.7  799.67
  4788.8   800.1  4801.3  801.75  4839.1  803.04  4919.8  803.18    4950  801.66
  4957.6  800.34  4962.6  800.76  4980.2  797.05  5017.4  794.06  5017.9  793.56
  5029.7  794.06  5031.3  795.41  5041.6  798.24  5051.9  803.16  5059.7  808.43
  5064.8  806.85  5072.5  811.96  5082.8  815.29  5100.9  820.06    5106   820.1
  5134.4  826.09  5142.1  828.73  5147.3  828.59  5183.3  838.49  5206.5  841.95
#Mann= 3 ,-1 , 0
  4597.3     .12       0  5017.4     .05       0  5029.7     .12       0
Bank Sta=5017.4,5029.7
XS Rating Curve= 0 ,0
Exp/Cntr=0.3,0.1

Type RM Length L Ch R = 1 ,14626   ,446,446,446
BEGIN DESCRIPTION:
Elm Creek 2 32.0
END DESCRIPTION:
XS GIS Cut Line= 3
      2233275.01     13825374.98        2233575.       13824975.
      2233675.02     13824824.96
#Sta/Elev= 30
  4499.8  819.74  4621.7  807.65  4636.2   807.4  4671.7  803.96  4763.3  800.67
  4799.8  797.34  4827.9  797.15  4857.1  792.92  4877.9  793.13  4899.8  791.37
  4907.1  792.82  4913.3  791.73  4921.7     793  4927.9  792.11  4936.2  794.55
  4942.5   793.3  4949.8  795.07  4957.1  794.91  4977.9   791.4  5002.8  792.27
  5007.1  790.65  5007.6  790.15  5019.4  790.65  5035.8  793.02  5064.4  811.18
  5085.4  826.74  5094.4  831.84    5144  851.14  5157.5  855.07  5180.1  859.27
#Mann= 3 ,-1 , 0
  4499.8     .12       0  5007.1     .05       0  5019.4     .12       0
Bank Sta=5007.1,5019.4
XS Rating Curve= 0 ,0
Exp/Cntr=0.3,0.1

Type RM Length L Ch R = 1 ,14180   ,483,483,483
BEGIN DESCRIPTION:
Elm Creek 2 31.0
END DESCRIPTION:
XS GIS Cut Line= 3
      2233424.99     13825725.01        2233825.       13825325.
        2233925.       13825275.
#Sta/Elev= 30
  4434.3  837.55  4462.6  834.07    4505  826.98  4575.7  813.75  4632.3  805.46
  4674.7   801.9  4688.9  801.86  4745.4  796.85  4858.6  794.75  4872.7  793.81
  4929.3  787.16  4957.6   788.3  4971.7  785.53  4985.9  783.76  4990.3  782.33
  4990.8  781.83  5002.2  781.83  5002.7  782.33    5014  782.48  5022.4  787.16
  5030.7  794.69  5036.3  796.91  5044.7  803.95  5053.1  816.35  5067.1  827.95
  5075.5  833.79  5081.1  834.84  5097.8  841.79    5109  845.28  5111.8  845.28
#Mann= 3 ,-1 , 0
  4434.3     .12       0  4990.3     .05       0  5002.7     .12       0
Bank Sta=4990.3,5002.7
XS Rating Curve= 0 ,0
Exp/Cntr=0.3,0.1

Type RM Length L Ch R = 1 ,13697   ,463,463,463
BEGIN DESCRIPTION:
Elm Creek 2 30.0
END DESCRIPTION:
XS GIS Cut Line= 3
        2233725.       13826125.        2233925.       13825775.
      2234125.02     13825474.98
#Sta/Elev= 30
  4597.7  857.56  4620.7  855.18  4655.3  845.89  4701.4  836.86  4735.9  822.28
  4772.6  808.57  4804.3  798.48  4816.5  792.95  4831.7  790.18  4884.9  789.06
  4906.5  786.56  4933.9  787.51  4949.7  785.81  4955.5  782.71  4980.9  780.74
  4981.4  780.24  4993.3  780.74  4997.9  782.28  5023.3  781.77  5044.4  783.59
  5059.4  785.53  5065.4  787.95  5095.5  791.25  5152.5  801.34  5217.1  810.52
  5266.7  815.37  5296.8  820.65  5317.8  822.18  5332.8   825.6  5361.4  828.31
#Mann= 3 ,-1 , 0
  4597.7     .12       0  4980.9     .05       0  4993.3     .12       0
Bank Sta=4980.9,4993.3
XS Rating Curve= 0 ,0
Exp/Cntr=0.3,0.1

Type RM Length L Ch R = 1 ,13234   ,450,450,450
BEGIN DESCRIPTION:
Elm Creek 2 29.0
END DESCRIPTION:
XS GIS Cut Line= 3
        2234175.     13826274.96        2234175.       13826125.
      2234224.36     13825344.22
#Sta/Elev= 30
  4845.7  873.49  4865.7  872.48  4875.7  869.29  4885.7  862.38  4895.7  858.16
  4905.7  846.58  4935.7  827.24  4955.7  811.59  4975.7  787.04  4985.7  780.76
    4987  778.88  4987.5  778.38  4999.4  778.88  5015.7  779.06  5065.8  784.15
  5085.8  783.24    5146  786.95  5196.1  786.83  5232.3  788.55  5246.2  787.06
  5336.3  791.86  5366.4  794.89  5391.7  799.73  5436.5  802.07  5551.1  813.85
  5636.9  826.27  5705.5  832.22  5710.5  831.73  5747.2  837.85    5778  840.96
#Mann= 3 ,-1 , 0
  4845.7     .12       0    4987     .05       0  4999.4     .12       0
Bank Sta=4987,4999.4
XS Rating Curve= 0 ,0
Exp/Cntr=0.3,0.1

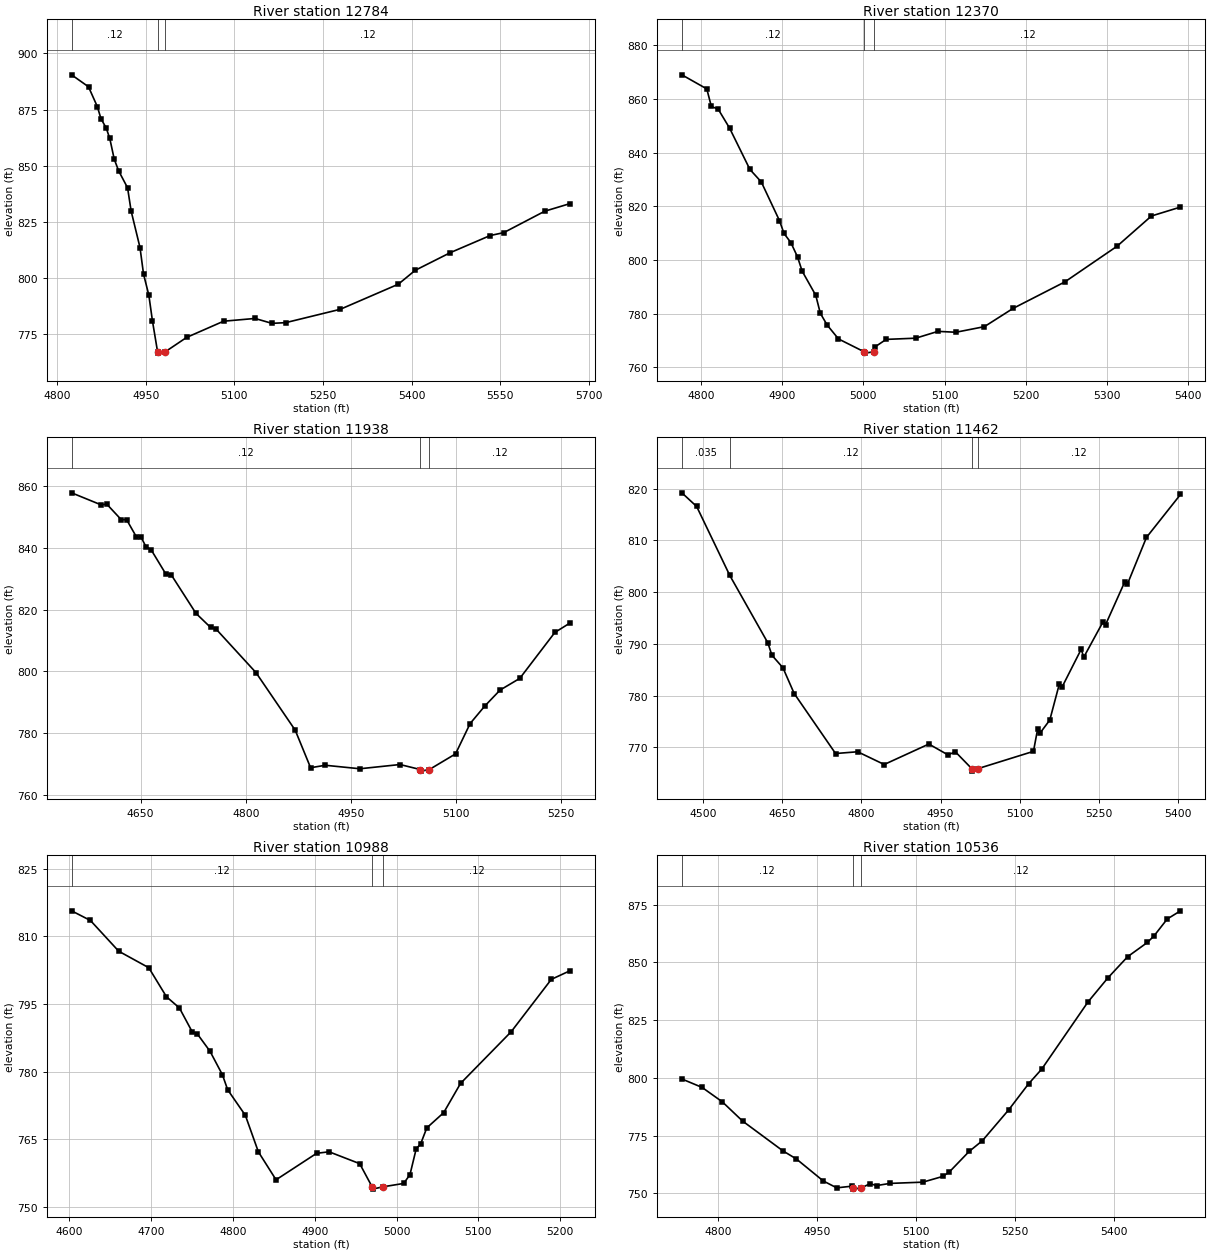
Type RM Length L Ch R = 1 ,12784   ,414,414,414
BEGIN DESCRIPTION:
Elm Creek 2 28.0
END DESCRIPTION:
XS GIS Cut Line= 3
        2234675.     13826125.01        2234575.       13825975.
      2234302.55     13825370.33
#Sta/Elev= 30
  4824.7  890.43  4853.3  885.11  4868.3  876.25  4874.3  870.98  4883.3  866.75
  4889.3  862.12  4896.8  852.95  4904.3  847.72  4919.4  840.18  4925.4  829.88
  4940.4  813.64  4946.4  801.82  4955.4  792.41  4961.4  781.12  4970.2  767.17
  4970.7  766.67  4982.6  767.17  5019.3  773.66  5081.8  780.86    5135  782.09
  5163.6  779.91  5186.8  780.22  5279.2  786.16  5377.4  797.32    5406   803.5
  5465.6  811.38  5532.7  818.95  5555.8  820.26  5625.2  829.79  5668.2  833.19
#Mann= 3 ,-1 , 0
  4824.7     .12       0  4970.2     .05       0  4982.6     .12       0
Bank Sta=4970.2,4982.6
XS Rating Curve= 0 ,0
Exp/Cntr=0.3,0.1

Type RM Length L Ch R = 1 ,12370   ,432,432,432
BEGIN DESCRIPTION:
Elm Creek 2 27.0
END DESCRIPTION:
XS GIS Cut Line= 3
        2234925.     13825874.99        2234825.       13825675.
      2234575.01     13825375.01
#Sta/Elev= 30
  4776.4  868.99  4807.1  863.74  4812.7  857.19  4821.1   856.2  4835.1  849.16
  4860.2  833.72  4874.2  829.07  4896.6  814.65  4902.2  809.86  4910.6  806.48
  4918.9  801.08  4924.5  795.84  4941.3  786.81  4946.9  780.12  4955.3  775.74
  4969.3  770.55  5000.9  765.76  5001.4  765.26  5013.4  765.76  5013.7  767.47
    5028  770.38  5064.4  770.83  5091.8  773.37  5113.9  773.04    5149  775.13
  5184.2  781.91    5248  791.79  5312.4  805.11  5354.7  816.37  5390.5   819.7
#Mann= 3 ,-1 , 0
  4776.4     .12       0  5000.9     .05       0  5013.4     .12       0
Bank Sta=5000.9,5013.4
XS Rating Curve= 0 ,0
Exp/Cntr=0.3,0.1

Type RM Length L Ch R = 1 ,11938   ,476,476,476
BEGIN DESCRIPTION:
Elm Creek 2 26.0
END DESCRIPTION:
XS GIS Cut Line= 3
      2235325.01     13825625.01        2234975.       13825325.
      2234774.99       13825175.
#Sta/Elev= 30
  4551.7   857.9    4594  853.98  4601.7  854.27  4622.5   849.2  4630.2  849.18
  4643.9  843.69    4651  843.43  4657.6  840.47  4665.3  839.37  4686.2  831.53
  4693.9  831.28    4729  818.84  4749.8  814.28  4757.5  813.78  4814.6  799.62
  4870.6  780.93  4892.5  768.77  4913.4  769.57  4962.8  768.44    5020  769.81
  5049.2  768.17  5049.7  767.67  5061.7  768.17  5099.2  773.26    5120   783.1
  5140.8  788.75  5162.7  793.95  5190.8  797.74  5240.8  812.63  5262.7  815.74
#Mann= 3 ,-1 , 0
  4551.7     .12       0  5049.2     .05       0  5061.7     .12       0
Bank Sta=5049.2,5061.7
XS Rating Curve= 0 ,0
Exp/Cntr=0.3,0.1

Type RM Length L Ch R = 1 ,11462   ,474,474,474
BEGIN DESCRIPTION:
Elm Creek 2 25.0
END DESCRIPTION:
XS GIS Cut Line= 3
      2235525.01     13825325.01        2235175.       13824925.
      2234775.03     13825024.99
#Sta/Elev= 30
  4460.4  819.18  4488.4  816.54  4551.1  803.22  4623.2  790.19  4630.8  787.82
  4651.7  785.39    4673  780.42  4751.3  768.83  4793.1  769.17  4843.4  766.71
  4927.9  770.66  4963.9  768.58  4978.2  769.15  5008.9  765.93  5009.4  765.43
  5021.4  765.93  5125.9  769.25  5133.7  773.49  5138.8  772.84  5156.8  775.29
  5174.9  782.27    5180  781.66  5216.1  788.93  5221.3  787.47  5257.3  794.21
  5262.5  793.74  5298.6  801.96  5303.7  801.53  5339.8  810.57  5404.2  818.86
#Mann= 4 ,-1 , 0
  4460.4    .035       0  4551.1     .12       0  5008.9     .05       0
  5021.4     .12       0
Bank Sta=5008.9,5021.4
XS Rating Curve= 0 ,0
Exp/Cntr=0.3,0.1

Type RM Length L Ch R = 1 ,10988   ,452,452,452
BEGIN DESCRIPTION:
Elm Creek 2 24.0
END DESCRIPTION:
XS GIS Cut Line= 3
      2235724.98     13824824.99        2235375.       13824625.
      2235325.01     13824425.05
#Sta/Elev= 30
    4603  815.66    4626  813.52  4660.6   806.7  4697.3  803.04  4718.9   796.6
  4734.7  794.12  4750.5  788.77  4756.3  788.43  4772.1  784.51  4787.3  779.28
  4793.7  775.96  4815.3  770.29  4831.2  762.19  4852.8  755.99  4902.4  761.87
  4917.6   762.2    4955  759.57  4970.2  754.42  4970.7  753.92    4983  754.42
  5008.7  755.18  5016.4  757.12  5024.1  762.91  5029.3  763.88    5037  767.51
  5057.6  770.88  5078.2  777.37  5140.1  788.84  5189.1  800.45  5212.2  802.39
#Mann= 3 ,-1 , 0
    4603     .12       0  4970.2     .05       0    4983     .12       0
Bank Sta=4970.2,4983
XS Rating Curve= 0 ,0
Exp/Cntr=0.3,0.1

Type RM Length L Ch R = 1 ,10536   ,446,446,446
BEGIN DESCRIPTION:
Elm Creek 2 23.0
END DESCRIPTION:
XS GIS Cut Line= 3
        2235775.     13824624.98        2235725.       13824375.
        2235725.     13823875.03
#Sta/Elev= 30
  4745.1  799.54  4775.7  795.89  4806.3  789.66  4836.9  781.36  4898.1  768.44
  4918.5  764.93  4959.2  755.42  4979.6  752.44  5002.5  753.17  5003.6  752.39
  5004.1  751.89  5016.4  752.39    5030  754.23    5040  753.43    5060  754.36
    5110  754.91    5140  757.38    5150   759.3    5180  768.19    5200  772.82
    5240  786.22    5270  797.45    5290  803.84    5360  832.88    5390  843.24
    5420  852.44    5450  858.62    5460  861.46    5480  868.76    5500  872.28
#Mann= 3 ,-1 , 0
  4745.1     .12       0  5003.6     .05       0  5016.4     .12       0
Bank Sta=5003.6,5016.4
XS Rating Curve= 0 ,0
Exp/Cntr=0.3,0.1

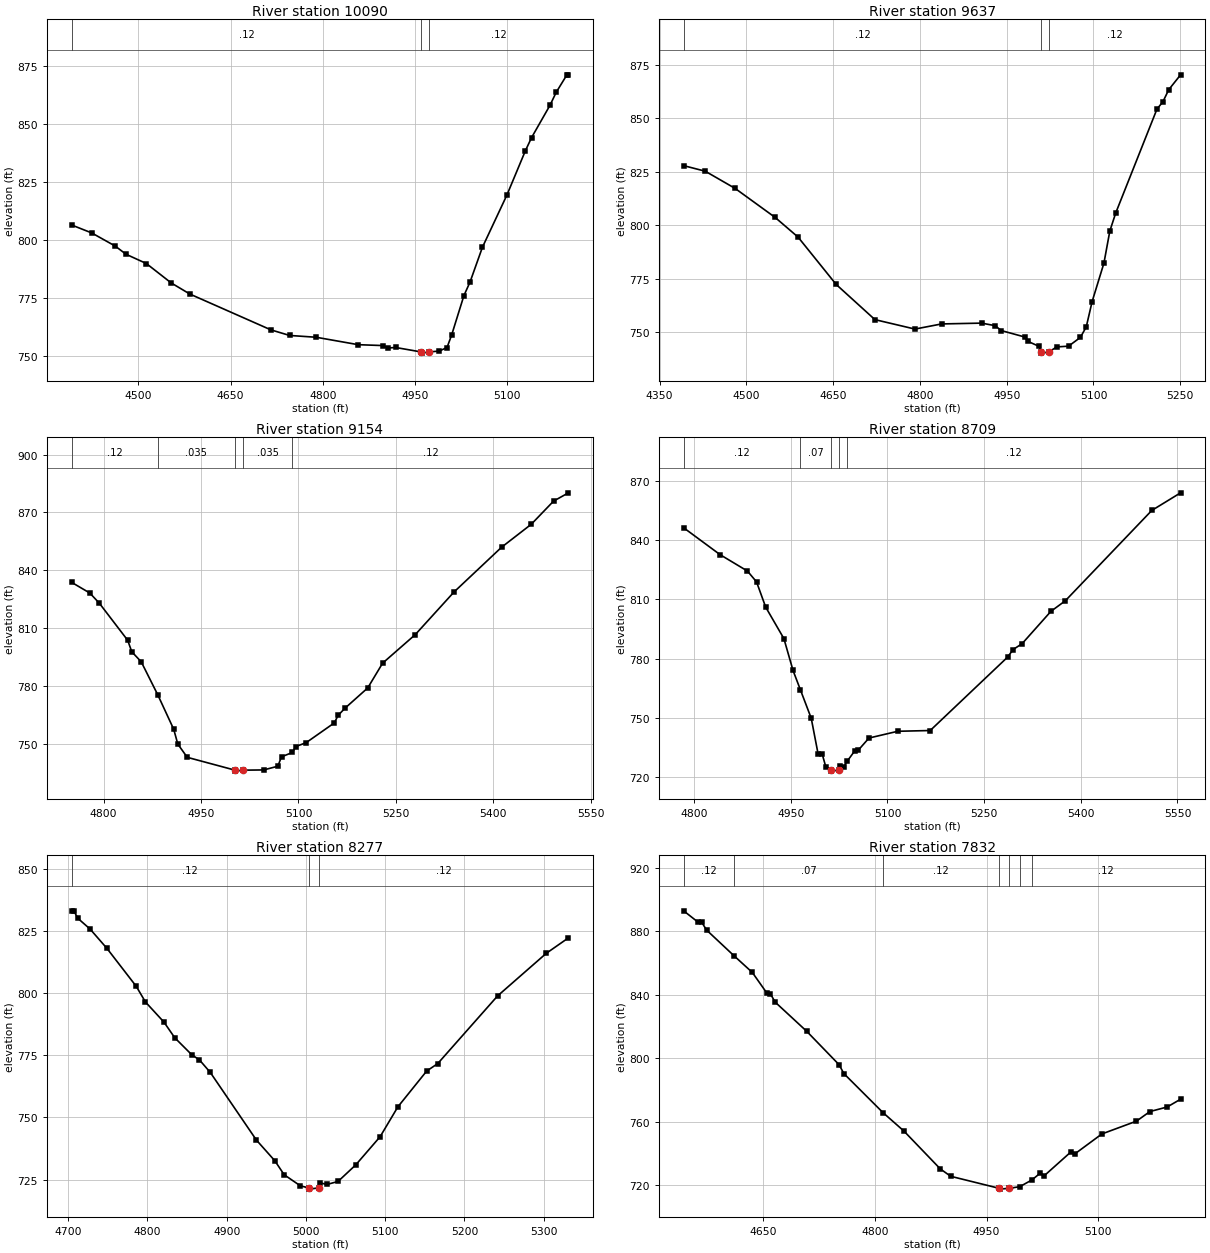
Type RM Length L Ch R = 1 ,10090   ,453,453,453
BEGIN DESCRIPTION:
Elm Creek 2 22.0
END DESCRIPTION:
XS GIS Cut Line= 3
        2235925.     13824675.01        2236025.       13824075.
        2236025.     13823874.99
#Sta/Elev= 30
  4391.2  806.52  4424.2  803.07  4462.2  797.45  4479.9  793.91  4512.9  789.93
  4553.4  781.57  4583.8  776.78  4715.6  761.38    4746  758.98  4789.1  758.21
  4857.6  755.01  4898.1  754.63  4905.7  753.58  4918.4  753.81  4960.1  751.88
  4960.6  751.38    4973  751.88  4989.4  752.28    5002  753.79  5009.5  759.16
  5029.5  776.14  5039.5  782.01  5059.5  796.87  5099.5  819.44  5129.5  838.46
  5139.5  844.08  5169.5  858.01  5179.5  863.54    5197   871.1  5199.5   871.1
#Mann= 3 ,-1 , 0
  4391.2     .12       0  4960.1     .05       0    4973     .12       0
Bank Sta=4960.1,4973
XS Rating Curve= 0 ,0
Exp/Cntr=0.3,0.1

Type RM Length L Ch R = 1 ,9637    ,483,483,483
BEGIN DESCRIPTION:
Elm Creek 2 21.0
END DESCRIPTION:
XS GIS Cut Line= 3
      2236074.99     13824875.03        2236325.       13824325.
      2236574.97     13824275.01
#Sta/Elev= 30
  4391.5  827.87  4428.9  825.26  4480.5  817.23  4549.7  803.67  4589.3  794.48
  4655.2  772.36  4722.2  755.92  4791.4  751.51  4837.5  753.91  4906.7  754.29
  4929.8  753.11  4940.8   750.8  4981.4  747.79  4986.9  745.74  5005.9  743.44
  5009.6  740.77  5010.1  740.27  5022.5  740.77  5036.5  743.17  5056.9  743.52
  5077.3  747.59  5087.5  752.48  5097.7  764.36  5118.1  782.33  5128.3  797.31
  5138.5  805.76  5209.8   854.3    5220  857.69  5230.2  863.38  5250.6   870.3
#Mann= 3 ,-1 , 0
  4391.5     .12       0  5009.6     .05       0  5022.5     .12       0
Bank Sta=5009.6,5022.5
XS Rating Curve= 0 ,0
Exp/Cntr=0.3,0.1

Type RM Length L Ch R = 1 ,9154    ,445,445,445
BEGIN DESCRIPTION:
Elm Creek 2 20.0
END DESCRIPTION:
XS GIS Cut Line= 3
      2236274.99     13824975.02        2236425.       13824775.
        2236675.       13824325.
#Sta/Elev= 30
  4750.7  833.76  4778.8   828.2  4793.4  822.96  4837.2  803.66  4843.4  797.74
    4858  792.51  4883.5  775.36    4908  757.51  4914.3  749.83  4928.8  742.97
  5002.3  736.31  5002.8  735.81  5015.2  736.31  5046.5  736.43  5068.2  738.35
  5073.9  743.24  5090.8   745.5  5095.7  748.54  5111.7  750.55  5155.2  760.83
  5160.9  764.68  5171.2  768.32  5206.6  778.97  5229.5  791.81  5279.8  806.63
  5339.3  828.69  5412.5  851.91  5458.3  863.86  5492.6  875.86  5515.5  880.16
#Mann= 5 ,-1 , 0
  4750.7     .12       0  4883.5    .035       0  5002.3    .035       0
  5015.2    .035       0  5090.8     .12       0
Bank Sta=5002.3,5015.2
XS Rating Curve= 0 ,0
Exp/Cntr=0.3,0.1

Type RM Length L Ch R = 1 ,8709    ,432,432,432
BEGIN DESCRIPTION:
Elm Creek 2 19.0
END DESCRIPTION:
XS GIS Cut Line= 3
        2236575.       13825225.        2236725.       13825075.
      2236974.98     13824575.04
#Sta/Elev= 30
  4783.7  846.27  4840.3  832.63  4882.7  824.33  4896.8  818.86    4911  806.06
  4939.3  790.07  4953.4  773.99  4964.8  764.21  4981.7   749.7  4992.3   731.7
  4998.6   731.7  5004.2  725.18  5011.7  723.42  5012.2  722.92  5024.6  723.42
  5026.6  725.66  5032.2   725.1  5037.5  727.96  5048.9  733.04  5054.5  733.47
  5071.3  739.69    5116  743.12  5166.3   743.5  5286.5  780.74  5294.9  784.54
  5308.9  787.52  5353.6   803.9    5376  809.28  5510.1  855.04  5554.8  863.98
#Mann= 5 ,-1 , 0
  4783.7     .12       0  4964.8     .07       0  5011.7     .05       0
  5024.6     .07       0  5037.5     .12       0
Bank Sta=5011.7,5024.6
XS Rating Curve= 0 ,0
Exp/Cntr=0.3,0.1

Type RM Length L Ch R = 1 ,8277    ,445,445,445
BEGIN DESCRIPTION:
Elm Creek 2 18.0
END DESCRIPTION:
XS GIS Cut Line= 3
      2236974.98     13825425.04        2237125.       13825175.
        2237275.     13824875.01
#Sta/Elev= 30
  4704.2  833.08  4707.2  833.08    4712  830.12  4727.6  825.76    4749  817.94
  4785.9  802.71  4797.5  796.43  4820.9  788.31  4834.5  782.03  4855.9  775.22
  4865.6  773.14  4879.2  768.15  4937.5   740.9  4960.8  732.56  4972.5  726.97
  4992.9  722.52  5003.3  721.68  5003.8  721.18  5016.3  721.68  5018.2  723.69
  5026.5  723.05  5040.5  724.27  5062.9  730.95  5093.6  742.27    5116  754.27
  5152.3  768.65  5166.3  771.66  5241.8  798.87  5303.3  816.01  5331.2  822.21
#Mann= 3 ,-1 , 0
  4704.2     .12       0  5003.3     .05       0  5016.3     .12       0
Bank Sta=5003.3,5016.3
XS Rating Curve= 0 ,0
Exp/Cntr=0.3,0.1

Type RM Length L Ch R = 1 ,7832    ,445,445,445
BEGIN DESCRIPTION:
Elm Creek 2 17.0
END DESCRIPTION:
XS GIS Cut Line= 3
        2237425.       13825775.        2237525.       13825325.
      2237475.01     13825125.03
#Sta/Elev= 30
  4543.4   892.9  4562.6  885.82  4567.7   885.7  4574.1  880.83  4610.7  864.74
  4635.6   854.1  4654.8  841.32  4659.9  840.62  4666.3   835.4  4708.6  817.05
  4752.1  795.99  4758.5  790.42  4810.9  765.89  4839.2  754.19  4887.9  730.42
  4901.9  725.74  4967.1  718.16  4967.6  717.66  4980.1  718.16  4994.6  719.19
  5011.1   723.5  5022.4  727.83  5027.6  726.14  5063.6  741.21  5068.8  739.93
  5104.9  752.41  5151.3  760.47  5169.3   766.5  5192.5  769.38  5210.5  774.28
#Mann= 7 ,-1 , 0
  4543.4     .12       0  4610.7     .07       0  4810.9     .12       0
  4967.1     .05       0  4980.1     .12       0  4994.6     .07       0
  5011.1     .12       0
Bank Sta=4967.1,4980.1
XS Rating Curve= 0 ,0
Exp/Cntr=0.3,0.1

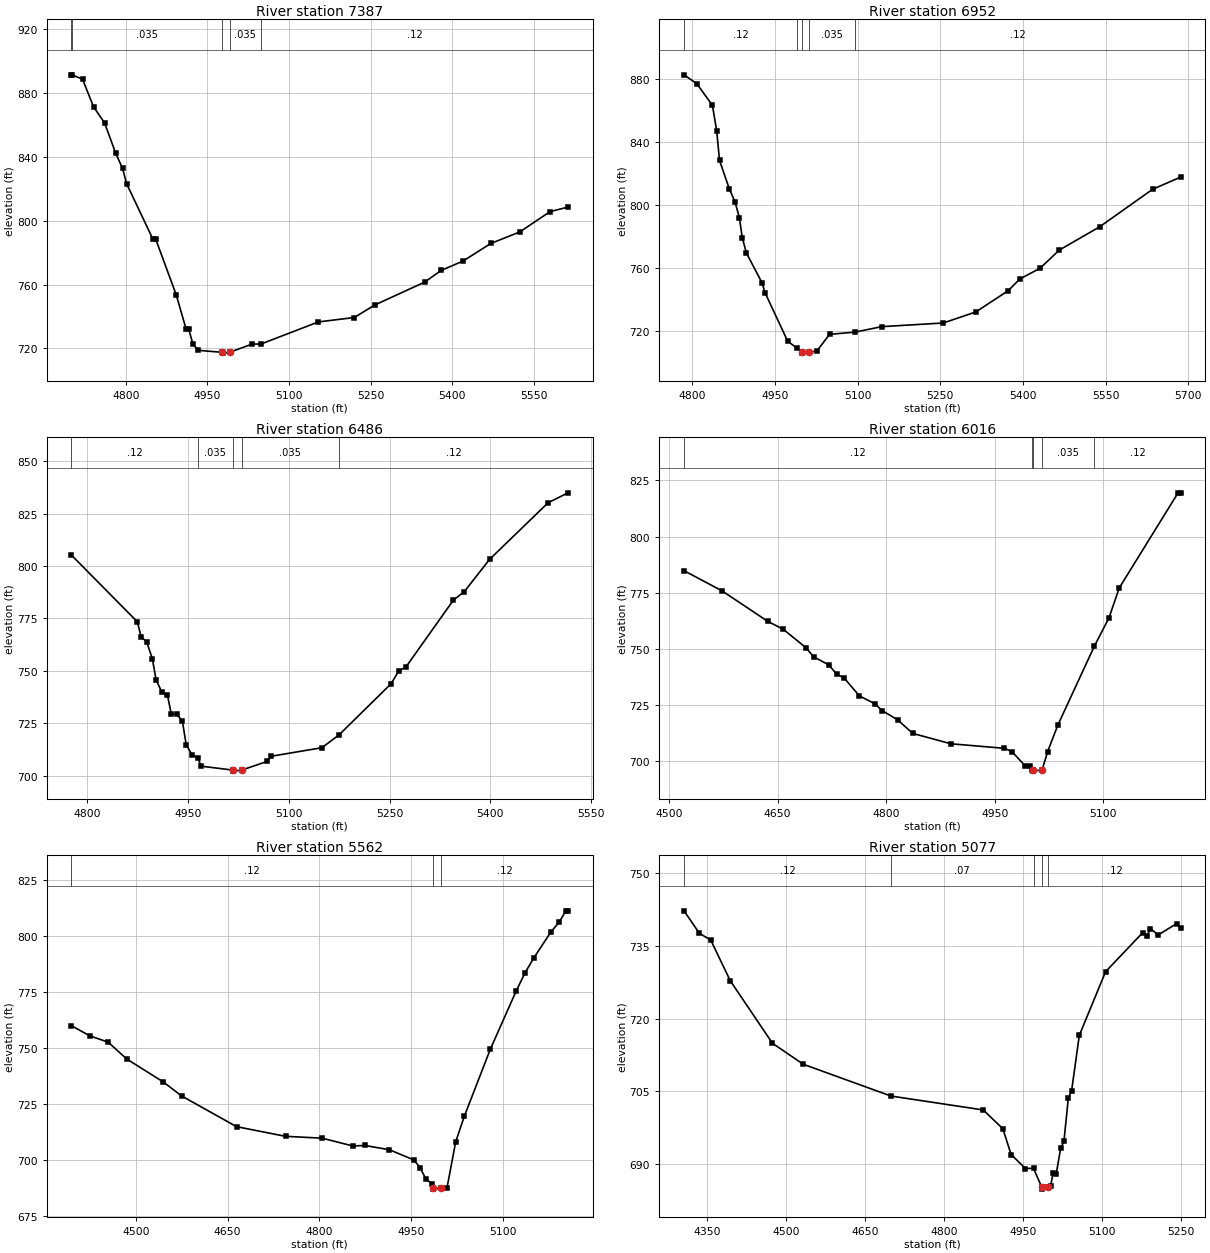
Type RM Length L Ch R = 1 ,7387    ,435,435,435
BEGIN DESCRIPTION:
Elm Creek 2 16.0
END DESCRIPTION:
XS GIS Cut Line= 3
      2237925.01     13825775.04        2237875.       13825475.
      2237774.99     13824874.95
#Sta/Elev= 30
  4700.1  891.47  4701.2  891.47  4720.4  888.73  4740.7   871.4    4761  861.27
  4781.2   842.4  4793.9  832.87  4801.5  823.15  4849.7  788.52  4854.7  788.69
  4892.8  753.35  4910.5  732.36  4915.6  732.12  4923.2  722.73  4933.3  718.82
  4977.5  717.58    4978  717.08  4990.6  717.58  5032.2  722.78  5048.1  722.76
  5153.8  736.64  5219.7  739.39  5257.7   747.3    5349  761.56  5379.4  768.88
  5419.9  774.83  5470.6  785.79  5523.8  793.01  5579.6  805.75  5612.6  808.62
#Mann= 5 ,-1 , 0
  4700.1     .12       0  4701.2    .035       0  4977.5    .035       0
  4990.6    .035       0  5048.1     .12       0
Bank Sta=4977.5,4990.6
XS Rating Curve= 0 ,0
Exp/Cntr=0.3,0.1

Type RM Length L Ch R = 1 ,6952    ,466,466,466
BEGIN DESCRIPTION:
Elm Creek 2 15.0
END DESCRIPTION:
XS GIS Cut Line= 3
      2238324.99     13825574.96        2238275.       13825375.
      2237925.02     13824775.03
#Sta/Elev= 30
  4785.3  882.42  4808.4  876.83  4836.8  863.09  4844.5     847  4849.7  828.12
  4867.7  809.81    4878  801.67  4885.8  791.64  4890.9  779.08  4898.6  769.27
    4927  750.32  4932.1  744.27  4973.4  713.33  4990.1  709.09  4998.5  706.33
    4999  705.83  5011.6  706.33  5026.6   707.3  5049.3  717.74  5095.1  719.16
    5144  722.63  5255.6  724.96  5314.3  731.92    5373  745.37  5394.5  752.87
  5431.3  759.73  5466.1  771.24  5539.3  786.01  5635.2  809.78    5686  817.51
#Mann= 5 ,-1 , 0
  4785.3     .12       0  4990.1    .035       0  4998.5    .035       0
  5011.6    .035       0  5095.1     .12       0
Bank Sta=4998.5,5011.6
XS Rating Curve= 0 ,0
Exp/Cntr=0.3,0.1

Type RM Length L Ch R = 1 ,6486    ,470,470,470
BEGIN DESCRIPTION:
Elm Creek 2 14.0
END DESCRIPTION:
XS GIS Cut Line= 3
      2238575.02     13825175.04        2238475.       13824975.
      2238225.01     13824525.03
#Sta/Elev= 30
  4777.1  805.12    4875  773.35  4880.6  766.24  4888.9  763.72  4897.3   755.8
  4902.9  745.59  4911.3  739.95  4919.7  738.45  4925.3  729.58  4933.7  729.29
  4942.1   725.8  4947.6   714.8    4956  710.02  4964.7  708.52    4970  704.45
  5017.1   702.6  5017.6   702.1  5030.2   702.6  5068.2  706.74    5074  709.19
  5149.5  713.28    5175  719.41  5252.4  743.81  5263.9  749.99  5274.2  751.68
  5345.1  783.73  5361.1  787.68  5398.8  803.12  5485.8  830.14  5515.5  834.87
#Mann= 5 ,-1 , 0
  4777.1     .12       0  4964.7    .035       0  5017.1    .035       0
  5030.2    .035       0    5175     .12       0
Bank Sta=5017.1,5030.2
XS Rating Curve= 0 ,0
Exp/Cntr=0.3,0.1

Type RM Length L Ch R = 1 ,6016    ,454,454,454
BEGIN DESCRIPTION:
Elm Creek 2 13.0
END DESCRIPTION:
XS GIS Cut Line= 3
      2238774.99     13825024.96        2238625.       13824575.
      2238475.03     13824425.03
#Sta/Elev= 30
  4520.6  784.78  4573.3  775.76  4636.5  762.17  4657.6  758.73  4689.2  750.45
  4699.8  746.41  4720.8   742.8  4731.4  738.72  4741.9     737    4763  729.02
  4784.1  725.55  4794.6  722.44  4815.7   718.4  4836.8   712.3  4889.5  707.69
  4963.3  705.67  4973.8  704.24  4992.3  697.79  4998.4  697.79  5002.2  696.14
  5002.5  696.01    5003  695.51  5015.6  696.01  5023.2   704.2  5037.3  715.99
  5087.7  751.09    5108  763.75  5122.2  777.09  5203.5  819.45    5207  819.45
#Mann= 5 ,-1 , 0
  4520.6     .12       0  5002.2    .035       0  5002.5     .05       0
  5015.6    .035       0  5087.7     .12       0
Bank Sta=5002.5,5015.6
XS Rating Curve= 0 ,0
Exp/Cntr=0.3,0.1

Type RM Length L Ch R = 1 ,5562    ,485,485,485
BEGIN DESCRIPTION:
Elm Creek 2 12.0
END DESCRIPTION:
XS GIS Cut Line= 3
        2238925.     13824875.02        2238925.       13824275.
      2238775.03     13824125.03
#Sta/Elev= 30
  4394.7  760.03  4424.7  755.49  4454.7  752.68  4484.7  745.22  4544.7  734.94
  4574.7  728.68  4664.7  714.95  4744.7  710.64  4804.7  709.81  4854.7  706.33
  4874.7  706.55  4914.7  704.64  4954.7  700.08  4964.7  696.65  4974.7  691.39
  4984.7   689.5  4985.6  687.56  4986.1  687.06  4998.8  687.56  5008.9  687.75
    5023  708.15  5037.1  719.55  5079.6  749.49    5122  775.55  5136.1  783.47
  5150.3   790.1  5178.6  801.81  5192.7  806.47  5203.3  811.32  5206.8  811.32
#Mann= 3 ,-1 , 0
  4394.7     .12       0  4985.6     .05       0  4998.8     .12       0
Bank Sta=4985.6,4998.8
XS Rating Curve= 0 ,0
Exp/Cntr=0.3,0.1

Type RM Length L Ch R = 1 ,5077    ,210,210,210
BEGIN DESCRIPTION:
Elm Creek 2 11.0
END DESCRIPTION:
XS GIS Cut Line= 3
      2239025.02     13824774.97        2239375.       13824175.
      2239224.99     13823974.99
#Sta/Elev= 30
  4305.4  742.27  4334.7  737.62  4356.2  736.25  4393.4  727.84  4473.6  714.95
  4532.4  710.61  4699.2  704.06  4874.7  701.19  4911.9  697.31  4927.6     692
  4954.9  689.11  4970.2  689.15  4985.5  685.36    4986  684.86  4998.7  685.36
  5003.1  685.51  5007.3  688.29  5013.5  688.04  5021.9  693.29  5028.1  694.71
  5036.4  703.61  5042.7  705.16  5057.3  716.56  5107.3  729.71  5178.1  737.79
  5186.4  737.17  5192.7  738.61  5207.3  737.29  5242.7  739.65    5250  738.63
#Mann= 5 ,-1 , 0
  4305.4     .12       0  4699.2     .07       0  4970.2     .12       0
  4985.5     .05       0  4998.7     .12       0
Bank Sta=4985.5,4998.7
XS Rating Curve= 0 ,0
Exp/Cntr=0.3,0.1

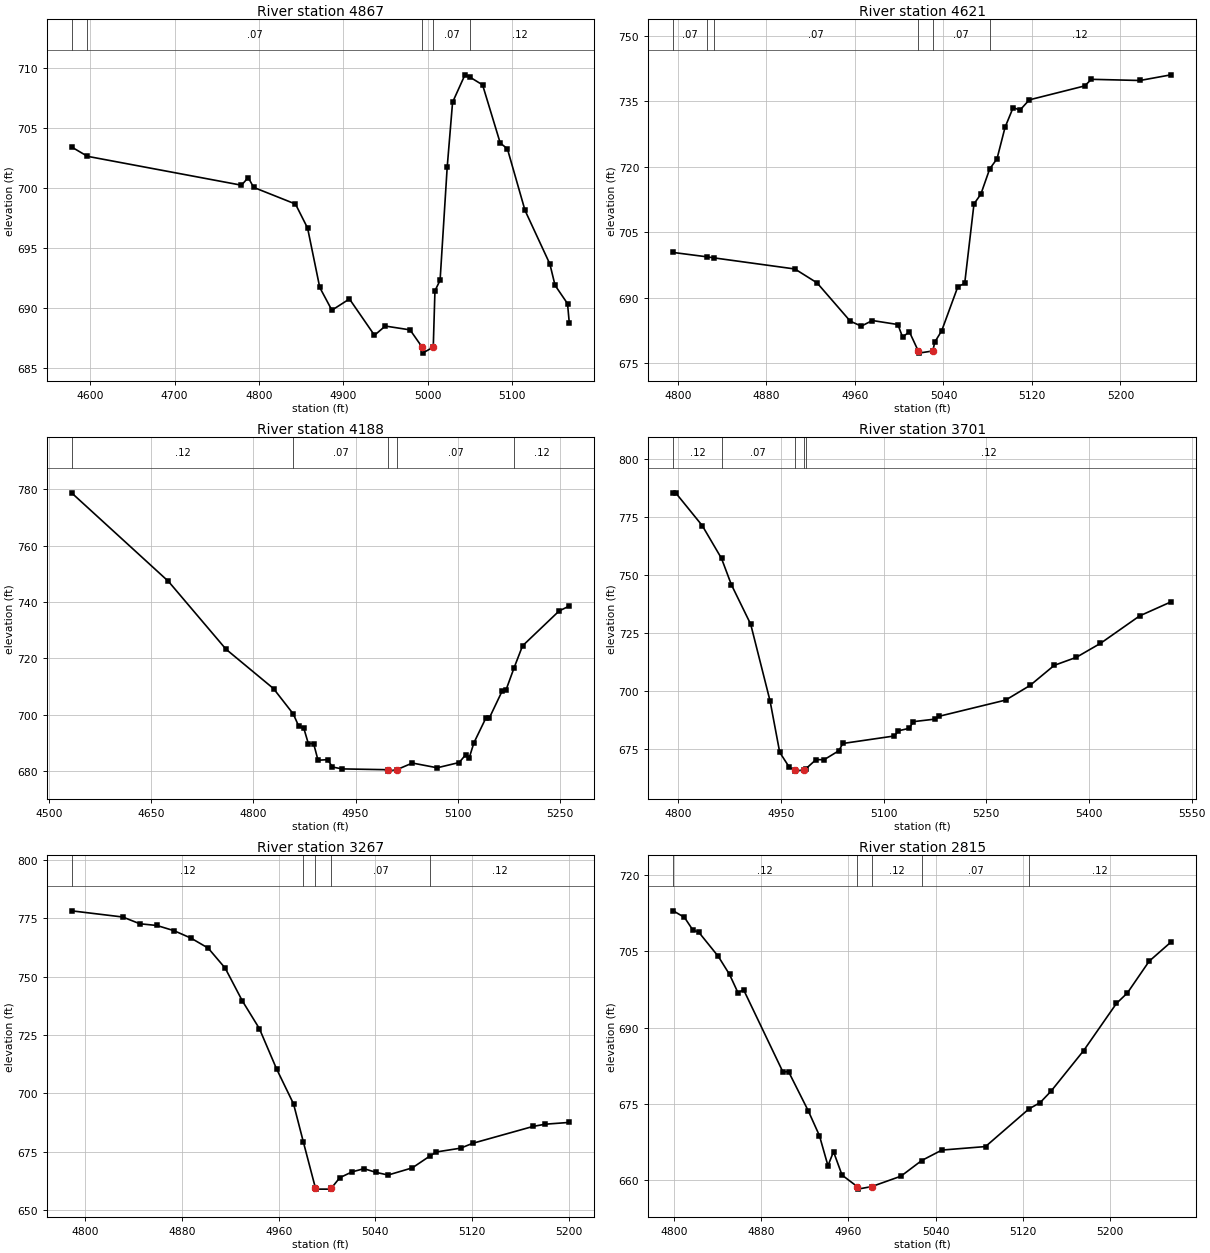
Type RM Length L Ch R = 1 ,4867    ,246,246,246
BEGIN DESCRIPTION:
X19134
END DESCRIPTION:
XS GIS Cut Line= 3
      2239269.48     13824463.44      2239535.32     13824249.72
       2239680.6     13824047.37
#Sta/Elev= 30
  4577.8   703.4  4596.7  702.62  4779.3  700.21  4787.3  700.85  4793.7  700.03
  4843.3  698.64  4857.7  696.63  4872.1  691.68  4886.5  689.78  4907.3  690.72
    4937  687.69  4949.8  688.46  4979.2  688.14  4993.5   686.7    4994   686.2
  5006.7   686.7  5008.7   691.4  5014.8  692.28  5023.2  701.69  5029.6  707.13
  5044.3  709.42  5049.9  709.24  5065.2  708.58  5086.1  703.73  5094.6  703.25
  5115.5  698.11    5145  693.63  5151.1  691.86  5165.9  690.33    5168  688.72
#Mann= 5 ,-1 , 0
  4577.8     .12       0  4596.7     .07       0  4993.5     .05       0
  5006.7     .07       0  5049.9     .12       0
Bank Sta=4993.5,5006.7
XS Rating Curve= 0 ,0
Exp/Cntr=0.3,0.1

Type RM Length L Ch R = 1 ,4621    ,433,433,433
BEGIN DESCRIPTION:
Elm Creek 2 10.0
END DESCRIPTION:
XS GIS Cut Line= 3
      2239425.01       13824375.        2239625.       13824375.
      2239825.01     13824525.01
#Sta/Elev= 30
  4795.7  700.36  4826.5  699.35  4832.2  699.13  4905.7  696.57  4925.7  693.39
  4955.7  684.61  4965.7  683.46  4975.7  684.75  4998.8  683.83    5003  680.97
  5009.2  682.15  5017.2  677.77  5017.7  677.27  5030.4  677.77  5032.1  679.78
  5038.4   682.4    5053  692.51  5059.2  693.27  5067.6  711.51  5073.8  713.73
  5081.8  719.53  5088.4  721.84  5095.7  729.08    5103   733.6  5109.2  733.02
  5117.6  735.37  5167.6  738.56  5173.8  740.08  5217.6  739.81  5245.7  741.11
#Mann= 6 ,-1 , 0
  4795.7     .07       0  4826.5     .12       0  4832.2     .07       0
  5017.2     .05       0  5030.4     .07       0  5081.8     .12       0
Bank Sta=5017.2,5030.4
XS Rating Curve= 0 ,0
Exp/Cntr=0.3,0.1

Type RM Length L Ch R = 1 ,4188    ,487,487,487
BEGIN DESCRIPTION:
Elm Creek 2 9.0
END DESCRIPTION:
XS GIS Cut Line= 3
        2239225.       13825125.        2239525.       13824775.
      2239774.97     13824675.01
#Sta/Elev= 30
  4533.3  778.73  4675.4  747.31  4759.9  723.22  4829.6  709.25  4858.6  700.24
  4866.4  696.01  4874.1  695.12  4880.7  689.71  4888.4  689.76  4894.9  683.81
  4909.2  684.05  4915.8  681.43  4930.1  680.75  4997.1  680.46  4997.6  679.96
  5010.3  680.46  5033.3  682.83  5069.7  681.15    5102  683.02  5111.4  685.75
  5116.8  684.74  5123.5  689.98    5141  698.73  5146.4  698.92  5165.3  708.53
  5170.6  708.71  5182.4  716.56  5194.9  724.42  5248.7  736.83  5263.5  738.55
#Mann= 5 ,-1 , 0
  4533.3     .12       0  4858.6     .07       0  4997.1     .05       0
  5010.3     .07       0  5182.4     .12       0
Bank Sta=4997.1,5010.3
XS Rating Curve= 0 ,0
Exp/Cntr=0.3,0.1

Type RM Length L Ch R = 1 ,3701    ,434,434,434
BEGIN DESCRIPTION:
Elm Creek 2 8.0
END DESCRIPTION:
XS GIS Cut Line= 3
      2239475.01     13825374.99        2239625.       13825225.
        2239875.       13824775.
#Sta/Elev= 30
  4792.9  785.27  4796.4  785.27  4835.3  771.14  4863.4  757.03  4877.7  745.79
    4906  728.71  4934.3  695.68  4948.4  673.56  4962.6  667.06  4970.1  665.98
  4970.6  665.48  4983.4  665.98  4986.5  666.48  5001.5  670.46    5013  670.36
  5034.8  674.26  5040.5  677.38    5116  680.62  5121.7  682.83  5137.7  683.93
  5143.4  686.77  5175.5  687.88  5181.2  689.09  5278.4  696.07  5313.9  702.35
  5349.3  711.01  5381.4  714.44  5416.8  720.47    5474  732.29  5519.8  738.33
#Mann= 5 ,-1 , 0
  4792.9     .12       0  4863.4     .07       0  4970.1     .05       0
  4983.4     .07       0  4986.5     .12       0
Bank Sta=4970.1,4983.4
XS Rating Curve= 0 ,0
Exp/Cntr=0.3,0.1

Type RM Length L Ch R = 1 ,3267    ,452,452,452
BEGIN DESCRIPTION:
Elm Creek 2 7.0
END DESCRIPTION:
XS GIS Cut Line= 3
      2239775.03     13825624.97        2239925.       13825475.
        2239925.     13825274.99
#Sta/Elev= 30
  4788.5  778.15  4830.9   775.5    4845  772.61  4859.2  771.87  4873.3  769.65
  4887.4  766.46  4901.6  762.19  4915.7  753.61  4929.9  739.58    4944  727.72
  4958.2   710.5  4972.3  695.47  4980.5     679  4990.4  659.47  4990.9  658.97
  5003.2  658.97  5003.7  659.47  5010.6  663.86  5020.6  666.33  5030.6  667.73
  5040.6  666.14  5050.6  665.01  5070.6  668.07  5085.6  673.29  5090.6  674.89
  5110.6  676.51  5120.6  678.59  5170.6  685.82  5180.6  686.77  5200.6  687.54
#Mann= 5 ,-1 , 0
  4788.5     .12       0  4980.5     .07       0  4990.4     .05       0
  5003.7     .07       0  5085.6     .12       0
Bank Sta=4990.4,5003.7
XS Rating Curve= 0 ,0
Exp/Cntr=0.3,0.1

Type RM Length L Ch R = 1 ,2815    ,473,473,473
BEGIN DESCRIPTION:
Elm Creek 2 6.0
END DESCRIPTION:
XS GIS Cut Line= 3
      2240274.99     13825525.04        2240325.       13825325.
        2240325.       13825075.
#Sta/Elev= 30
  4799.4  712.98  4809.7  711.68  4817.5  709.15  4822.6  708.82  4840.7     704
    4851  700.45  4858.7  696.87  4863.9  697.43  4899.9  681.26  4905.1  681.31
  4923.1  673.62  4933.4   668.7  4941.2  662.79  4946.3  665.55  4954.1  660.95
    4968  658.68  4968.5  658.18  4981.3  658.68  5008.1  660.73  5027.1  663.81
  5045.6  665.87  5085.6  666.56  5125.5  673.99  5135.6   675.2  5145.6  677.45
  5175.6  685.47  5205.6  694.74  5215.6   696.8  5235.6  703.06  5255.6  706.83
#Mann= 5 ,-1 , 0
  4799.4     .12       0    4968     .05       0  4981.3     .12       0
  5027.1     .07       0  5125.5     .12       0
Bank Sta=4968,4981.3
XS Rating Curve= 0 ,0
Exp/Cntr=0.3,0.1

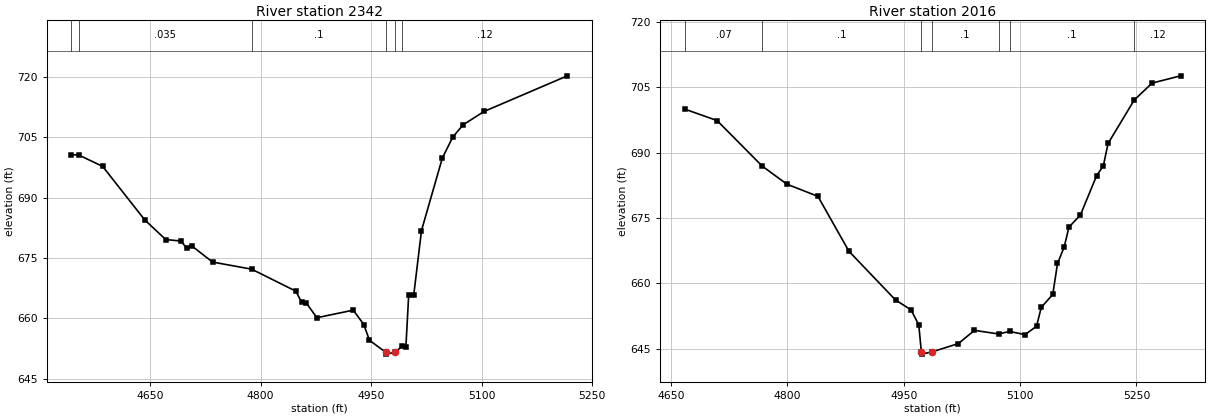
Type RM Length L Ch R = 1 ,2342    ,326,326,326
BEGIN DESCRIPTION:
Elm Creek 2 5.0
END DESCRIPTION:
XS GIS Cut Line= 3
      2240975.01     13825425.01        2240675.       13825075.
      2240525.01     13824925.01
#Sta/Elev= 30
  4543.4  700.72  4553.5   700.6  4585.7   697.8  4642.7  684.53  4671.3  679.62
  4692.1  679.24  4699.8  677.46  4706.4  678.08  4734.9  674.02    4788  672.25
    4848  666.78  4855.7  664.03  4862.3  663.81  4876.5  660.19  4925.9  662.07
  4940.2   658.5  4947.9  654.57  4969.7  651.64  4970.2  651.14    4983  651.64
  4992.4  653.15  4997.3  652.87  5001.1  665.71  5007.9  665.71  5018.5  681.85
  5046.8  699.87    5061  705.09  5075.1  708.14  5103.4  711.44  5216.5   720.3
#Mann= 6 ,-1 , 0
  4543.4     .07       0  4553.5    .035       0    4788      .1       0
  4969.7     .05       0    4983      .1       0  4992.4     .12       0
Bank Sta=4969.7,4983
XS Rating Curve= 0 ,0
Exp/Cntr=0.3,0.1

Type RM Length L Ch R = 1 ,2016    ,0,0,0
BEGIN DESCRIPTION:
Elm Creek 2 4.0
END DESCRIPTION:
XS GIS Cut Line= 3
      2241005.08     13825406.72      2241005.08     13825078.42
        2240825.     13824824.99
#Sta/Elev= 30
  4667.7     700  4709.4  697.37  4767.5  686.93  4799.4  682.77  4839.4  679.97
  4879.4  667.36  4939.4  656.18  4959.4  653.92  4969.4  650.45  4972.7  644.25
  4973.2  643.75  4986.1  644.25  5020.3  646.16  5041.2  649.21  5072.2  648.38
  5086.4  648.96  5106.4  648.22  5121.2  650.16  5127.3   654.5  5142.1  657.44
  5148.2  664.56  5156.8  668.34    5163  672.92  5177.7  675.68  5198.6  684.71
  5207.3  686.98  5213.4  692.12  5247.1  702.08  5270.1  705.97  5306.9  707.64
#Mann= 7 ,-1 , 0
  4667.7     .07       0  4767.5      .1       0  4972.7     .05       0
  4986.1      .1       0  5072.2    .035       0  5086.4      .1       0
  5247.1     .12       0
Bank Sta=4972.7,4986.1
XS Rating Curve= 0 ,0
Exp/Cntr=0.3,0.1

Chan Stop Cuts=-1
Use User Specified Reach Order=0
Composite Channel Slope=5