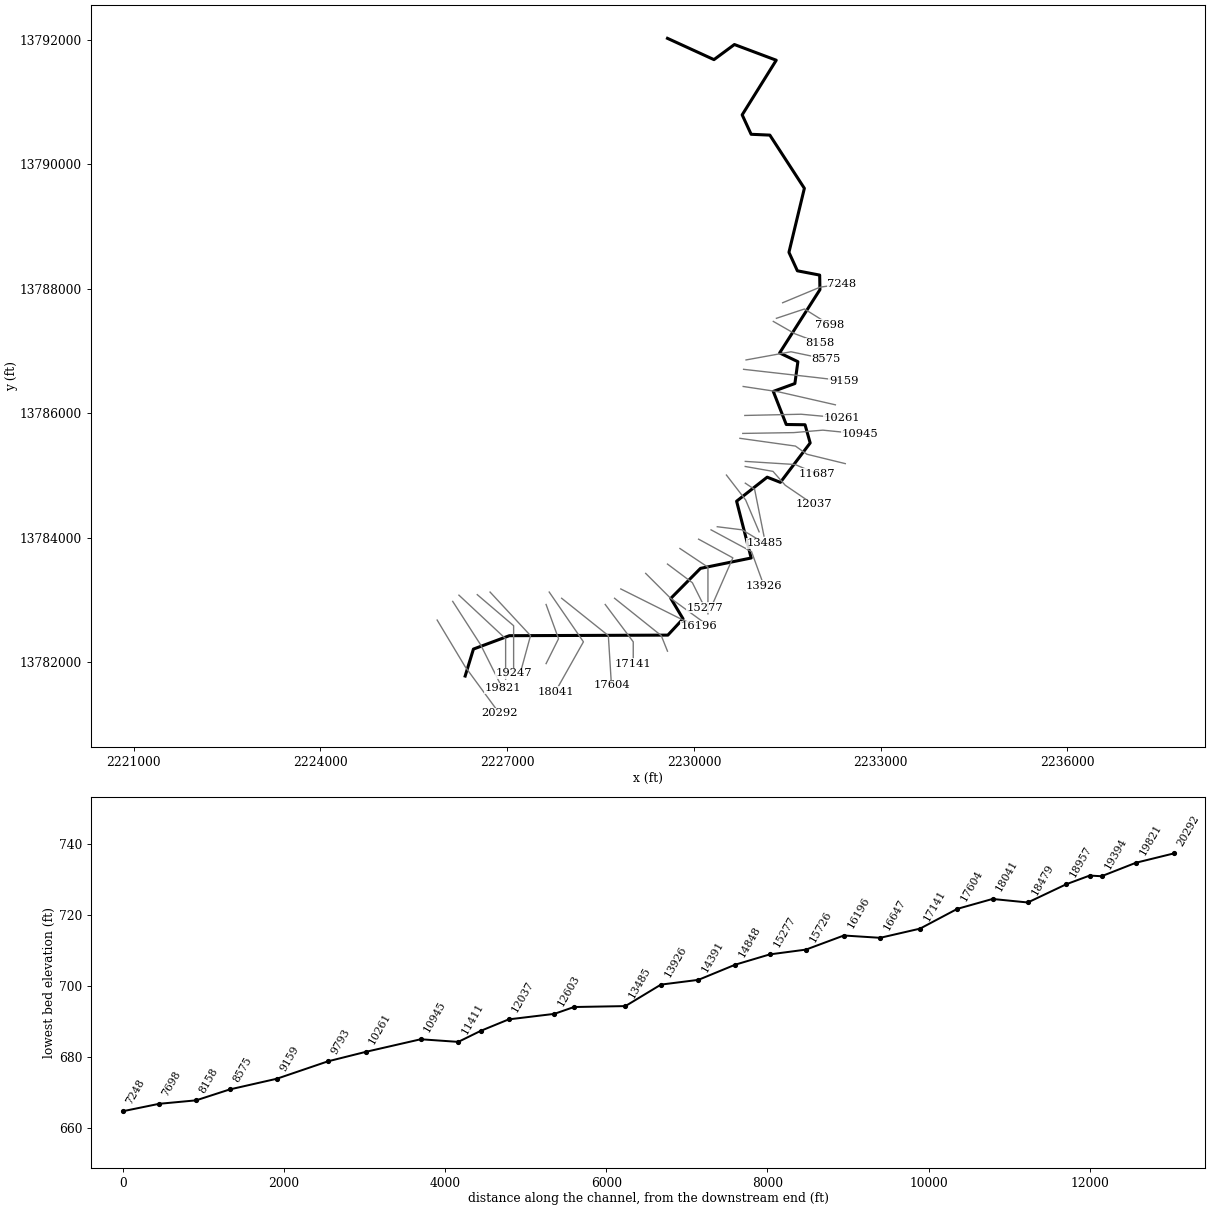
--- Fourmile Creek.prj (project) ---

Proj Title=Fourmile Creek Base Level Engineering
Current Plan=p01
Default Exp/Contr=0.3,0.1
English Units
Geom File=g01
Flow File=f01
Plan File=p01
BEGIN DESCRIPTION:
Fourmile Creek
END DESCRIPTION:

--- Fourmile Creek.p01 (plan) ---

Plan Title=Multiple Run
Short Identifier=Multiple
Geom File=g01
Flow File=f01
Subcritical Flow
K Sum by GR= 0
Std Step Tol= 0.01
Critical Tol= 0.01
Num of Std Step Trials= 20
Max Error Tol= 0.3
Flow Tol Ratio= 0.001
Split Flow NTrial= 30
Split Flow Tol= 0.02
Split Flow Ratio= 0.02
Log Output Level= 0
Friction Slope Method= 1
Unsteady Friction Slope Method= 2
Unsteady Bridges Friction Slope Method= 1
Parabolic Critical Depth
Global Vel Dist=  1 , 1 , 1
Global Log Level= 0
CheckData=True
Encroach Param= -1, 0, 0, 0
BEGIN DESCRIPTION:
Multiple Run
END DESCRIPTION:

--- Fourmile Creek.f01 (steady flow) ---

Flow Title=Multiple
Number of Profiles=7
Profile Names=10-year,25-year,50-year,1pct_min,100-year,1pct_plu,500-year
River Rch & RM= Fourmile Creek,Reach-1,20292
     915    1512    2063    1362    2718    5423    4669
River Rch & RM= Fourmile Creek,Reach-1,17141
    1178    1970    2709    1800    3592    7166    6254
River Rch & RM= Fourmile Creek,Reach-1,12847
    1368    2301    3176    2117    4223    8427    7401
River Rch & RM= Fourmile Creek,Reach-1,7698
    1739    2958    4115    2762    5511   10995    9794
River Rch & RM= Fourmile Creek,Reach-1,4972
    1799    3061    4258    2857    5700   11373   10124
Boundary for River Rch & Prof#=Fourmile Creek,Reach-1,1
Up Type=0
Dn Type=3
Dn Slope=0.005
Boundary for River Rch & Prof#=Fourmile Creek,Reach-1,2
Up Type=0
Dn Type=3
Dn Slope=0.005
Boundary for River Rch & Prof#=Fourmile Creek,Reach-1,3
Up Type=0
Dn Type=3
Dn Slope=0.005
Boundary for River Rch & Prof#=Fourmile Creek,Reach-1,4
Up Type=0
Dn Type=3
Dn Slope=0.005
Boundary for River Rch & Prof#=Fourmile Creek,Reach-1,5
Up Type=0
Dn Type=3
Dn Slope=0.005
Boundary for River Rch & Prof#=Fourmile Creek,Reach-1,6
Up Type=0
Dn Type=3
Dn Slope=0.005
Boundary for River Rch & Prof#=Fourmile Creek,Reach-1,7
Up Type=0
Dn Type=3
Dn Slope=0.005

--- Fourmile Creek.g01 (geometry) ---

Geom Title=Existing Conditions

River Reach=Fourmile Creek,Reach-1
Reach XY= 30
      2226325.00     13781775.00      2226457.95     13782208.51
      2227035.51     13782423.78      2229581.19     13782432.81
      2229825.06     13782694.99      2229628.43     13783023.43
      2230104.95     13783505.65      2230919.48     13783672.56
      2230685.34     13784585.12      2231176.50     13784971.54
      2231388.69     13784888.27      2231867.18     13785521.56
      2231784.71     13785814.25      2231482.86     13785818.17
      2231274.49     13786350.04      2231621.46     13786476.46
      2231669.65     13786827.70      2231376.56     13786968.40
      2232023.95     13787985.43      2232019.82     13788219.56
      2231661.59     13788288.52      2231526.10     13788585.55
      2231773.80     13789614.49      2231219.41     13790469.45
      2230918.79     13790482.80      2230774.89     13790795.11
      2231322.15     13791673.24      2230650.00     13791925.59
      2230321.77     13791682.84      2229575.00     13792025.00

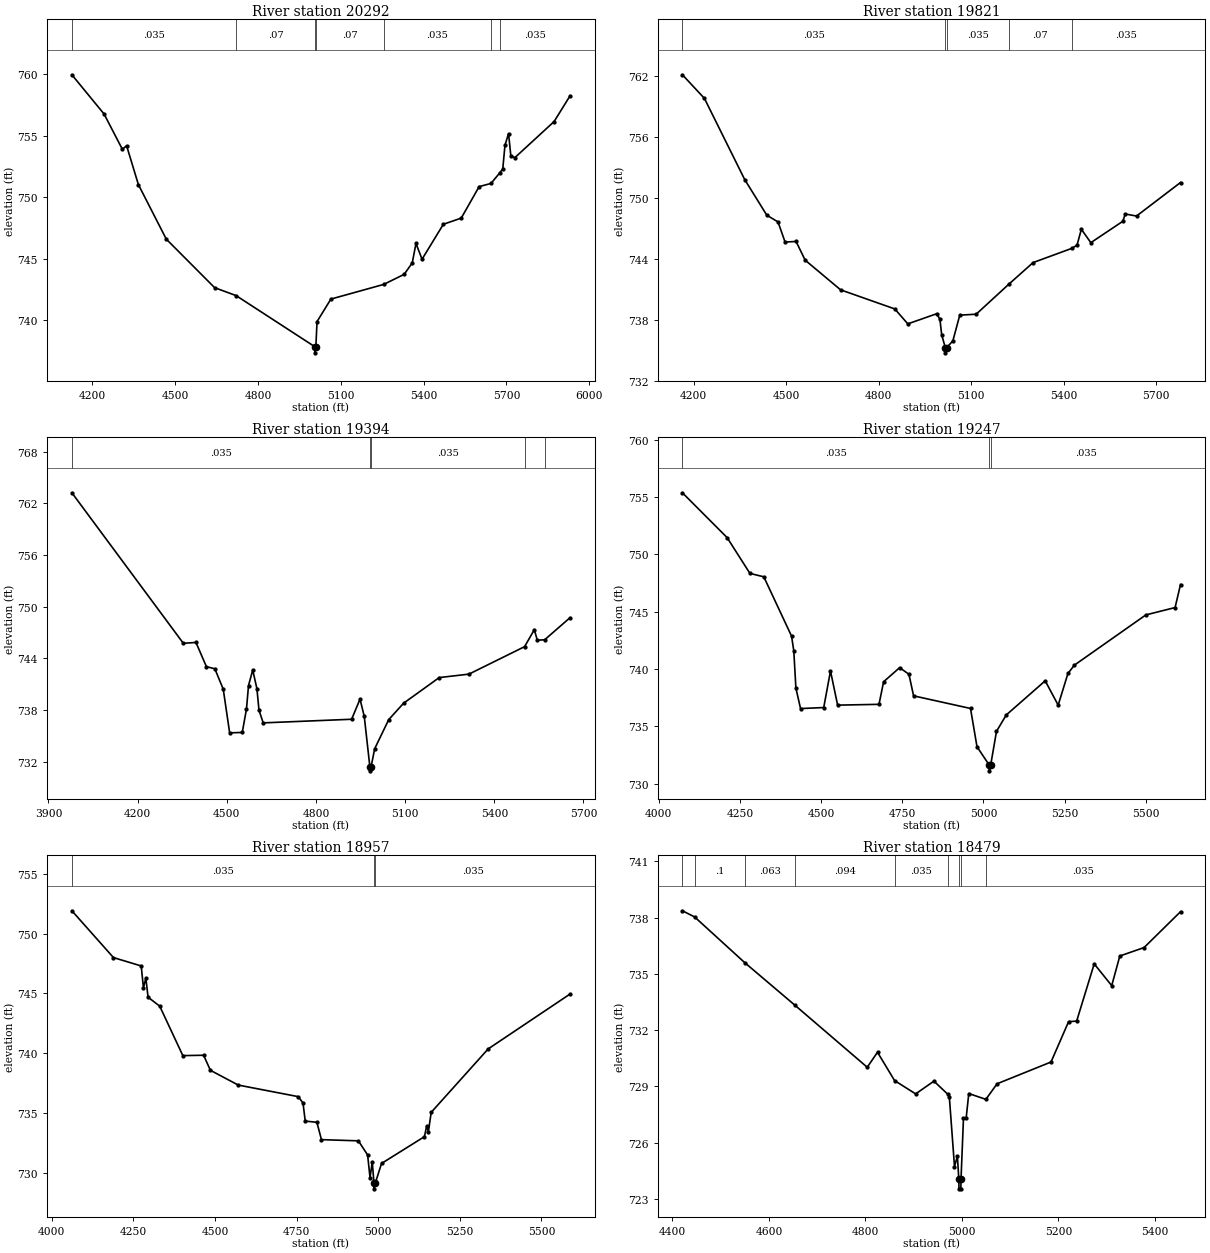
Type RM Length L Ch R = 1,20292,471,471,471
BEGIN DESCRIPTION:
Fourmile Creek 37.0
END DESCRIPTION:
XS GIS Cut Line= 3
      2225874.98     13782675.03      2226325.00     13781925.00
      2226874.98     13781175.03
#Sta/Elev= 30
  4125.5  759.96  4242.2  756.77  4308.2  753.91  4323.8  754.19  4366.5  751.03
  4467.6  746.60  4642.5  742.66  4720.7  742.01  5005.5  737.86  5005.8  737.36
  5009.5  737.86  5013.7  739.90  5063.9  741.73  5255.1  742.92  5329.4  743.74
  5358.7  744.67  5372.2  746.25  5394.2  744.97  5471.4  747.81  5536.2  748.31
  5601.0  750.87  5644.1  751.13  5675.1  751.97  5686.7  752.31  5694.6  754.23
  5707.6  755.18  5716.0  753.35  5730.7  753.23  5872.7  756.16  5930.2  758.24
#Mann=7,-1,0
  4125.5   0.035       0  4720.7    0.07       0  5005.5    0.05       0
  5009.5    0.07       0  5255.1   0.035       0  5644.1    0.07       0
  5675.1   0.035       0
Bank Sta=5005.5,5009.5
Exp/Cntr=0.3,0.1

Type RM Length L Ch R = 1,19821,427,427,427
BEGIN DESCRIPTION:
Fourmile Creek 36.0
END DESCRIPTION:
XS GIS Cut Line= 3
      2226125.02     13782974.97      2226575.00     13782275.00
      2226925.02     13781574.96
#Sta/Elev= 30
  4163.7  762.09  4235.0  759.77  4365.8  751.77  4437.4  748.27  4473.7  747.61
  4496.5  745.63  4532.2  745.69  4561.6  743.85  4676.5  740.93  4852.2  739.05
  4894.5  737.58  4988.2  738.58  4998.6  738.03  5004.2  736.51  5016.1  735.23
  5016.3  734.73  5020.3  735.23  5040.6  735.92  5062.9  738.44  5116.0  738.53
  5221.8  741.48  5300.5  743.61  5425.2  745.00  5443.0  745.32  5457.0  746.89
  5487.8  745.57  5591.2  747.67  5599.6  748.39  5635.9  748.19  5778.5  751.49
#Mann=5,-1,0
  4163.7   0.035       0  5016.1   0.035       0  5020.3   0.035       0
  5221.8    0.07       0  5425.2   0.035       0
Bank Sta=5016.1,5020.3
Exp/Cntr=0.3,0.1

Type RM Length L Ch R = 1,19394,147,147,147
BEGIN DESCRIPTION:
Fourmile Creek 35.0
END DESCRIPTION:
XS GIS Cut Line= 3
      2226224.99     13783075.01      2226975.00     13782375.00
      2226975.00     13781725.03
#Sta/Elev= 30
  3978.7  763.22  4353.7  745.74  4396.2  745.84  4431.3  743.03  4459.7  742.78
  4488.0  740.41  4509.5  735.34  4552.0  735.39  4566.2  738.13  4573.0  740.84
  4587.2  742.64  4601.3  740.46  4608.2  737.98  4622.4  736.50  4919.9  736.92
  4948.2  739.26  4962.4  737.25  4981.2  731.43  4981.5  730.93  4985.5  731.43
  4997.5  733.50  5044.6  736.87  5094.6  738.78  5214.6  741.76  5314.6  742.16
  5501.8  745.35  5534.6  747.32  5544.6  746.10  5569.4  746.15  5654.6  748.71
#Mann=5,-1,0
  3978.7   0.035       0  4981.2   0.035       0  4985.5   0.035       0
  5501.8    0.07       0  5569.4   0.035       0
Bank Sta=4981.2,4985.5
Exp/Cntr=0.3,0.1

Type RM Length L Ch R = 1,19247,290,290,290
BEGIN DESCRIPTION:
X19214
END DESCRIPTION:
XS GIS Cut Line= 3
      2226519.45     13783082.94      2227103.38     13782584.30
      2227103.38     13781818.27
#Sta/Elev= 30
  4073.0  755.37  4210.7  751.46  4280.9  748.34  4323.7  748.04  4409.1  742.87
  4416.0  741.59  4422.5  738.33  4436.8  736.55  4508.2  736.64  4529.0  739.83
  4551.0  736.85  4678.4  736.92  4692.6  738.89  4742.0  740.12  4770.6  739.54
  4784.9  737.66  4960.2  736.56  4980.2  733.22  5018.0  731.62  5018.3  731.12
  5022.3  731.62  5040.2  734.56  5070.2  735.99  5190.2  738.97  5230.2  736.85
  5260.2  739.61  5280.2  740.34  5500.2  744.72  5590.2  745.36  5606.9  747.37
#Mann=3,-1,0
  4073.0   0.035       0  5018.0   0.035       0  5022.3   0.035       0
Bank Sta=5018,5022.3
Exp/Cntr=0.3,0.1

Type RM Length L Ch R = 1,18957,478,478,478
BEGIN DESCRIPTION:
Fourmile Creek 34.0
END DESCRIPTION:
XS GIS Cut Line= 3
      2226725.01     13783124.99      2227375.00     13782425.00
      2227225.01     13781875.02
#Sta/Elev= 30
  4062.1  751.91  4189.4  748.00  4274.4  747.30  4281.2  745.48  4288.6  746.28
  4295.4  744.69  4331.1  743.94  4401.9  739.81  4465.4  739.84  4486.4  738.58
  4571.5  737.35  4755.7  736.38  4769.9  735.84  4776.7  734.34  4812.4  734.24
  4826.3  732.79  4939.4  732.69  4967.7  731.51  4975.1  729.61  4981.9  730.93
  4987.1  729.18  4987.4  728.68  4991.5  729.18  5010.3  730.80  5141.7  733.04
  5148.6  733.94  5153.8  733.45  5162.4  735.07  5336.9  740.37  5587.4  744.95
#Mann=3,-1,0
  4062.1   0.035       0  4987.1   0.035       0  4991.5   0.035       0
Bank Sta=4987.1,4991.5
Exp/Cntr=0.3,0.1

Type RM Length L Ch R = 1,18479,438,438,438
BEGIN DESCRIPTION:
Fourmile Creek 33.0
END DESCRIPTION:
XS GIS Cut Line= 3
      2227624.99     13782925.02      2227825.00     13782375.00
      2227624.99     13781974.97
#Sta/Elev= 30
  4420.7  738.36  4446.1  738.03  4549.7  735.60  4653.3  733.34  4803.8  730.02
  4825.1  730.82  4860.5  729.31  4904.2  728.60  4942.1  729.28  4971.2  728.57
  4974.0  728.44  4984.7  724.73  4990.7  725.28  4993.7  724.04  4994.0  723.54
  4997.9  723.54  4998.2  724.04  5003.3  727.29  5008.8  727.29  5014.3  728.62
  5049.7  728.31  5073.0  729.14  5184.8  730.30  5221.2  732.45  5237.9  732.48
  5274.3  735.53  5310.6  734.37  5327.4  735.95  5377.7  736.40  5453.2  738.31
#Mann=9,-1,0
  4420.7   0.063       0  4446.1     0.1       0  4549.7   0.063       0
  4653.3   0.094       0  4860.5   0.035       0  4971.2    0.07       0
  4993.7    0.05       0  4998.2    0.07       0  5049.7   0.035       0
Bank Sta=4993.7,4998.2
Exp/Cntr=0.3,0.1

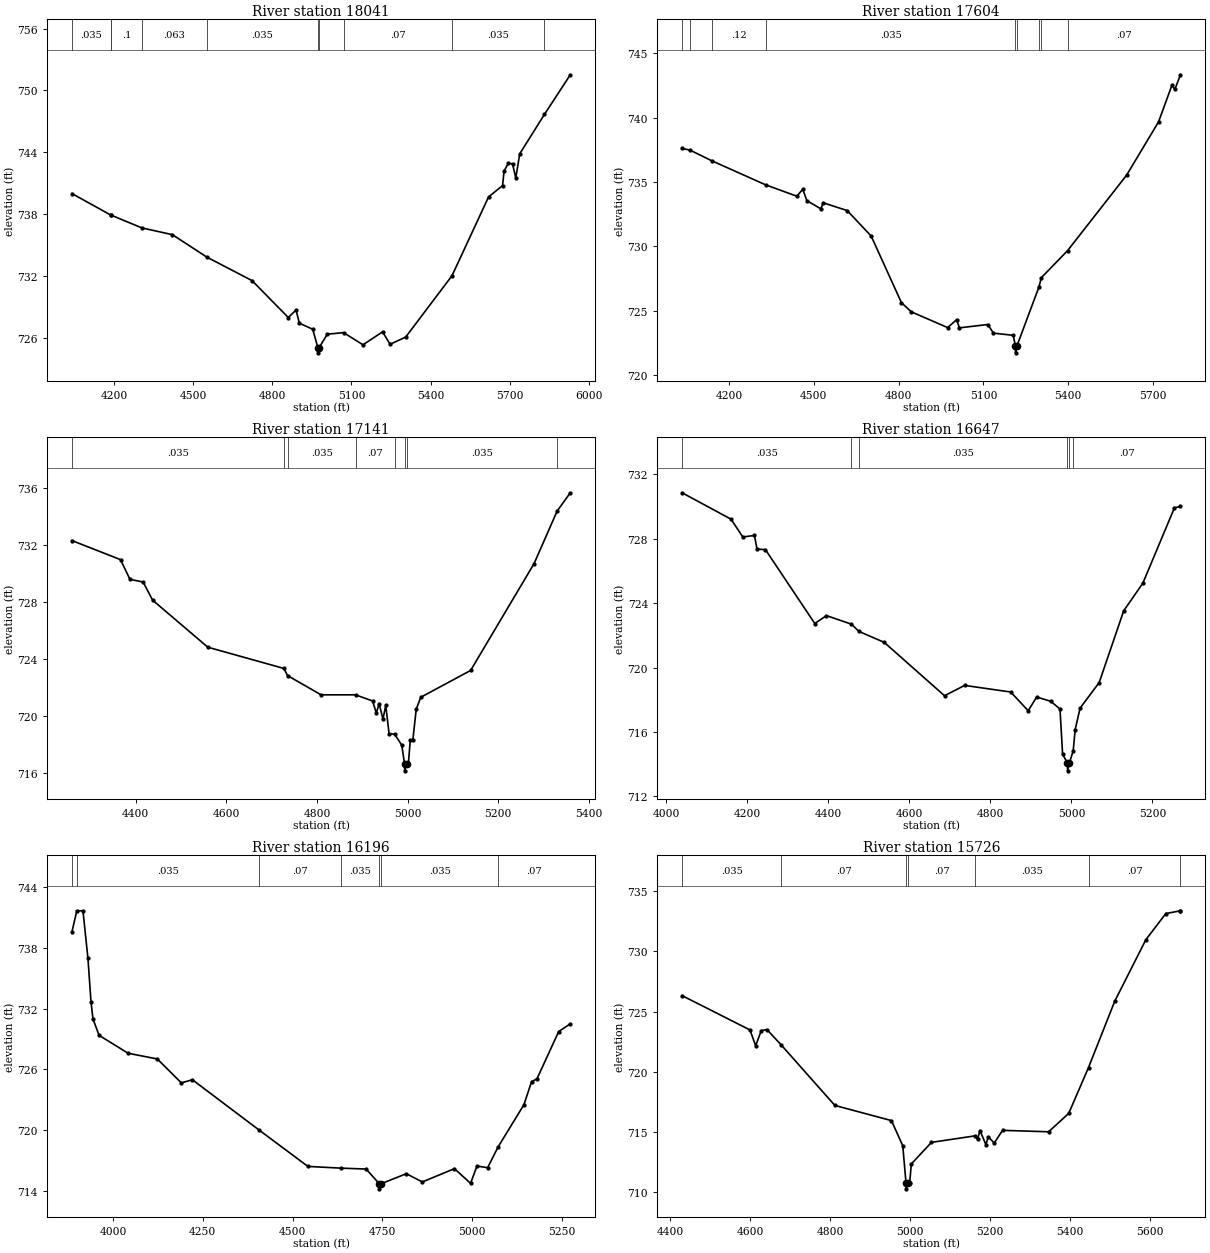
Type RM Length L Ch R = 1,18041,437,437,437
BEGIN DESCRIPTION:
Fourmile Creek 32.0
END DESCRIPTION:
XS GIS Cut Line= 3
      2227674.97     13783125.04      2228225.00     13782325.00
      2227774.98     13781524.96
#Sta/Elev= 30
  4040.6  739.99  4188.3  737.90  4188.6  737.90  4305.4  736.66  4421.5  736.00
  4552.1  733.82  4723.3  731.54  4860.6  727.96  4890.1  728.69  4902.5  727.41
  4953.3  726.82  4972.8  725.03  4973.1  724.53  4977.4  725.03  5008.4  726.34
  5070.2  726.49  5143.7  725.31  5218.0  726.57  5246.4  725.36  5305.6  726.06
  5481.2  732.02  5619.6  739.66  5672.8  740.77  5678.5  742.17  5694.5  742.94
  5710.4  742.87  5722.8  741.51  5737.8  743.85  5831.3  747.67  5929.4  751.52
#Mann=10,-1,0
  4040.6   0.035       0  4188.3   0.063       0  4188.6     0.1       0
  4305.4   0.063       0  4552.1   0.035       0  4972.8   0.035       0
  4977.4   0.035       0  5070.2    0.07       0  5481.2   0.035       0
  5831.3    0.07       0
Bank Sta=4972.8,4977.4
Exp/Cntr=0.3,0.1

Type RM Length L Ch R = 1,17604,463,463,463
BEGIN DESCRIPTION:
Fourmile Creek 31.0
END DESCRIPTION:
XS GIS Cut Line= 3
      2227874.98     13783025.02      2228625.00     13782425.00
      2228675.00     13781624.96
#Sta/Elev= 30
  4034.6  737.61  4062.7  737.48  4139.8  736.65  4330.4  734.78  4440.4  733.90
  4461.2  734.45  4475.6  733.56  4525.3  732.92  4533.3  733.39  4618.1  732.79
  4703.0  730.81  4810.2  725.63  4845.4  724.92  4973.5  723.70  5005.1  724.31
  5015.1  723.68  5115.3  723.94  5135.4  723.27  5205.5  723.10  5213.2  722.24
  5213.5  721.74  5217.8  722.24  5296.4  726.86  5304.5  727.57  5397.6  729.68
  5606.3  735.54  5719.0  739.67  5766.6  742.53  5776.6  742.19  5796.7  743.33
#Mann=9,-1,0
  4034.6    0.07       0  4062.7     0.1       0  4139.8    0.12       0
  4330.4   0.035       0  5213.2   0.035       0  5217.8   0.035       0
  5296.4    0.07       0  5304.5   0.035       0  5397.6    0.07       0
Bank Sta=5213.2,5217.8
Exp/Cntr=0.3,0.1

Type RM Length L Ch R = 1,17141,494,494,494
BEGIN DESCRIPTION:
Fourmile Creek 30.0
END DESCRIPTION:
XS GIS Cut Line= 3
      2228574.99     13782925.02      2229025.00     13782325.00
      2229025.00     13781975.02
#Sta/Elev= 30
  4259.2  732.32  4366.5  730.98  4387.3  729.60  4416.5  729.41  4437.3  728.14
  4559.2  724.84  4727.1  723.35  4735.2  722.85  4809.2  721.50  4885.2  721.50
  4922.8  721.07  4931.1  720.22  4937.3  720.89  4945.7  719.79  4951.9  720.76
  4959.2  718.78  4971.5  718.74  4987.3  717.97  4993.3  716.67  4993.6  716.17
  4998.1  716.67  5001.9  716.72  5006.1  718.34  5011.7  718.34  5019.2  720.50
  5029.2  721.33  5139.2  723.21  5279.2  730.70  5330.0  734.38  5359.2  735.67
#Mann=8,-1,0
  4259.2   0.035       0  4727.1    0.07       0  4735.2   0.035       0
  4885.2    0.07       0  4971.5   0.035       0  4993.3   0.035       0
  4998.1   0.035       0  5330.0    0.07       0
Bank Sta=4993.3,4998.1
Exp/Cntr=0.3,0.1

Type RM Length L Ch R = 1,16647,451,451,451
BEGIN DESCRIPTION:
Fourmile Creek 29.0
END DESCRIPTION:
XS GIS Cut Line= 3
      2228724.98     13783025.02      2229475.00     13782425.00
      2229575.02     13782174.96
#Sta/Elev= 30
  4039.4  730.84  4160.3  729.20  4189.1  728.10  4217.9  728.19  4224.3  727.35
  4245.1  727.31  4366.8  722.73  4395.6  723.22  4457.2  722.69  4475.7  722.24
  4538.1  721.56  4686.9  718.25  4736.6  718.89  4850.2  718.48  4893.4  717.32
  4914.3  718.17  4949.5  717.90  4971.9  717.42  4978.3  714.61  4990.2  714.09
  4990.6  713.59  4995.1  714.09  5004.4  714.82  5009.3  716.15  5021.4  717.48
  5068.6  719.07  5129.1  723.52  5176.3  725.23  5254.3  729.91  5269.2  729.99
#Mann=6,-1,0
  4039.4   0.035       0  4457.2    0.07       0  4475.7   0.035       0
  4990.2   0.035       0  4995.1   0.035       0  5004.4    0.07       0
Bank Sta=4990.2,4995.1
Exp/Cntr=0.3,0.1

Type RM Length L Ch R = 1,16196,470,470,470
BEGIN DESCRIPTION:
Fourmile Creek 28.0
END DESCRIPTION:
XS GIS Cut Line= 3
      2228824.99     13783175.01      2229825.00     13782675.00
      2230074.99     13782575.00
#Sta/Elev= 30
  3885.8  739.54  3899.5  741.64  3916.6  741.64  3930.5  736.94  3938.9  732.69
  3944.5  730.99  3961.3  729.37  4042.3  727.60  4123.4  727.04  4190.5  724.68
  4221.2  724.99  4406.6  720.04  4542.7  716.45  4634.7  716.28  4704.8  716.19
  4741.5  714.74  4741.8  714.24  4746.4  714.74  4816.6  715.73  4861.3  714.92
  4950.7  716.23  4995.5  714.78  5013.3  716.49  5042.9  716.32  5072.6  718.40
  5143.9  722.52  5165.4  724.81  5180.2  725.07  5240.8  729.74  5273.1  730.50
#Mann=7,-1,0
  3885.8    0.07       0  3899.5   0.035       0  4406.6    0.07       0
  4634.7   0.035       0  4741.5   0.035       0  4746.4   0.035       0
  5072.6    0.07       0
Bank Sta=4741.5,4746.4
Exp/Cntr=0.3,0.1

Type RM Length L Ch R = 1,15726,449,449,449
BEGIN DESCRIPTION:
Fourmile Creek 27.0
END DESCRIPTION:
XS GIS Cut Line= 3
      2229225.01     13783424.99      2229625.00     13783025.00
      2230174.96     13782625.03
#Sta/Elev= 30
  4430.4  726.32  4600.1  723.47  4614.2  722.16  4628.4  723.42  4642.5  723.50
  4678.8  722.20  4812.2  717.20  4953.6  715.94  4981.9  713.86  4990.0  710.77
  4990.4  710.27  4995.0  710.77  4999.2  710.77  5003.4  712.34  5053.6  714.13
  5162.2  714.67  5168.8  714.38  5175.0  715.11  5189.7  713.94  5195.8  714.60
  5210.5  714.07  5231.4  715.13  5346.5  715.01  5396.8  716.54  5446.2  720.35
  5511.9  725.87  5589.6  730.97  5639.4  733.14  5676.0  733.37  5676.1  733.37
#Mann=7,-1,0
  4430.4   0.035       0  4678.8    0.07       0  4990.0    0.05       0
  4995.0    0.07       0  5162.2   0.035       0  5446.2    0.07       0
  5676.0   0.035       0
Bank Sta=4990,4995
Exp/Cntr=0.3,0.1

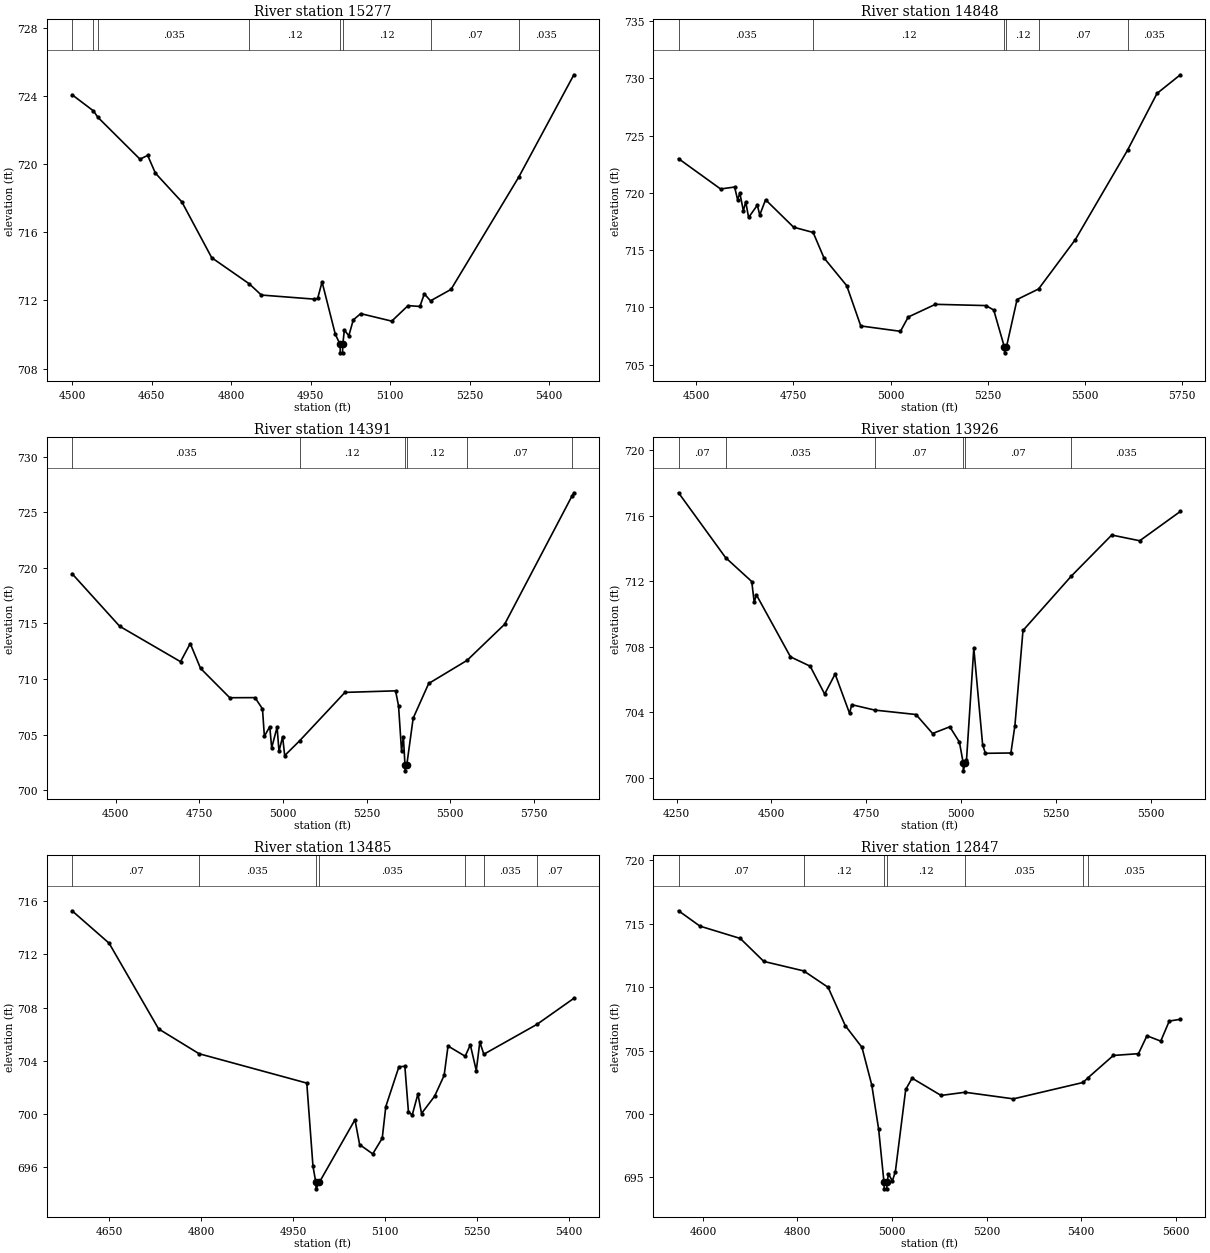
Type RM Length L Ch R = 1,15277,429,429,429
BEGIN DESCRIPTION:
Fourmile Creek 26.0
END DESCRIPTION:
XS GIS Cut Line= 3
      2229574.98     13783575.02      2229975.00     13783275.00
      2230174.98     13782875.04
#Sta/Elev= 30
  4499.7  724.06  4540.1  723.11  4548.3  722.74  4627.9  720.28  4642.4  720.50
  4657.0  719.46  4707.0  717.77  4763.3  714.50  4834.1  712.97  4857.0  712.31
  4957.0  712.07  4963.3  712.11  4971.6  713.08  4996.6  710.01  5005.6  709.42
  5006.0  708.92  5010.3  708.92  5010.7  709.42  5013.7  710.26  5022.1  709.92
  5030.5  710.85  5044.5  711.22  5103.1  710.78  5133.9  711.69  5156.3  711.64
  5164.6  712.38  5176.3  711.97  5215.0  712.64  5342.9  719.23  5446.9  725.23
#Mann=8,-1,0
  4499.7   0.035       0  4540.1   0.094       0  4548.3   0.035       0
  4834.1    0.12       0  5005.6    0.05       0  5010.7    0.12       0
  5176.3    0.07       0  5342.9   0.035       0
Bank Sta=5005.6,5010.7
Exp/Cntr=0.3,0.1

Type RM Length L Ch R = 1,14848,457,457,457
BEGIN DESCRIPTION:
Fourmile Creek 25.0
END DESCRIPTION:
XS GIS Cut Line= 3
      2229774.98     13783825.02      2230225.00     13783525.00
      2230225.00     13782774.96
#Sta/Elev= 30
  4454.3  722.99  4562.5  720.34  4598.6  720.51  4606.1  719.42  4612.1  719.97
  4621.1  718.43  4627.1  719.22  4634.6  717.85  4657.1  718.93  4663.2  718.06
  4678.2  719.40  4750.3  717.00  4800.6  716.54  4828.4  714.32  4887.0  711.89
  4923.1  708.37  5025.2  707.90  5045.2  709.15  5115.2  710.26  5245.2  710.15
  5265.2  709.76  5292.6  706.52  5293.0  706.02  5297.8  706.52  5325.2  710.68
  5380.5  711.60  5475.2  715.92  5609.4  723.73  5685.2  728.69  5745.2  730.32
#Mann=6,-1,0
  4454.3   0.035       0  4800.6    0.12       0  5292.6    0.05       0
  5297.8    0.12       0  5380.5    0.07       0  5609.4   0.035       0
Bank Sta=5292.6,5297.8
Exp/Cntr=0.3,0.1

Type RM Length L Ch R = 1,14391,465,465,465
BEGIN DESCRIPTION:
Fourmile Creek 24.0
END DESCRIPTION:
XS GIS Cut Line= 3
      2230074.96     13783975.02      2230625.00     13783675.00
      2230274.98     13782874.96
#Sta/Elev= 30
  4369.4  719.47  4511.8  714.74  4693.6  711.56  4722.6  713.19  4753.4  710.96
  4840.7  708.32  4916.2  708.33  4938.5  707.32  4944.2  704.86  4960.3  705.72
  4966.0  703.81  4982.2  705.68  4987.9  703.50  4998.7  704.82  5004.9  703.12
  5049.5  704.45  5185.0  708.80  5336.3  708.94  5345.2  707.59  5354.2  703.53
  5359.6  704.82  5364.5  702.25  5364.9  701.75  5369.7  702.25  5388.9  706.48
  5435.3  709.60  5550.1  711.68  5662.2  714.92  5863.8  726.46  5869.2  726.74
#Mann=6,-1,0
  4369.4   0.035       0  5049.5    0.12       0  5364.5   0.035       0
  5369.7    0.12       0  5550.1    0.07       0  5863.8   0.035       0
Bank Sta=5364.5,5369.7
Exp/Cntr=0.3,0.1

Type RM Length L Ch R = 1,13926,441,441,441
BEGIN DESCRIPTION:
Fourmile Creek 23.0
END DESCRIPTION:
XS GIS Cut Line= 3
      2230274.98     13784125.01      2230925.00     13783775.00
      2231125.00     13783225.00
#Sta/Elev= 30
  4255.0  717.39  4379.1  713.43  4448.1  711.97  4454.6  710.70  4460.3  711.16
  4550.3  707.37  4602.2  706.80  4640.4  705.10  4668.0  706.32  4706.1  703.92
  4711.8  704.45  4772.4  704.12  4881.3  703.85  4925.1  702.69  4970.5  703.10
  4995.9  702.16  5005.7  700.91  5006.1  700.41  5011.5  700.91  5014.5  701.05
  5033.8  707.90  5057.1  702.00  5064.4  701.48  5131.6  701.50  5142.2  703.17
  5163.5  708.98  5291.3  712.31  5397.6  714.81  5471.4  714.46  5578.5  716.25
#Mann=6,-1,0
  4255.0    0.07       0  4379.1   0.035       0  4772.4    0.07       0
  5005.7    0.05       0  5011.5    0.07       0  5291.3   0.035       0
Bank Sta=5005.7,5011.5
Exp/Cntr=0.3,0.1

Type RM Length L Ch R = 1,13485,638,638,638
BEGIN DESCRIPTION:
Fourmile Creek 22.0
END DESCRIPTION:
XS GIS Cut Line= 3
      2230375.02     13784175.00      2230775.00     13784125.00
      2231130.87     13783910.51
#Sta/Elev= 30
  4589.4  715.29  4649.8  712.85  4730.5  706.40  4796.6  704.53  4972.3  702.32
  4982.4  696.06  4987.0  694.86  4987.5  694.36  4992.9  694.86  5050.9  699.56
  5058.5  697.69  5079.9  696.99  5095.4  698.17  5101.2  700.55  5122.6  703.55
  5132.3  703.58  5138.1  700.18  5144.3  699.91  5153.6  701.50  5159.5  700.03
  5180.8  701.33  5196.4  702.90  5202.7  705.11  5230.7  704.34  5239.1  705.20
  5248.8  703.26  5254.6  705.41  5261.1  704.49  5347.8  706.74  5408.0  708.70
#Mann=7,-1,0
  4589.4    0.07       0  4796.6   0.035       0  4987.0   0.035       0
  4992.9   0.035       0  5230.7    0.07       0  5261.1   0.035       0
  5347.8    0.07       0
Bank Sta=4987,4992.9
Exp/Cntr=0.3,0.1

Type RM Length L Ch R = 1,12847,244,244,244
BEGIN DESCRIPTION:
X19213
END DESCRIPTION:
XS GIS Cut Line= 3
      2230521.97     13785005.46      2230830.33     13784605.25
      2231046.84     13784093.50
#Sta/Elev= 30
  4548.5  716.01  4593.8  714.80  4679.0  713.83  4728.8  712.02  4813.3  711.27
  4864.7  709.98  4901.0  706.96  4936.3  705.25  4957.1  702.27  4971.6  698.79
  4982.9  694.60  4983.4  694.10  4988.8  694.10  4989.3  694.60  4992.4  695.26
  5000.6  694.72  5006.9  695.45  5028.8  701.93  5042.3  702.82  5103.5  701.46
  5154.3  701.71  5256.5  701.19  5403.7  702.48  5414.5  702.86  5467.8  704.61
  5520.9  704.75  5538.8  706.16  5568.0  705.74  5586.0  707.32  5609.4  707.46
#Mann=7,-1,0
  4548.5    0.07       0  4813.3    0.12       0  4982.9    0.05       0
  4989.3    0.12       0  5154.3   0.035       0  5403.7    0.12       0
  5414.5   0.035       0
Bank Sta=4982.9,4989.3
Exp/Cntr=0.3,0.1

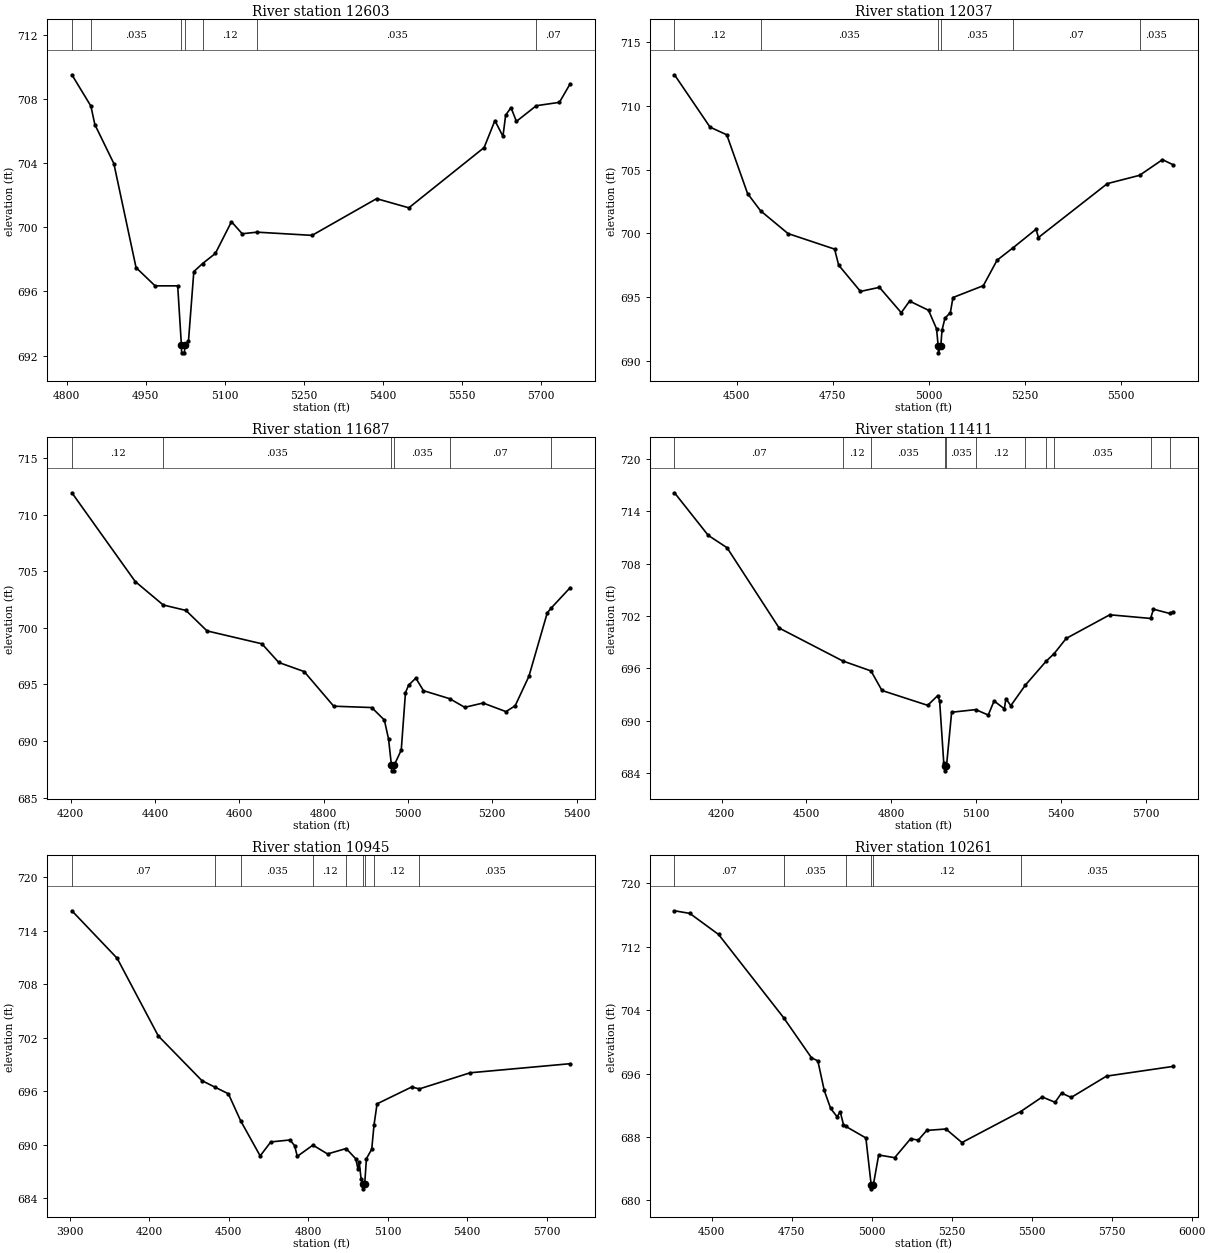
Type RM Length L Ch R = 1,12603,566,566,566
BEGIN DESCRIPTION:
Fourmile Creek 21.0
END DESCRIPTION:
XS GIS Cut Line= 3
      2230824.98     13784875.01      2230975.00     13784775.00
      2231125.01     13784024.96
#Sta/Elev= 30
  4810.2  709.52  4846.2  707.57  4853.8  706.41  4889.8  703.98  4931.9  697.49
  4968.0  696.35  5010.9  696.35  5017.9  692.67  5018.4  692.17  5023.8  692.17
  5024.3  692.67  5031.3  692.88  5041.5  697.24  5058.0  697.74  5082.3  698.37
  5112.9  700.35  5133.3  699.60  5161.3  699.70  5265.8  699.50  5388.2  701.79
  5449.4  701.22  5592.2  704.98  5612.6  706.66  5627.9  705.68  5633.0  707.00
  5643.2  707.47  5653.4  706.61  5691.1  707.59  5735.0  707.80  5755.4  708.96
#Mann=7,-1,0
  4810.2    0.07       0  4846.2   0.035       0  5017.9   0.035       0
  5024.3   0.035       0  5058.0    0.12       0  5161.3   0.035       0
  5691.1    0.07       0
Bank Sta=5017.9,5024.3
Exp/Cntr=0.3,0.1

Type RM Length L Ch R = 1,12037,350,350,350
BEGIN DESCRIPTION:
X19212
END DESCRIPTION:
XS GIS Cut Line= 4
      2230823.73     13785143.30      2231269.95     13785064.56
      2231466.80     13784841.46      2231919.51     13784533.10
#Sta/Elev= 30
  4337.5  712.44  4430.2  708.33  4473.7  707.73  4527.9  703.12  4561.7  701.77
  4633.3  699.98  4754.7  698.76  4765.3  697.50  4822.1  695.44  4871.5  695.76
  4928.4  693.77  4950.1  694.68  4999.5  693.96  5020.4  692.50  5024.7  691.12
  5025.2  690.62  5031.3  691.12  5034.6  692.39  5042.2  693.34  5056.4  693.78
  5063.1  694.96  5142.2  695.89  5178.1  697.89  5220.0  698.87  5279.6  700.32
  5285.9  699.67  5465.4  703.90  5549.4  704.55  5609.1  705.78  5635.9  705.39
#Mann=6,-1,0
  4337.5    0.12       0  4561.7   0.035       0  5024.7   0.035       0
  5031.3   0.035       0  5220.0    0.07       0  5549.4   0.035       0
Bank Sta=5024.7,5031.3
Exp/Cntr=0.3,0.1

Type RM Length L Ch R = 1,11687,276,276,276
BEGIN DESCRIPTION:
Fourmile Creek 20.0
END DESCRIPTION:
XS GIS Cut Line= 3
      2230825.02     13785225.00      2231625.00     13785175.00
      2231974.97     13785025.01
#Sta/Elev= 30
  4202.6  711.92  4352.9  704.08  4419.3  702.01  4473.1  701.53  4523.2  699.72
  4653.5  698.58  4693.5  696.93  4753.7  696.13  4823.8  693.07  4914.0  692.95
  4944.0  691.85  4954.0  690.16  4960.8  687.86  4961.3  687.36  4966.9  687.36
  4967.4  687.86  4984.1  689.20  4994.1  694.27  5001.6  694.93  5018.7  695.55
  5036.8  694.44  5099.2  693.73  5134.7  692.97  5178.2  693.35  5232.6  692.59
  5254.4  693.11  5287.0  695.71  5330.5  701.31  5338.9  701.70  5384.9  703.54
#Mann=6,-1,0
  4202.6    0.12       0  4419.3   0.035       0  4960.8   0.035       0
  4967.4   0.035       0  5099.2    0.07       0  5338.9   0.035       0
Bank Sta=4960.8,4967.4
Exp/Cntr=0.3,0.1

Type RM Length L Ch R = 1,11411,466,466,466
BEGIN DESCRIPTION:
X19211
END DESCRIPTION:
XS GIS Cut Line= 4
      2230738.42     13785596.05      2231630.84     13785471.37
      2231814.56     13785340.14      2232431.31     13785189.23
#Sta/Elev= 30
  4033.3  716.12  4152.7  711.24  4219.1  709.83  4403.4  700.63  4628.3  696.86
  4728.1  695.72  4766.9  693.48  4928.5  691.78  4964.1  692.90  4970.7  692.30
  4985.4  685.16  4988.3  684.78  4988.8  684.28  4994.9  684.78  5013.2  690.99
  5098.3  691.29  5142.7  690.67  5163.3  692.28  5199.7  691.38  5204.9  692.55
  5222.4  691.74  5273.5  694.08  5347.8  696.85  5375.6  697.70  5418.2  699.44
  5572.4  702.15  5716.7  701.73  5726.8  702.79  5784.2  702.30  5795.1  702.50
#Mann=11,-1,0
  4033.3    0.07       0  4628.3    0.12       0  4728.1   0.035       0
  4988.3   0.035       0  4994.9   0.035       0  5098.3    0.12       0
  5273.5   0.035       0  5347.8    0.07       0  5375.6   0.035       0
  5716.7    0.07       0  5784.2   0.035       0
Bank Sta=4988.3,4994.9
Exp/Cntr=0.3,0.1

Type RM Length L Ch R = 1,10945,684,684,684
BEGIN DESCRIPTION:
X19210
END DESCRIPTION:
XS GIS Cut Line= 4
      2230784.37     13785674.78      2231604.59     13785687.90
      2232070.46     13785727.27      2232660.46     13785668.27
#Sta/Elev= 30
  3908.4  716.26  4079.1  710.93  4234.5  702.20  4399.1  697.18  4446.7  696.47
  4499.1  695.70  4545.1  692.68  4619.1  688.72  4659.1  690.29  4731.4  690.51
  4748.9  689.88  4759.2  688.67  4818.1  689.93  4873.5  688.94  4943.7  689.55
  4980.0  688.39  4988.1  687.27  4993.1  688.01  5000.1  686.10  5006.8  685.52
  5007.3  685.02  5013.5  685.52  5020.2  688.41  5040.2  689.48  5048.8  692.20
  5060.3  694.57  5190.8  696.46  5220.2  696.25  5411.9  698.06  5789.2  699.08
#Mann=9,-1,0
  3908.4    0.07       0  4446.7    0.12       0  4545.1   0.035       0
  4818.1    0.12       0  4943.7   0.035       0  5006.8   0.035       0
  5013.5   0.035       0  5048.8    0.12       0  5220.2   0.035       0
Bank Sta=5006.8,5013.5
Exp/Cntr=0.3,0.1

Type RM Length L Ch R = 1,10261,468,468,468
BEGIN DESCRIPTION:
X19209
END DESCRIPTION:
XS GIS Cut Line= 3
      2230817.23     13785963.49      2231722.70     13785983.17
      2232371.14     13785924.22
#Sta/Elev= 30
  4384.2  716.54  4432.0  716.21  4522.0  713.55  4725.4  703.04  4812.1  698.00
  4832.1  697.60  4852.1  693.87  4872.1  691.60  4892.1  690.56  4902.1  691.17
  4912.1  689.56  4919.8  689.33  4982.1  687.88  4998.7  681.96  4999.2  681.46
  5005.5  681.96  5022.1  685.73  5072.1  685.39  5122.1  687.79  5145.6  687.60
  5172.2  688.83  5232.2  689.01  5282.2  687.30  5465.8  691.21  5533.2  693.05
  5573.3  692.38  5593.4  693.54  5623.6  692.99  5734.0  695.68  5941.0  696.90
#Mann=6,-1,0
  4384.2    0.07       0  4725.4   0.035       0  4919.8    0.12       0
  4998.7    0.05       0  5005.5    0.12       0  5465.8   0.035       0
Bank Sta=4998.7,5005.5
Exp/Cntr=0.3,0.1

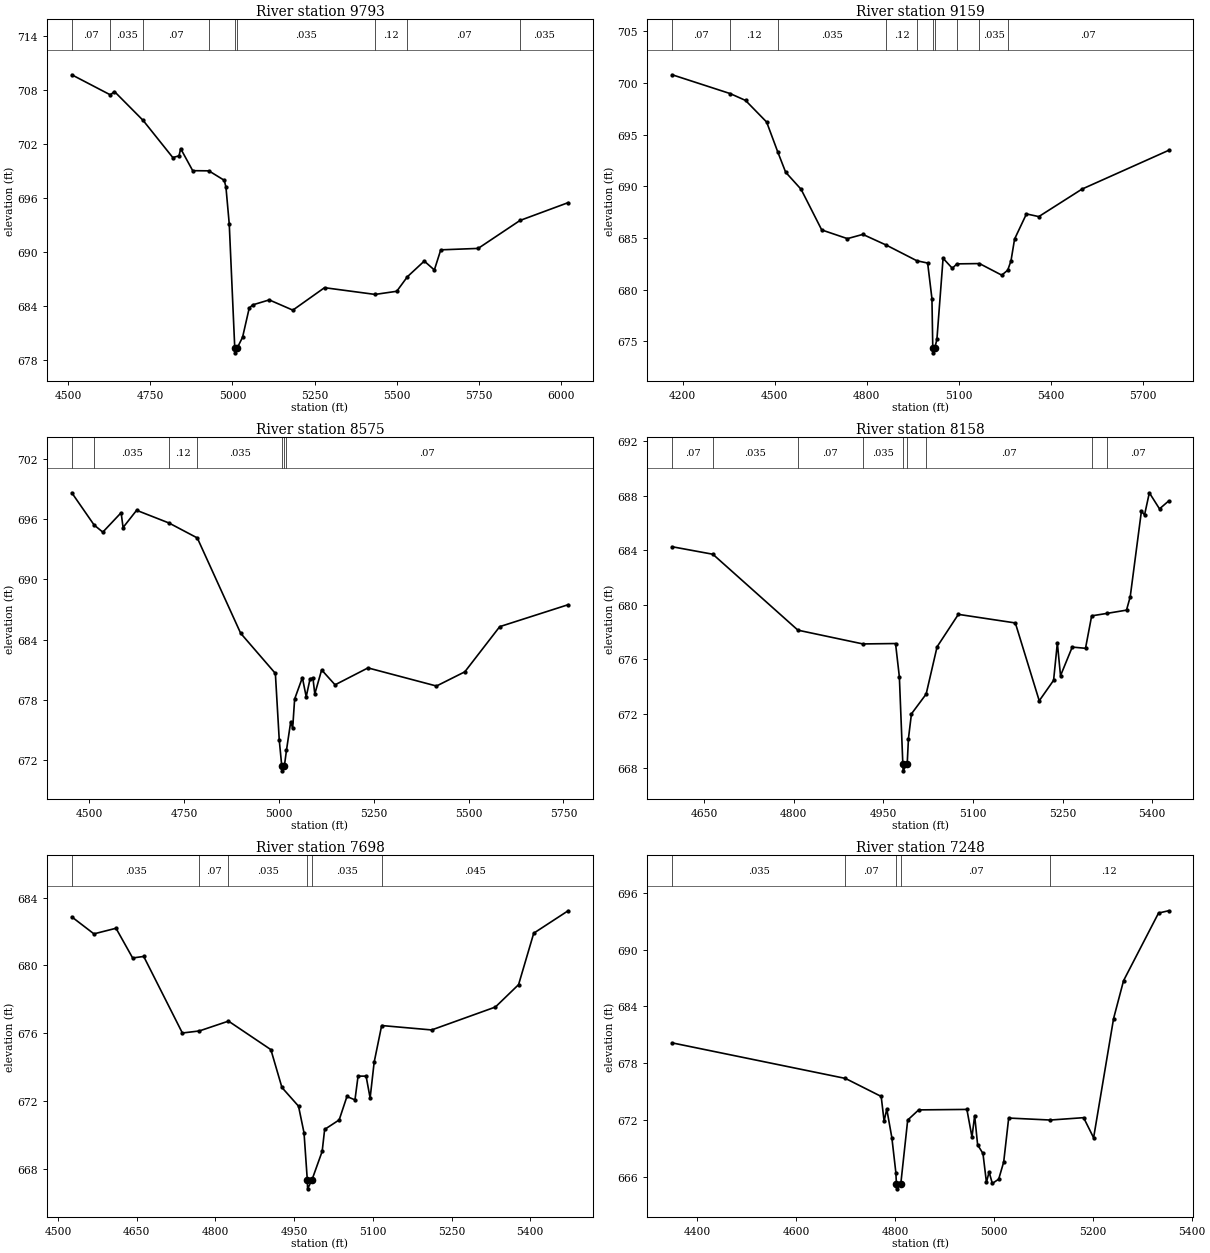
Type RM Length L Ch R = 1,9793,634,634,634
BEGIN DESCRIPTION:
X19208
END DESCRIPTION:
XS GIS Cut Line= 3
      2230790.99     13786429.35      2231355.25     13786344.05
      2232271.94     13786134.53
#Sta/Elev= 30
  4510.8  709.74  4627.9  707.51  4640.8  707.87  4728.0  704.66  4818.3  700.53
  4837.2  700.72  4842.3  701.52  4878.9  699.07  4928.1  699.05  4974.9  698.00
  4980.1  697.24  4990.2  693.12  5007.0  679.30  5007.5  678.80  5013.8  679.30
  5030.7  680.53  5050.9  683.77  5061.0  684.13  5112.0  684.69  5183.8  683.55
  5280.2  686.05  5434.2  685.30  5500.1  685.65  5532.6  687.27  5583.9  689.01
  5614.6  688.02  5634.1  690.26  5748.0  690.42  5875.4  693.53  6021.8  695.51
#Mann=9,-1,0
  4510.8    0.07       0  4627.9   0.035       0  4728.0    0.07       0
  4928.1   0.035       0  5007.0   0.035       0  5013.8   0.035       0
  5434.2    0.12       0  5532.6    0.07       0  5875.4   0.035       0
Bank Sta=5007,5013.8
Exp/Cntr=0.3,0.1

Type RM Length L Ch R = 1,9159,584,584,584
BEGIN DESCRIPTION:
X19207
END DESCRIPTION:
XS GIS Cut Line= 3
      2230797.54     13786704.94      2231958.91     13786573.71
      2232405.07     13786521.22
#Sta/Elev= 30
  4166.5  700.78  4355.6  698.96  4405.5  698.30  4474.3  696.21  4511.2  693.27
  4536.3  691.36  4586.6  689.71  4653.9  685.78  4737.6  684.94  4787.9  685.35
  4864.7  684.31  4964.1  682.80  4999.2  682.58  5013.2  679.14  5015.9  674.40
  5016.4  673.90  5022.8  674.40  5029.4  675.21  5049.5  683.04  5079.7  682.07
  5094.4  682.50  5168.2  682.53  5240.8  681.41  5260.2  681.89  5270.9  682.79
  5282.6  684.90  5321.3  687.33  5361.5  687.07  5502.5  689.73  5784.5  693.47
#Mann=10,-1,0
  4166.5    0.07       0  4355.6    0.12       0  4511.2   0.035       0
  4864.7    0.12       0  4964.1   0.035       0  5015.9   0.035       0
  5022.8   0.035       0  5094.4    0.07       0  5168.2   0.035       0
  5260.2    0.07       0
Bank Sta=5015.9,5022.8
Exp/Cntr=0.3,0.1

Type RM Length L Ch R = 1,8575,417,417,417
BEGIN DESCRIPTION:
X19206
END DESCRIPTION:
XS GIS Cut Line= 3
      2230836.85     13786855.84      2231558.66     13786987.08
      2232121.52     13786869.27
#Sta/Elev= 30
  4453.6  698.66  4512.5  695.44  4535.4  694.73  4583.7  696.67  4588.8  695.19
  4624.5  696.91  4710.0  695.64  4784.5  694.15  4898.9  684.63  4990.4  680.62
  5000.6  673.99  5007.2  671.39  5007.7  670.89  5014.2  671.39  5019.7  672.95
  5030.9  675.80  5036.0  675.14  5041.2  678.06  5061.6  680.20  5071.7  678.29
  5081.9  680.08  5089.4  680.17  5094.4  678.57  5112.4  680.97  5147.8  679.48
  5234.6  681.17  5415.2  679.36  5490.0  680.78  5582.0  685.29  5762.3  687.48
#Mann=7,-1,0
  4453.6    0.07       0  4512.5   0.035       0  4710.0    0.12       0
  4784.5   0.035       0  5007.2   0.035       0  5014.2   0.035       0
  5019.7    0.07       0
Bank Sta=5007.2,5014.2
Exp/Cntr=0.3,0.1

Type RM Length L Ch R = 1,8158,460,460,460
BEGIN DESCRIPTION:
Fourmile Creek 15.0
END DESCRIPTION:
XS GIS Cut Line= 3
      2231275.03     13787474.98      2231625.00     13787275.00
      2232025.02     13787124.99
#Sta/Elev= 30
  4596.9  684.26  4664.9  683.71  4807.2  678.14  4915.9  677.13  4970.5  677.16
  4976.9  674.71  4982.7  668.32  4983.2  667.82  4990.0  668.32  4992.1  670.19
  4997.1  672.00  5021.7  673.45  5040.0  676.92  5075.6  679.30  5170.9  678.67
  5210.9  672.96  5234.9  674.46  5241.2  677.20  5246.5  674.80  5266.1  676.90
  5288.3  676.81  5298.6  679.19  5324.0  679.37  5356.9  679.61  5363.1  680.59
  5381.8  686.86  5387.1  686.60  5395.1  688.22  5412.1  687.04  5427.2  687.61
#Mann=9,-1,0
  4596.9    0.07       0  4664.9   0.035       0  4807.2    0.07       0
  4915.9   0.035       0  4982.7   0.035       0  4990.0   0.035       0
  5021.7    0.07       0  5298.6   0.035       0  5324.0    0.07       0
Bank Sta=4982.7,4990
Exp/Cntr=0.3,0.1

Type RM Length L Ch R = 1,7698,450,450,450
BEGIN DESCRIPTION:
Fourmile Creek 14.0
END DESCRIPTION:
XS GIS Cut Line= 3
      2231324.98     13787524.99      2231775.00     13787675.00
      2232175.03     13787424.98
#Sta/Elev= 30
  4526.1  682.86  4568.3  681.86  4610.4  682.19  4642.1  680.44  4663.2  680.53
  4736.9  676.02  4769.1  676.14  4824.8  676.72  4905.6  675.04  4926.7  672.81
  4958.3  671.71  4968.8  670.14  4975.1  667.34  4975.6  666.84  4983.6  667.34
  5003.4  669.05  5008.1  670.34  5035.8  670.90  5050.6  672.28  5065.9  672.08
  5071.8  673.48  5087.1  673.48  5094.8  672.19  5102.5  674.30  5116.8  676.46
  5212.1  676.20  5333.6  677.55  5377.8  678.87  5406.7  681.90  5472.2  683.22
#Mann=6,-1,0
  4526.1   0.035       0  4769.1    0.07       0  4824.8   0.035       0
  4975.1   0.035       0  4983.6   0.035       0  5116.8   0.045       0
Bank Sta=4975.1,4983.6
Exp/Cntr=0.3,0.1

Type RM Length L Ch R = 1,7248,342,342,342
BEGIN DESCRIPTION:
Fourmile Creek 13.0
END DESCRIPTION:
XS GIS Cut Line= 3
      2231425.04     13787775.02      2232025.00     13788025.00
      2232374.99     13788075.00
#Sta/Elev= 30
  4349.6  680.15  4699.8  676.40  4772.1  674.50  4778.0  671.89  4783.4  673.17
  4793.7  670.14  4801.8  666.45  4802.9  665.25  4803.4  664.75  4811.7  665.25
  4825.7  672.01  4847.9  673.08  4945.4  673.13  4955.7  670.21  4961.1  672.48
  4967.1  669.39  4977.9  668.48  4984.9  665.44  4990.3  666.53  4996.8  665.32
  5009.7  665.77  5019.8  667.58  5029.9  672.22  5114.1  672.01  5181.4  672.26
  5201.6  670.14  5242.0  682.72  5262.2  686.72  5332.9  693.85  5353.1  694.09
#Mann=5,-1,0
  4349.6   0.035       0  4699.8    0.07       0  4802.9    0.05       0
  4811.7    0.07       0  5114.1    0.12       0
Bank Sta=4802.9,4811.7
Exp/Cntr=0.3,0.1