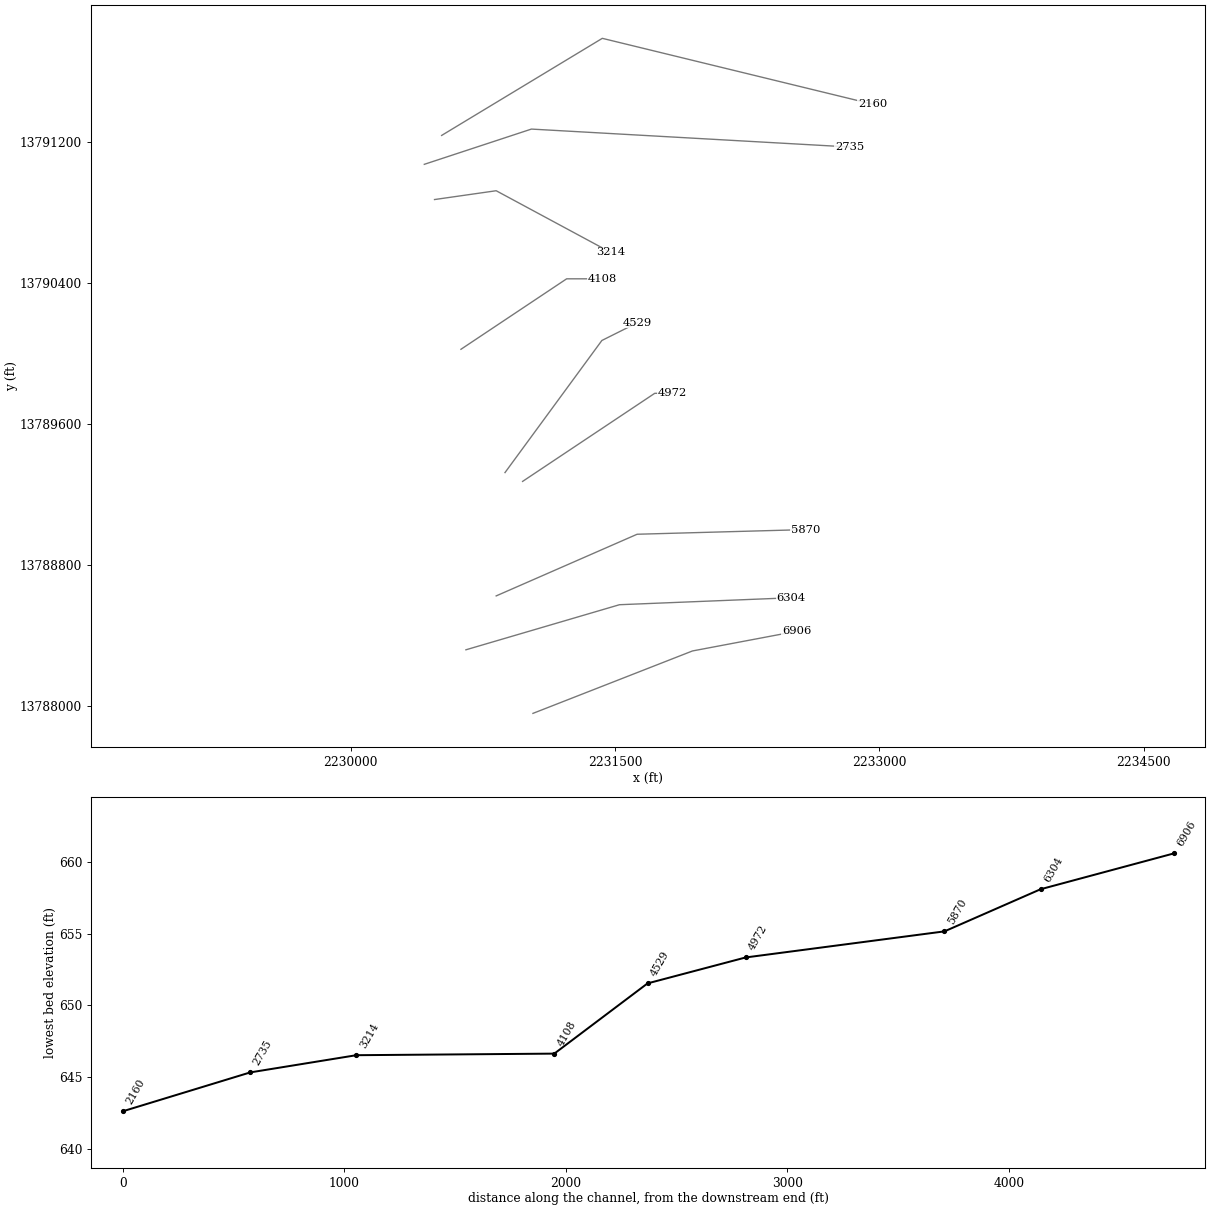
HEC-RAS study Fourmile Creek.prj: Fourmile Creek Base Level Engineering

--- Fourmile Creek.g01 (geometry) --- (continued)

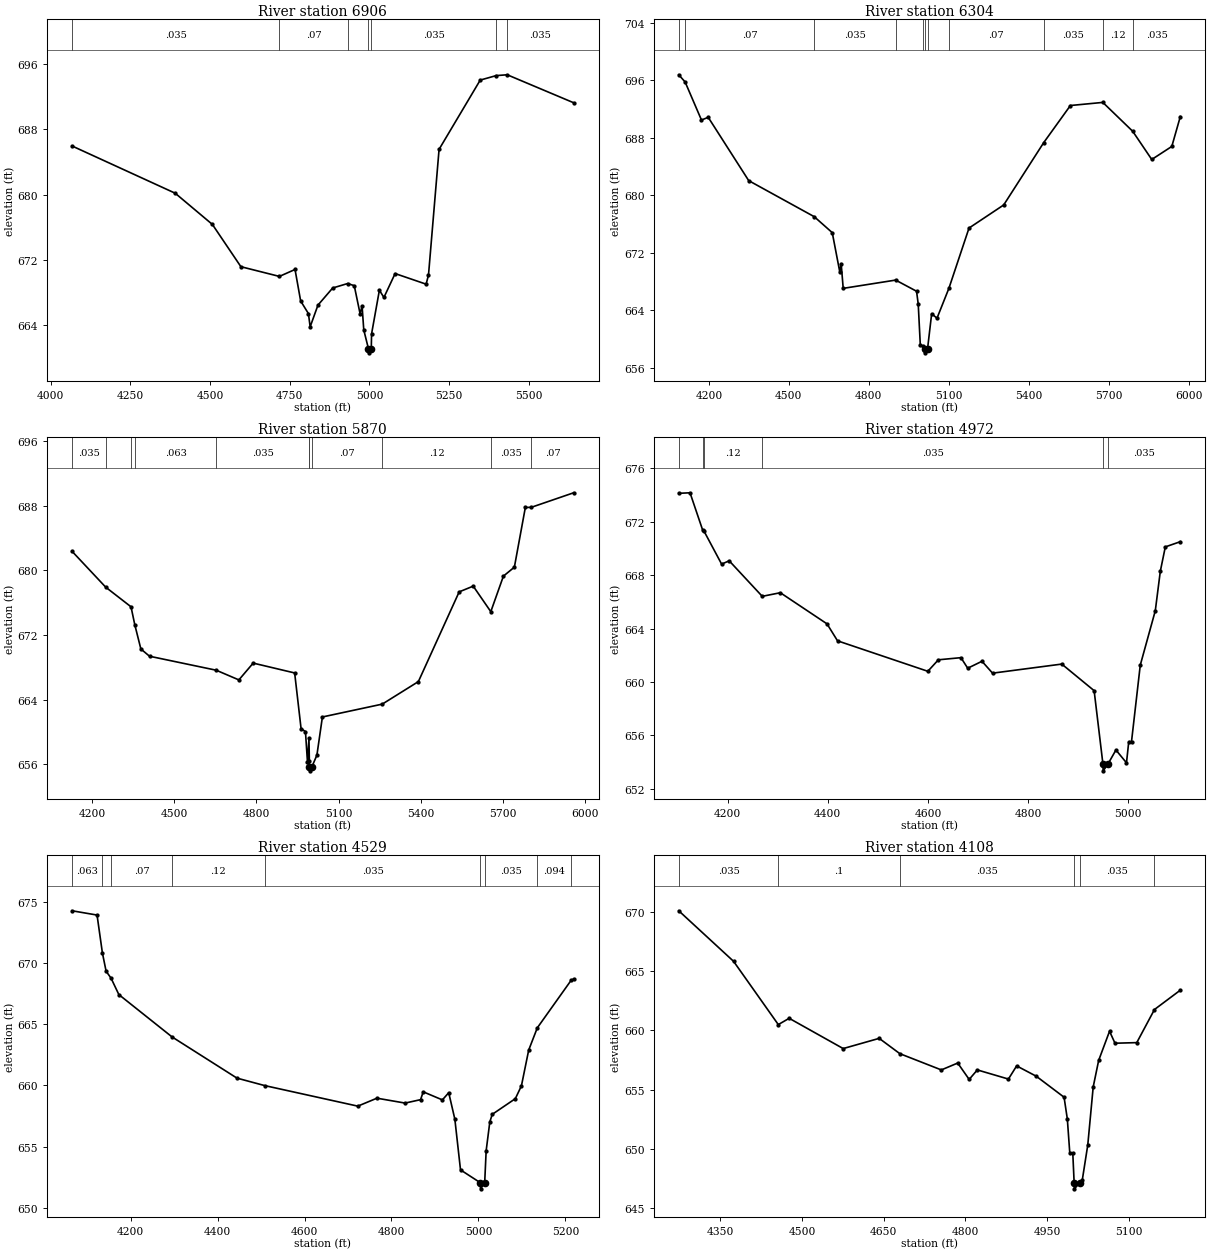
Type RM Length L Ch R = 1,6906,602,602,602
BEGIN DESCRIPTION:
Fourmile Creek 12.0
END DESCRIPTION:
XS GIS Cut Line= 3
      2231033.73     13787958.18      2231939.23     13788312.51
      2232529.73     13788424.05
#Sta/Elev= 30
  4067.1  685.97  4390.6  680.18  4507.3  676.35  4596.7  671.17  4717.4  669.98
  4766.5  670.83  4784.1  666.97  4808.5  665.42  4813.9  663.80  4838.4  666.46
  4884.6  668.56  4931.8  669.11  4952.3  668.84  4970.5  665.41  4976.8  666.35
  4982.1  663.42  4996.8  661.11  4997.3  660.61  5005.6  661.11  5006.6  662.94
  5031.1  668.29  5045.3  667.40  5080.4  670.33  5177.6  669.03  5185.1  670.14
  5218.3  685.56  5347.4  694.05  5397.6  694.60  5432.1  694.70  5640.4  691.27
#Mann=7,-1,0
  4067.1   0.035       0  4717.4    0.07       0  4931.8   0.035       0
  4996.8   0.035       0  5005.6   0.035       0  5397.6    0.12       0
  5432.1   0.035       0
Bank Sta=4996.8,5005.6
Exp/Cntr=0.3,0.1

Type RM Length L Ch R = 1,6304,434,434,434
BEGIN DESCRIPTION:
Fourmile Creek 11.0
END DESCRIPTION:
XS GIS Cut Line= 3
      2230653.21     13788319.09      2231525.00     13788575.00
      2232496.93     13788614.34
#Sta/Elev= 30
  4087.0  696.75  4110.9  695.75  4172.2  690.46  4197.5  690.84  4349.4  682.04
  4595.2  677.03  4662.8  674.81  4691.0  669.35  4696.2  670.51  4703.8  667.07
  4900.5  668.22  4978.9  666.67  4985.2  664.90  4993.0  659.21  5002.0  659.05
  5011.2  658.61  5011.7  658.11  5020.0  658.61  5035.6  663.55  5055.6  662.92
  5100.5  667.10  5175.7  675.45  5305.8  678.66  5456.0  687.33  5556.0  692.48
  5677.6  692.91  5789.6  688.90  5861.1  684.98  5936.3  686.79  5968.3  690.95
#Mann=11,-1,0
  4087.0     0.1       0  4110.9    0.07       0  4595.2   0.035       0
  4900.5    0.07       0  5002.0    0.12       0  5011.2    0.05       0
  5020.0    0.12       0  5100.5    0.07       0  5456.0   0.035       0
  5677.6    0.12       0  5789.6   0.035       0
Bank Sta=5011.2,5020
Exp/Cntr=0.3,0.1

Type RM Length L Ch R = 1,5870,898,898,898
BEGIN DESCRIPTION:
Fourmile Creek 10.0
END DESCRIPTION:
XS GIS Cut Line= 3
      2230825.02     13788625.01      2231625.00     13788975.00
      2232581.15     13789001.44
#Sta/Elev= 30
  4127.5  682.35  4250.3  677.91  4342.6  675.48  4356.4  673.25  4378.5  670.26
  4410.1  669.36  4653.3  667.63  4736.0  666.43  4788.2  668.51  4939.5  667.29
  4962.9  660.40  4978.9  660.03  4986.3  656.23  4991.7  659.18  4993.1  656.45
  4993.5  655.67  4994.0  655.17  5002.5  655.67  5020.7  657.12  5040.7  661.84
  5259.0  663.43  5390.8  666.22  5539.6  677.33  5590.9  678.04  5655.0  674.88
  5701.0  679.28  5741.0  680.39  5781.0  687.78  5802.8  687.80  5957.2  689.60
#Mann=11,-1,0
  4127.5   0.035       0  4250.3   0.063       0  4342.6   0.035       0
  4356.4   0.063       0  4653.3   0.035       0  4993.1    0.07       0
  4993.5    0.05       0  5002.5    0.07       0  5259.0    0.12       0
  5655.0   0.035       0  5802.8    0.07       0
Bank Sta=4993.5,5002.5
Exp/Cntr=0.3,0.1

Type RM Length L Ch R = 1,4972,443,443,443
BEGIN DESCRIPTION:
Fourmile Creek 8.0
END DESCRIPTION:
XS GIS Cut Line= 3
      2230975.00     13789275.00      2231725.00     13789775.00
      2231825.01     13789775.00
#Sta/Elev= 30
  4102.5  674.12  4125.0  674.16  4150.3  671.36  4153.2  671.27  4188.1  668.82
  4203.2  669.07  4269.2  666.41  4305.3  666.68  4398.5  664.35  4419.5  663.08
  4599.8  660.80  4620.8  661.66  4665.9  661.82  4679.4  661.03  4707.9  661.55
  4729.0  660.66  4867.2  661.34  4931.8  659.35  4949.4  653.85  4949.9  653.35
  4959.3  653.85  4975.3  654.91  4996.4  653.95  5000.9  655.53  5006.4  655.53
  5023.9  661.26  5053.9  665.33  5063.9  668.28  5073.9  670.11  5103.9  670.50
#Mann=6,-1,0
  4102.5   0.094       0  4150.3   0.035       0  4153.2    0.12       0
  4269.2   0.035       0  4949.4   0.035       0  4959.3   0.035       0
Bank Sta=4949.4,4959.3
Exp/Cntr=0.3,0.1

Type RM Length L Ch R = 1,4529,421,421,421
BEGIN DESCRIPTION:
Fourmile Creek 7.0
END DESCRIPTION:
XS GIS Cut Line= 3
      2230875.01     13789325.02      2231425.00     13790075.00
      2231624.97     13790174.98
#Sta/Elev= 30
  4065.4  674.27  4122.9  673.92  4135.2  670.82  4143.7  669.33  4155.1  668.76
  4173.0  667.42  4295.3  663.96  4444.7  660.59  4508.5  659.98  4722.6  658.30
  4766.6  658.95  4831.4  658.55  4866.9  658.83  4873.1  659.47  4917.1  658.81
  4931.7  659.40  4945.8  657.23  4958.8  653.09  5004.4  652.04  5004.9  651.54
  5014.4  652.04  5017.8  654.66  5026.2  657.01  5031.8  657.63  5084.9  658.91
  5098.9  659.96  5115.6  662.88  5135.4  664.70  5213.7  668.61  5219.0  668.68
#Mann=9,-1,0
  4065.4   0.063       0  4135.2   0.035       0  4155.1    0.07       0
  4295.3    0.12       0  4508.5   0.035       0  5004.4   0.035       0
  5014.4   0.035       0  5135.4   0.094       0  5213.7   0.035       0
Bank Sta=5004.4,5014.4
Exp/Cntr=0.3,0.1

Type RM Length L Ch R = 1,4108,894,894,894
BEGIN DESCRIPTION:
Fourmile Creek 6.0
END DESCRIPTION:
XS GIS Cut Line= 3
      2230625.00     13790025.00      2231225.00     13790425.00
      2231424.99     13790425.00
#Sta/Elev= 30
  4273.5  670.07  4374.2  665.81  4456.3  660.48  4476.3  661.01  4575.5  658.46
  4641.6  659.32  4679.5  658.03  4755.7  656.66  4785.8  657.24  4806.8  655.86
  4821.8  656.66  4878.9  655.89  4894.0  657.00  4930.0  656.13  4981.1  654.36
  4987.1  652.52  4991.6  649.65  4997.1  649.65  4999.6  647.14  5000.1  646.64
  5009.7  647.14  5014.6  647.40  5024.6  650.33  5034.6  655.23  5044.6  657.46
  5064.6  659.92  5074.6  658.91  5114.6  658.96  5147.1  661.75  5194.6  663.38
#Mann=6,-1,0
  4273.5   0.035       0  4456.3     0.1       0  4679.5   0.035       0
  4999.6   0.035       0  5009.7   0.035       0  5147.1   0.063       0
Bank Sta=4999.6,5009.7
Exp/Cntr=0.3,0.1

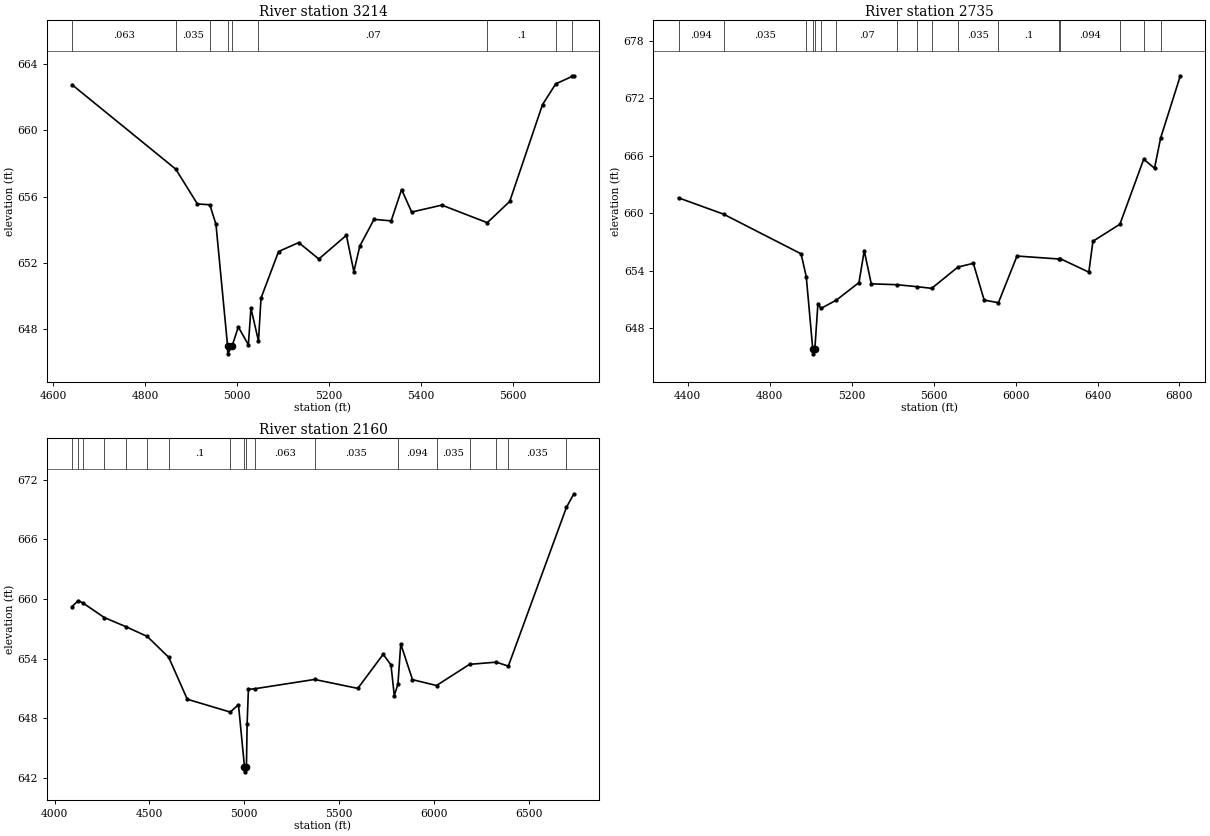
Type RM Length L Ch R = 1,3214,479,479,479
BEGIN DESCRIPTION:
Fourmile Creek 5.0
END DESCRIPTION:
XS GIS Cut Line= 3
      2230475.01     13790875.00      2230825.00     13790925.00
      2231475.01     13790574.99
#Sta/Elev= 30
  4641.3  662.76  4866.9  657.67  4914.0  655.57  4941.1  655.52  4954.4  654.34
  4979.6  647.03  4980.1  646.53  4989.8  647.03  5003.0  648.15  5024.9  647.08
  5030.5  649.28  5046.9  647.30  5052.4  649.89  5090.6  652.70  5134.4  653.24
  5178.2  652.25  5238.2  653.68  5254.4  651.49  5267.4  653.03  5298.3  654.64
  5335.6  654.55  5358.3  656.44  5380.2  655.08  5445.9  655.50  5544.7  654.44
  5593.5  655.72  5664.9  661.56  5693.6  662.81  5729.1  663.26  5733.1  663.30
#Mann=9,-1,0
  4641.3   0.063       0  4866.9   0.035       0  4941.1    0.12       0
  4979.6    0.05       0  4989.8    0.12       0  5046.9    0.07       0
  5544.7     0.1       0  5693.6   0.035       0  5729.1   0.063       0
Bank Sta=4979.6,4989.8
Exp/Cntr=0.3,0.1

Type RM Length L Ch R = 1,2735,575,575,575
BEGIN DESCRIPTION:
Fourmile Creek 4.0
END DESCRIPTION:
XS GIS Cut Line= 3
      2230416.97     13791074.92      2231025.00     13791275.00
      2232830.84     13791173.38
#Sta/Elev= 30
  4355.4  661.60  4574.9  659.90  4953.4  655.76  4978.8  653.37  5010.4  645.83
  5010.9  645.33  5020.6  645.83  5035.6  650.57  5050.5  650.06  5126.0  650.94
  5235.9  652.76  5261.7  656.08  5296.0  652.63  5422.4  652.54  5521.3  652.33
  5590.8  652.16  5718.9  654.38  5794.1  654.77  5846.8  650.94  5916.5  650.66
  6007.1  655.53  6213.0  655.22  6216.9  655.27  6357.7  653.85  6377.7  657.07
  6509.4  658.85  6625.5  665.63  6678.2  664.69  6708.1  667.84  6804.2  674.33
#Mann=17,-1,0
  4355.4   0.094       0  4574.9   0.035       0  4978.8     0.1       0
  5010.4    0.05       0  5020.6     0.1       0  5050.5    0.12       0
  5126.0    0.07       0  5422.4   0.035       0  5521.3   0.063       0
  5590.8   0.094       0  5718.9   0.035       0  5916.5     0.1       0
  6213.0   0.063       0  6216.9   0.094       0  6509.4   0.035       0
  6625.5   0.063       0  6708.1   0.035       0
Bank Sta=5010.4,5020.6
Exp/Cntr=0.3,0.1

Type RM Length L Ch R = 1,2160,0,0,0
BEGIN DESCRIPTION:
Fourmile Creek 3.0
END DESCRIPTION:
XS GIS Cut Line= 3
      2230515.34     13791238.93      2231427.43     13791790.12
      2232961.38     13791416.46
#Sta/Elev= 30
  4092.0  659.24  4124.7  659.84  4149.2  659.60  4262.2  658.13  4375.3  657.22
  4488.3  656.23  4601.3  654.14  4699.2  649.92  4925.5  648.63  4968.9  649.37
  5000.7  643.12  5001.2  642.62  5010.9  643.12  5014.6  647.46  5021.3  650.92
  5053.5  650.97  5369.9  651.91  5597.8  651.01  5731.6  654.44  5772.7  653.37
  5790.1  650.29  5809.3  651.43  5824.2  655.48  5886.0  651.89  6012.6  651.30
  6186.8  653.43  6327.9  653.65  6391.1  653.25  6697.5  669.22  6736.5  670.58
#Mann=18,-1,0
  4092.0   0.094       0  4124.7    0.07       0  4149.2   0.035       0
  4262.2    0.07       0  4375.3   0.035       0  4488.3    0.07       0
  4601.3     0.1       0  4925.5    0.12       0  5000.7    0.05       0
  5010.9    0.12       0  5053.5   0.063       0  5369.9   0.035       0
  5809.3   0.094       0  6012.6   0.035       0  6186.8    0.07       0
  6327.9   0.094       0  6391.1   0.035       0  6697.5   0.063       0
Bank Sta=5000.7,5010.9
Exp/Cntr=0.3,0.1

Chan Stop Cuts=-1