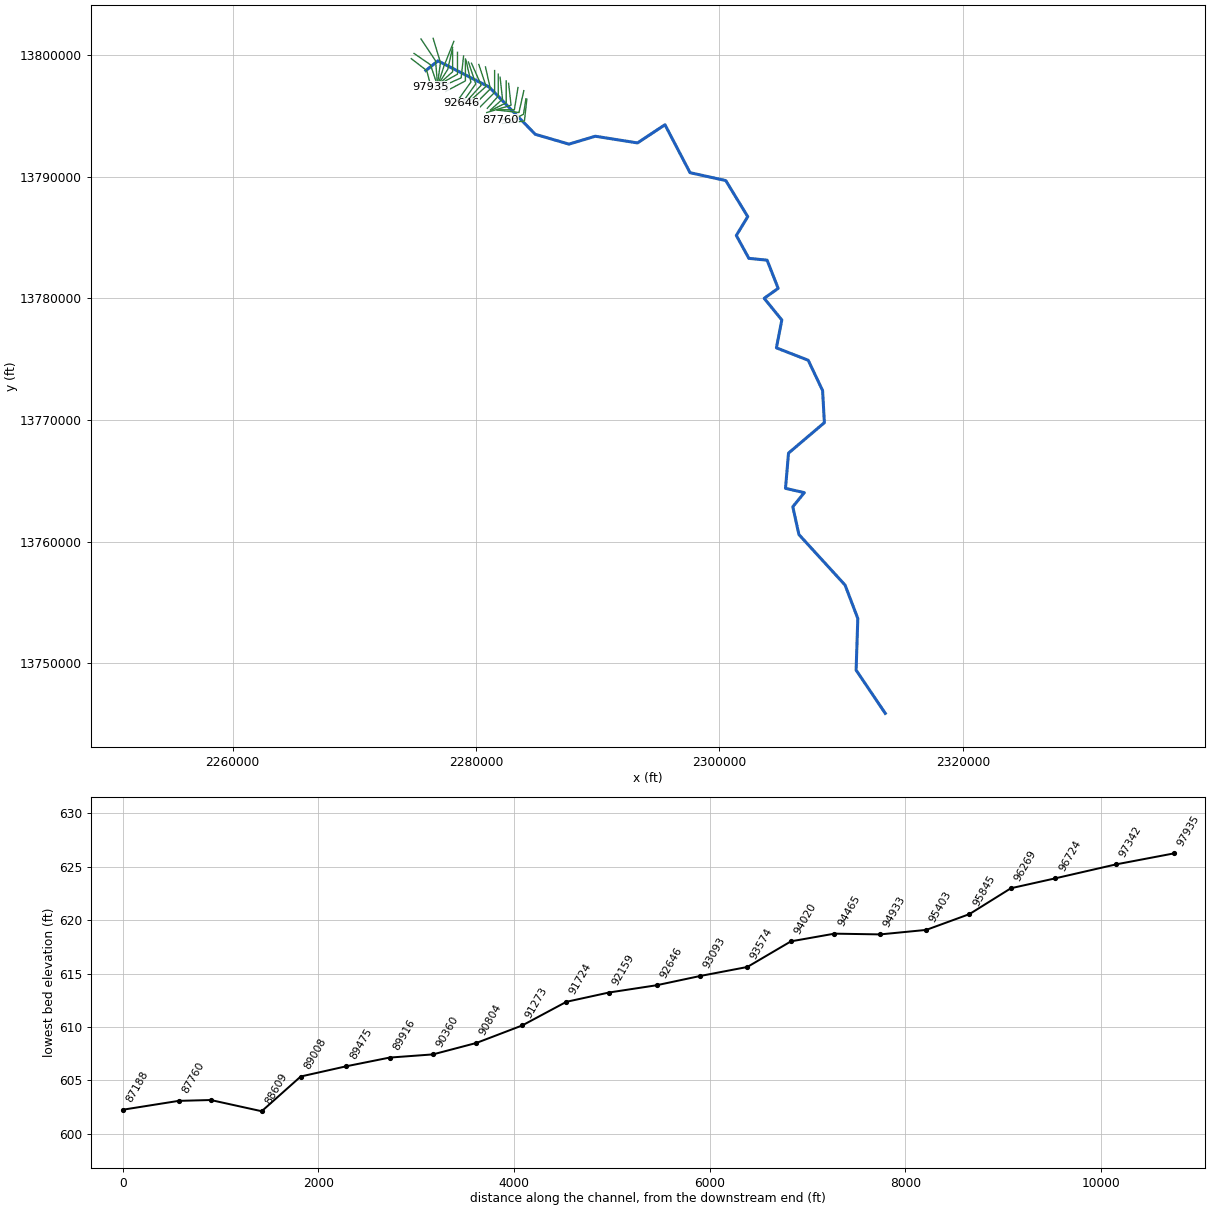
--- GERONIMO CREEK.prj (project) ---

Proj Title=GERONIMO CREEK Base Level Engineering
Current Plan=p01
Default Exp/Contr=0.3,0.1
English Units
Geom File=g01
Flow File=f01
Plan File=p01
Y Axis Title=Elevation
X Axis Title(PF)=Main Channel Distance
X Axis Title(XS)=Station
BEGIN DESCRIPTION:
GERONIMO CREEK
END DESCRIPTION:
DSS Export Rating Curves= 0
DSS Export Rating Curve Sorted= 0
DSS Export Volume Flow Curves= 0
DXF OffsetX= 0
DXF OffsetY= 0
DXF ScaleX= 1
DXF ScaleY= 10

--- GERONIMO CREEK.p01 (plan) ---

Plan Title=Multiple Run
Program Version=4.10
Short Identifier=Multiple
Geom File=g01
Flow File=f01
Subcritical Flow
K Sum by GR= 0
Std Step Tol= 0.01
Critical Tol= 0.01
Num of Std Step Trials= 20
Max Error Tol= 0.3
Flow Tol Ratio= 0.001
Split Flow NTrial= 30
Split Flow Tol= 0.02
Split Flow Ratio= 0.02
Log Output Level= 0
Friction Slope Method= 1
Unsteady Friction Slope Method= 2
Unsteady Bridges Friction Slope Method= 1
Parabolic Critical Depth
Global Vel Dist= 1 , 1 , 1
Global Log Level= 0
CheckData=True
Encroach Param=-1 ,0,0, 0
BEGIN DESCRIPTION:
Multiple Run
END DESCRIPTION:
Computation Interval=1HOUR
Output Interval=1HOUR
Run HTab= 0
Run UNet= 0
Run PostProcess= 0
Run WQNet= 0
UNET Theta= 1
UNET Theta Warmup= 1
UNET ZTol= 0.02
UNET ZSATol= 0.05
UNET MxIter= 20
UNET MaxInSteps= 0
UNET DtIC= 0
UNET DtMin= 0
UNET MaxCRTS= 20
UNET WFStab= 2
UNET SFStab= 1
UNET WFX= 1
UNET SFX= 1
UNET DSS MLevel= 4
UNET DZMax Abort= 100
UNET Convert EG Bridges= 0
UNET Use Existing IB Tables=-1
UNET Froude Reduction=False
UNET Froude Limit= 1
UNET Froude Power= 10
UNET Time Slicing=0,0, 5
UNET Junction Losses=0
Instantaneous Interval=1HOUR
Write IC File= 0
Write IC File at Sim End=0
Echo Input=False
Echo Parameters=False
Echo Output=False
Write Detailed= 0
WQ AD Non Conservative
WQ ULTIMATE=-1
WQ Max Comp Step=1HOUR
WQ Output Interval=15MIN
WQ Output Selected Increments= 0
WQ Output face flow=0
WQ Output face velocity=0
WQ Output face area=0
WQ Output face dispersion=0
WQ Output cell volume=0
WQ Output cell surface area=0
WQ Output cell continuity=0
WQ Output cumulative cell continuity=0
WQ Output face conc=0
WQ Output face dconc_dx=0
WQ Output face courant=0
WQ Output face peclet=0
WQ Output face adv mass=0
WQ Output face disp mass=0
WQ Output cell mass=0
WQ Output cell source sink temp=0
WQ Output cell source sink nsm=0
WQ Output MaxMinRange=-1
WQ Daily Max Min Mean=-1
WQ Daily Range=0
WQ Daily Time=0
WQ Create Restart=0
WQ Fixed Restart=0
WQ System Summary=0
WQ Use Fixed Temperature=0
Sorting and Armoring Iterations= 10
XS Update Threshold= 0.02
Hydraulics Update Threshold= 0.02
Energy Slope Method= 1
Volume Change Method= 0
XS Weighting Method= 0
Number of US Weighted Cross Sections= 1
Number of DS Weighted Cross Sections= 1
Upstream XS Weight=0.25
Main XS Weight=0.5
Downstream XS Weight=0.25
Number of DS XS's Weighted with US Boundary= 1
Upstream Boundary Weight= 1
Weight of XSs Associated with US Boundary= 0
Number of US XS's Weighted with DS Boundary= 1
Downstream Boundary Weight= 0.5
Weight of XSs Associated with DS Boundary= 0.5
Sediment Output Level= 4
Mass or Volume Output= 0
Output Increment Type= 1
Profile and TS Output Increment= 10
XS Output Flag= 0
XS Output Increment= 10
Disregard all LS=0
Disregard all Conn=0
Disregard all Breaches=0
Disregard all Pumps=0

--- GERONIMO CREEK.f01 (steady flow) ---

Flow Title=Multiple
Program Version=4.10
Number of Profiles= 7
Profile Names=10-year,25-year,50-year,1pct_min,100-year,1pct_plu,500-year
River Rch & RM=GERONIMO CREEK,Reach-1         ,97935
     465     714     926     580    1157    2309    1789
River Rch & RM=GERONIMO CREEK,Reach-1         ,96269
     927    1497    2009    1301    2596    5180    4294
River Rch & RM=GERONIMO CREEK,Reach-1         ,95403
    1070    1727    2318    1500    2992    5970    4938
River Rch & RM=GERONIMO CREEK,Reach-1         ,89475
    1353    2213    2996    1954    3899    7780    6543
River Rch & RM=GERONIMO CREEK,Reach-1         ,85334
    1417    2326    3157    2066    4122    8224    6966
River Rch & RM=GERONIMO CREEK,Reach-1         ,79215
    5106    8816   12386    8364   16688   33297   30029
River Rch & RM=GERONIMO CREEK,Reach-1         ,74277
    5388    9315   13101    8855   17668   35252   31849
River Rch & RM=GERONIMO CREEK,Reach-1         ,70128
    5373    9275   13030    8796   17550   35017   31559
River Rch & RM=GERONIMO CREEK,Reach-1         ,65828
    5579    9644   13560    9161   18279   36472   32926
River Rch & RM=GERONIMO CREEK,Reach-1         ,64898
    6118   10597   14922   10095   20142   40189   36373
River Rch & RM=GERONIMO CREEK,Reach-1         ,61758
    6004   10423   14697    9955   19862   39631   35972
River Rch & RM=GERONIMO CREEK,Reach-1         ,60638
    6030   10465   14755    9993   19939   39783   36100
River Rch & RM=GERONIMO CREEK,Reach-1         ,57894
    6121   10626   14984   10150   20252   40408   36678
River Rch & RM=GERONIMO CREEK,Reach-1         ,55750
    6213   10790   15218   10309   20570   41043   37264
River Rch & RM=GERONIMO CREEK,Reach-1         ,50742
    6178   10720   15110   10230   20412   40727   36932
River Rch & RM=GERONIMO CREEK,Reach-1         ,47404
    6781   11794   16654   11294   22534   44961   40897
River Rch & RM=GERONIMO CREEK,Reach-1         ,46190
    6873   11962   16899   11464   22874   45640   41550
River Rch & RM=GERONIMO CREEK,Reach-1         ,43511
    6878   11958   16880   11443   22831   45554   41404
River Rch & RM=GERONIMO CREEK,Reach-1         ,38591
    6880   11958   16877   11438   22822   45535   41370
River Rch & RM=GERONIMO CREEK,Reach-1         ,37641
    7646   13319   18828   12779   25498   50875   46350
River Rch & RM=GERONIMO CREEK,Reach-1         ,30849
    7657   13340   18858   12801   25540   50960   46433
River Rch & RM=GERONIMO CREEK,Reach-1         ,30423
    7871   13727   19421   13192   26322   52520   47925
River Rch & RM=GERONIMO CREEK,Reach-1         ,26645
    8140   14211   20120   13676   27287   54446   49746
River Rch & RM=GERONIMO CREEK,Reach-1         ,17837
    8166   14248   20165   13701   27338   54546   49795
River Rch & RM=GERONIMO CREEK,Reach-1         ,15340
    8436   14714   20820   14141   28216   56298   51360
River Rch & RM=GERONIMO CREEK,Reach-1         ,10028
    8474   14775   20902   14195   28322   56509   51530
River Rch & RM=GERONIMO CREEK,Reach-1         ,5771
    8636   15076   21345   14508   28946   57756   52755
Boundary for River Rch & Prof#=GERONIMO CREEK,Reach-1         , 1
Up Type= 0
Dn Type= 3
Dn Slope=0.0008
Boundary for River Rch & Prof#=GERONIMO CREEK,Reach-1         , 2
Up Type= 0
Dn Type= 3
Dn Slope=0.0008
Boundary for River Rch & Prof#=GERONIMO CREEK,Reach-1         , 3
Up Type= 0
Dn Type= 3
Dn Slope=0.0008
Boundary for River Rch & Prof#=GERONIMO CREEK,Reach-1         , 4
Up Type= 0
Dn Type= 3
Dn Slope=0.0008
Boundary for River Rch & Prof#=GERONIMO CREEK,Reach-1         , 5
Up Type= 0
Dn Type= 3
Dn Slope=0.0008
Boundary for River Rch & Prof#=GERONIMO CREEK,Reach-1         , 6
Up Type= 0
Dn Type= 3
Dn Slope=0.0008
Boundary for River Rch & Prof#=GERONIMO CREEK,Reach-1         , 7
Up Type= 0
Dn Type= 3
Dn Slope=0.0008
DSS Import GetInterval= 0
DSS Import GetPeak= 0
DSS Import FillOption= 0

--- GERONIMO CREEK.g01 (geometry) ---

Geom Title=Existing Conditions
Program Version=4.10

River Reach=GERONIMO CREEK  ,Reach-1
Reach XY= 30
        2275875.       13798725.      2276869.07     13799522.76
      2281077.67     13797369.58      2284868.95     13793483.16
      2287630.86     13792677.06      2289799.63      13793325.4
       2293264.5      13792776.2      2295523.54     13794271.47
      2297580.18     13790330.41      2300517.25     13789681.19
      2302323.81      13786714.5      2301384.03     13785167.99
      2302415.32     13783285.78      2303914.37       13783135.
      2304823.39     13780818.98      2303674.66     13780000.22
      2305123.72     13778218.96      2304678.61      13775926.5
      2307291.76     13774908.57      2308472.85     13772419.03
      2308621.25     13769776.55        2305675.       13767275.
        2305425.       13764375.      2306971.46     13764023.54
      2306024.96     13762859.66      2306528.45     13760576.25
      2310321.24     13756423.44      2311367.44       13753675.
      2311227.26     13749430.94        2313625.       13745875.

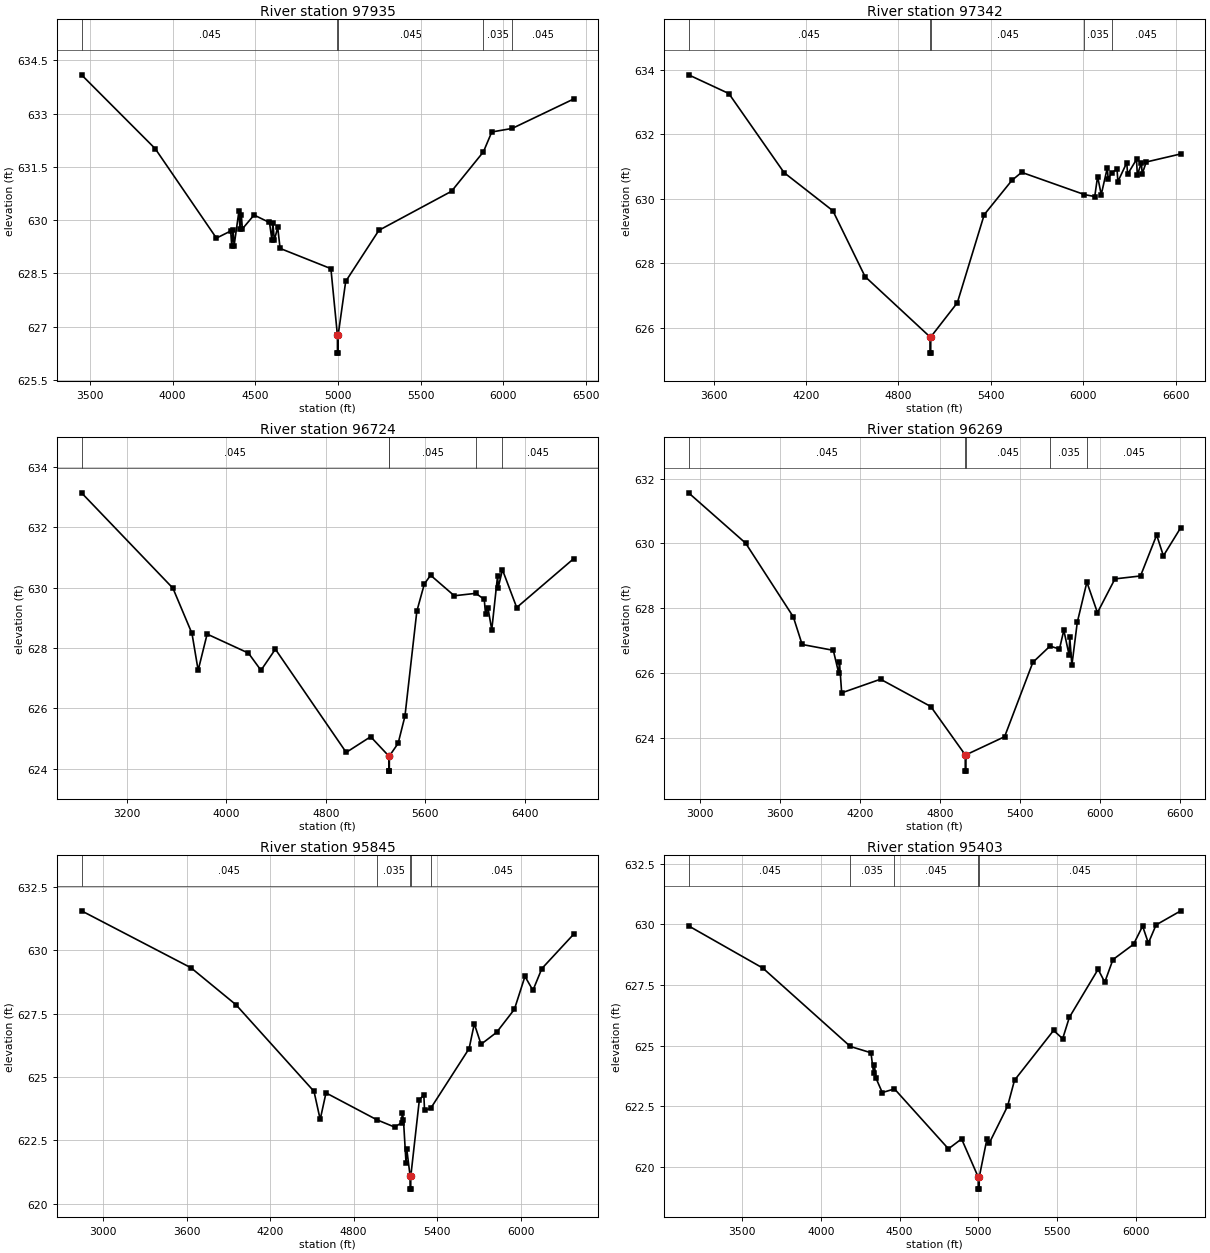
Type RM Length L Ch R = 1 ,97935   ,593,593,593
BEGIN DESCRIPTION:
A18964
END DESCRIPTION:
XS GIS Cut Line= 3
      2274678.73      13799703.3      2275946.93     13798725.86
      2276299.56     13797395.77
#Sta/Elev= 30
  3449.5  634.09  3895.1  632.01  4265.4  629.49  4351.7  629.69    4358  629.27
  4366.2  629.71  4372.5  629.28  4401.5  630.25  4407.8  629.74    4416  630.15
  4422.3  629.75    4493  630.14  4586.3  629.93  4600.8  629.45  4607.1  629.91
  4615.3  629.43  4636.1  629.79  4650.6   629.2  4957.8  628.63  4997.3  626.75
  4997.6  626.25  5001.2  626.25  5001.5  626.75  5047.3  628.27  5248.1  629.71
  5687.4  630.81  5880.2  631.92  5930.9  632.48  6054.3  632.58  6426.7  633.41
#Mann= 5 ,-1 , 0
  3449.5    .045       0  4997.3    .045       0  5001.5    .045       0
  5880.2    .035       0  6054.3    .045       0
Bank Sta=4997.3,5001.5
XS Rating Curve= 0 ,0
Exp/Cntr=0.3,0.1

Type RM Length L Ch R = 1 ,97342   ,618,618,618
BEGIN DESCRIPTION:
A18963
END DESCRIPTION:
XS GIS Cut Line= 3
      2274907.67     13800130.12      2276256.25     13799202.21
      2276750.57     13797725.41
#Sta/Elev= 30
    3438  633.84  3699.3  633.26  4057.8  630.81  4374.4  629.63  4583.4  627.59
  5005.4  625.72  5005.6  625.22  5009.3  625.22  5009.6  625.72    5182  626.78
  5356.7  629.51    5536  630.57  5599.3  630.82  6007.3  630.13  6073.8  630.07
  6092.3  630.69    6116  630.13  6155.4  630.96  6160.7  630.62  6185.3  630.81
  6218.6  630.92  6223.8  630.53  6281.7  631.12    6287  630.76  6344.9  631.22
  6350.1  630.73  6376.4  631.12  6381.7  630.77    6408  631.14  6632.3  631.39
#Mann= 5 ,-1 , 0
    3438    .045       0  5005.4    .045       0  5009.6    .045       0
  6007.3    .035       0  6185.3    .045       0
Bank Sta=5005.4,5009.6
XS Rating Curve= 0 ,0
Exp/Cntr=0.3,0.1

Type RM Length L Ch R = 1 ,96724   ,455,455,455
BEGIN DESCRIPTION:
GERONIMO CREEK 31.0
END DESCRIPTION:
XS GIS Cut Line= 3
      2275475.01     13801324.98        2276675.       13799525.
      2276819.04     13797738.01
#Sta/Elev= 30
  2836.7  633.14  3571.3  629.98  3724.5  628.48  3774.1  627.26  3846.2  628.46
  4178.2  627.83  4278.9  627.26  4394.6  627.96    4964  624.54  5160.5  625.06
  5306.4  624.42  5306.7  623.92  5310.4  623.92  5310.7  624.42  5381.2  624.84
    5436  625.74  5531.7  629.22  5591.9  630.12  5642.1  630.41  5832.7  629.73
  6005.8  629.81  6073.5  629.61  6083.5  629.13  6103.6  629.32  6133.7   628.6
  6180.6  630.39  6185.6     630  6219.8  630.59  6334.3  629.34  6792.8  630.96
#Mann= 5 ,-1 , 0
  2836.7    .045       0  5306.4    .045       0  5310.7    .045       0
  6005.8    .035       0  6219.8    .045       0
Bank Sta=5306.4,5310.7
XS Rating Curve= 0 ,0
Exp/Cntr=0.3,0.1

Type RM Length L Ch R = 1 ,96269   ,424,424,424
BEGIN DESCRIPTION:
GERONIMO CREEK 30.0
END DESCRIPTION:
XS GIS Cut Line= 3
      2276474.99     13801375.04        2277075.       13799375.
      2276856.32     13797785.57
#Sta/Elev= 30
  2912.4  631.56  3340.5  630.01  3698.1  627.74  3764.2  626.89  3998.2  626.71
  4039.1     626  4044.3  626.35  4060.9   625.4  4352.3  625.82  4729.1  624.98
  4987.9  623.49  4988.2  622.99    4992  622.99  4992.3  623.49  5283.1  624.05
  5495.1  626.34  5623.7  626.84  5694.7  626.75  5727.3  627.33  5766.7  626.57
  5771.8  627.11  5787.8  626.25  5828.2  627.57  5900.3  628.81  5979.6  627.87
  6110.9  628.91  6302.7     629  6423.8  630.26  6474.3  629.62  6604.9  630.49
#Mann= 5 ,-1 , 0
  2912.4    .045       0  4987.9    .045       0  4992.3    .045       0
  5623.7    .035       0  5900.3    .045       0
Bank Sta=4987.9,4992.3
XS Rating Curve= 0 ,0
Exp/Cntr=0.3,0.1

Type RM Length L Ch R = 1 ,95845   ,442,442,442
BEGIN DESCRIPTION:
GERONIMO CREEK 29.0
END DESCRIPTION:
XS GIS Cut Line= 3
      2278174.99     13801124.98        2277375.       13799125.
      2276949.55     13797811.64
#Sta/Elev= 30
    2846  631.56  3632.2  629.31  3955.3  627.85  4515.4  624.43  4559.8  623.32
  4601.5  624.37    4966  623.31  5094.7  623.02    5144  623.19  5149.3  623.59
  5157.7  623.31    5176  621.62  5181.3  622.16  5205.8  621.07  5206.1  620.57
  5209.9  620.57  5210.2  621.07    5272   624.1    5304  624.29  5309.2  623.68
  5353.4  623.76  5629.1  626.12  5666.4   627.1  5714.8  626.29  5826.4  626.76
  5954.3  627.67  6030.2  628.97  6087.5  628.42  6151.5  629.28  6380.6  630.64
#Mann= 5 ,-1 , 0
    2846    .045       0    4966    .035       0  5205.8    .035       0
  5210.2    .035       0  5353.4    .045       0
Bank Sta=5205.8,5210.2
XS Rating Curve= 0 ,0
Exp/Cntr=0.3,0.1

Type RM Length L Ch R = 1 ,95403   ,470,470,470
BEGIN DESCRIPTION:
GERONIMO CREEK 28.0
END DESCRIPTION:
XS GIS Cut Line= 3
      2278075.01     13800625.04        2277675.       13798825.
      2276992.42     13797742.25
#Sta/Elev= 30
  3160.7  629.94    3632   628.2  4187.2  624.97  4318.3  624.71    4335  623.86
  4340.1  624.22    4349  623.68    4390  623.07  4467.5  623.22    4810  620.75
  4893.3  621.16  4998.7  619.59  4999.2  619.09    5005  619.09  5005.5  619.59
  5054.7  621.17    5070     621  5185.3  622.51  5229.3  623.58  5477.2  625.63
  5534.9  625.29  5577.3  626.17  5759.7  628.15  5802.1  627.62  5853.9  628.55
  5984.5  629.18  6042.2  629.93  6078.7  629.23  6127.7  629.98  6284.6  630.56
#Mann= 5 ,-1 , 0
  3160.7    .045       0  4187.2    .035       0  4467.5    .045       0
  4998.7    .045       0  5005.5    .045       0
Bank Sta=4998.7,5005.5
XS Rating Curve= 0 ,0
Exp/Cntr=0.3,0.1

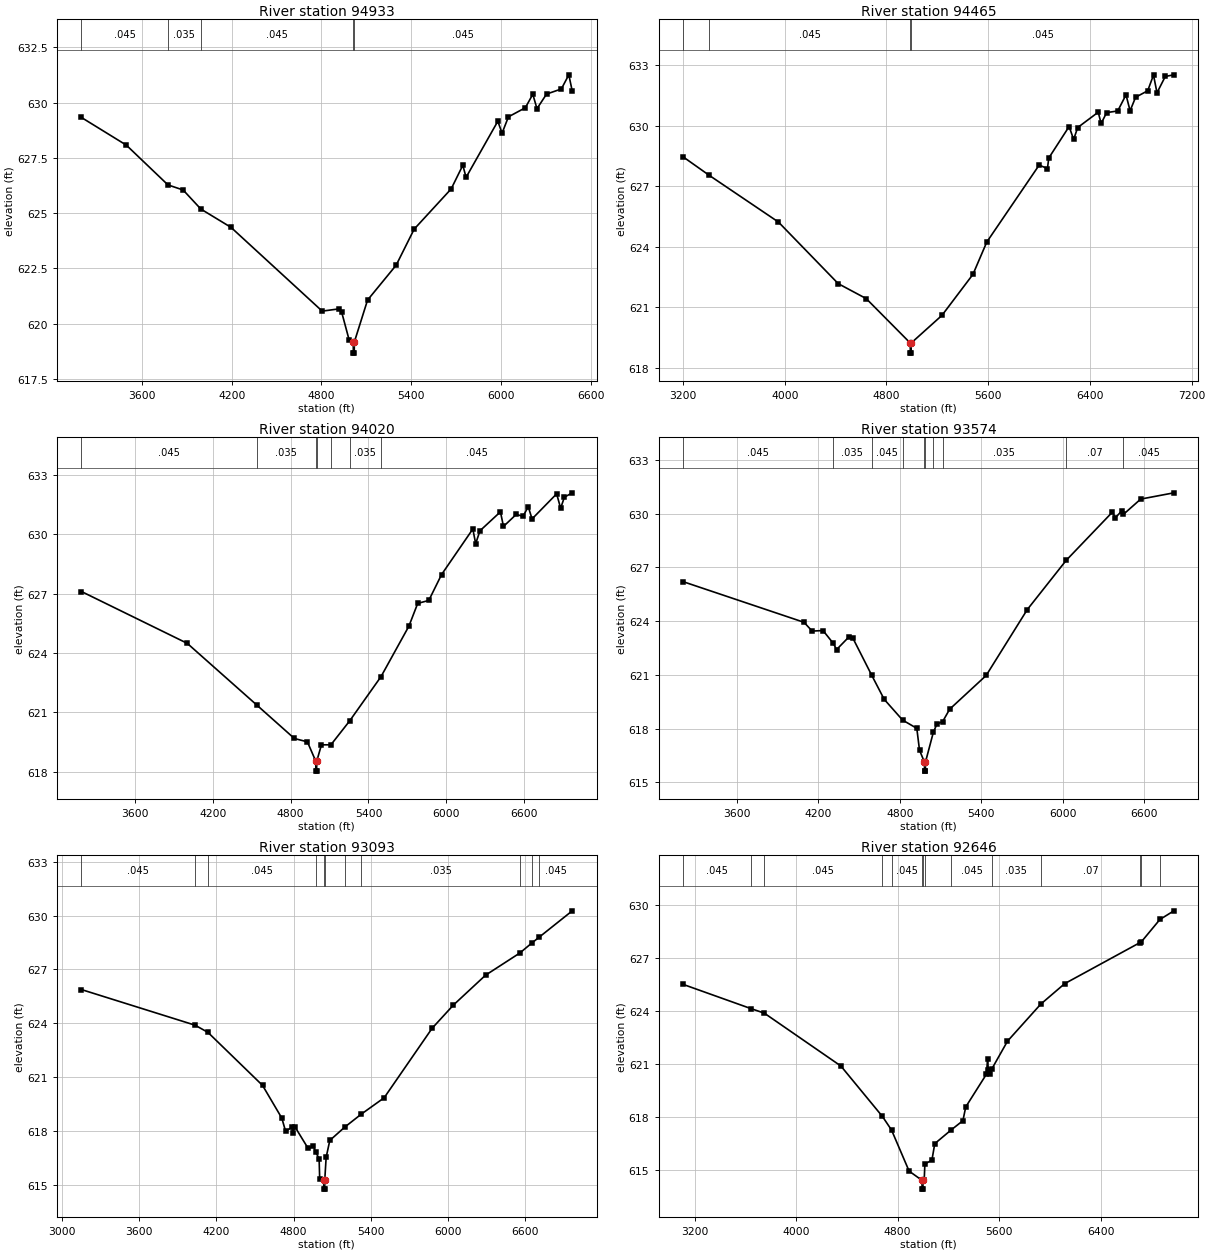
Type RM Length L Ch R = 1 ,94933   ,468,468,468
BEGIN DESCRIPTION:
GERONIMO CREEK 27.0
END DESCRIPTION:
XS GIS Cut Line= 3
        2278075.     13800425.02        2278075.       13798625.
      2276968.86     13797638.14
#Sta/Elev= 30
  3195.2  629.33  3495.2  628.08  3773.7  626.28  3875.2  626.05  3993.3  625.19
  4195.2  624.36  4805.2  620.57  4915.2  620.67  4935.2  620.53  4985.2  619.27
    5013  619.17  5013.5  618.67  5019.5  618.67    5020  619.17  5108.5  621.07
    5300  622.65  5420.3  624.28  5667.8   626.1  5745.7  627.17  5767.3  626.62
  5979.7  629.16  6008.1  628.62  6050.7  629.36  6163.6  629.77  6213.7  630.38
  6241.5  629.73  6305.7  630.39  6404.4  630.62  6454.5  631.26  6477.6  630.52
#Mann= 5 ,-1 , 0
  3195.2    .045       0  3773.7    .035       0  3993.3    .045       0
    5013    .045       0    5020    .045       0
Bank Sta=5013,5020
XS Rating Curve= 0 ,0
Exp/Cntr=0.3,0.1

Type RM Length L Ch R = 1 ,94465   ,445,445,445
BEGIN DESCRIPTION:
GERONIMO CREEK 26.0
END DESCRIPTION:
XS GIS Cut Line= 3
        2278475.     13800224.96        2278475.       13798425.
      2276674.98     13797424.99
#Sta/Elev= 30
  3200.7  628.46  3407.2  627.54  3950.7  625.23  4420.7  622.18  4640.7  621.44
  4987.1  619.24  4987.6  618.74  4993.7  618.74  4994.2  619.24  5236.3  620.61
    5480  622.64  5588.7  624.24  6000.5  628.05  6065.7  627.88    6076   628.4
  6236.1  629.96  6271.6  629.32  6303.6  629.91  6464.9  630.67  6487.8  630.11
  6531.3  630.65  6618.2  630.73  6683.4  631.53  6715.5  630.74  6758.9  631.41
  6853.9  631.73  6899.6  632.51  6927.1  631.63  6992.3  632.44  7059.8  632.52
#Mann= 4 ,-1 , 0
  3200.7    .035       0  3407.2    .045       0  4987.1    .045       0
  4994.2    .045       0
Bank Sta=4987.1,4994.2
XS Rating Curve= 0 ,0
Exp/Cntr=0.3,0.1

Type RM Length L Ch R = 1 ,94020   ,446,446,446
BEGIN DESCRIPTION:
GERONIMO CREEK 25.0
END DESCRIPTION:
XS GIS Cut Line= 3
        2278975.       13799925.        2278775.       13798125.
      2276975.04     13797325.02
#Sta/Elev= 30
  3189.2   627.1  4004.2  624.48  4538.3  621.37  4829.2  619.67  4929.8   619.5
  4994.2  618.52  4994.7  618.02  5000.9  618.02  5001.4  618.52  5037.9  619.35
  5110.6  619.35  5255.3  620.56  5496.9   622.8  5711.6  625.35  5779.3   626.5
  5864.8  626.65  5963.3  627.96    6204  630.26  6225.9  629.52  6258.7  630.17
  6416.7  631.13    6440  630.39  6538.5     631  6590.5   630.9  6630.8  631.39
  6660.2  630.77  6849.7  632.04  6880.4  631.31  6909.2  631.87    6970  632.09
#Mann= 7 ,-1 , 0
  3189.2    .045       0  4538.3    .035       0  4994.2    .035       0
  5001.4    .035       0  5110.6    .045       0  5255.3    .035       0
  5496.9    .045       0
Bank Sta=4994.2,5001.4
XS Rating Curve= 0 ,0
Exp/Cntr=0.3,0.1

Type RM Length L Ch R = 1 ,93574   ,481,481,481
BEGIN DESCRIPTION:
GERONIMO CREEK 24.0
END DESCRIPTION:
XS GIS Cut Line= 3
        2279125.     13799675.03        2279125.       13797875.
        2277525.       13797025.
#Sta/Elev= 30
  3204.7   626.2  4094.7  623.93  4154.7  623.44  4234.7  623.47  4309.5  622.76
  4334.7  622.41  4424.7  623.11  4454.7  623.04  4592.5  620.98  4684.7  619.63
  4820.2  618.47  4924.7  618.01  4944.7  616.79  4981.1  616.12  4981.6  615.62
  4987.9  615.62  4988.4  616.12  5046.5  617.79  5072.7  618.25  5115.1  618.39
  5166.8  619.08    5435  620.96  5737.6  624.64  6024.1  627.39  6363.7  630.08
  6386.2  629.77  6431.5  630.14  6445.7  629.96  6572.2  630.81  6816.5  631.16
#Mann= 10 ,-1 , 0
  3204.7    .045       0  4309.5    .035       0  4592.5    .045       0
  4820.2    .035       0  4981.1    .035       0  4988.4    .035       0
  5046.5    .045       0  5115.1    .035       0  6024.1     .07       0
  6445.7    .045       0
Bank Sta=4981.1,4988.4
XS Rating Curve= 0 ,0
Exp/Cntr=0.3,0.1

Type RM Length L Ch R = 1 ,93093   ,447,447,447
BEGIN DESCRIPTION:
GERONIMO CREEK 23.0
END DESCRIPTION:
XS GIS Cut Line= 3
        2279175.     13799575.02        2279575.       13797775.
      2278425.02     13796175.03
#Sta/Elev= 30
  3151.8  625.88  4034.5   623.9  4134.6   623.5  4559.1  620.55  4708.9  618.73
  4738.4  617.99    4787  618.23  4792.1  617.91  4811.3  618.24  4913.8  617.04
  4954.8  617.16  4970.9  616.86  4998.8  616.47  5003.1  615.36  5034.8  615.28
  5035.3  614.78    5042  614.78  5042.5  615.28  5053.4  616.55  5081.9  617.49
  5196.4  618.22  5326.2  618.95    5504  619.86  5877.2  623.73  6042.5  625.02
  6292.2  626.68  6557.8  627.91  6655.5  628.49  6708.2  628.79  6966.1  630.26
#Mann= 11 ,-1 , 0
  3151.8    .045       0  4034.5    .035       0  4134.6    .045       0
  4970.9    .035       0  5034.8    .035       0  5042.5    .035       0
  5196.4    .045       0  5326.2    .035       0  6557.8     .07       0
  6655.5    .035       0  6708.2    .045       0
Bank Sta=5034.8,5042.5
XS Rating Curve= 0 ,0
Exp/Cntr=0.3,0.1

Type RM Length L Ch R = 1 ,92646   ,487,487,487
BEGIN DESCRIPTION:
GERONIMO CREEK 22.0
END DESCRIPTION:
XS GIS Cut Line= 3
        2279375.     13799424.99        2279975.       13797625.
      2278824.98     13796024.97
#Sta/Elev= 30
    3109  625.52  3646.1  624.14  3748.8  623.89  4352.8  620.89  4680.1  618.03
  4751.9  617.26  4890.4  614.93  4991.9  614.41  4992.4  613.91  4999.3  613.91
  4999.8  614.41  5009.4  614.45  5014.6  615.33  5070.2  615.56  5092.6  616.49
  5224.1  617.28  5314.2  617.79  5336.6  618.57  5499.9  620.43  5508.5  621.27
  5514.6  620.68  5529.3  620.41    5541  620.71  5665.6   622.3  5927.8   624.4
  6116.2  625.56  6710.1  627.89  6721.4  627.94  6866.7   629.2  6976.8  629.69
#Mann= 14 ,-1 , 0
    3109    .045       0  3646.1    .035       0  3748.8    .045       0
  4680.1    .035       0  4751.9    .045       0  4991.9    .045       0
  4999.8    .045       0  5014.6    .035       0  5224.1    .045       0
    5541    .035       0  5927.8     .07       0  6710.1    .035       0
  6721.4     .07       0  6866.7    .045       0
Bank Sta=4991.9,4999.8
XS Rating Curve= 0 ,0
Exp/Cntr=0.3,0.1

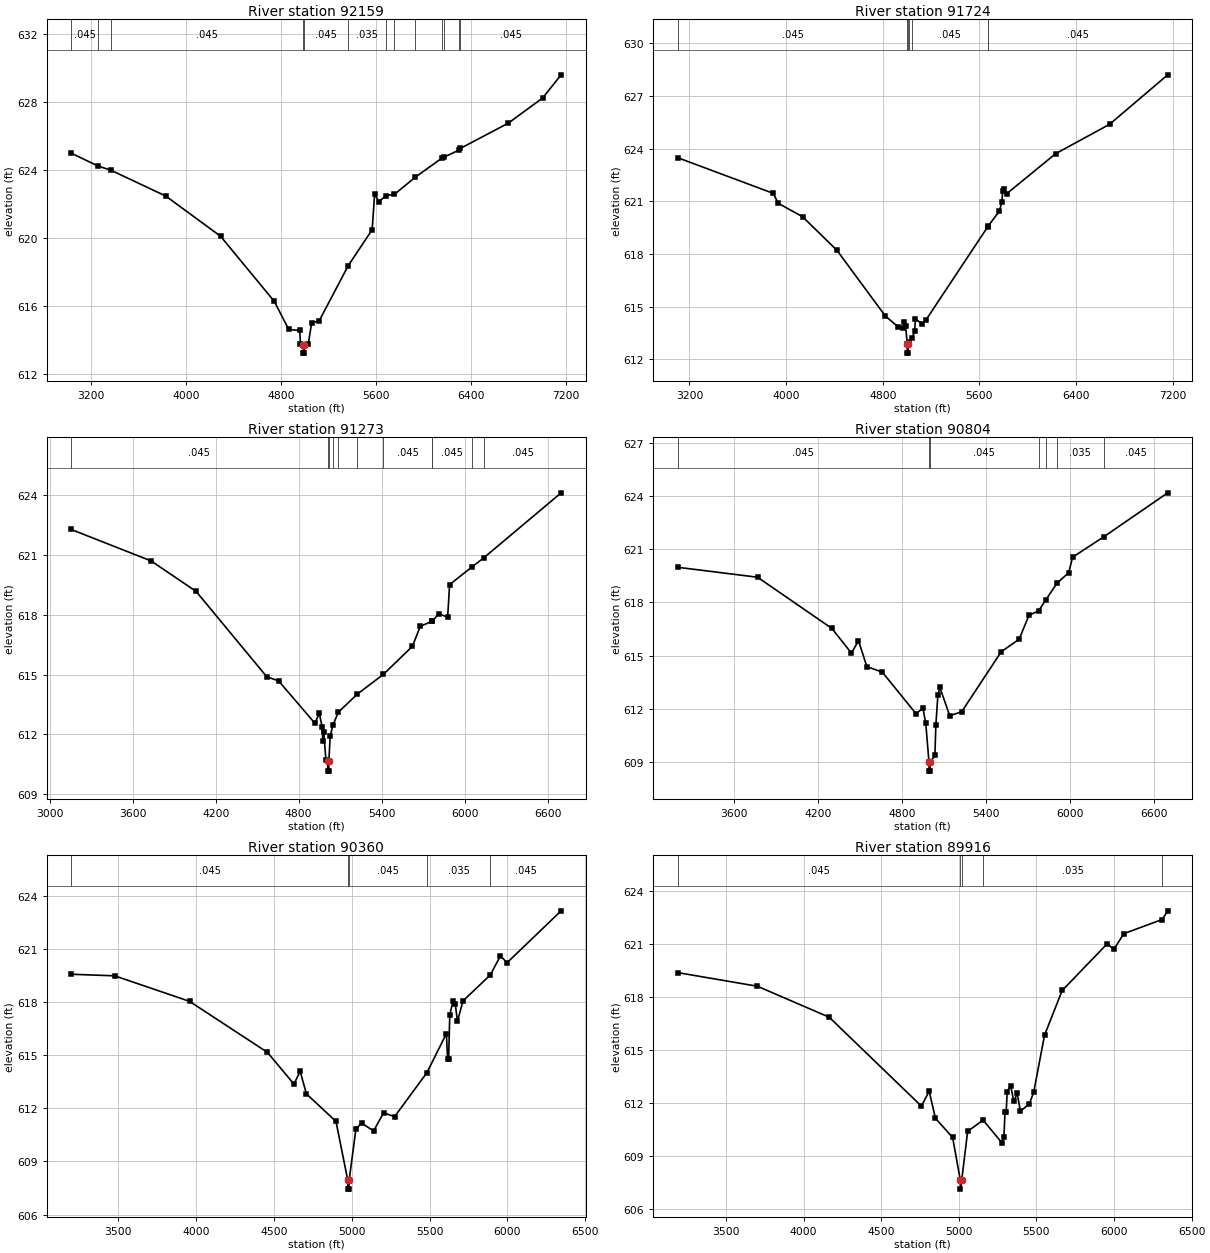
Type RM Length L Ch R = 1 ,92159   ,435,435,435
BEGIN DESCRIPTION:
GERONIMO CREEK 21.0
END DESCRIPTION:
XS GIS Cut Line= 3
      2279624.99     13799325.02        2280425.       13797525.
      2278974.98     13795924.98
#Sta/Elev= 30
  3030.2  624.98  3257.4  624.22  3363.7  623.98    3827  622.46  4288.7   620.1
  4742.1  616.27  4863.9  614.62  4956.2  614.56  4962.4  613.77  4987.1  613.73
  4987.6  613.23  4994.6  613.23  4995.1  613.73    5028  613.74  5056.4     615
  5120.6  615.13  5365.2  618.37  5566.7  620.48  5587.6  622.58  5622.8  622.13
  5686.1  622.49  5752.8  622.55    5931  623.57  6153.3  624.68  6174.6  624.75
  6295.4  625.15  6311.1  625.26  6713.6  626.74  7003.5  628.22  7159.3  629.58
#Mann= 13 ,-1 , 0
  3030.2    .045       0  3257.4    .035       0  3363.7    .045       0
  4987.1    .045       0  4995.1    .045       0  5365.2    .035       0
  5686.1    .045       0  5752.8    .035       0    5931    .045       0
  6153.3     .07       0  6174.6    .045       0  6295.4    .035       0
  6311.1    .045       0
Bank Sta=4987.1,4995.1
XS Rating Curve= 0 ,0
Exp/Cntr=0.3,0.1

Type RM Length L Ch R = 1 ,91724   ,451,451,451
BEGIN DESCRIPTION:
GERONIMO CREEK 20.0
END DESCRIPTION:
XS GIS Cut Line= 3
      2280224.99     13799225.02        2280825.       13797425.
      2279224.98     13795974.98
#Sta/Elev= 30
  3102.7  623.49  3893.3  621.46  3935.5  620.89  4135.7  620.13  4420.3  618.22
  4820.9  614.48  4926.3  613.86  4968.5  613.78    4979  614.15  4989.5  613.89
  5003.1  612.86  5003.6  612.36  5010.7  612.36  5011.2  612.86  5016.3  612.97
  5043.2   613.2    5064  613.61  5070.7  614.32  5127.5     614  5155.9  614.23
  5668.8  619.55  5673.5   619.6  5764.8  620.44  5785.7  620.94  5793.2  621.62
  5799.9  621.71  5828.3  621.45  6231.8  623.72  6677.8  625.39  7159.4  628.21
#Mann= 7 ,-1 , 0
  3102.7    .045       0  5003.1    .045       0  5011.2    .045       0
  5016.3     .07       0  5043.2    .045       0  5668.8    .035       0
  5673.5    .045       0
Bank Sta=5003.1,5011.2
XS Rating Curve= 0 ,0
Exp/Cntr=0.3,0.1

Type RM Length L Ch R = 1 ,91273   ,469,469,469
BEGIN DESCRIPTION:
GERONIMO CREEK 19.0
END DESCRIPTION:
XS GIS Cut Line= 3
      2280775.01     13799024.95        2281175.       13797225.
      2279975.01     13796025.01
#Sta/Elev= 30
  3155.9  622.29  3733.4  620.71  4058.6  619.18  4569.5  614.89  4655.3  614.68
  4917.8  612.55  4948.5  613.07    4969  612.39  4975.4  611.66  4980.6  612.12
  4997.2   610.7  5009.7  610.65  5010.2  610.15  5017.6  610.15  5018.1  610.65
    5028  611.92  5047.4  612.46    5087  613.11  5222.3  614.01  5412.1  615.01
    5622  616.42  5678.6  617.42  5763.4  617.68  5764.6  617.67  5812.9  618.06
  5876.6  617.88  5890.7  619.52  6051.1   620.4  6138.7  620.87  6696.8  624.13
#Mann= 11 ,-1 , 0
  3155.9    .045       0  5009.7    .045       0  5018.1    .045       0
  5047.4     .07       0    5087    .045       0  5222.3     .07       0
  5412.1    .045       0  5763.4    .035       0  5764.6    .045       0
  6051.1    .035       0  6138.7    .045       0
Bank Sta=5009.7,5018.1
XS Rating Curve= 0 ,0
Exp/Cntr=0.3,0.1

Type RM Length L Ch R = 1 ,90804   ,444,444,444
BEGIN DESCRIPTION:
GERONIMO CREEK 18.0
END DESCRIPTION:
XS GIS Cut Line= 3
        2281525.     13798725.02        2281525.       13796925.
      2280324.98     13795724.98
#Sta/Elev= 30
  3200.3  619.98  3770.3  619.42  4300.3  616.54  4440.3  615.15  4490.3  615.85
  4550.3  614.39  4660.3  614.08  4900.3  611.75  4950.3  612.04  4970.3  611.23
  4993.5  609.01    4994  608.51  5001.7  608.51  5002.2  609.01  5035.7  609.39
  5042.7  611.11  5056.9  612.78    5071  613.22  5141.7  611.63  5226.6  611.85
  5509.4  615.23  5636.7  615.93  5707.4  617.28  5775.8  617.53  5826.6  618.14
  5907.7  619.09  5990.3  619.67  6018.6  620.55  6240.2  621.69  6697.4  624.17
#Mann= 7 ,-1 , 0
  3200.3    .045       0  4993.5    .045       0  5002.2    .045       0
  5775.8    .035       0  5826.6    .045       0  5907.7    .035       0
  6240.2    .045       0
Bank Sta=4993.5,5002.2
XS Rating Curve= 0 ,0
Exp/Cntr=0.3,0.1

Type RM Length L Ch R = 1 ,90360   ,444,444,444
BEGIN DESCRIPTION:
GERONIMO CREEK 17.0
END DESCRIPTION:
XS GIS Cut Line= 3
        2281825.     13798424.97        2281825.       13796625.
      2280925.02     13795625.02
#Sta/Elev= 30
  3199.6  619.57  3479.6  619.48  3959.6  618.04  4459.6  615.16  4629.6  613.37
  4669.6  614.09  4709.6  612.82  4899.6  611.26  4975.2  607.94  4975.7  607.44
  4983.4  607.44  4983.9  607.94  5027.6  610.84  5063.5  611.17  5141.2  610.72
  5204.7  611.75  5275.7  611.53    5483  614.01  5608.3  616.22  5615.8  614.81
  5622.5  614.79    5630  617.28    5651  618.06  5665.2  617.89  5679.4  616.91
  5714.5  618.06  5890.3  619.53  5955.2  620.61  5997.8  620.22  6344.9  623.15
#Mann= 5 ,-1 , 0
  3199.6    .045       0  4975.2    .045       0  4983.9    .045       0
    5483    .035       0  5890.3    .045       0
Bank Sta=4975.2,4983.9
XS Rating Curve= 0 ,0
Exp/Cntr=0.3,0.1

Type RM Length L Ch R = 1 ,89916   ,441,441,441
BEGIN DESCRIPTION:
GERONIMO CREEK 16.0
END DESCRIPTION:
XS GIS Cut Line= 3
        2281975.     13798174.98        2282175.       13796375.
      2281175.01     13795475.01
#Sta/Elev= 30
  3189.3  619.37  3702.4   618.6  4165.2  616.85  4758.9  611.83  4809.2  612.67
  4849.4  611.14  4960.1  610.06  5009.8  607.64  5010.3  607.14  5018.6  607.64
  5056.8   610.4  5156.2  611.04  5276.5  609.77  5290.7   610.1  5297.5  611.51
  5304.9  611.47  5311.7  612.64  5333.3  612.99  5354.3   612.1  5375.9  612.55
  5396.9  611.54  5453.7  611.95  5482.1   612.6  5552.3  615.84  5665.9  618.36
  5955.9     621  5998.5  620.68  6062.8  621.57  6310.2  622.37  6345.7  622.86
#Mann= 5 ,-1 , 0
  3189.3    .045       0  5009.8    .045       0  5018.6    .045       0
  5156.2    .035       0  6310.2    .045       0
Bank Sta=5009.8,5018.6
XS Rating Curve= 0 ,0
Exp/Cntr=0.3,0.1

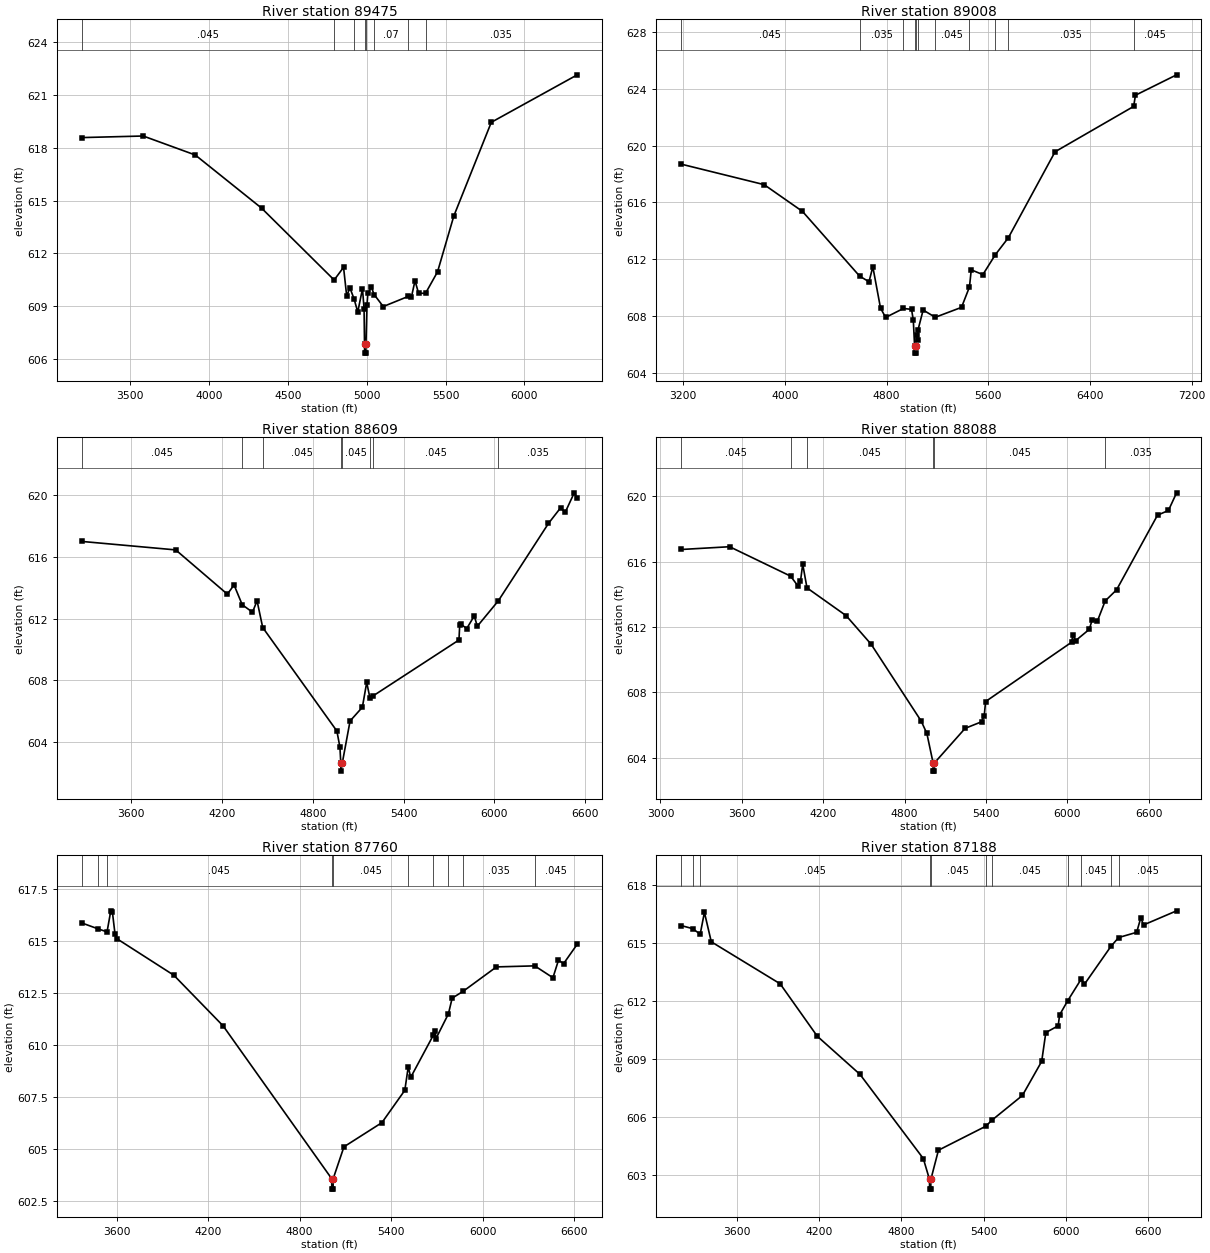
Type RM Length L Ch R = 1 ,89475   ,467,467,467
BEGIN DESCRIPTION:
GERONIMO CREEK 15.0
END DESCRIPTION:
XS GIS Cut Line= 3
        2282475.     13797874.98        2282475.       13796075.
      2281275.02     13795475.01
#Sta/Elev= 30
  3193.6  618.59  3583.6  618.68  3913.6   617.6  4333.6  614.58    4794  610.49
  4853.6  611.21  4873.6  609.57  4893.6  610.05  4920.4  609.41  4943.6  608.67
  4973.6  609.99  4983.6  608.86  4986.5  606.83    4987  606.33  4995.1  606.33
  4995.6  606.83    5002  609.04  5007.6  609.73  5029.9  610.08  5047.5  609.66
  5105.4  608.98  5264.6  609.56  5284.3  609.54  5306.6  610.45    5329  609.74
  5373.1  609.73  5449.2  610.95  5552.6  614.13  5790.2  619.46  6335.2  622.16
#Mann= 8 ,-1 , 0
  3193.6    .045       0    4794    .035       0  4920.4    .045       0
  4986.5    .045       0  4995.6    .045       0  5047.5     .07       0
  5264.6    .045       0  5373.1    .035       0
Bank Sta=4986.5,4995.6
XS Rating Curve= 0 ,0
Exp/Cntr=0.3,0.1

Type RM Length L Ch R = 1 ,89008   ,399,399,399
BEGIN DESCRIPTION:
GERONIMO CREEK 14.0
END DESCRIPTION:
XS GIS Cut Line= 3
        2282675.     13797674.99        2282875.       13795875.
      2280875.03     13795275.01
#Sta/Elev= 30
    3182  618.71    3836  617.26  4137.8  615.37  4587.7   610.8    4661  610.41
  4691.2  611.46  4751.6  608.55  4791.8  607.89  4931.6  608.52  4995.7  608.46
  5009.6   607.7  5019.8  605.87  5020.3  605.37  5028.5  605.37    5029  605.87
  5034.8  606.64  5042.7  606.28  5046.1  606.99    5087  608.41  5182.4   607.9
  5388.9   608.6  5451.5  610.04  5465.5  611.25  5556.8  610.91  5655.4  612.32
  5757.3  613.51    6125  619.58  6743.1  622.78  6757.5  623.57  7081.1  625.01
#Mann= 11 ,-1 , 0
    3182    .045       0  4587.7    .035       0  4931.6    .045       0
  5019.8    .045       0    5029    .045       0  5046.1    .035       0
  5182.4    .045       0  5451.5     .07       0  5655.4    .045       0
  5757.3    .035       0  6743.1    .045       0
Bank Sta=5019.8,5029
XS Rating Curve= 0 ,0
Exp/Cntr=0.3,0.1

Type RM Length L Ch R = 1 ,88609   ,521,521,521
BEGIN DESCRIPTION:
A18962
END DESCRIPTION:
XS GIS Cut Line= 3
      2283444.71     13797327.79      2283147.77     13795502.81
      2281724.96     13795496.62
#Sta/Elev= 30
  3274.7  617.01  3895.5  616.46  4236.5  613.59  4280.5  614.19  4334.3  612.91
  4402.1  612.42  4432.5  613.16  4469.7  611.43  4959.4  604.72  4979.6  603.67
  4985.3  602.62  4985.8  602.12  4994.7  602.62  5046.5  605.37  5127.6  606.26
  5156.4  607.87  5177.3  606.88  5195.8  606.98  5765.4  610.62  5770.4   611.6
  5776.5  611.66  5816.5  611.36  5866.5  612.18  5886.5  611.51  6025.3  613.16
  6356.5  618.18  6436.5  619.19  6466.5  618.89  6526.5  620.16  6546.5  619.82
#Mann= 8 ,-1 , 0
  3274.7    .045       0  4334.3    .035       0  4469.7    .045       0
  4985.3    .045       0  4994.7    .045       0  5177.3    .035       0
  5195.8    .045       0  6025.3    .035       0
Bank Sta=4985.3,4994.7
XS Rating Curve= 0 ,0
Exp/Cntr=0.3,0.1

Type RM Length L Ch R = 1 ,88088   ,328,328,328
BEGIN DESCRIPTION:
GERONIMO CREEK 13.0
END DESCRIPTION:
XS GIS Cut Line= 3
      2283924.99     13797074.96        2283525.       13795275.
      2281725.04       13795475.
#Sta/Elev= 30
  3151.3  616.74  3509.8  616.91  3959.2  615.11  4011.7  614.53  4032.2  614.79
  4048.9  615.84  4080.4  614.39    4369  612.69  4553.4  610.94  4922.2  606.24
  4964.4  605.48  5010.5  603.67    5011  603.17  5019.6  603.17  5020.1  603.67
  5246.7  605.79  5367.4  606.19  5387.6  606.57  5397.6  607.43  6031.5  611.06
  6041.6  611.52  6061.7  611.16  6162.3  611.85  6182.4   612.4  6222.7  612.37
  6279.5  613.59  6363.5  614.27  6665.4  618.84  6745.9  619.13  6806.2  620.21
#Mann= 6 ,-1 , 0
  3151.3    .045       0  3959.2    .035       0  4080.4    .045       0
  5010.5    .045       0  5020.1    .045       0  6279.5    .035       0
Bank Sta=5010.5,5020.1
XS Rating Curve= 0 ,0
Exp/Cntr=0.3,0.1

Type RM Length L Ch R = 1 ,87760   ,572,572,572
BEGIN DESCRIPTION:
A18961
END DESCRIPTION:
XS GIS Cut Line= 4
      2284094.27     13796393.63      2283896.31     13795131.63
      2283209.63     13794766.64      2282015.72     13794692.41
#Sta/Elev= 30
  3370.2  615.86  3475.7  615.58  3536.5  615.43  3561.1  616.44  3571.3   616.4
  3588.9  615.32  3601.6   615.1  3974.8  613.35  4298.1  610.92  5010.4  603.59
  5010.9  603.09  5019.6  603.09  5020.1  603.59  5090.8  605.12  5339.9  606.28
    5490  607.83  5512.7  608.96  5528.7  608.45  5677.6  610.48  5689.4  610.68
  5694.4  610.31  5776.2   611.5  5800.6  612.25  5874.7  612.59  6091.2  613.75
  6342.5   613.8  6461.9  613.23  6498.1  614.07    6532  613.91  6621.5  614.84
#Mann= 10 ,-1 , 0
  3370.2    .045       0  3475.7    .035       0  3536.5    .045       0
  5010.4    .045       0  5020.1    .045       0  5512.7    .035       0
  5677.6    .045       0  5776.2     .07       0  5874.7    .035       0
  6342.5    .045       0
Bank Sta=5010.4,5020.1
XS Rating Curve= 0 ,0
Exp/Cntr=0.3,0.1

Type RM Length L Ch R = 1 ,87188   ,451,451,451
BEGIN DESCRIPTION:
GERONIMO CREEK 12.0
END DESCRIPTION:
XS GIS Cut Line= 3
      2284174.99     13796374.95        2283975.       13794575.
      2282175.01       13794375.
#Sta/Elev= 30
    3189  615.88  3274.3  615.72  3329.1  615.43    3360  616.56  3410.3  615.04
  3913.4  612.87    4185  610.16    4497  608.19  4959.8  603.84  5005.2  602.76
  5005.7  602.26  5014.5  602.26    5015  602.76  5070.5  604.27  5416.6  605.51
  5459.4  605.81  5684.2   607.1  5825.1  608.86  5855.3  610.35  5945.8   610.7
  5955.9  611.26  6014.9  611.99  6113.7  613.11    6137  612.84  6331.8  614.81
  6387.8  615.26  6519.3  615.53  6549.5  616.28  6569.6  615.91  6811.1  616.64
#Mann= 11 ,-1 , 0
    3189    .045       0  3274.3    .035       0  3329.1    .045       0
  5005.2    .045       0    5015    .045       0  5416.6    .035       0
  5459.4    .045       0  6014.9    .035       0  6113.7    .045       0
  6331.8    .035       0  6387.8    .045       0
Bank Sta=5005.2,5015
XS Rating Curve= 0 ,0
Exp/Cntr=0.3,0.1