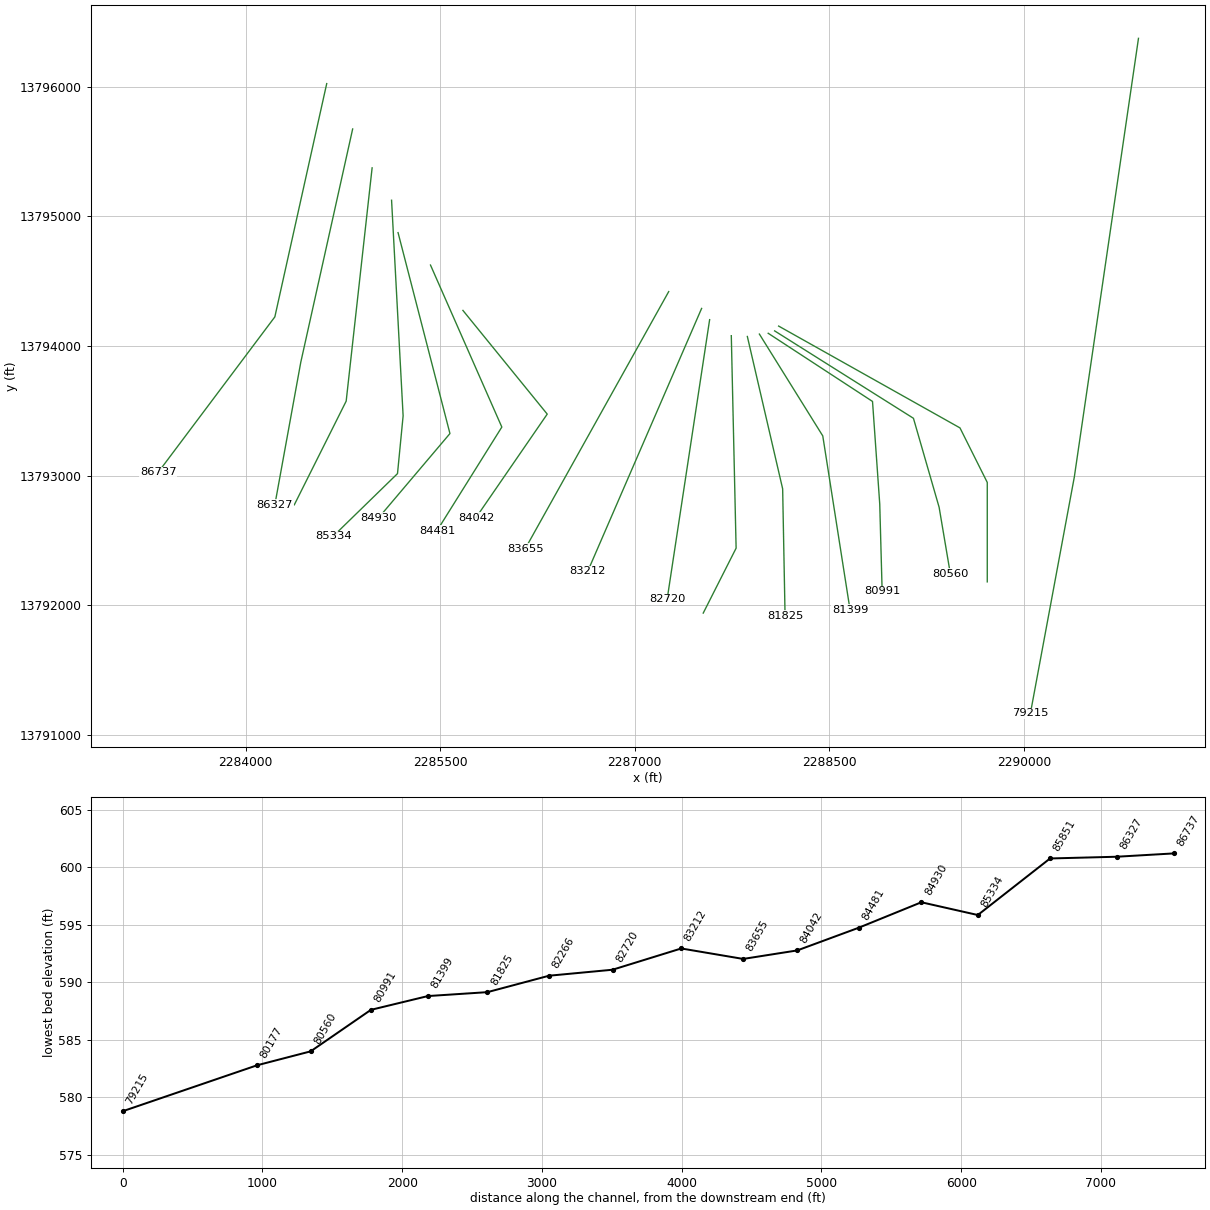
HEC-RAS study GERONIMO CREEK.prj: GERONIMO CREEK Base Level Engineering

--- GERONIMO CREEK.g01 (geometry) --- (continued)

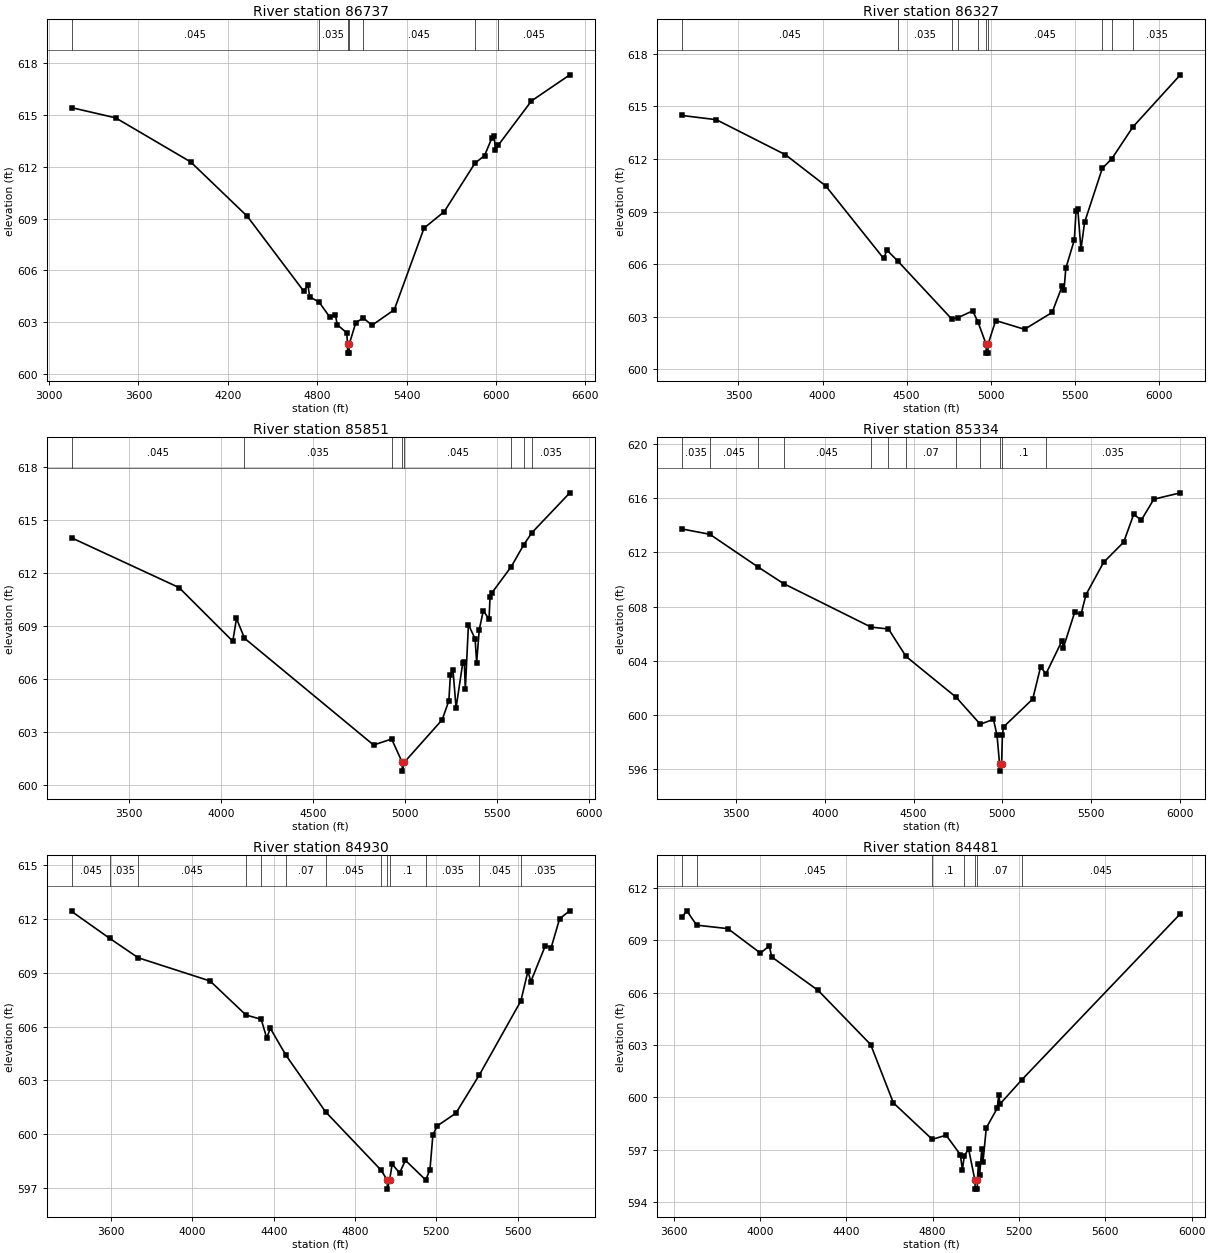
Type RM Length L Ch R = 1 ,86737   ,410,410,410
BEGIN DESCRIPTION:
GERONIMO CREEK 11.0
END DESCRIPTION:
XS GIS Cut Line= 3
      2284624.99     13796024.95        2284225.       13794225.
      2283324.98     13793024.97
#Sta/Elev= 30
  3150.9  615.42  3446.6  614.83  3949.9  612.28  4330.2  609.13  4707.9  604.81
  4737.4  605.14  4748.9  604.47  4812.6  604.16  4883.4   603.3  4921.8  603.43
  4933.3  602.86  4997.9  602.38  5002.8  601.71  5003.3  601.21  5013.3  601.21
  5013.8  601.71  5058.3  602.97  5108.7  603.25  5166.6  602.82  5316.6  603.72
  5516.6  608.45  5652.1   609.4  5857.6   612.2  5922.9  612.65  5972.9  613.69
  5987.5  613.78  5994.8  612.98  6013.9  613.24  6237.5  615.81  6494.8  617.32
#Mann= 7 ,-1 , 0
  3150.9    .045       0  4812.6    .035       0  5002.8    .035       0
  5013.8    .035       0  5108.7    .045       0  5857.6    .035       0
  6013.9    .045       0
Bank Sta=5002.8,5013.8
XS Rating Curve= 0 ,0
Exp/Cntr=0.3,0.1

Type RM Length L Ch R = 1 ,86327   ,476,476,476
BEGIN DESCRIPTION:
GERONIMO CREEK 10.0
END DESCRIPTION:
XS GIS Cut Line= 3
      2284824.99     13795674.97        2284425.       13793875.
        2284225.     13792775.02
#Sta/Elev= 30
    3165  614.48  3368.6  614.24  3779.6  612.24  4019.1  610.46  4363.5  606.32
  4382.7   606.8  4449.6  606.15  4766.7  602.88  4804.1  602.94  4892.4  603.33
  4924.7  602.68  4972.7  601.42  4973.2  600.92  4983.2  600.92  4983.7  601.42
  5029.2  602.78  5200.7  602.28  5364.6  603.24  5424.3  604.74  5435.8  604.54
  5445.9  605.75  5496.8  607.38  5506.9  609.02  5517.1  609.17  5536.1  606.84
  5557.7  608.38  5662.9  611.46  5720.2  612.02  5845.3  613.83  6126.9   616.8
#Mann= 10 ,-1 , 0
    3165    .045       0  4449.6    .035       0  4766.7    .045       0
  4804.1    .035       0  4924.7    .045       0  4972.7    .045       0
  4983.7    .045       0  5662.9    .035       0  5720.2    .045       0
  5845.3    .035       0
Bank Sta=4972.7,4983.7
XS Rating Curve= 0 ,0
Exp/Cntr=0.3,0.1

Type RM Length L Ch R = 1 ,85851   ,517,517,517
BEGIN DESCRIPTION:
GERONIMO CREEK 9.0
END DESCRIPTION:
XS GIS Cut Line= 3
        2284975.     13795375.01        2284775.       13793575.
      2284375.01     13792775.02
#Sta/Elev= 30
  3189.2  613.99  3772.8  611.17  4064.6  608.13  4084.7  609.42  4128.1   608.3
  4829.2  602.25  4927.1  602.59  4984.6  601.27  4985.1  600.77  4995.8  601.27
  5201.5  603.68  5237.9  604.76  5246.3  606.24  5260.2  606.52    5277  604.35
  5313.3   606.9  5321.7  606.98  5327.3   605.4  5344.1  609.07  5380.4  608.27
  5388.8  606.92  5402.8  608.78  5425.1  609.87  5455.9  609.37  5461.5  610.61
  5469.9  610.85  5576.9  612.36  5644.1  613.59  5688.6  614.28  5894.7  616.54
#Mann= 8 ,-1 , 0
  3189.2    .045       0  4128.1    .035       0  4927.1    .045       0
  4984.6    .045       0  4995.8    .045       0  5576.9    .035       0
  5644.1     .07       0  5688.6    .035       0
Bank Sta=4984.6,4995.8
XS Rating Curve= 0 ,0
Exp/Cntr=0.3,0.1

Type RM Length L Ch R = 1 ,85334   ,404,404,404
BEGIN DESCRIPTION:
GERONIMO CREEK 8.0
END DESCRIPTION:
XS GIS Cut Line= 4
        2285125.     13795125.05      2285213.99     13793461.33
      2285170.68     13793015.92      2284675.79      13792533.4
#Sta/Elev= 30
  3196.7  613.72    3353  613.33  3623.8  610.92  3768.1  609.69  4260.2  606.48
  4358.6  606.34    4457  604.32  4739.8   601.3  4875.3  599.31  4949.5  599.67
  4969.6   598.5  4984.1  596.35  4984.6  595.85  4995.4  596.35  4999.8  598.51
  5006.1  599.11  5170.6  601.17  5214.9  603.54  5245.2  603.03  5336.2  605.49
  5343.3  604.97  5406.9  607.58  5442.3  607.41  5470.6  608.88  5569.6  611.26
  5682.6  612.75  5739.2  614.81  5781.6  614.37  5852.4  615.92  6001.5  616.39
#Mann= 12 ,-1 , 0
  3196.7    .035       0    3353    .045       0  3623.8    .035       0
  3768.1    .045       0  4260.2    .035       0  4358.6    .045       0
    4457     .07       0  4739.8    .045       0  4875.3      .1       0
  4984.1     .05       0  4995.4      .1       0  5245.2    .035       0
Bank Sta=4984.1,4995.4
XS Rating Curve= 0 ,0
Exp/Cntr=0.3,0.1

Type RM Length L Ch R = 1 ,84930   ,449,449,449
BEGIN DESCRIPTION:
GERONIMO CREEK 7.0
END DESCRIPTION:
XS GIS Cut Line= 3
        2285175.     13794875.02        2285575.       13793325.
      2285024.98     13792674.98
#Sta/Elev= 30
  3405.2   612.4  3592.6   610.9  3733.2  609.82  4086.8  608.53  4263.4  606.64
  4338.4   606.4  4365.7  605.36  4383.4   605.9  4460.4   604.4  4655.1  601.26
  4928.9  598.01    4959  597.46  4959.5  596.96  4970.4  597.46  4983.1  598.35
  5019.7  597.86  5048.3  598.56  5148.2  597.47  5169.1  598.04  5183.4  599.96
  5204.3  600.47  5296.6  601.18  5412.2  603.31  5616.5  607.42  5651.4  609.08
  5665.7   608.5  5737.2   610.5  5765.8  610.39  5807.5     612  5857.5  612.43
#Mann= 13 ,-1 , 0
  3405.2    .045       0  3592.6    .035       0  3733.2    .045       0
  4263.4    .035       0  4338.4    .045       0  4460.4     .07       0
  4655.1    .045       0  4928.9      .1       0    4959     .05       0
  4970.4      .1       0  5148.2    .035       0  5412.2    .045       0
  5616.5    .035       0
Bank Sta=4959,4970.4
XS Rating Curve= 0 ,0
Exp/Cntr=0.3,0.1

Type RM Length L Ch R = 1 ,84481   ,439,439,439
BEGIN DESCRIPTION:
GERONIMO CREEK 6.0
END DESCRIPTION:
XS GIS Cut Line= 3
      2285424.99     13794625.03        2285975.       13793375.
      2285474.99     13792574.98
#Sta/Elev= 30
  3638.6  610.33  3660.5  610.68  3706.1  609.86  3850.7  609.66  4001.6  608.26
  4042.9  608.67  4053.8  608.04  4269.3  606.12  4512.6  603.02  4617.9  599.68
    4798  597.59  4862.3  597.83  4927.8  596.72  4937.7  595.86  4946.6  596.65
  4966.5  597.04  4995.8  595.24  4996.3  594.74  5006.7  594.74  5007.2  595.24
  5011.9  596.18  5017.8  595.56  5027.3  597.01  5033.2  596.31  5048.5  598.25
  5098.6  599.36  5106.3  600.13  5112.2  599.62  5213.6  601.01  5947.7  610.51
#Mann= 7 ,-1 , 0
  3638.6    .035       0  3706.1    .045       0    4798      .1       0
  4946.6     .07       0  4995.8     .05       0  5007.2     .07       0
  5213.6    .045       0
Bank Sta=4995.8,5007.2
XS Rating Curve= 0 ,0
Exp/Cntr=0.3,0.1

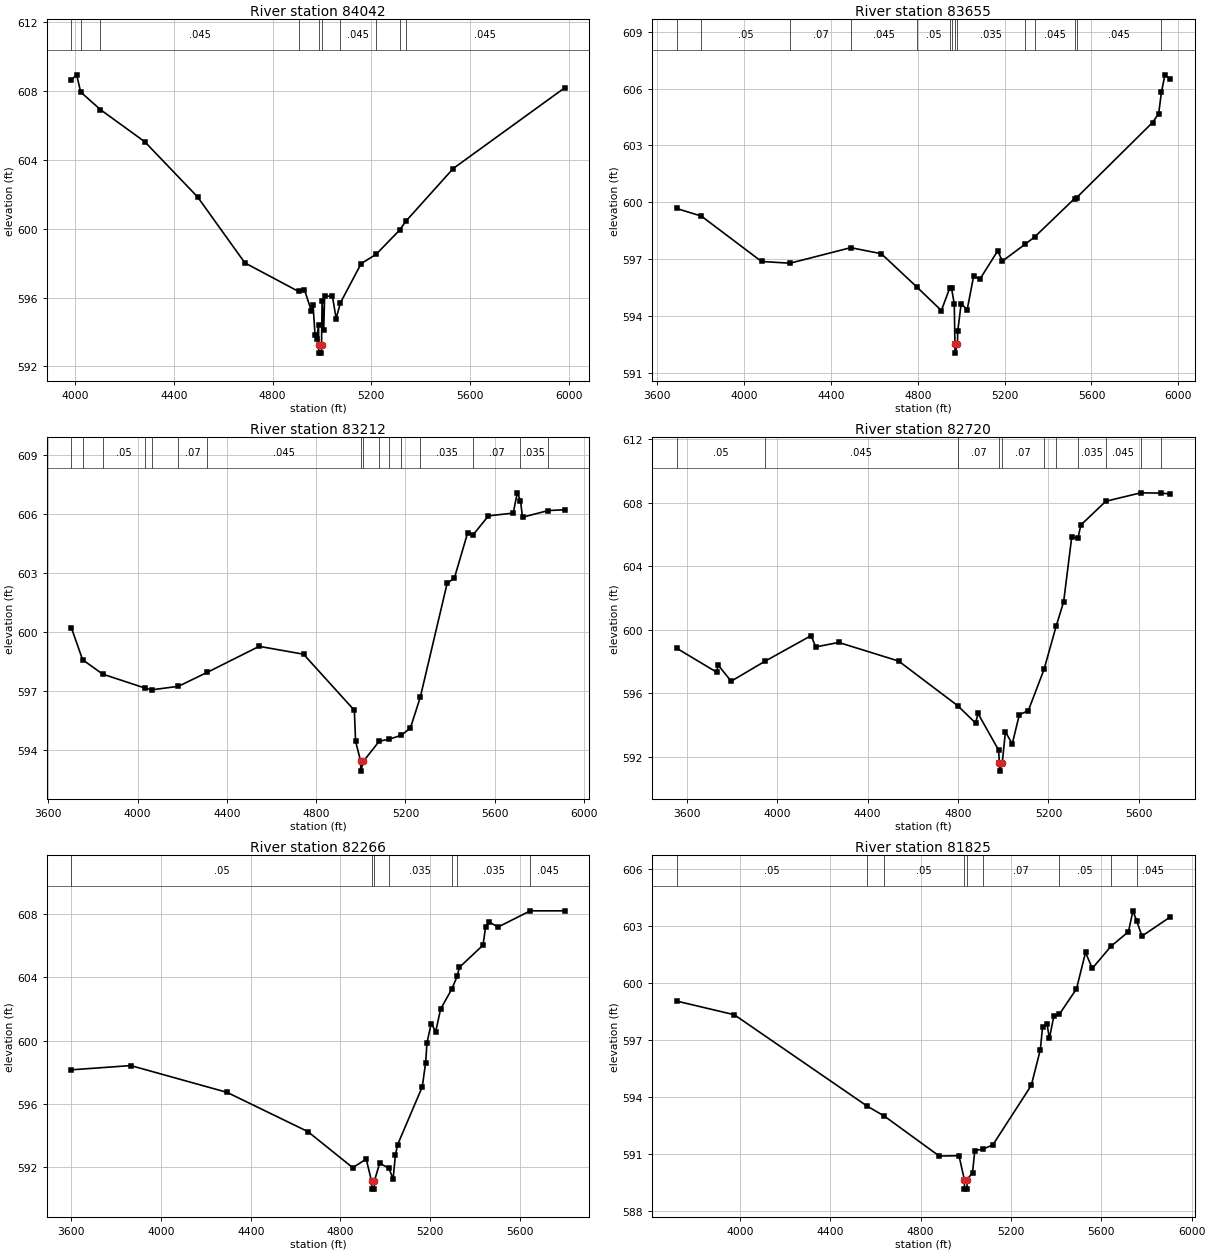
Type RM Length L Ch R = 1 ,84042   ,387,387,387
BEGIN DESCRIPTION:
GERONIMO CREEK 5.0
END DESCRIPTION:
XS GIS Cut Line= 3
      2285675.01     13794274.98        2286325.       13793475.
      2285774.99     13792674.98
#Sta/Elev= 30
  3983.3  608.64  4004.8  608.93  4021.2  607.93  4101.3  606.91  4281.4  605.04
  4495.4  601.84  4687.2  598.01  4905.1  596.35  4928.6  596.46  4957.3  595.21
  4963.8  595.57  4971.7  593.83  4978.1  593.58  4986.1   594.4  4986.7  593.27
  4987.2  592.77  4997.7  592.77  4998.2  593.27  5000.4  595.82  5006.9   594.1
  5010.8   596.1  5042.5  596.06  5057.4  594.78  5074.7  595.69  5158.9  597.97
    5219   598.5  5314.7  599.91  5340.9  600.44  5532.3  603.49  5984.9  608.18
#Mann= 10 ,-1 , 0
  3983.3    .045       0  4021.2    .035       0  4101.3    .045       0
  4905.1     .07       0  4986.7     .05       0  4998.2     .07       0
  5074.7    .045       0    5219    .035       0  5314.7     .07       0
  5340.9    .045       0
Bank Sta=4986.7,4998.2
XS Rating Curve= 0 ,0
Exp/Cntr=0.3,0.1

Type RM Length L Ch R = 1 ,83655   ,443,443,443
BEGIN DESCRIPTION:
A18960
END DESCRIPTION:
XS GIS Cut Line= 2
      2287261.63     13794420.17      2286154.32     13792434.44
#Sta/Elev= 30
  3688.3  599.67  3802.2  599.27  4079.8  596.87    4211  596.78  4490.6   597.6
  4631.8  597.28  4796.4  595.51  4908.3  594.28  4946.3  595.45  4955.2  595.45
  4967.8  594.63  4970.7  592.53  4971.2  592.03  4982.5  592.53  4983.8   593.2
  4999.5  594.64  5027.2  594.32  5056.7  596.08  5086.6  595.95  5167.8  597.43
  5189.5  596.89  5292.7  597.77  5339.3  598.18  5521.8  600.19  5531.3  600.24
  5881.1  604.21  5909.5  604.68    5922   605.8  5938.4  606.73  5961.9   606.5
#Mann= 14 ,-1 , 0
  3688.3    .035       0  3802.2     .05       0    4211     .07       0
  4490.6    .045       0  4796.4     .05       0  4946.3    .045       0
  4955.2    .035       0  4970.7    .035       0  4982.5    .035       0
  5292.7     .07       0  5339.3    .045       0  5521.8    .035       0
  5531.3    .045       0    5922     .07       0
Bank Sta=4970.7,4982.5
XS Rating Curve= 0 ,0
Exp/Cntr=0.3,0.1

Type RM Length L Ch R = 1 ,83212   ,492,492,492
BEGIN DESCRIPTION:
A18959
END DESCRIPTION:
XS GIS Cut Line= 2
       2287515.3     13794290.33      2286636.85     13792261.22
#Sta/Elev= 30
    3703  600.23  3753.4   598.6  3843.3  597.87  4033.1  597.16  4062.8  597.07
    4183  597.25  4312.2  597.96  4544.7  599.28  4743.4  598.88  4971.1  596.03
  4976.6  594.46  4999.4  593.44  4999.9  592.94  5011.7  593.44  5082.7  594.46
  5126.3  594.56  5181.3  594.76  5222.3  595.13  5266.7   596.7  5386.9  602.48
  5419.6  602.76  5478.9  605.05  5502.1  604.93  5572.2  605.91  5683.1  606.05
  5701.1  607.08  5715.6  606.68  5724.6  605.84  5840.3  606.18  5914.1  606.22
#Mann= 16 ,-1 , 0
    3703     .05       0  3753.4    .035       0  3843.3     .05       0
  4033.1     .07       0  4062.8     .05       0    4183     .07       0
  4312.2    .045       0  4999.4    .045       0  5011.7    .045       0
  5082.7     .07       0  5126.3    .035       0  5181.3     .07       0
  5266.7    .035       0  5502.1     .07       0  5715.6    .035       0
  5840.3    .045       0
Bank Sta=4999.4,5011.7
XS Rating Curve= 0 ,0
Exp/Cntr=0.3,0.1

Type RM Length L Ch R = 1 ,82720   ,454,454,454
BEGIN DESCRIPTION:
A18958
END DESCRIPTION:
XS GIS Cut Line= 2
      2287577.15     13794203.73      2287249.28     13792044.68
#Sta/Elev= 30
  3554.4  598.83  3732.7  597.31  3737.7  597.78  3795.9  596.75  3945.9  598.01
  4149.9  599.62  4170.1  598.91  4272.2  599.19  4536.9  598.02  4798.3  595.21
  4878.1  594.11  4888.2  594.72  4979.3  592.42  4983.2  591.59  4983.7  591.09
  4995.5  591.59  5009.6  593.56    5040  592.81  5071.4  594.65  5110.8  594.89
  5180.5  597.49  5234.3  600.22  5267.3  601.75  5302.9   605.8  5331.3  605.79
  5343.4  606.58    5454  608.08  5608.7  608.61  5700.4  608.59  5738.2  608.54
#Mann= 11 ,-1 , 0
  3554.4     .05       0  3945.9    .045       0  4798.3     .07       0
  4983.2     .05       0  4995.5     .07       0  5180.5    .035       0
  5234.3     .07       0  5331.3    .035       0    5454    .045       0
  5608.7    .035       0  5700.4    .045       0
Bank Sta=4983.2,4995.5
XS Rating Curve= 0 ,0
Exp/Cntr=0.3,0.1

Type RM Length L Ch R = 1 ,82266   ,441,441,441
BEGIN DESCRIPTION:
A18957
END DESCRIPTION:
XS GIS Cut Line= 3
      2287744.18     13794079.93       2287781.3      13792440.6
      2287527.78     13791939.76
#Sta/Elev= 30
  3599.9  598.14  3864.9  598.41  4294.4  596.71  4655.1  594.22  4855.2  591.93
  4915.2  592.48    4939  591.07  4939.5  590.57  4950.9  590.57  4951.4  591.07
  4975.2  592.22  5016.6  591.89  5035.2  591.21  5045.2  592.71  5055.2  593.39
  5165.2  597.06  5180.2  598.58  5186.3  599.86  5205.2  601.08  5225.2  600.57
    5247  601.99    5297  603.27  5321.7   604.1  5330.5  604.64  5436.3  606.05
  5447.7  607.21  5464.2  607.52  5503.2   607.2  5646.9  608.23    5801  608.23
#Mann= 7 ,-1 , 0
  3599.9     .05       0    4939     .05       0  4951.4     .05       0
  5016.6    .035       0    5297     .05       0  5321.7    .035       0
  5646.9    .045       0
Bank Sta=4939,4951.4
XS Rating Curve= 0 ,0
Exp/Cntr=0.3,0.1

Type RM Length L Ch R = 1 ,81825   ,426,426,426
BEGIN DESCRIPTION:
A18956
END DESCRIPTION:
XS GIS Cut Line= 3
       2287867.9     13794073.78       2288140.1     13792898.38
      2288158.66     13791920.96
#Sta/Elev= 30
  3720.2  599.04  3975.6  598.32  4563.6  593.51  4638.9  592.99    4883  590.88
  4970.1   590.9  4993.9  589.64  4994.4  589.14  5005.8  589.14  5006.3  589.64
  5030.1  590.01  5040.1  591.17  5077.1  591.25  5120.1  591.47  5290.1   594.6
  5330.2  596.48  5340.2   597.7  5360.2  597.81  5370.2  597.07  5390.2  598.26
  5414.7  598.35  5490.2  599.68  5530.2   601.6  5560.2  600.76  5642.6  601.92
  5720.2  602.69  5740.2  603.79  5755.9  603.28  5780.2  602.46  5904.3  603.46
#Mann= 9 ,-1 , 0
  3720.2     .05       0  4563.6    .035       0  4638.9     .05       0
  4993.9     .05       0  5006.3     .05       0  5077.1     .07       0
  5414.7     .05       0  5642.6    .035       0  5755.9    .045       0
Bank Sta=4993.9,5006.3
XS Rating Curve= 0 ,0
Exp/Cntr=0.3,0.1

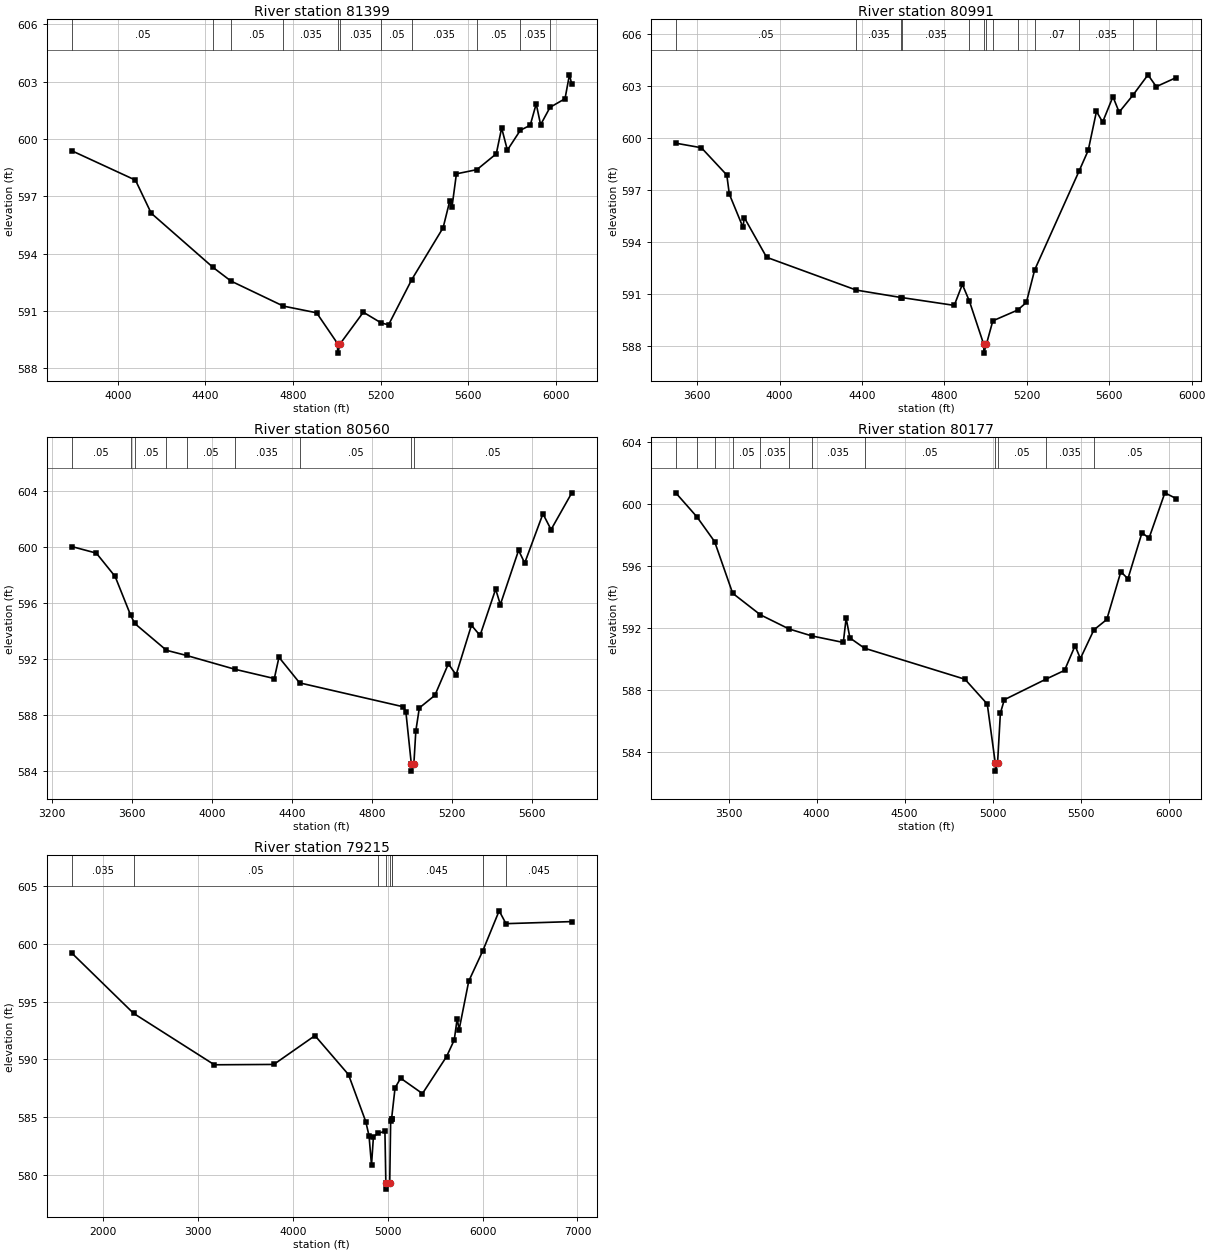
Type RM Length L Ch R = 1 ,81399   ,408,408,408
BEGIN DESCRIPTION:
A18955
END DESCRIPTION:
XS GIS Cut Line= 3
      2287960.67     13794092.38      2288449.41     13793306.68
      2288659.75     13791964.26
#Sta/Elev= 30
  3789.1  599.39  4080.4  597.85  4152.3  596.12  4435.2  593.28  4516.7  592.57
  4755.9  591.26  4907.7  590.91  5003.3   589.3  5003.8   588.8  5015.9   589.3
    5121  590.94  5202.6  590.38  5236.2  590.28  5342.3  592.65  5485.4  595.36
  5515.7  596.76  5525.9  596.44  5546.1  598.18  5639.8   598.4  5728.3  599.23
  5752.7  600.58  5778.9  599.42  5838.1  600.46  5883.1  600.72  5910.5  601.84
  5930.7  600.75  5973.7  601.66  6042.1  602.11  6062.3  603.36  6073.2  602.86
#Mann= 11 ,-1 , 0
  3789.1     .05       0  4435.2    .035       0  4516.7     .05       0
  4755.9    .035       0  5003.3    .035       0  5015.9    .035       0
  5202.6     .05       0  5342.3    .035       0  5639.8     .05       0
  5838.1    .035       0  5973.7    .045       0
Bank Sta=5003.3,5015.9
XS Rating Curve= 0 ,0
Exp/Cntr=0.3,0.1

Type RM Length L Ch R = 1 ,80991   ,431,431,431
BEGIN DESCRIPTION:
A18954
END DESCRIPTION:
XS GIS Cut Line= 4
      2288028.75     13794098.52      2288832.96     13793572.69
      2288888.64     13792780.84      2288907.15     13792108.26
#Sta/Elev= 30
  3497.4  599.69  3620.5  599.43  3743.8  597.86  3756.1  596.76  3822.6  594.84
  3828.5  595.41  3937.1  593.12  4372.6  591.23  4591.6   590.8  4593.5   590.8
  4847.8  590.35    4887  591.56  4921.4  590.59    4991   588.1  4991.5   587.6
  5003.6   588.1    5035  589.46  5155.5  590.08  5197.8  590.52    5238  592.39
  5453.4  598.08    5498  599.28    5538  601.52    5568  600.91    5618  602.37
  5648.1  601.48  5713.9  602.44  5788.1  603.63  5828.3  602.95  5924.9  603.47
#Mann= 13 ,-1 , 0
  3497.4     .05       0  4372.6    .035       0  4591.6     .05       0
  4593.5    .035       0  4921.4     .05       0    4991     .05       0
  5003.6     .05       0    5035    .035       0  5155.5     .05       0
    5238     .07       0  5453.4    .035       0  5713.9     .05       0
  5828.3    .035       0
Bank Sta=4991,5003.6
XS Rating Curve= 0 ,0
Exp/Cntr=0.3,0.1

Type RM Length L Ch R = 1 ,80560   ,383,383,383
BEGIN DESCRIPTION:
A18953
END DESCRIPTION:
XS GIS Cut Line= 4
      2288078.23     13794117.08      2289148.46     13793442.77
      2289346.43      13792756.1      2289433.03     13792242.64
#Sta/Elev= 30
    3300  600.05  3423.1  599.58  3517.2  597.91  3594.4  595.15    3615  594.55
  3773.9  592.63  3874.4  592.26    4117  591.27    4313  590.61  4336.3  592.13
  4439.6   590.3  4958.1  588.59  4970.7  588.23    4998  584.49  4998.5  583.99
  5010.6  584.49  5020.5  586.87    5038  588.51  5115.7  589.41    5183  591.66
  5221.9  590.88  5298.5  594.42  5341.5  593.69  5419.5     597    5443   595.9
  5534.2  599.78  5564.7  598.87  5655.9  602.39  5696.5  601.26  5800.3  603.89
#Mann= 9 ,-1 , 0
    3300     .05       0  3594.4    .035       0    3615     .05       0
  3773.9    .035       0  3874.4     .05       0    4117    .035       0
  4439.6     .05       0    4998     .05       0  5010.6     .05       0
Bank Sta=4998,5010.6
XS Rating Curve= 0 ,0
Exp/Cntr=0.3,0.1

Type RM Length L Ch R = 1 ,80177   ,962,962,962
BEGIN DESCRIPTION:
A18952
END DESCRIPTION:
XS GIS Cut Line= 4
      2288109.13     13794154.22      2289507.27     13793368.54
       2289717.6     13792947.87       2289717.6     13792180.76
#Sta/Elev= 30
  3201.8  600.69  3320.6  599.16  3420.9  597.57  3523.5  594.24  3681.2  592.85
  3843.6  591.94  3973.5  591.49  4152.1  591.07  4168.1  592.63  4189.7  591.36
  4272.5   590.7  4843.1   588.7  4969.9   587.1  5015.6  583.28  5016.1  582.78
  5028.3  583.28  5044.3  586.51  5066.7  587.38  5305.9  588.72  5408.8  589.27
  5468.8  590.86  5498.8  590.03  5575.5  591.88  5648.8  592.55  5728.8  595.63
  5768.8  595.17  5848.8  598.14  5888.8  597.79  5978.8  600.71    6043  600.34
#Mann= 12 ,-1 , 0
  3201.8    .035       0  3320.6     .05       0  3420.9    .035       0
  3523.5     .05       0  3681.2    .035       0  3843.6     .05       0
  3973.5    .035       0  4272.5     .05       0  5015.6     .05       0
  5028.3     .05       0  5305.9    .035       0  5575.5     .05       0
Bank Sta=5015.6,5028.3
XS Rating Curve= 0 ,0
Exp/Cntr=0.3,0.1

Type RM Length L Ch R = 1 ,79215   ,1143,1143,1143
BEGIN DESCRIPTION:
ALLIGATOR CREEK 94.0
END DESCRIPTION:
XS GIS Cut Line= 3
      2290883.44     13796374.25      2290388.65     13792988.85
      2290050.11     13791165.98
#Sta/Elev= 30
  1665.5   599.2  2317.9  593.98  3170.6  589.53  3797.2  589.56  4231.7  592.05
  4585.4  588.68  4767.4  584.62  4801.8   583.4    4828  580.86  4848.2   583.3
  4894.5   583.6  4969.5  583.78  4979.4  579.28  4980.4  578.78  5020.1  579.28
  5030.1  584.71  5038.9   584.8    5039   584.8  5076.5  587.54  5135.4  588.37
  5365.4  587.04  5619.7  590.24    5701  591.68  5731.6  593.53  5751.9  592.56
  5853.6  596.76  6002.8   599.4  6174.4  602.84  6246.4  601.73  6940.9  601.91
#Mann= 9 ,-1 , 0
  1665.5    .035       0  2317.9     .05       0  4894.5    .035       0
  4979.4    .035       0  5020.1    .035       0  5038.9     .07       0
    5039    .045       0  6002.8    .035       0  6246.4    .045       0
Bank Sta=4979.4,5020.1
XS Rating Curve= 0 ,0
Exp/Cntr=0.3,0.1