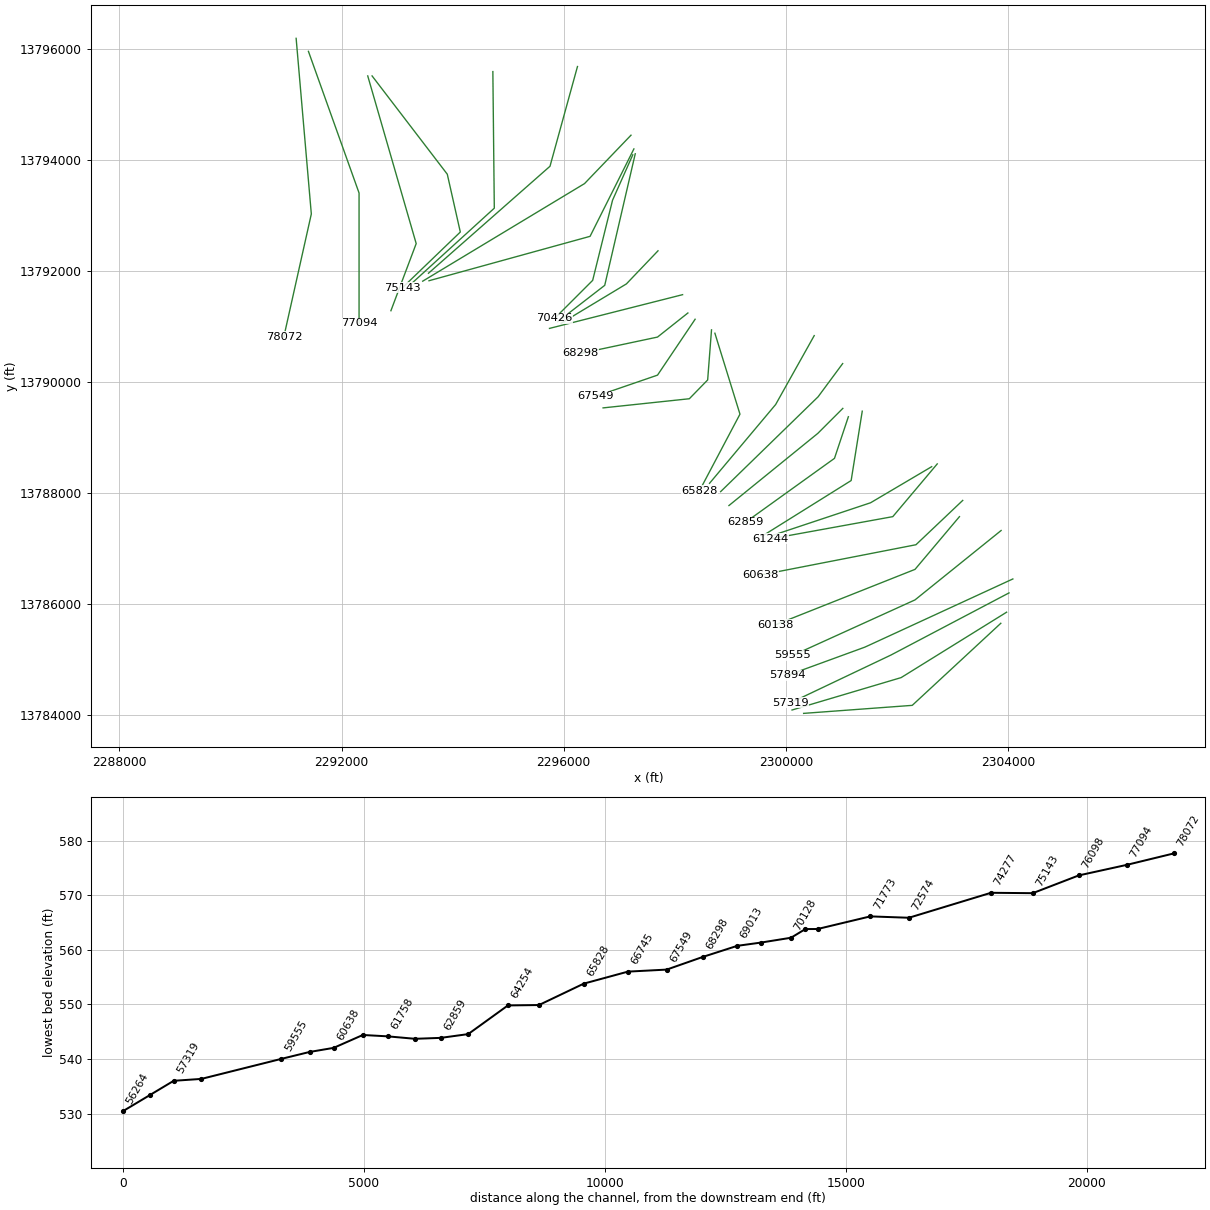
HEC-RAS study GERONIMO CREEK.prj: GERONIMO CREEK Base Level Engineering

--- GERONIMO CREEK.g01 (geometry) --- (continued)

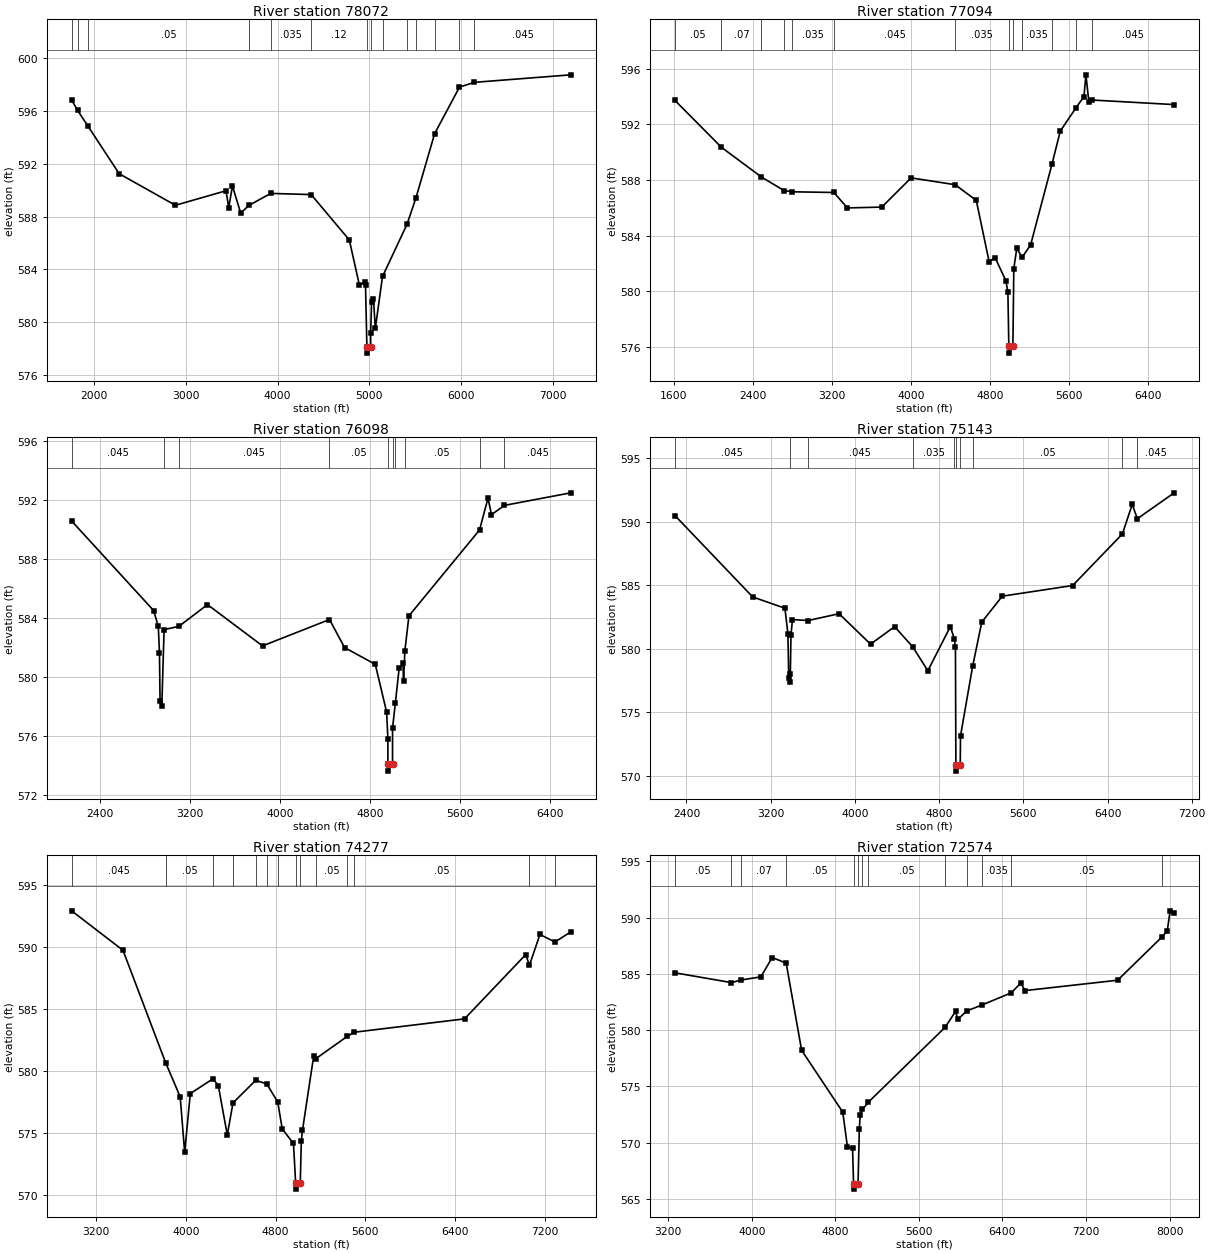
Type RM Length L Ch R = 1 ,78072   ,978,978,978
BEGIN DESCRIPTION:
ALLIGATOR CREEK 93.0
END DESCRIPTION:
XS GIS Cut Line= 3
      2291182.91     13796192.02      2291456.36     13793027.92
      2290961.56     13790814.34
#Sta/Elev= 30
  1753.7  596.85  1818.8  596.05  1933.8  594.84  2272.6  591.25  2885.6  588.86
    3437  589.96  3467.1  588.68  3507.2  590.33  3597.6  588.26  3686.6  588.85
  3924.7  589.76  4366.2  589.67    4782  586.23  4892.4  582.79  4953.1  583.04
  4958.5  582.79  4973.7  578.15  4974.7  577.65  5014.5  578.15  5014.6  579.16
  5024.8  581.51  5045.3  581.74  5065.8  579.53  5143.9  583.46  5412.1  587.43
  5509.5  589.44  5712.5  594.29  5983.5  597.82  6145.4  598.18  7197.8  598.75
#Mann= 14 ,-1 , 0
  1753.7    .035       0  1818.8     .07       0  1933.8     .05       0
  3686.6    .045       0  3924.7    .035       0  4366.2     .12       0
  4973.7     .05       0  5014.5     .12       0  5143.9     .05       0
  5412.1    .045       0  5509.5     .05       0  5712.5    .045       0
  5983.5    .035       0  6145.4    .045       0
Bank Sta=4973.7,5014.5
XS Rating Curve= 0 ,0
Exp/Cntr=0.3,0.1

Type RM Length L Ch R = 1 ,77094   ,996,996,996
BEGIN DESCRIPTION:
ALLIGATOR CREEK 92.0
END DESCRIPTION:
XS GIS Cut Line= 3
      2291404.27     13795957.62      2292315.73     13793405.52
      2292315.73      13791061.8
#Sta/Elev= 30
  1609.5  593.72    2080  590.35  2483.6  588.22  2713.3  587.24  2798.6  587.15
  3218.4   587.1    3355  585.99  3703.3  586.05  4000.6  588.15  4446.2  587.66
    4660  586.53    4790  582.13    4850  582.42    4960  580.75    4980  579.95
  4989.5  576.05  4990.5  575.55  5030.6  576.05    5040  581.63    5070  583.08
  5124.1  582.44    5210  583.33  5427.9  589.18    5510  591.51  5670.2   593.2
    5750  593.99    5770  595.56    5800   593.6  5826.6  593.75  6663.2  593.42
#Mann= 13 ,-1 , 0
  1609.5     .05       0    2080     .07       0  2483.6    .035       0
  2713.3     .05       0  2798.6    .035       0  3218.4    .045       0
  4446.2    .035       0  4989.5    .035       0  5030.6    .035       0
  5124.1    .035       0  5427.9     .05       0  5670.2    .035       0
  5826.6    .045       0
Bank Sta=4989.5,5030.6
XS Rating Curve= 0 ,0
Exp/Cntr=0.3,0.1

Type RM Length L Ch R = 1 ,76098   ,955,955,955
BEGIN DESCRIPTION:
ALLIGATOR CREEK 91.0
END DESCRIPTION:
XS GIS Cut Line= 3
      2292471.97     13795514.94      2293344.38     13792494.06
      2292889.31     13791284.89
#Sta/Elev= 30
  2149.1  590.58  2877.6  584.51  2919.3  583.43  2929.7  581.65  2934.9  578.38
  2950.5  578.02  2970.7  583.22  3101.1  583.43  3356.4  584.91  3845.7  582.11
  4440.7   583.9  4574.3     582  4847.6  580.86  4948.5  577.62  4959.4  575.83
  4959.6  574.12  4960.6  573.62  5000.7  574.12    5001  576.54  5025.9  578.24
  5059.8  580.61  5093.5  580.92  5098.7  579.76  5110.2  581.76  5146.7  584.15
  5773.9  589.97  5849.3  592.13  5880.1  591.01  5995.8  591.64  6585.4  592.49
#Mann= 10 ,-1 , 0
  2149.1    .045       0  2970.7    .035       0  3101.1    .045       0
  4440.7     .05       0  4959.6     .05       0  5000.7     .05       0
  5025.9     .07       0  5110.2     .05       0  5773.9    .035       0
  5995.8    .045       0
Bank Sta=4959.6,5000.7
XS Rating Curve= 0 ,0
Exp/Cntr=0.3,0.1

Type RM Length L Ch R = 1 ,75143   ,866,866,866
BEGIN DESCRIPTION:
ALLIGATOR CREEK 90.0
END DESCRIPTION:
XS GIS Cut Line= 4
      2292550.09     13795514.92      2293904.27     13793744.06
      2294138.65     13792702.39      2293097.11     13791699.92
#Sta/Elev= 30
  2290.6   590.5  3029.1  584.09  3335.4   583.2  3363.7   581.2  3371.9  577.73
  3381.8  578.02  3385.7  577.38  3392.7  581.07  3407.2  582.31  3555.1  582.23
  3849.8  582.77    4149  580.37  4377.6  581.75  4549.2  580.16  4693.2  578.28
  4906.9  581.75    4944  580.81  4955.3  580.12  4959.6  570.87  4960.6  570.37
  5000.8  570.87  5003.7  573.15  5118.4  578.62  5205.7  582.11  5400.4  584.15
  6069.2  584.99  6541.4  589.05  6634.9  591.38  6683.3  590.25  7033.2  592.29
#Mann= 10 ,-1 , 0
  2290.6    .045       0  3381.8    .035       0  3555.1    .045       0
  4549.2    .035       0    4944     .12       0  4959.6     .05       0
  5000.8     .12       0  5118.4     .05       0  6541.4    .035       0
  6683.3    .045       0
Bank Sta=4959.6,5000.8
XS Rating Curve= 0 ,0
Exp/Cntr=0.3,0.1

Type RM Length L Ch R = 1 ,74277   ,1703,1703,1703
BEGIN DESCRIPTION:
ALLIGATOR CREEK 89.0
END DESCRIPTION:
XS GIS Cut Line= 3
      2294724.58     13795593.06      2294750.63     13793132.08
      2293279.63     13791791.26
#Sta/Elev= 30
  2981.7  592.93  3439.8  589.74  3819.7  580.66  3949.8   577.9  3989.8   573.4
  4039.8  578.16  4242.6  579.36  4289.8  578.79  4369.8  574.82  4420.7  577.41
  4622.8  579.23  4721.2  578.95  4819.6  577.48  4859.9   575.3  4959.9  574.13
  4979.3  570.94  4980.3  570.44  5020.5  570.94  5029.9  574.34  5039.9  575.18
  5139.9  581.18  5160.7  580.99  5440.4  582.79  5502.8  583.12  6485.3   584.2
  7030.5  589.39  7064.3  588.54  7157.6  591.02  7291.5  590.41  7433.2  591.23
#Mann= 14 ,-1 , 0
  2981.7    .045       0  3819.7     .05       0  4242.6     .07       0
  4420.7     .05       0  4622.8    .035       0  4721.2     .07       0
  4819.6      .1       0  4979.3     .05       0  5020.5      .1       0
  5160.7     .05       0  5440.4    .035       0  5502.8     .05       0
  7064.3    .035       0  7291.5    .045       0
Bank Sta=4979.3,5020.5
XS Rating Curve= 0 ,0
Exp/Cntr=0.3,0.1

Type RM Length L Ch R = 1 ,72574   ,801,801,801
BEGIN DESCRIPTION:
ALLIGATOR CREEK 88.0
END DESCRIPTION:
XS GIS Cut Line= 3
      2296248.03     13795684.19      2295753.23     13793887.29
      2293565.77     13791960.24
#Sta/Elev= 30
    3265   585.1    3806  584.23  3897.7  584.46  4087.5  584.74  4195.9  586.46
  4329.9  585.96  4477.7  578.21  4871.8  572.71  4916.7  569.59  4965.2  569.54
  4974.8  566.37  4975.8  565.87  5017.8  566.37  5030.3  571.22  5037.8  572.43
  5059.9  572.95  5116.6   573.6  5851.8  580.26  5951.4  581.67  5972.3  580.96
    6059  581.71  6201.4  582.23  6484.6  583.32  6574.7  584.18  6617.4  583.52
  7502.5  584.44  7925.6  588.27  7977.8  588.83  8005.3  590.61    8044  590.43
#Mann= 13 ,-1 , 0
    3265     .05       0    3806    .035       0  3897.7     .07       0
  4329.9     .05       0  4974.8     .05       0  5017.8     .05       0
  5059.9     .07       0  5116.6     .05       0  5851.8    .035       0
    6059     .05       0  6201.4    .035       0  6484.6     .05       0
  7925.6    .035       0
Bank Sta=4974.8,5017.8
XS Rating Curve= 0 ,0
Exp/Cntr=0.3,0.1

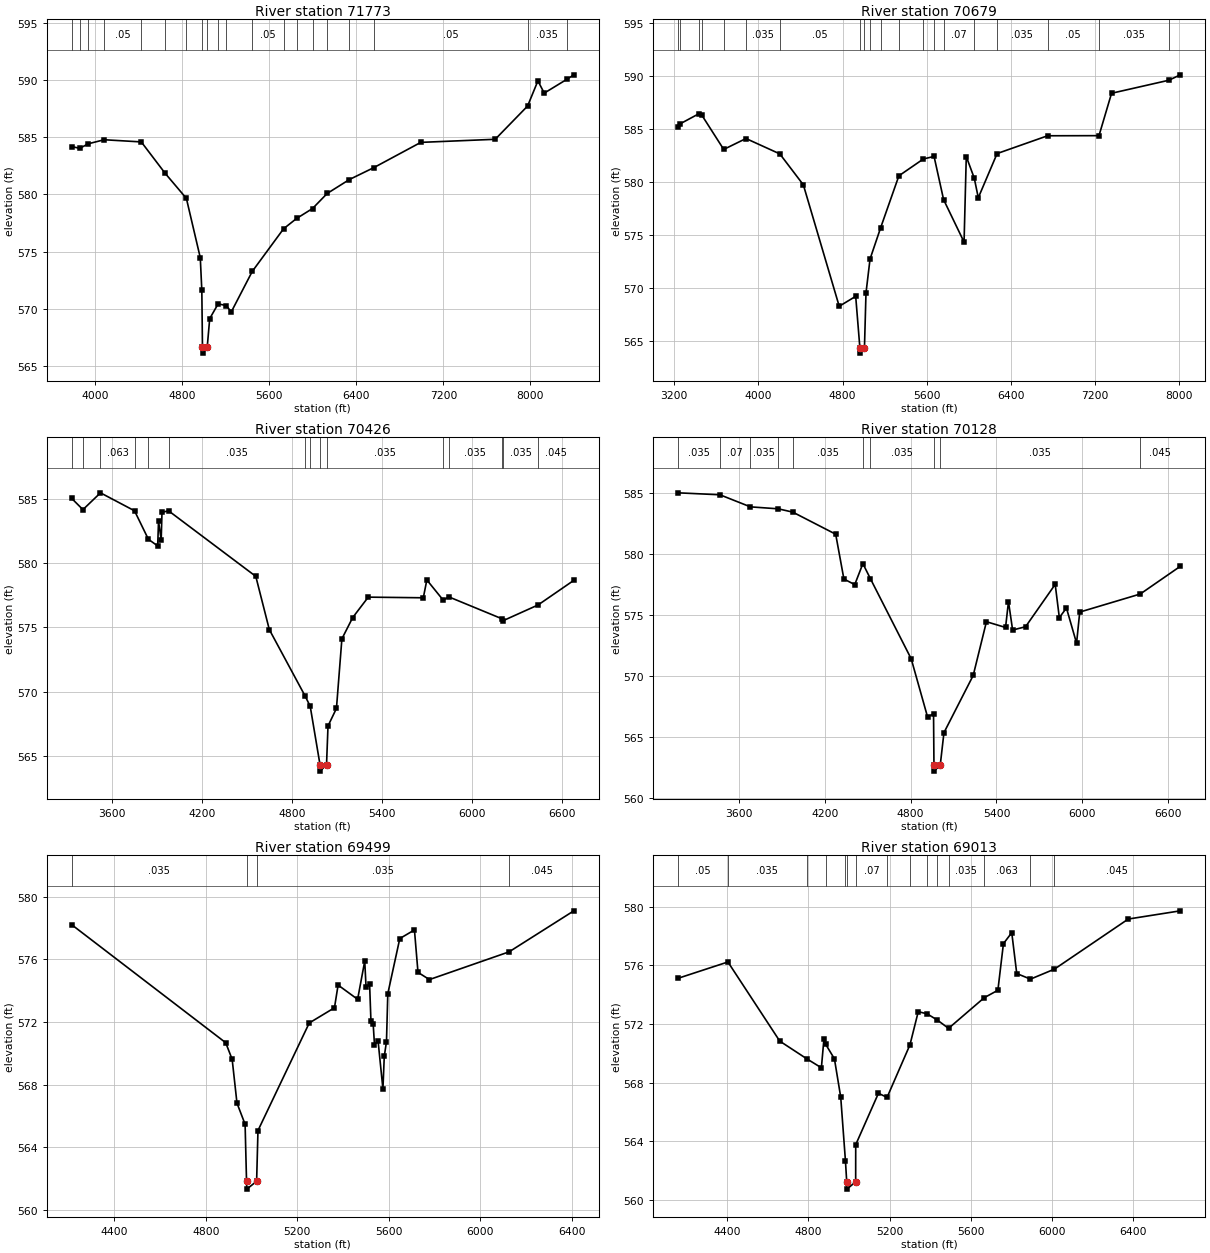
Type RM Length L Ch R = 1 ,71773   ,1094,1094,1094
BEGIN DESCRIPTION:
ALLIGATOR CREEK 87.0
END DESCRIPTION:
XS GIS Cut Line= 3
      2297211.54     13794447.16        2296375.       13793575.
      2293461.53     13791816.96
#Sta/Elev= 30
  3786.9  584.19    3860  584.04  3939.6  584.44  4084.8  584.79  4425.4   584.6
    4644  581.86  4839.5  579.66  4967.2  574.47  4981.4   571.6  4987.3  566.62
  4988.3  566.12  5030.7  566.62  5053.8  569.14  5131.3  570.43  5206.8  570.28
  5251.6  569.72  5444.6  573.27  5732.2     577  5851.4   577.9    5998  578.77
  6132.8  580.09    6337  581.31  6563.1  582.36  6992.6  584.56    7676  584.83
  7973.4  587.74  8068.1  589.94  8126.3  588.87  8336.2  590.09  8398.2  590.47
#Mann= 20 ,-1 , 0
  3786.9    .035       0    3860     .05       0  3939.6    .035       0
  4084.8     .05       0  4425.4     .07       0    4644     .05       0
  4839.5     .12       0  4987.3     .05       0  5030.7      .1       0
  5131.3     .12       0  5206.8     .07       0  5444.6     .05       0
  5732.2    .035       0  5851.4     .05       0    5998     .07       0
  6132.8     .12       0    6337     .12       0  6563.1     .05       0
  7973.4    .035       0  8336.2    .045       0
Bank Sta=4987.3,5030.7
XS Rating Curve= 0 ,0
Exp/Cntr=0.3,0.1

Type RM Length L Ch R = 1 ,70679   ,253,253,253
BEGIN DESCRIPTION:
ALLIGATOR CREEK 86.0
END DESCRIPTION:
XS GIS Cut Line= 3
      2297263.63     13794199.75        2296475.       13792625.
        2293575.       13791825.
#Sta/Elev= 30
  3238.5  585.14  3255.2  585.44  3435.1   586.4  3462.9  586.26  3670.6  583.03
    3882  584.06  4203.4  582.61    4427  579.69  4767.8  568.23  4924.3  569.17
    4964  564.31    4965  563.81  5007.5  564.31  5022.1  569.49  5060.6  572.69
  5161.9  575.66  5334.5  580.54  5567.3  582.13  5668.7  582.37  5759.4  578.29
  5953.7  574.29  5974.8  582.36  6050.7  580.32  6088.9  578.47  6267.5  582.64
  6747.4  584.32  7235.5  584.33  7354.8  588.33  7899.4  589.56    8008  590.07
#Mann= 20 ,-1 , 0
  3238.5    .035       0  3255.2    .063       0  3435.1    .035       0
  3462.9    .063       0  3670.6    .035       0    3882    .035       0
  4203.4     .05       0    4964     .05       0  5007.5     .05       0
  5060.6     .07       0  5161.9     .05       0  5334.5    .035       0
  5567.3     .07       0  5668.7     .05       0  5759.4     .07       0
  6050.7     .05       0  6267.5    .035       0  6747.4     .05       0
  7235.5    .035       0  7899.4    .045       0
Bank Sta=4964,5007.5
XS Rating Curve= 0 ,0
Exp/Cntr=0.3,0.1

Type RM Length L Ch R = 1 ,70426   ,298,298,298
BEGIN DESCRIPTION:
GER21678
END DESCRIPTION:
XS GIS Cut Line= 4
      2297243.45     13794093.07      2296879.31     13793275.35
      2296521.54     13791831.51      2295837.94     13791147.91
#Sta/Elev= 30
  3332.3  585.05  3406.8  584.18  3523.8  585.49  3750.9  584.09  3843.5  581.87
  3905.5  581.35    3911  583.28  3928.8  581.83  3934.2  583.97  3977.9  584.09
  4559.9  578.98  4650.2  574.83  4889.6  569.64    4923  568.85  4988.3   564.3
  4989.3   563.8  5031.8   564.3  5041.7  567.32    5098  568.69  5134.3  574.11
  5206.5  575.77  5310.1  577.36  5677.5  577.31    5701   578.7  5811.3  577.11
  5845.7  577.39    6203  575.67  6208.8  575.52    6443  576.75  6681.7  578.67
#Mann= 15 ,-1 , 0
  3332.3    .063       0  3406.8    .035       0  3523.8    .063       0
  3750.9    .035       0  3843.5    .063       0  3977.9    .035       0
  4889.6    .063       0    4923    .035       0  4988.3    .035       0
  5031.8    .035       0  5811.3     .05       0  5845.7    .035       0
    6203    .045       0  6208.8    .035       0    6443    .045       0
Bank Sta=4988.3,5031.8
XS Rating Curve= 0 ,0
Exp/Cntr=0.3,0.1

Type RM Length L Ch R = 1 ,70128   ,629,629,629
BEGIN DESCRIPTION:
ALLIGATOR CREEK 85.0
END DESCRIPTION:
XS GIS Cut Line= 3
      2297288.19      13794112.3      2296738.76     13791742.07
      2295889.52     13791084.39
#Sta/Elev= 30
  3177.2  585.01  3468.5  584.85  3681.5  583.86  3875.4   583.7  3977.2  583.43
  4277.1  581.62  4334.4  577.95  4410.2  577.49    4467  579.21  4519.8  577.97
  4804.6  571.41  4919.5  566.62  4960.6  566.93  4963.5  562.71  4964.5  562.21
  5007.5  562.71  5033.3  565.36  5237.7  570.05  5330.1  574.45  5463.6  573.98
  5484.1   576.1    5513  573.77  5603.5  574.04  5810.4  577.51  5839.3  574.79
  5889.1  575.57  5959.7  572.69  5981.8  575.24  6404.5  576.72  6684.4  578.99
#Mann= 10 ,-1 , 0
  3177.2    .035       0  3468.5     .07       0  3681.5    .035       0
  3875.4     .07       0  3977.2    .035       0    4467    .063       0
  4519.8    .035       0  4963.5    .035       0  5007.5    .035       0
  6404.5    .045       0
Bank Sta=4963.5,5007.5
XS Rating Curve= 0 ,0
Exp/Cntr=0.3,0.1

Type RM Length L Ch R = 1 ,69499   ,486,486,486
BEGIN DESCRIPTION:
X18000
END DESCRIPTION:
XS GIS Cut Line= 3
      2297697.68     13792363.86      2297128.47     13791767.62
      2295954.21     13791059.24
#Sta/Elev= 30
  4213.5   578.2  4886.6  570.67  4914.9  569.61    4936  566.81  4971.5  565.46
  4977.8  561.82  4978.8  561.32  5021.9  561.82  5027.8  565.06  5252.1  571.93
  5362.3   572.9  5378.2  574.35  5463.6  573.44  5494.7  575.88  5500.5  574.22
    5516   574.4  5521.9  572.03  5531.5  571.89  5537.4  570.53  5552.9   570.8
  5574.3  567.71  5580.1  569.79  5589.8  570.74  5595.6   573.8    5648  577.32
  5712.1  577.87  5727.6  575.16  5777.6   574.7  6125.9  576.47  6409.2  579.09
#Mann= 4 ,-1 , 0
  4213.5    .035       0  4977.8    .035       0  5021.9    .035       0
  6125.9    .045       0
Bank Sta=4977.8,5021.9
XS Rating Curve= 0 ,0
Exp/Cntr=0.3,0.1

Type RM Length L Ch R = 1 ,69013   ,715,715,715
BEGIN DESCRIPTION:
X17999
END DESCRIPTION:
XS GIS Cut Line= 2
      2298140.35     13791573.91      2295744.51     13790966.27
#Sta/Elev= 30
  4158.9  575.12  4403.5  576.23  4658.7  570.83  4792.1  569.62  4863.6  569.01
  4876.3  570.99  4884.5  570.62  4927.8  569.62  4958.8  567.01  4982.1  562.65
  4988.3  561.23  4989.3  560.73  5032.4  561.23  5032.6  563.76  5144.5  567.27
    5187  566.99  5299.7  570.58  5340.5  572.84  5384.3  572.69  5435.2  572.26
  5489.6   571.7  5665.1  573.79  5732.5   574.3  5759.8  577.48  5800.8  578.23
  5825.4  575.44    5893  575.06  6010.7  575.74  6374.4  579.16  6630.6  579.72
#Mann= 15 ,-1 , 0
  4158.9     .05       0  4403.5    .035       0  4792.1     .07       0
  4884.5    .035       0  4982.1     .07       0  4988.3     .05       0
  5032.4     .07       0    5187    .035       0  5299.7    .063       0
  5384.3    .035       0  5435.2    .063       0  5489.6    .035       0
  5665.1    .063       0    5893    .035       0  6010.7    .045       0
Bank Sta=4988.3,5032.4
XS Rating Curve= 0 ,0
Exp/Cntr=0.3,0.1

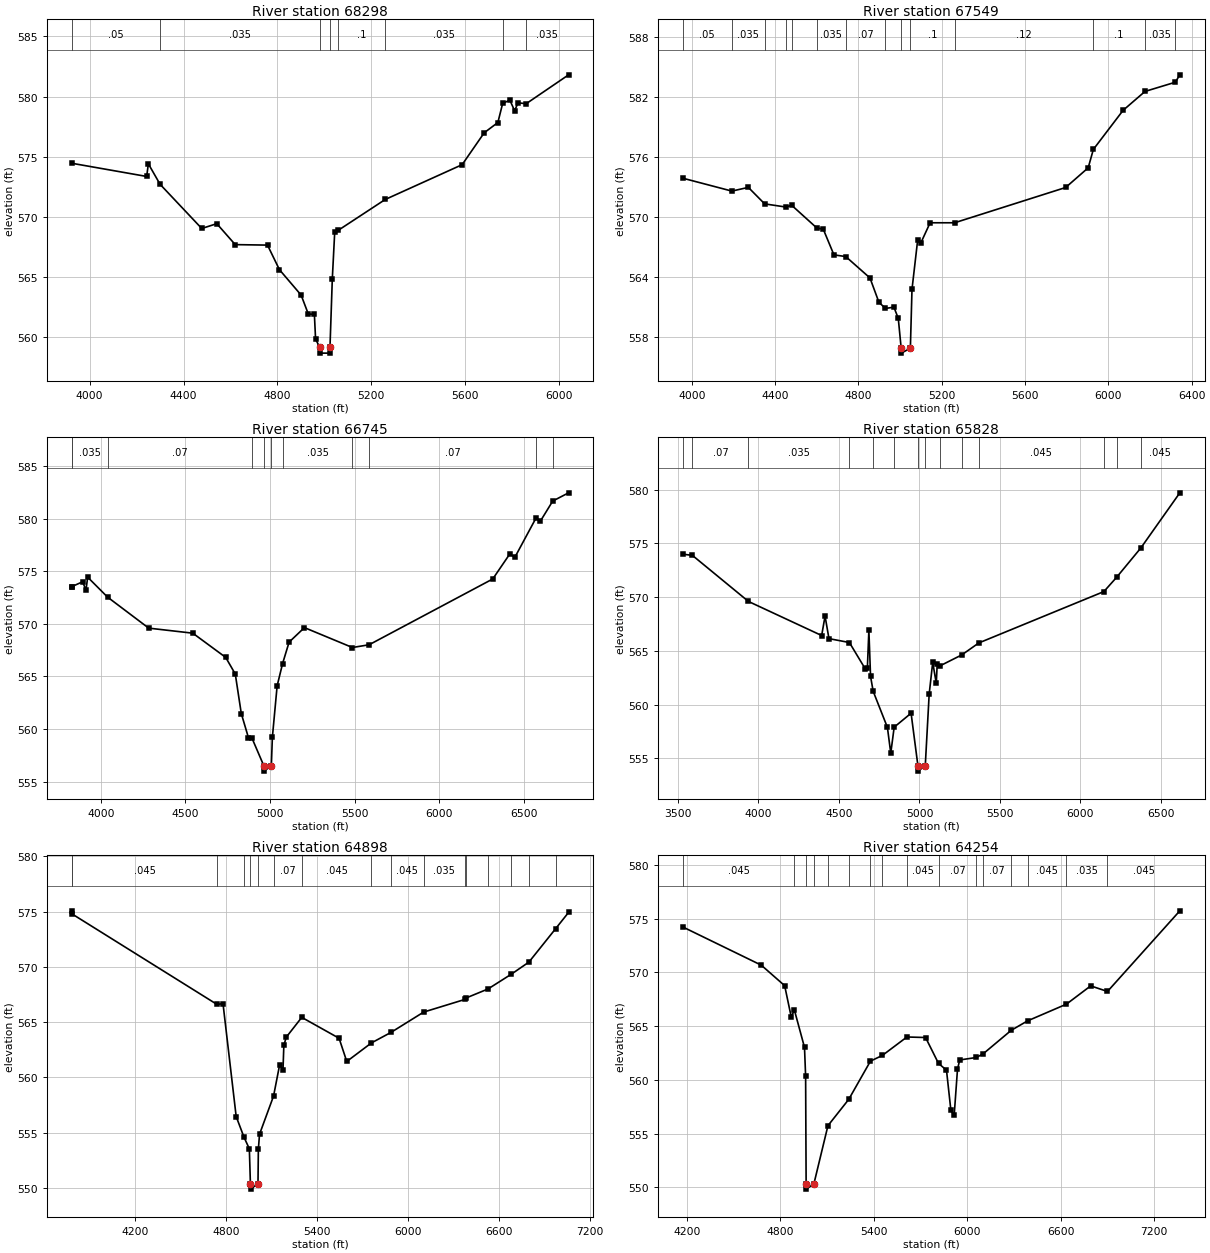
Type RM Length L Ch R = 1 ,68298   ,749,749,749
BEGIN DESCRIPTION:
X17998
END DESCRIPTION:
XS GIS Cut Line= 3
      2298235.84     13791244.04      2297688.99     13790810.03
      2296300.15      13790514.9
#Sta/Elev= 30
  3922.7  574.47  4242.9  573.37  4250.1  574.42    4300  572.72  4477.6  569.05
  4541.7  569.45  4620.2  567.71  4757.8  567.67  4808.6  565.63    4901  563.52
  4931.6  561.95  4957.5  561.92  4962.6  559.86  4979.9   559.2  4980.9   558.7
    5023   558.7    5024   559.2  5033.9  564.87  5044.1  568.74  5059.3   568.9
  5259.5  571.46  5587.1  574.35  5681.2     577  5739.3  577.85  5759.8  579.44
  5790.4  579.71  5810.8  578.82    5825  579.49  5859.8  579.41  6040.7  581.81
#Mann= 8 ,-1 , 0
  3922.7     .05       0    4300    .035       0  4979.9    .035       0
    5024    .035       0  5059.3      .1       0  5259.5    .035       0
  5759.8    .063       0  5859.8    .035       0
Bank Sta=4979.9,5024
XS Rating Curve= 0 ,0
Exp/Cntr=0.3,0.1

Type RM Length L Ch R = 1 ,67549   ,804,804,804
BEGIN DESCRIPTION:
X17997
END DESCRIPTION:
XS GIS Cut Line= 3
      2298366.06     13791131.18      2297688.99     13790124.27
      2296578.92     13789742.68
#Sta/Elev= 30
  3956.1  573.88    4192  572.59  4271.2  572.96  4349.5  571.31  4452.8  570.99
  4478.8  571.18  4599.4  568.91  4631.2  568.77  4682.2  566.21    4739  566.04
  4855.3   563.9  4898.2  561.47  4929.7  560.85  4970.2  560.98  4991.2  559.86
  5005.1  556.88  5006.1  556.38  5049.3  556.88  5057.1  562.76  5084.2  567.67
  5099.2  567.39  5144.1  569.42  5261.7  569.42  5795.1  572.95  5903.3  574.92
  5928.1  576.76    6071  580.67  6176.2  582.56  6321.8  583.48  6343.3  584.22
#Mann= 14 ,-1 , 0
  3956.1     .05       0    4192    .035       0  4349.5     .07       0
  4452.8    .035       0  4478.8     .07       0  4599.4    .035       0
    4739     .07       0  4929.7      .1       0  5005.1     .05       0
  5049.3      .1       0  5261.7     .12       0  5928.1      .1       0
  6176.2    .035       0  6321.8    .063       0
Bank Sta=5005.1,5049.3
XS Rating Curve= 0 ,0
Exp/Cntr=0.3,0.1

Type RM Length L Ch R = 1 ,66745   ,917,917,917
BEGIN DESCRIPTION:
X17996
END DESCRIPTION:
XS GIS Cut Line= 4
      2298661.22     13790940.23      2298591.77     13790037.46
      2298261.91     13789698.92      2296709.04     13789534.09
#Sta/Elev= 30
    3826  573.52  3827.4  573.53  3891.4  573.99  3911.5  573.21  3921.5  574.43
  4038.9  572.54  4282.6  569.59  4543.3  569.11  4737.9  566.81  4794.5  565.23
    4830  561.48  4872.4  559.18  4892.5  559.17  4963.5  556.51  4964.5  556.01
  5007.7  556.51  5013.8  559.22    5042  564.11  5074.3  566.23  5112.7  568.26
  5203.4  569.64  5487.1  567.75  5585.8  568.01  6317.2  574.26  6417.8  576.63
    6448  576.32  6573.1  580.05  6598.8  579.75  6671.9  581.66  6765.7  582.44
#Mann= 11 ,-1 , 0
    3826     .05       0  3827.4    .035       0  4038.9     .07       0
  4892.5      .1       0  4963.5     .05       0  5007.7      .1       0
  5074.3    .035       0  5487.1     .12       0  5585.8     .07       0
  6573.1      .1       0  6671.9    .035       0
Bank Sta=4963.5,5007.7
XS Rating Curve= 0 ,0
Exp/Cntr=0.3,0.1

Type RM Length L Ch R = 1 ,65828   ,930,930,930
BEGIN DESCRIPTION:
ALLIGATOR CREEK 84.0
END DESCRIPTION:
XS GIS Cut Line= 3
      2298721.99     13790879.46      2299173.37     13789421.14
      2298444.18     13788040.89
#Sta/Elev= 30
  3529.6     574  3589.5  573.89  3937.9   569.6  4392.6  566.43  4413.6  568.24
  4437.9  566.14  4564.8  565.78  4664.8  563.29  4676.6  563.45  4685.8  566.92
  4696.2  562.63  4712.5  561.24  4800.9  557.88  4821.8  555.48  4842.9   557.9
    4948   559.2  4990.4  554.31  4991.4  553.81  5036.1  554.31  5060.4  560.99
  5082.4  563.93  5104.5  561.98  5110.1  563.75  5127.9  563.61  5263.2  564.63
  5368.7  565.74  6145.6  570.52  6224.1  571.84  6375.2  574.58  6617.2  579.71
#Mann= 14 ,-1 , 0
  3529.6    .035       0  3589.5     .07       0  3937.9    .035       0
  4564.8     .07       0  4712.5    .035       0  4842.9      .1       0
  4990.4     .05       0  5036.1      .1       0  5127.9     .07       0
  5263.2    .035       0  5368.7    .045       0  6145.6     .07       0
  6224.1    .035       0  6375.2    .045       0
Bank Sta=4990.4,5036.1
XS Rating Curve= 0 ,0
Exp/Cntr=0.3,0.1

Type RM Length L Ch R = 1 ,64898   ,644,644,644
BEGIN DESCRIPTION:
ALLIGATOR CREEK 83.0
END DESCRIPTION:
XS GIS Cut Line= 3
      2300510.16     13790836.04      2299815.73     13789594.76
      2298625.01     13788175.01
#Sta/Elev= 30
  3783.7  575.07  3789.4  574.77  4742.4   566.6  4781.8  566.68  4868.6  556.46
  4920.4  554.58  4955.4  553.54  4962.4  550.39  4963.4  549.89  5012.4  550.39
  5014.8  553.49  5022.4  554.85  5114.9  558.31  5155.3  561.16    5177  560.66
  5182.8   562.9  5198.7  563.64  5300.8  565.43  5546.7  563.54  5597.3  561.44
  5759.9  563.12  5888.7  564.07  6104.2  565.91  6374.9  567.05  6382.7  567.18
    6528     568  6681.9  569.34  6797.4  570.43  6973.3  573.45    7059  574.93
#Mann= 17 ,-1 , 0
  3783.7    .035       0  3789.4    .045       0  4742.4    .035       0
  4920.4      .1       0  4962.4     .05       0  5012.4      .1       0
  5114.9     .07       0  5300.8    .045       0  5759.9     .07       0
  5888.7    .045       0  6104.2    .035       0  6374.9    .045       0
  6382.7    .035       0    6528    .045       0  6681.9     .07       0
  6797.4    .035       0  6973.3    .045       0
Bank Sta=4962.4,5012.4
XS Rating Curve= 0 ,0
Exp/Cntr=0.3,0.1

Type RM Length L Ch R = 1 ,64254   ,824,824,824
BEGIN DESCRIPTION:
ALLIGATOR CREEK 82.0
END DESCRIPTION:
XS GIS Cut Line= 3
      2301022.31     13790332.58      2300579.62     13789733.64
      2298824.99     13788024.99
#Sta/Elev= 30
  4172.5  574.24  4677.1  570.68  4827.4  568.77  4869.1  565.89  4890.5  566.47
  4954.9  563.02  4962.1  560.33  4965.3  550.32  4966.3  549.82  5015.4  550.32
  5105.5  555.73  5239.1  558.18  5378.6  561.74  5455.9  562.28    5613  563.99
  5732.9  563.94  5815.9  561.53  5867.2   560.9  5895.5  557.15  5916.6   556.7
  5937.9  560.98  5952.1  561.85    6059  562.08  6103.5  562.43    6283  564.61
    6388  565.49  6638.1  567.05  6793.7  568.75  6901.6  568.23  7366.4  575.74
#Mann= 16 ,-1 , 0
  4172.5    .045       0  4890.5     .07       0  4965.3     .05       0
  5015.4     .12       0  5105.5     .12       0  5239.1     .07       0
  5378.6    .045       0  5455.9     .07       0    5613    .045       0
  5815.9     .07       0    6059    .035       0  6103.5     .07       0
    6283    .035       0    6388    .045       0  6638.1    .035       0
  6901.6    .045       0
Bank Sta=4965.3,5015.4
XS Rating Curve= 0 ,0
Exp/Cntr=0.3,0.1

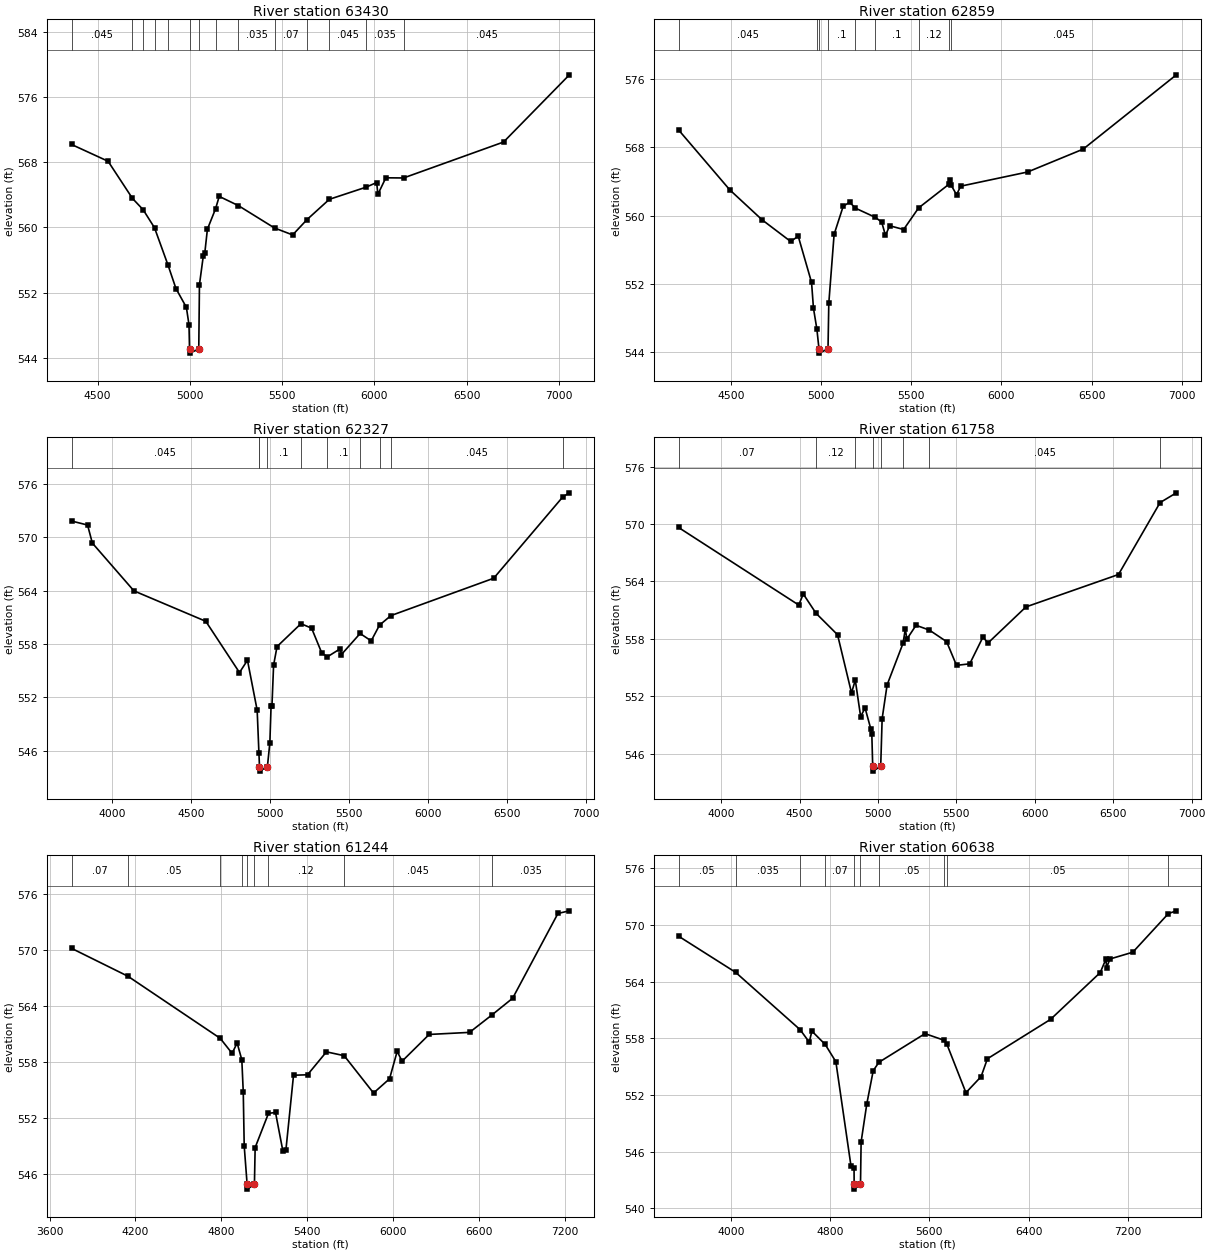
Type RM Length L Ch R = 1 ,63430   ,571,571,571
BEGIN DESCRIPTION:
ALLIGATOR CREEK 81.0
END DESCRIPTION:
XS GIS Cut Line= 3
      2301024.98     13789524.98        2300575.       13789075.
      2298975.02     13787775.02
#Sta/Elev= 30
  4359.1  570.18  4557.1  568.12  4689.2  563.56  4747.1  562.17  4808.6  559.96
  4882.4  555.34  4924.8   552.5  4981.3  550.19  4995.5  548.06  4998.4  545.07
  4999.4  544.57  5048.5  545.07  5052.2  552.98    5073  556.49    5081  556.83
  5095.3  559.78  5139.7   562.3  5159.3  563.81  5263.7  562.67    5459  559.93
  5557.2  559.08  5635.5  560.97  5756.2  563.45  5955.2  564.94  6012.6  565.51
  6019.1  564.06  6062.2  566.09  6158.2  566.07  6700.2  570.48    7057  578.73
#Mann= 14 ,-1 , 0
  4359.1    .045       0  4689.2     .07       0  4747.1    .045       0
  4808.6     .07       0  4882.4     .12       0  4998.4     .05       0
  5048.5     .12       0  5139.7     .12       0  5263.7    .035       0
    5459     .07       0  5635.5    .035       0  5756.2    .045       0
  5955.2    .035       0  6158.2    .045       0
Bank Sta=4998.4,5048.5
XS Rating Curve= 0 ,0
Exp/Cntr=0.3,0.1

Type RM Length L Ch R = 1 ,62859   ,532,532,532
BEGIN DESCRIPTION:
ALLIGATOR CREEK 80.0
END DESCRIPTION:
XS GIS Cut Line= 3
      2301124.98     13789374.95        2300875.       13788625.
      2299275.02     13787475.01
#Sta/Elev= 30
  4209.2  570.05  4493.8  563.01    4673   559.5  4831.1  556.97  4873.2  557.58
    4947  552.17  4957.6  549.15  4976.6  546.69  4988.2  544.38  4989.2  543.88
  5038.3  544.38  5042.7  549.74  5072.1   557.8  5122.5  561.09  5158.1  561.57
  5190.5  560.87  5301.3  559.79  5336.1  559.23    5357  557.68  5380.3  558.81
  5457.7  558.37  5540.7   560.9  5709.3  563.68  5715.5  564.19  5721.3  563.56
  5751.1  562.45  5774.4  563.45  6145.2  565.11  6453.3  567.79  6970.1   576.5
#Mann= 9 ,-1 , 0
  4209.2    .045       0  4976.6      .1       0  4988.2     .05       0
  5038.3      .1       0  5190.5    .035       0  5301.3      .1       0
  5540.7     .12       0  5709.3     .07       0  5721.3    .045       0
Bank Sta=4988.2,5038.3
XS Rating Curve= 0 ,0
Exp/Cntr=0.3,0.1

Type RM Length L Ch R = 1 ,62327   ,569,569,569
BEGIN DESCRIPTION:
ALLIGATOR CREEK 79.0
END DESCRIPTION:
XS GIS Cut Line= 3
        2301375.     13789475.03        2301175.       13788225.
      2299575.02     13787225.01
#Sta/Elev= 30
  3744.3  571.82  3845.6  571.37    3876  569.34  4139.3  563.97  4594.4  560.55
  4807.7  554.79  4858.3  556.17  4919.7  550.56  4930.9  545.75  4934.5  544.21
  4935.5  543.71  4984.6  544.21  5000.1  546.91  5007.7  550.98  5013.2  550.98
  5023.8  555.62  5045.6  557.71    5197  560.28  5264.4  559.78  5328.6     557
  5363.6  556.55  5446.5  557.47    5453  556.81  5571.7  559.18  5641.7  558.35
  5694.6  560.12  5766.6  561.19  6417.7  565.39  6855.2  574.53    6897  574.99
#Mann= 10 ,-1 , 0
  3744.3    .045       0  4930.9      .1       0  4934.5     .05       0
  4984.6      .1       0    5197     .12       0  5363.6      .1       0
  5571.7    .045       0  5694.6     .07       0  5766.6    .045       0
  6855.2    .035       0
Bank Sta=4934.5,4984.6
XS Rating Curve= 0 ,0
Exp/Cntr=0.3,0.1

Type RM Length L Ch R = 1 ,61758   ,514,514,514
BEGIN DESCRIPTION:
ALLIGATOR CREEK 78.0
END DESCRIPTION:
XS GIS Cut Line= 3
      2302624.96     13788474.98        2301525.       13787825.
      2299725.02     13787225.01
#Sta/Elev= 30
  3727.5  569.64  4494.1  561.53  4523.3  562.68  4604.3  560.67  4741.8  558.42
  4830.9  552.34  4854.9  553.68    4889  549.87  4917.4  550.76  4954.4  548.54
  4960.3  548.06    4966  544.66    4967  544.16    5017  544.66  5026.2  549.65
  5057.9  553.18  5159.5  557.53  5173.8     559  5184.3  557.97  5242.3  559.41
  5327.2  558.91  5437.3   557.7  5500.6  555.22  5584.9  555.38  5669.2  558.18
  5700.9  557.55  5943.3  561.33  6533.6  564.72  6798.8  572.24  6902.5  573.26
#Mann= 8 ,-1 , 0
  3727.5     .07       0  4604.3     .12       0  4854.9      .1       0
    4966     .05       0    5017      .1       0  5159.5     .12       0
  5327.2    .045       0  6798.8    .035       0
Bank Sta=4966,5017
XS Rating Curve= 0 ,0
Exp/Cntr=0.3,0.1

Type RM Length L Ch R = 1 ,61244   ,606,606,606
BEGIN DESCRIPTION:
ALLIGATOR CREEK 77.0
END DESCRIPTION:
XS GIS Cut Line= 3
      2302724.97     13788524.97        2301925.       13787575.
        2299725.       13787175.
#Sta/Elev= 30
  3753.4  570.14  4147.2  567.16  4791.6  560.53    4875  558.92  4910.2  560.03
  4942.9  558.23    4953  554.78  4959.6  549.02    4980  544.91    4981  544.41
    5031  544.91    5036  548.85  5129.2  552.51  5178.3   552.6  5229.1  548.53
  5250.7  548.56  5304.1  556.58  5401.9  556.63    5534  559.08  5657.9  558.67
  5863.1  554.68  5974.9   556.2  6028.2  559.13  6062.5  558.08  6251.9  560.94
  6533.9  561.16    6690  563.02    6835  564.81  7151.4  573.87  7231.4  574.15
#Mann= 9 ,-1 , 0
  3753.4     .07       0  4147.2     .05       0  4791.6     .07       0
  4942.9      .1       0    4980     .05       0    5031      .1       0
  5129.2     .12       0  5657.9    .045       0    6690    .035       0
Bank Sta=4980,5031
XS Rating Curve= 0 ,0
Exp/Cntr=0.3,0.1

Type RM Length L Ch R = 1 ,60638   ,500,500,500
BEGIN DESCRIPTION:
ALLIGATOR CREEK 76.0
END DESCRIPTION:
XS GIS Cut Line= 3
      2303183.79     13787867.33      2302341.77     13787068.71
        2299539.     13786522.04
#Sta/Elev= 30
  3576.4  568.83    4037     565  4557.3  558.93  4631.2  557.61  4652.3  558.78
    4760  557.36  4845.7  555.54    4968  544.48  4992.4  544.33  4993.4  542.55
  4994.4  542.05  5044.5  542.55  5049.5  547.05  5095.6  551.09  5147.2  554.59
  5193.3  555.48    5565  558.51  5718.6  557.81  5740.8  557.41  5895.1  552.26
  6017.4  553.96  6068.3  555.85  6577.7  560.02  6978.3  564.97  7024.8  566.41
  7029.8  565.49  7056.6  566.41  7241.3  567.13  7528.5  571.22  7592.5  571.51
#Mann= 10 ,-1 , 0
  3576.4     .05       0    4037    .035       0  4557.3     .05       0
    4760     .07       0  4993.4     .05       0  5044.5     .07       0
  5193.3     .05       0  5718.6     .07       0  5740.8     .05       0
  7528.5    .035       0
Bank Sta=4993.4,5044.5
XS Rating Curve= 0 ,0
Exp/Cntr=0.3,0.1

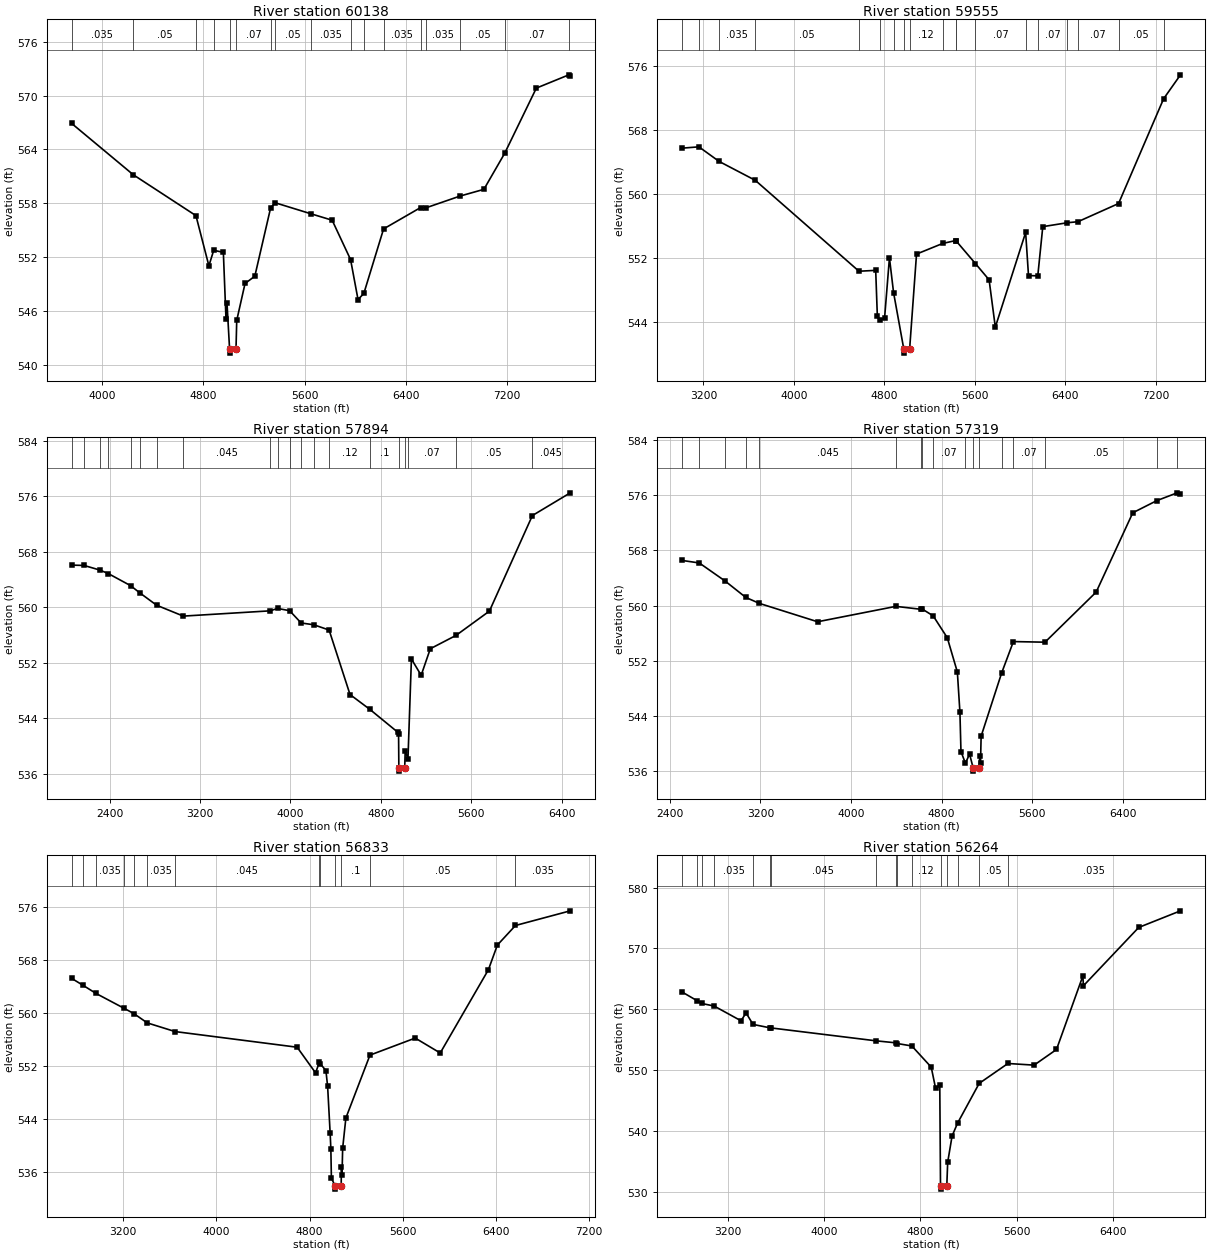
Type RM Length L Ch R = 1 ,60138   ,583,583,583
BEGIN DESCRIPTION:
ALLIGATOR CREEK 75.0
END DESCRIPTION:
XS GIS Cut Line= 3
      2303125.01     13787575.01        2302325.       13786625.
       2299815.7     13785627.73
#Sta/Elev= 30
  3758.7   566.9  4245.9  561.18  4741.7  556.62    4844  551.03  4882.2  552.76
  4958.4  552.53  4979.2  545.12    4987  546.94  5007.4   541.8  5008.4   541.3
  5058.5   541.8  5064.1  544.94  5129.8  549.06  5207.1  549.87  5332.3   557.5
  5369.1  558.05    5650  556.83  5818.5  556.11  5964.2  551.72    6023  547.27
    6069  547.95    6225  555.14  6517.7  557.52  6561.9   557.5  6829.4   558.8
  7018.1  559.55  7182.2  563.56  7432.6  570.83  7689.9  572.31  7700.9  572.18
#Mann= 17 ,-1 , 0
  3758.7    .035       0  4245.9     .05       0  4741.7     .07       0
  4882.2     .12       0  5007.4     .05       0  5058.5     .07       0
  5332.3     .07       0  5369.1     .05       0    5650    .035       0
  5964.2     .07       0    6069     .05       0    6225    .035       0
  6517.7     .05       0  6561.9    .035       0  6829.4     .05       0
  7182.2     .07       0  7689.9    .035       0
Bank Sta=5007.4,5058.5
XS Rating Curve= 0 ,0
Exp/Cntr=0.3,0.1

Type RM Length L Ch R = 1 ,59555   ,1661,1661,1661
BEGIN DESCRIPTION:
ALLIGATOR CREEK 74.0
END DESCRIPTION:
XS GIS Cut Line= 3
      2303875.02     13787325.02        2302325.       13786075.
      2300124.97     13785074.99
#Sta/Elev= 30
  3008.7  565.74  3159.7  565.91  3338.5  564.08  3658.2  561.71  4574.7  550.31
  4722.5  550.42  4736.9  544.75  4756.9  544.19  4800.8   544.4    4844  551.99
  4880.5  547.63    4971  540.54    4972  540.04  5022.4  540.54  5083.4  552.46
  5313.9  553.79  5430.2  554.16  5430.5  554.16  5604.1  551.27  5724.9  549.23
  5779.9   543.3  6047.9  555.17  6073.2  549.77  6155.2  549.73  6199.5   555.9
  6415.9  556.39  6510.1  556.52  6869.3   558.8  7267.1  571.93  7416.6  574.94
#Mann= 19 ,-1 , 0
  3008.7    .035       0  3159.7     .05       0  3338.5    .035       0
  3658.2     .05       0  4574.7     .07       0  4756.9    .045       0
  4880.5     .12       0    4971     .05       0  5022.4     .12       0
  5313.9     .05       0  5430.2      .1       0  5430.5     .05       0
  5604.1     .07       0  6047.9      .1       0  6155.2     .07       0
  6415.9     .05       0  6510.1     .07       0  6869.3     .05       0
  7267.1    .045       0
Bank Sta=4971,5022.4
XS Rating Curve= 0 ,0
Exp/Cntr=0.3,0.1

Type RM Length L Ch R = 1 ,57894   ,575,575,575
BEGIN DESCRIPTION:
ALLIGATOR CREEK 73.0
END DESCRIPTION:
XS GIS Cut Line= 3
      2304086.55     13786452.39        2301425.       13785225.
      2300032.76     13784716.29
#Sta/Elev= 30
  2063.2   566.1  2173.6  566.05  2313.9  565.38  2387.6  564.88  2584.8  563.14
  2667.1  562.09  2815.6  560.31  3051.9  558.74  3820.3   559.5  3885.7  559.85
  3992.7  559.52  4094.6  557.75  4206.6  557.49  4342.1  556.73  4527.3  547.42
  4703.6  545.27  4950.1  541.98  4956.9  541.74  4959.4  536.87  4960.4  536.37
  5011.4  536.87  5015.4  539.26  5040.1  538.18  5070.5  552.55  5156.8   550.2
  5237.7  554.03  5465.8  555.96  5760.7  559.46    6141  573.25  6476.4  576.53
#Mann= 20 ,-1 , 0
  2063.2    .035       0  2173.6    .035       0  2313.9    .035       0
  2387.6     .05       0  2584.8     .07       0  2667.1     .05       0
  2815.6    .035       0  3051.9    .045       0  3820.3    .045       0
  3885.7     .07       0  3992.7     .12       0  4094.6    .035       0
  4206.6     .12       0  4342.1     .12       0  4703.6      .1       0
  4959.4     .05       0  5011.4      .1       0  5040.1     .07       0
  5465.8     .05       0    6141    .045       0
Bank Sta=4959.4,5011.4
XS Rating Curve= 0 ,0
Exp/Cntr=0.3,0.1

Type RM Length L Ch R = 1 ,57319   ,486,486,486
BEGIN DESCRIPTION:
ALLIGATOR CREEK 72.0
END DESCRIPTION:
XS GIS Cut Line= 3
      2304017.12     13786200.66      2301890.38     13785080.87
      2300084.79     13784221.48
#Sta/Elev= 30
  2506.2  566.55  2660.4  566.18  2887.8  563.57  3070.7  561.19  3191.4  560.32
  3705.2  557.66  4396.2  559.89  4616.3  559.47  4623.6  559.56  4725.9  558.51
  4850.4  555.34  4939.2  550.38  4961.9  544.54  4971.1  538.86  5010.2  537.17
  5047.2  538.49    5078  536.52    5079  536.02    5130  536.52  5137.2  538.16
  5143.6  537.16  5149.1  541.08    5330  550.23    5434  554.79  5713.1   554.7
  6164.9  561.96  6488.3  573.45  6700.4  575.21  6880.5  576.34  6909.4  576.22
#Mann= 17 ,-1 , 0
  2506.2    .035       0  2660.4     .05       0  2887.8     .07       0
  3070.7     .05       0  3191.4    .045       0  4396.2    .035       0
  4616.3     .07       0  4623.6    .035       0  4725.9     .07       0
  5010.2     .12       0    5078     .05       0    5130     .12       0
    5330     .05       0    5434     .07       0  5713.1     .05       0
  6700.4     .07       0  6880.5    .045       0
Bank Sta=5078,5130
XS Rating Curve= 0 ,0
Exp/Cntr=0.3,0.1

Type RM Length L Ch R = 1 ,56833   ,569,569,569
BEGIN DESCRIPTION:
ALLIGATOR CREEK 71.0
END DESCRIPTION:
XS GIS Cut Line= 3
      2303973.69     13785853.42        2302075.       13784675.
      2300110.86     13784091.28
#Sta/Elev= 30
  2755.4  565.22  2853.9  564.17  2965.9  562.94    3208  560.69  3291.2   559.9
    3405  558.51  3644.3   557.2    4693  554.84  4851.3  550.97  4884.8  552.63
  4893.1  552.31  4939.9  551.33  4954.7  548.95  4976.5  541.85  4982.4  539.57
  4987.1   535.1  5019.1  533.95  5020.1  533.45  5071.1  533.95  5073.1  536.75
  5078.3  535.56  5083.9  539.63  5111.5  544.17  5318.4  553.65  5707.2  556.22
    5922  553.97  6335.8  566.52  6412.9  570.24  6568.4  573.19  7039.1   575.4
#Mann= 13 ,-1 , 0
  2755.4    .035       0  2853.9     .05       0  2965.9    .035       0
    3208     .05       0  3291.2    .045       0    3405    .035       0
  3644.3    .045       0  4884.8     .12       0  4893.1      .1       0
  5019.1     .05       0  5071.1      .1       0  5318.4     .05       0
  6568.4    .035       0
Bank Sta=5019.1,5071.1
XS Rating Curve= 0 ,0
Exp/Cntr=0.3,0.1

Type RM Length L Ch R = 1 ,56264   ,514,514,514
BEGIN DESCRIPTION:
ALLIGATOR CREEK 70.0
END DESCRIPTION:
XS GIS Cut Line= 3
      2303869.55     13785653.78        2302275.       13784175.
      2300319.64     13784030.55
#Sta/Elev= 30
  2820.9  562.86  2945.5  561.43  2986.1  560.95  3088.8  560.53  3311.5  558.11
    3354  559.39  3411.3  557.51  3551.7  556.95  3557.5  556.94  4432.8  554.81
  4597.7  554.48  4607.3  554.37  4728.4  553.97  4889.3  550.49    4925  547.05
  4960.2  547.54  4966.2  530.95  4967.2  530.45  5018.3  530.95  5025.7  534.86
  5062.1  539.17  5107.2  541.27  5286.9  547.82  5525.3  551.09  5742.4  550.82
  5928.1  553.39  6146.6  565.46  6151.6  563.86    6610  573.44  6956.3  576.17
#Mann= 16 ,-1 , 0
  2820.9     .05       0  2945.5    .035       0  2986.1     .05       0
  3088.8    .035       0  3411.3    .045       0  3551.7    .035       0
  3557.5    .045       0  4432.8    .035       0  4597.7    .045       0
  4607.3    .035       0  4728.4     .12       0  4966.2     .05       0
  5018.3     .12       0  5107.2     .12       0  5286.9     .05       0
  5525.3    .035       0
Bank Sta=4966.2,5018.3
XS Rating Curve= 0 ,0
Exp/Cntr=0.3,0.1