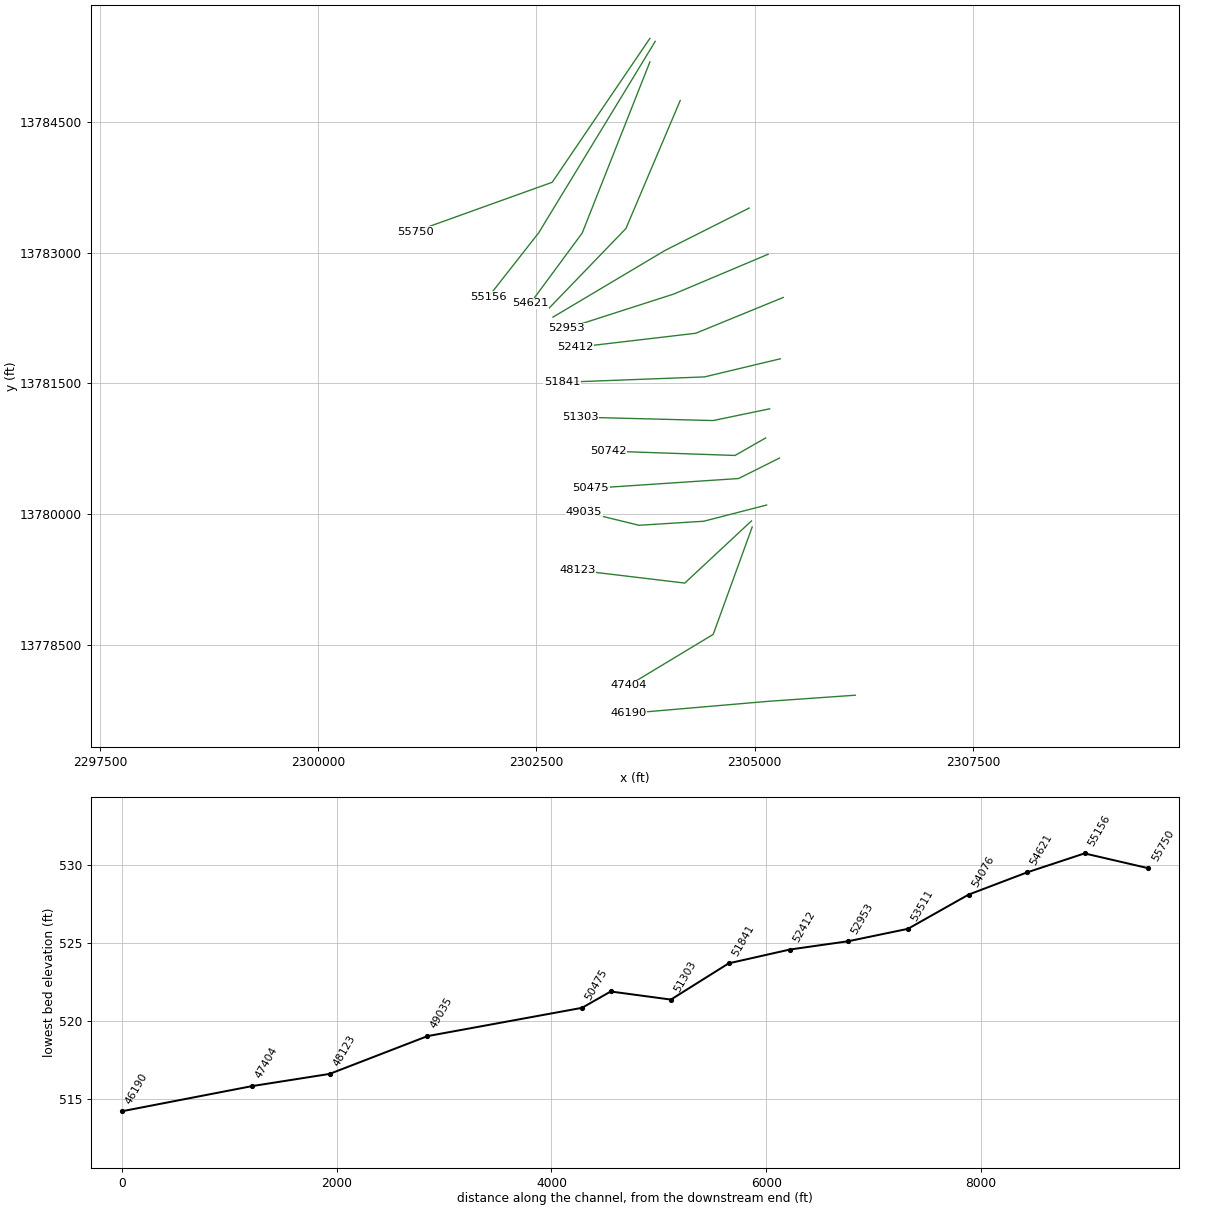
HEC-RAS study GERONIMO CREEK.prj: GERONIMO CREEK Base Level Engineering

--- GERONIMO CREEK.g01 (geometry) --- (continued)

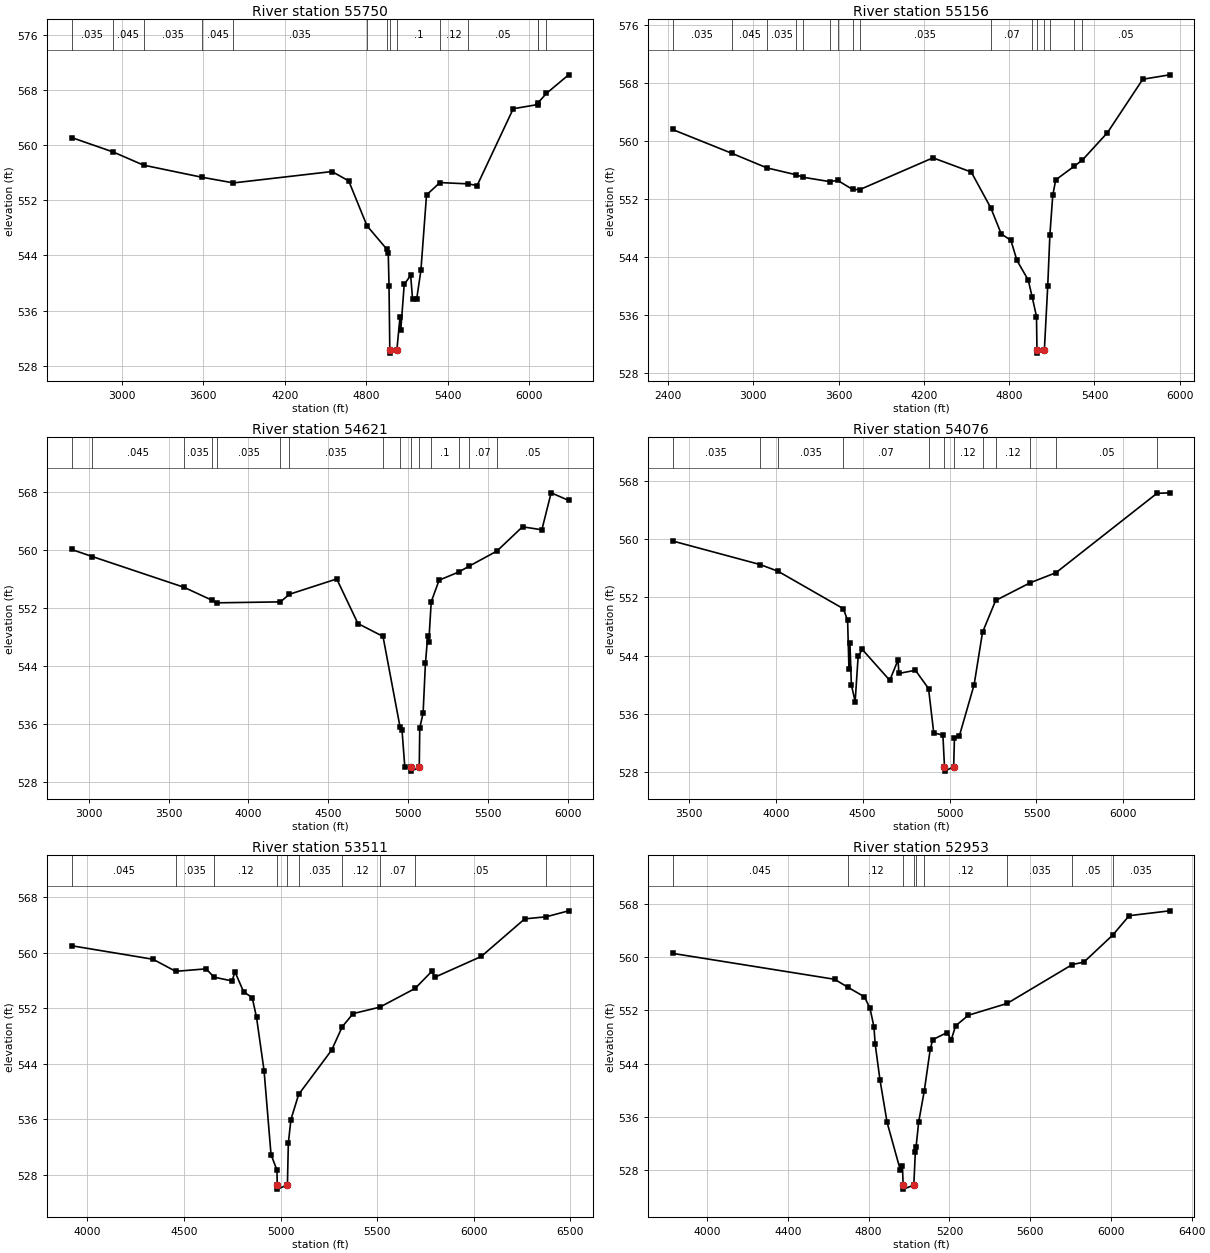
Type RM Length L Ch R = 1 ,55750   ,594,594,594
BEGIN DESCRIPTION:
ALLIGATOR CREEK 69.0
END DESCRIPTION:
XS GIS Cut Line= 3
      2303800.13     13785454.16      2302680.31     13783804.83
      2301109.59     13783240.75
#Sta/Elev= 30
  2629.3  561.12  2935.9  559.02  3159.6  557.11  3587.7  555.36  3822.4  554.53
  4548.2  556.18  4671.5  554.82  4806.3   548.3  4953.4  544.88  4962.9   544.3
  4968.5  539.63  4974.2  530.32  4975.2  529.82  5026.5  530.32  5049.8  535.12
  5055.1  533.17  5080.5  539.81  5127.9   541.1    5142  537.64  5172.7  537.73
  5203.4  541.83  5244.8  552.78  5343.6  554.58  5550.7  554.39  5617.7  554.15
  5883.7   565.3  6063.2   565.9  6068.4   566.2  6127.4  567.51  6291.8  570.22
#Mann= 14 ,-1 , 0
  2629.3    .035       0  2935.9    .045       0  3159.6    .035       0
  3587.7    .045       0  3822.4    .035       0  4806.3     .07       0
  4953.4      .1       0  4974.2     .05       0  5026.5      .1       0
  5343.6     .12       0  5550.7     .05       0  6063.2    .045       0
  6068.4     .05       0  6127.4    .045       0
Bank Sta=4974.2,5026.5
XS Rating Curve= 0 ,0
Exp/Cntr=0.3,0.1

Type RM Length L Ch R = 1 ,55156   ,535,535,535
BEGIN DESCRIPTION:
ALLIGATOR CREEK 68.0
END DESCRIPTION:
XS GIS Cut Line= 3
      2303860.87     13785419.42        2302525.       13783225.
      2301951.17     13782494.09
#Sta/Elev= 30
  2430.9  561.62  2849.9  558.32  3095.4  556.32  3299.3  555.38    3350  555.03
    3537  554.43  3592.7   554.6  3697.9  553.35  3748.9  553.33  4263.9  557.71
  4533.1  555.75    4671  550.79  4744.3  547.21    4812  546.33  4854.7  543.56
  4934.1  540.85  4961.9  538.52  4992.2  535.82  4995.5  531.27  4996.5  530.77
  5047.8  531.27  5071.3  540.03  5086.5  547.09  5106.6  552.52  5127.4  554.67
  5255.6  556.52    5315   557.4  5491.6  561.18  5740.2  568.55  5929.2  569.16
#Mann= 16 ,-1 , 0
  2430.9    .035       0  2849.9    .045       0  3095.4    .035       0
  3299.3     .07       0    3350    .035       0    3537     .07       0
  3592.7    .035       0  3697.9     .07       0  3748.9    .035       0
    4671     .07       0  4961.9     .12       0  4995.5     .05       0
  5047.8     .12       0  5086.5     .12       0  5255.6     .07       0
    5315     .05       0
Bank Sta=4995.5,5047.8
XS Rating Curve= 0 ,0
Exp/Cntr=0.3,0.1

Type RM Length L Ch R = 1 ,54621   ,545,545,545
BEGIN DESCRIPTION:
ALLIGATOR CREEK 67.0
END DESCRIPTION:
XS GIS Cut Line= 3
       2303800.1     13785185.03        2303025.       13783225.
      2302429.27     13782416.87
#Sta/Elev= 30
  2892.7  560.08    3022  559.11    3597  554.87  3771.6  553.09  3803.5  552.73
    4200  552.86    4257  553.91  4552.9  556.02  4685.4  549.88  4842.5   548.1
  4949.6  535.56  4961.2  535.28  4978.9  530.11  5017.1  530.05  5018.1  529.55
  5069.4  530.05  5072.5  535.52  5093.4  537.52    5108  544.41  5122.6  548.18
  5128.8  547.27  5144.3  552.87  5193.6  555.85  5316.1  556.97  5382.4  557.79
  5555.5  559.86  5715.7   563.2  5836.8  562.79  5894.9  567.88  6004.4  566.84
#Mann= 15 ,-1 , 0
  2892.7    .035       0    3022    .045       0    3597    .035       0
  3771.6     .07       0  3803.5    .035       0    4200     .07       0
    4257    .035       0  4842.5     .07       0  4949.6     .12       0
  5017.1     .05       0  5069.4     .12       0  5144.3      .1       0
  5316.1     .05       0  5382.4     .07       0  5555.5     .05       0
Bank Sta=5017.1,5069.4
XS Rating Curve= 0 ,0
Exp/Cntr=0.3,0.1

Type RM Length L Ch R = 1 ,54076   ,565,565,565
BEGIN DESCRIPTION:
ALLIGATOR CREEK 66.0
END DESCRIPTION:
XS GIS Cut Line= 3
      2304147.32     13784742.31        2303525.       13783275.
      2302645.62     13782363.88
#Sta/Elev= 30
  3406.2  559.76  3910.1  556.52  4013.1   555.6    4389  550.45  4413.5  548.84
  4421.3  542.16  4426.8  545.76  4435.2  539.97  4456.9  537.69  4474.1  543.89
  4497.8  544.85  4656.1   540.6  4703.4  543.39  4708.8  541.55  4803.5  541.99
  4879.2  539.47    4909  533.39  4961.8  533.06  4970.9  528.72    4972  528.12
  5023.7  528.72  5028.2  532.67  5056.5  532.96  5141.4     540  5189.7   547.2
  5265.3  551.58  5463.4  554.01  5612.3   555.4  6193.3  566.31  6266.3  566.38
#Mann= 12 ,-1 , 0
  3406.2    .035       0  3910.1     .07       0  4013.1    .035       0
    4389     .07       0  4879.2     .12       0  4970.9     .05       0
  5023.7     .12       0  5189.7      .1       0  5265.3     .12       0
  5463.4     .07       0  5612.3     .05       0  6193.3    .035       0
Bank Sta=4970.9,5023.7
XS Rating Curve= 0 ,0
Exp/Cntr=0.3,0.1

Type RM Length L Ch R = 1 ,53511   ,558,558,558
BEGIN DESCRIPTION:
ALLIGATOR CREEK 65.0
END DESCRIPTION:
XS GIS Cut Line= 3
      2304937.23     13783509.67        2303975.       13783025.
      2302689.77     13782260.15
#Sta/Elev= 30
    3918  560.99    4340  559.04  4457.1   557.3  4614.7  557.66  4655.6  556.46
  4749.1  555.92  4763.9  557.23  4808.6  554.36  4853.2  553.51  4875.5  550.69
  4914.5  543.01  4950.6   530.9  4981.5  528.65  4982.6  526.52  4983.6  525.92
  5035.5  526.52  5040.2  532.53  5053.6  535.95  5093.7  539.57  5264.1  545.94
    5319   549.3  5375.2  551.21  5513.7  552.14  5696.6  554.84  5784.1  557.34
  5798.3  556.45  6039.2  559.45  6263.8  564.86  6374.7  565.16    6491  566.02
#Mann= 10 ,-1 , 0
    3918    .045       0  4457.1    .035       0  4655.6     .12       0
  4982.6     .05       0  5035.5     .12       0  5093.7    .035       0
    5319     .12       0  5513.7     .07       0  5696.6     .05       0
  6374.7    .035       0
Bank Sta=4982.6,5035.5
XS Rating Curve= 0 ,0
Exp/Cntr=0.3,0.1

Type RM Length L Ch R = 1 ,52953   ,541,541,541
BEGIN DESCRIPTION:
ALLIGATOR CREEK 64.0
END DESCRIPTION:
XS GIS Cut Line= 3
      2305154.26     13782980.17        2304075.       13782525.
      2302846.02     13782129.73
#Sta/Elev= 30
  3828.6  560.59  4631.6  556.69  4697.7  555.48  4779.3  554.05  4806.9  552.31
  4826.3  549.52  4832.2  546.98  4855.9  541.61  4891.4  535.16  4956.2  528.05
  4967.4  528.63  4970.8  525.72  4971.8  525.12  5023.7  525.72  5031.4  530.76
    5035   531.5    5048  535.25  5075.6   539.9    5105  546.15  5117.5  547.61
    5189  548.68  5208.5  547.53    5231   549.7    5294  551.28  5485.5  553.05
  5808.9  558.91    5866  559.27  6009.3  563.35  6090.6  566.26  6290.9  566.99
#Mann= 9 ,-1 , 0
  3828.6    .045       0  4697.7     .12       0  4970.8     .05       0
  5023.7     .12       0    5035     .07       0  5075.6     .12       0
  5485.5    .035       0  5808.9     .05       0  6009.3    .035       0
Bank Sta=4970.8,5023.7
XS Rating Curve= 0 ,0
Exp/Cntr=0.3,0.1

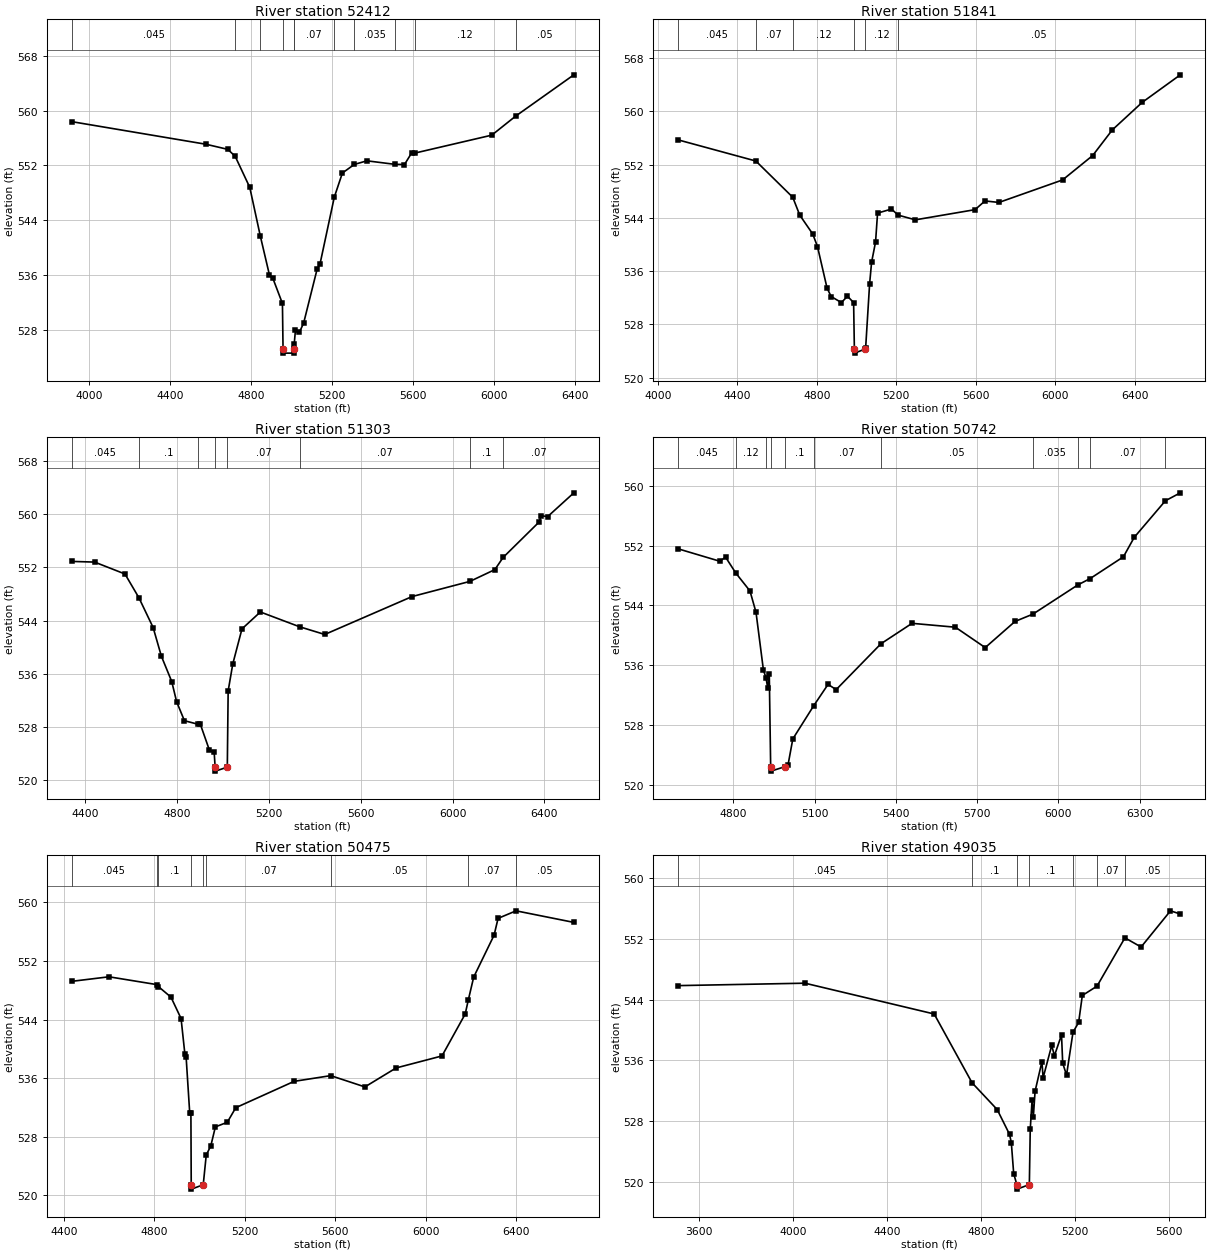
Type RM Length L Ch R = 1 ,52412   ,571,571,571
BEGIN DESCRIPTION:
ALLIGATOR CREEK 63.0
END DESCRIPTION:
XS GIS Cut Line= 3
      2305327.91     13782485.39        2304325.       13782075.
      2302940.73     13781912.46
#Sta/Elev= 30
  3916.4   558.4  4578.6   555.1  4686.7  554.35  4722.8  553.33  4794.7   548.8
  4846.6  541.71    4892  535.98  4907.9  535.58  4955.9  531.84  4958.9  525.19
  4959.9  524.59  5010.7  524.59  5011.8  525.19    5014  525.92  5020.2  527.98
  5039.1  527.61  5060.4  528.97  5127.3  536.89    5141  537.57  5211.7  547.36
  5251.7   550.9  5310.5  552.15  5372.6  552.68  5509.6  552.17  5558.1  552.14
  5594.1  553.86    5608   553.8    5989  556.43  6106.3   559.2  6393.8  565.24
#Mann= 11 ,-1 , 0
  3916.4    .045       0  4722.8     .07       0  4846.6     .12       0
  4958.9     .05       0  5011.8     .12       0    5014     .07       0
  5211.7     .05       0  5310.5    .035       0  5509.6     .05       0
    5608     .12       0  6106.3     .05       0
Bank Sta=4958.9,5011.8
XS Rating Curve= 0 ,0
Exp/Cntr=0.3,0.1

Type RM Length L Ch R = 1 ,51841   ,538,538,538
BEGIN DESCRIPTION:
ALLIGATOR CREEK 62.0
END DESCRIPTION:
XS GIS Cut Line= 3
      2305293.13     13781782.25        2304425.       13781575.
      2302793.19     13781513.16
#Sta/Elev= 30
  4102.9  555.71  4493.4  552.54  4678.9   547.1  4714.1  544.42  4779.5  541.58
  4803.4  539.69  4851.5  533.46  4872.1   532.2  4923.5  531.29  4954.3  532.24
  4985.1  531.29  4988.9   524.3    4990   523.7  5041.9   524.3  5045.5  524.44
  5065.5  534.08  5075.5  537.35  5095.5   540.4  5105.5  544.72  5175.6  545.33
  5208.9  544.42  5295.6  543.71  5595.9  545.24  5645.9  546.55  5715.9  546.32
  6036.2   549.7  6187.5  553.36  6286.3  557.21  6436.5  561.34  6628.4  565.48
#Mann= 6 ,-1 , 0
  4102.9    .045       0  4493.4     .07       0  4678.9     .12       0
  4988.9     .05       0  5041.9     .12       0  5208.9     .05       0
Bank Sta=4988.9,5041.9
XS Rating Curve= 0 ,0
Exp/Cntr=0.3,0.1

Type RM Length L Ch R = 1 ,51303   ,561,561,561
BEGIN DESCRIPTION:
ALLIGATOR CREEK 61.0
END DESCRIPTION:
XS GIS Cut Line= 3
      2305171.64     13781209.34        2304525.       13781075.
      2303001.54     13781113.85
#Sta/Elev= 30
  4343.5  552.89  4442.9  552.79    4575     551  4635.6  547.43  4697.5  542.95
  4733.4  538.64  4778.4  534.84  4799.7   531.8  4833.6  528.95  4891.3  528.43
  4901.8  528.52  4942.7  524.49  4963.1   524.2  4967.2  521.97  4968.3  521.37
  5020.2  521.97  5023.9  533.42    5044  537.48    5084  542.75    5164  545.29
  5334.5  543.07  5444.1  541.91  5824.2  547.61  6075.9  549.89  6184.3  551.66
    6220  553.48  6378.1  558.86  6384.4  559.75  6414.4  559.64  6527.9   563.2
#Mann= 8 ,-1 , 0
  4343.5    .045       0  4635.6      .1       0  4891.3     .07       0
  4967.2     .05       0  5020.2     .07       0  5334.5     .07       0
  6075.9      .1       0    6220     .07       0
Bank Sta=4967.2,5020.2
XS Rating Curve= 0 ,0
Exp/Cntr=0.3,0.1

Type RM Length L Ch R = 1 ,50742   ,267,267,267
BEGIN DESCRIPTION:
ALLIGATOR CREEK 60.0
END DESCRIPTION:
XS GIS Cut Line= 3
      2305125.01     13780875.01        2304775.       13780675.
      2303324.99       13780725.
#Sta/Elev= 30
  4596.5  551.56  4749.8  549.91  4771.4  550.45  4809.1  548.33  4861.4  545.94
  4883.7  543.09  4911.1  535.37  4920.6  534.35  4926.9  532.99  4932.7  534.88
  4937.8  522.49  4938.9  521.89  4990.9  522.49  5002.1  522.75  5019.6  526.19
  5096.4   530.6  5149.7  533.47  5179.7  532.77    5345  538.89  5459.9  541.62
    5620   541.1  5730.1  538.38  5840.1  541.87  5906.3  542.85  6071.8  546.74
  6117.8   547.6  6240.4   550.5  6280.4   553.1  6395.4  557.98  6450.5  559.04
#Mann= 11 ,-1 , 0
  4596.5    .045       0  4809.1     .12       0  4920.6      .1       0
  4937.8     .05       0  4990.9      .1       0  5096.4     .07       0
    5345     .05       0  5906.3    .035       0  6071.8     .05       0
  6117.8     .07       0  6395.4     .05       0
Bank Sta=4937.8,4990.9
XS Rating Curve= 0 ,0
Exp/Cntr=0.3,0.1

Type RM Length L Ch R = 1 ,50475   ,1440,1440,1440
BEGIN DESCRIPTION:
ALLIGATOR CREEK 59.0
END DESCRIPTION:
XS GIS Cut Line= 3
      2305284.48      13780645.1      2304815.73     13780410.73
      2303123.06     13780297.88
#Sta/Elev= 30
  4435.3  549.22    4600  549.84  4810.3  548.78  4818.2  548.51    4874  547.06
  4918.7  544.14  4935.4  539.33    4941   538.9    4957  531.21  4962.2  531.21
  4963.6  521.44  4964.7  520.84  5016.7  521.44    5030  525.49  5050.3  526.76
  5070.4  529.34  5123.1  529.97  5160.6  531.96  5418.7  535.56  5580.5  536.34
  5731.8   534.8  5869.7  537.39  6072.6  539.03  6175.4  544.76  6188.7  546.63
  6212.9   549.8  6303.1  555.53  6320.7  557.82  6400.2  558.85  6655.8  557.27
#Mann= 9 ,-1 , 0
  4435.3    .045       0  4810.3     .12       0  4818.2      .1       0
  4963.6     .05       0  5016.7      .1       0    5030     .07       0
  5580.5     .05       0  6188.7     .07       0  6400.2     .05       0
Bank Sta=4963.6,5016.7
XS Rating Curve= 0 ,0
Exp/Cntr=0.3,0.1

Type RM Length L Ch R = 1 ,49035   ,912,912,912
BEGIN DESCRIPTION:
ALLIGATOR CREEK 58.0
END DESCRIPTION:
XS GIS Cut Line= 4
      2305136.92     13780106.91      2304416.09     13779921.32
        2303675.       13779875.      2303044.87     13780028.79
#Sta/Elev= 30
  3512.7  545.85  4051.6  546.17  4601.3  542.11  4762.4  533.04  4869.3  529.51
  4921.9  526.24  4929.4  525.16  4939.5  521.06  4952.9  519.62    4954  519.02
  5006.1  519.62  5009.9  526.89  5017.8  530.81    5023  528.49  5030.5  531.93
  5059.5  535.81  5064.7   533.7  5101.2  537.96  5112.8  536.61  5142.9  539.35
    5148  535.63  5164.3  534.05  5191.8  539.71  5215.7  540.99  5231.4  544.55
  5293.9  545.78  5412.6  552.15  5481.4  550.94  5606.4  555.71  5648.2  555.29
#Mann= 7 ,-1 , 0
  3512.7    .045       0  4762.4      .1       0  4952.9     .05       0
  5006.1      .1       0  5191.8     .12       0  5293.9     .07       0
  5412.6     .05       0
Bank Sta=4952.9,5006.1
XS Rating Curve= 0 ,0
Exp/Cntr=0.3,0.1

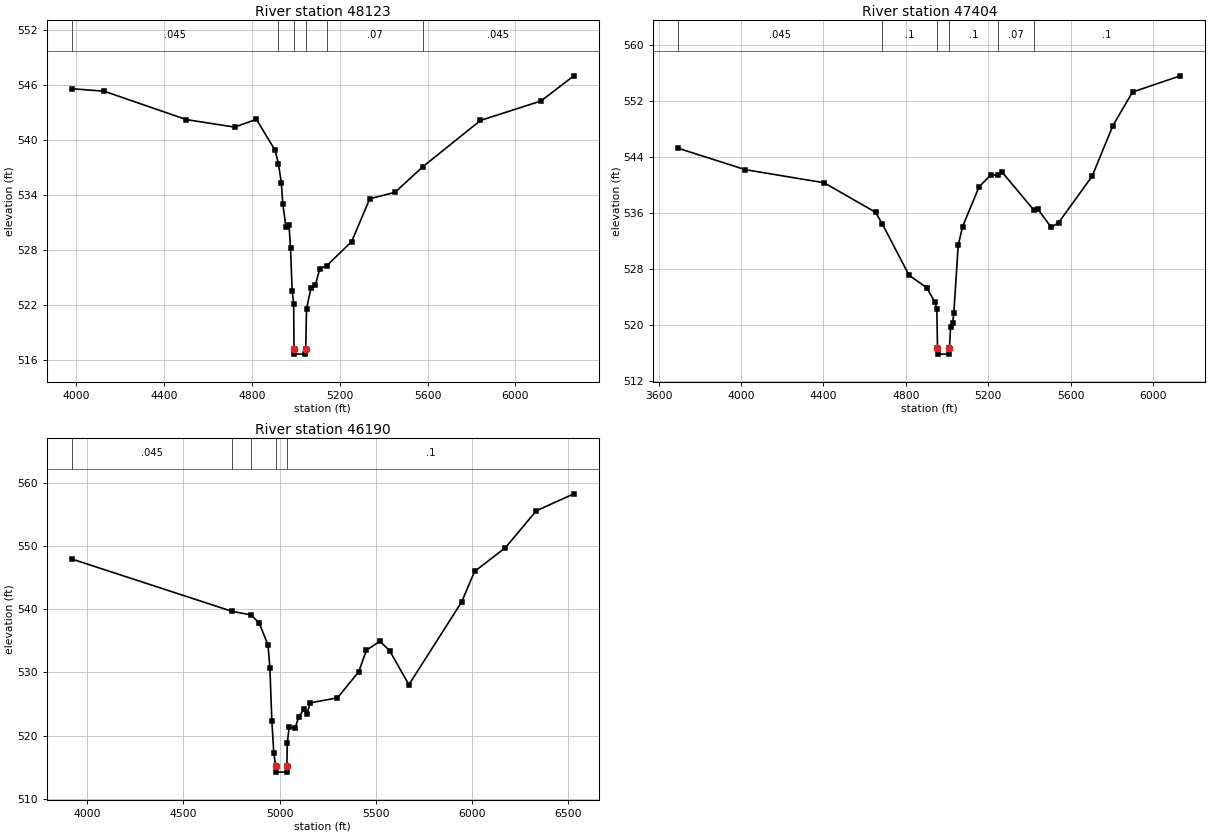
Type RM Length L Ch R = 1 ,48123   ,719,719,719
BEGIN DESCRIPTION:
ALLIGATOR CREEK 56.0
END DESCRIPTION:
XS GIS Cut Line= 3
      2304963.29     13779924.61      2304199.41     13779212.81
      2302966.73     13779360.39
#Sta/Elev= 30
  3980.5  545.62  4127.8  545.35  4502.5  542.24  4721.9  541.42  4821.1  542.27
  4906.1  538.88  4921.4  537.39  4934.4  535.33  4941.3     533  4955.4  530.51
  4969.6  530.68  4976.4  528.16  4983.8   523.5  4990.6  522.11  4992.3  517.19
  4993.4  516.59  5044.4  516.59  5045.5  517.19  5049.2  521.55  5069.3   523.8
  5089.8   524.2  5109.6  525.94  5141.6  526.27  5254.5   528.9  5336.9  533.58
  5452.1  534.29  5577.8  537.07    5841  542.15  6116.8  544.28  6266.1  547.03
#Mann= 6 ,-1 , 0
  3980.5    .045       0  4921.4      .1       0  4992.3     .05       0
  5045.5      .1       0  5141.6     .07       0  5577.8    .045       0
Bank Sta=4992.3,5045.5
XS Rating Curve= 0 ,0
Exp/Cntr=0.3,0.1

Type RM Length L Ch R = 1 ,47404   ,1214,1214,1214
BEGIN DESCRIPTION:
ALLIGATOR CREEK 55.0
END DESCRIPTION:
XS GIS Cut Line= 3
      2304971.99      13779855.2        2304525.       13778625.
       2303558.5     13778041.81
#Sta/Elev= 30
  3695.4  545.26  4021.7   542.2  4403.6  540.33  4653.2  536.11  4686.9   534.4
    4816   527.1  4902.5   525.3  4940.4   523.3  4951.1  522.32  4954.1  516.71
  4955.4  515.81  5010.6  515.81    5012  516.71  5017.9  519.71  5027.6  520.21
  5033.4   521.7  5054.8  531.39  5076.1  534.07  5156.1  539.75  5214.5   541.5
    5246  541.37  5266.3  541.91  5421.5  536.43    5441  536.57  5506.5  533.95
    5542  534.61    5705  541.27  5805.9  548.51  5901.1  553.31  6133.1  555.63
#Mann= 6 ,-1 , 0
  3695.4    .045       0  4686.9      .1       0  4954.1     .05       0
    5012      .1       0    5246     .07       0  5421.5      .1       0
Bank Sta=4954.1,5012
XS Rating Curve= 0 ,0
Exp/Cntr=0.3,0.1

Type RM Length L Ch R = 1 ,46190   ,1084,1084,1084
BEGIN DESCRIPTION:
ALLIGATOR CREEK 54.0
END DESCRIPTION:
XS GIS Cut Line= 3
      2306152.54     13777928.09      2305162.95     13777858.64
      2303550.63     13777719.95
#Sta/Elev= 30
  3919.9     548    4753   539.7  4851.6  539.13  4893.7  537.88    4940  534.38
    4950  530.73  4960.1  522.31  4970.1   517.3  4979.9  515.09  4981.2  514.19
  5036.8  514.19  5038.2  515.09  5040.4  518.81  5050.4  521.39  5080.5  521.12
  5100.6  523.01  5127.6  524.17  5140.7  523.38  5160.8  525.18  5301.3  525.98
  5411.7  530.11  5451.9  533.53  5522.1  534.95  5572.3  533.46  5672.7  528.06
  5947.5  541.22  6013.9  546.02  6174.5   549.8  6335.1  555.65  6530.2  558.34
#Mann= 5 ,-1 , 0
  3919.9    .045       0    4753     .07       0  4851.6      .1       0
  4979.9     .05       0  5038.2      .1       0
Bank Sta=4979.9,5038.2
XS Rating Curve= 0 ,0
Exp/Cntr=0.3,0.1