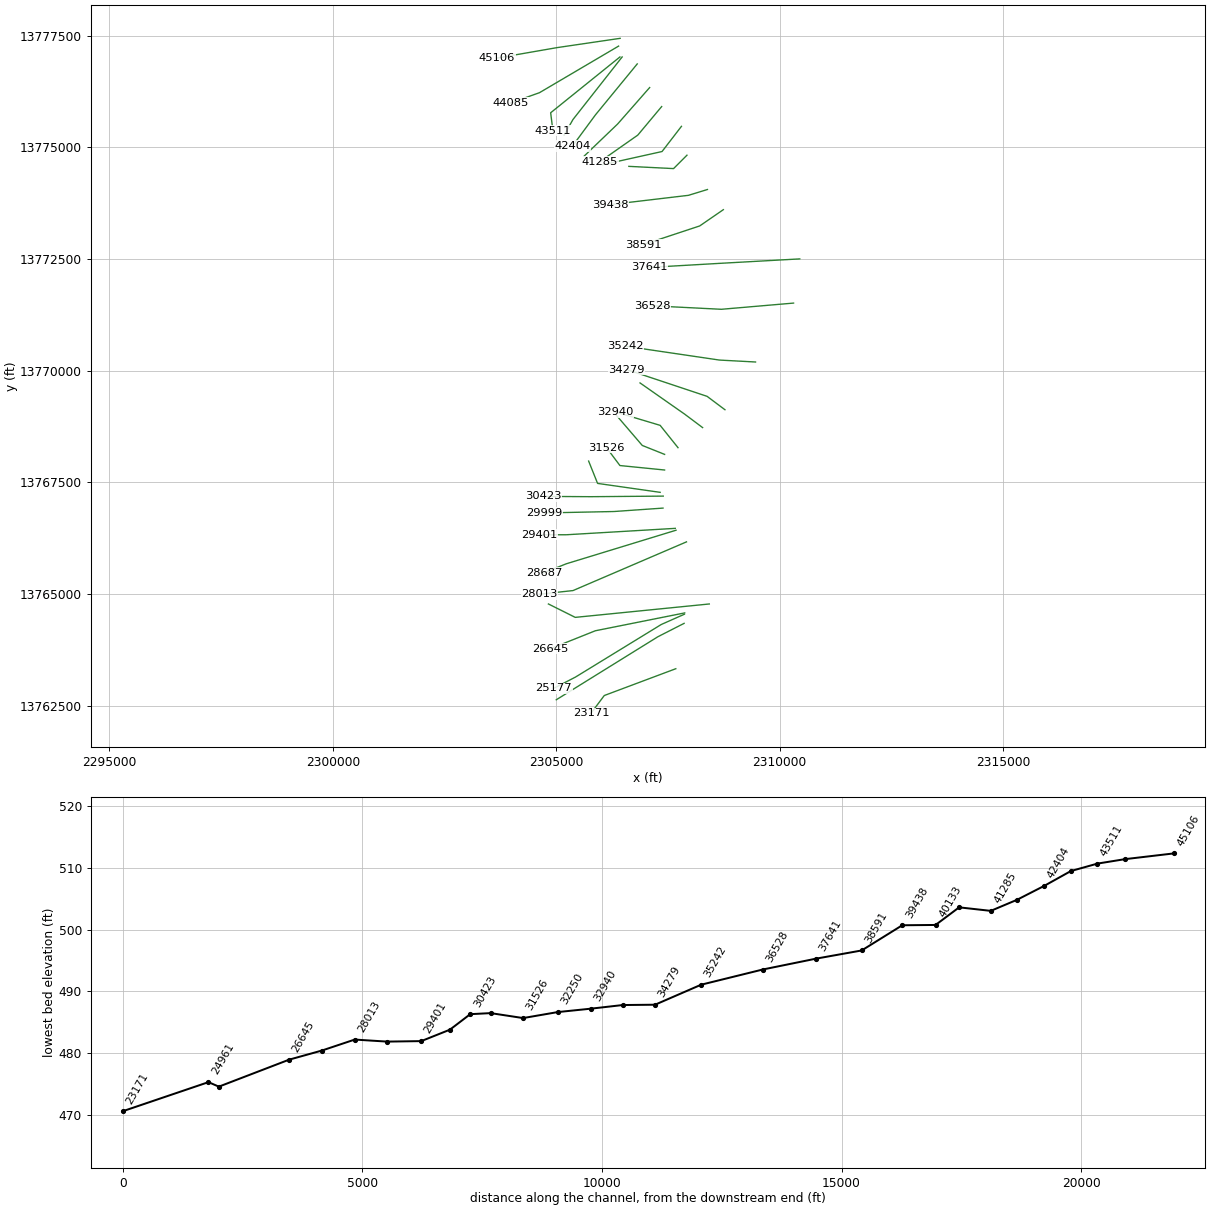
HEC-RAS study GERONIMO CREEK.prj: GERONIMO CREEK Base Level Engineering

--- GERONIMO CREEK.g01 (geometry) --- (continued)

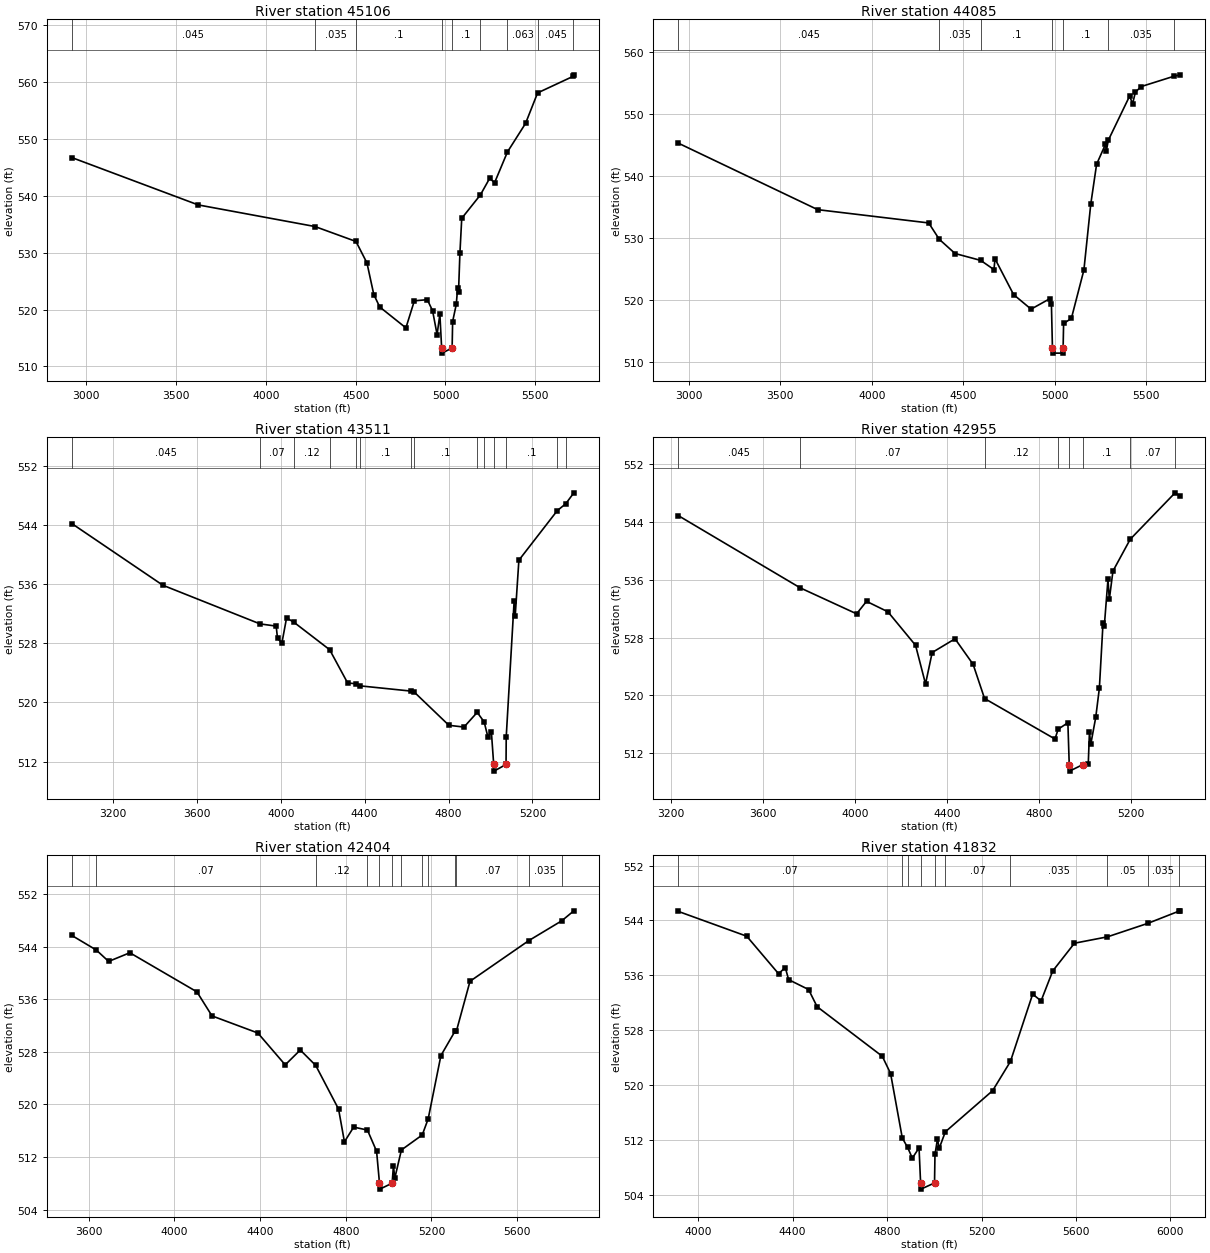
Type RM Length L Ch R = 1 ,45106   ,1021,1021,1021
BEGIN DESCRIPTION:
ALLIGATOR CREEK 53.0
END DESCRIPTION:
XS GIS Cut Line= 3
      2306430.36     13777441.98      2305015.38     13777233.64
      2303669.97     13776999.28
#Sta/Elev= 30
  2918.9  546.75  3622.9  538.42  4272.9  534.62  4501.6  531.99  4562.7  528.21
  4600.8  522.66  4633.7  520.47  4779.6  516.79  4826.6  521.55  4898.8  521.75
  4928.1  519.81  4953.3  515.61  4968.7   519.2  4978.6  513.25    4980  512.35
    5037  513.25  5039.8  517.91  5060.1  520.93  5067.4  523.72  5072.5  523.02
  5080.4  529.97  5090.5  536.06  5194.2  540.17  5246.1   543.1  5273.2  542.31
  5345.1  547.74  5445.8  552.75  5512.9  558.12  5711.8  561.05  5714.8   561.3
#Mann= 9 ,-1 , 0
  2918.9    .045       0  4272.9    .035       0  4501.6      .1       0
  4978.6     .05       0    5037      .1       0  5194.2    .035       0
  5345.1    .063       0  5512.9    .045       0  5711.8     .07       0
Bank Sta=4978.6,5037
XS Rating Curve= 0 ,0
Exp/Cntr=0.3,0.1

Type RM Length L Ch R = 1 ,44085   ,574,574,574
BEGIN DESCRIPTION:
ALLIGATOR CREEK 52.0
END DESCRIPTION:
XS GIS Cut Line= 3
       2306395.6     13777268.37        2304625.       13776225.
      2303973.76     13775992.34
#Sta/Elev= 30
    2941  545.28    3704  534.55  4311.1  532.41  4369.1  529.77  4455.4  527.48
  4595.7  526.37  4668.2  524.89    4674  526.63  4775.6  520.86  4871.2  518.51
  4972.9  520.18  4982.5  519.39  4988.1  512.32  4989.5  511.42  5045.2  511.42
  5046.6  512.32  5049.2   516.2  5091.7  517.01  5160.2  524.81  5197.9  535.46
  5229.8  541.88    5278  545.07  5283.3  544.07  5293.9  545.75  5410.3  552.86
  5426.7  551.63  5442.1  553.51    5474   554.4  5654.8  556.08  5687.7  556.29
#Mann= 7 ,-1 , 0
    2941    .045       0  4369.1    .035       0  4595.7      .1       0
  4988.1     .05       0  5046.6      .1       0  5293.9    .035       0
  5654.8     .07       0
Bank Sta=4988.1,5046.6
XS Rating Curve= 0 ,0
Exp/Cntr=0.3,0.1

Type RM Length L Ch R = 1 ,43511   ,556,556,556
BEGIN DESCRIPTION:
ALLIGATOR CREEK 51.0
END DESCRIPTION:
XS GIS Cut Line= 3
      2306425.01     13777025.01        2304875.       13775775.
        2304925.     13775374.96
#Sta/Elev= 30
  3003.3  544.25  3437.5  535.89    3901  530.65  3978.1  530.35  3984.5   528.7
  4005.4  528.06  4027.7  531.46  4063.8  530.85  4233.2  527.15  4318.8  522.65
  4356.8  522.54  4376.3  522.26  4622.7  521.54    4634  521.48  4801.8  516.91
  4873.8  516.67  4936.8  518.66    4970  517.37  4987.4  515.37  5004.6  515.94
  5015.5   511.6  5016.9   510.7  5074.3   511.6  5075.2  515.35    5113  533.77
    5118  531.71  5135.6  539.28  5318.8     546  5359.1  546.93  5397.7  548.41
#Mann= 14 ,-1 , 0
  3003.3    .045       0    3901     .07       0  4063.8     .12       0
  4233.2     .07       0  4356.8     .12       0  4376.3      .1       0
  4622.7     .12       0    4634      .1       0  4936.8     .12       0
    4970      .1       0  5015.5     .05       0  5074.3      .1       0
  5318.8     .07       0  5359.1    .035       0
Bank Sta=5015.5,5074.3
XS Rating Curve= 0 ,0
Exp/Cntr=0.3,0.1

Type RM Length L Ch R = 1 ,42955   ,551,551,551
BEGIN DESCRIPTION:
ALLIGATOR CREEK 50.0
END DESCRIPTION:
XS GIS Cut Line= 3
        2306475.     13777025.01        2305375.       13775625.
      2305174.98     13775274.97
#Sta/Elev= 30
  3231.3  544.89  3762.2  534.87  4007.1  531.28  4050.1  533.01  4143.2  531.56
  4263.4  526.92  4306.8  521.57  4335.7  525.92  4435.1  527.82  4513.8  524.28
  4563.5  519.55  4869.8  513.94  4883.7   515.3  4925.9  516.19  4931.8  510.39
  4933.2  509.49  4990.6  510.39  5014.6  510.49  5019.7   514.9  5025.4  513.21
    5047  516.92  5062.9  520.99  5078.7  529.97  5084.5  529.65  5100.3  536.07
  5106.1  533.27  5121.9   537.2  5197.1  541.61  5392.1  548.04  5414.9  547.57
#Mann= 8 ,-1 , 0
  3231.3    .045       0  3762.2     .07       0  4563.5     .12       0
  4883.7      .1       0  4931.8     .05       0  4990.6      .1       0
  5197.1     .07       0  5392.1    .035       0
Bank Sta=4931.8,4990.6
XS Rating Curve= 0 ,0
Exp/Cntr=0.3,0.1

Type RM Length L Ch R = 1 ,42404   ,572,572,572
BEGIN DESCRIPTION:
ALLIGATOR CREEK 49.0
END DESCRIPTION:
XS GIS Cut Line= 3
      2306812.23     13776869.03        2305875.       13775725.
      2305363.06      13775029.4
#Sta/Elev= 30
  3521.6  545.72  3636.2  543.49  3693.6  541.76  3792.6  543.08  4105.5  537.13
  4175.9  533.47  4389.7  530.87  4517.5  526.02  4587.8  528.28  4659.9  525.93
  4766.5  519.28  4793.8  514.31  4836.9  516.55  4901.1   516.1  4943.8  512.88
  4957.4  508.01  4958.9  507.11  5016.3  508.01  5022.5  510.67  5028.7  508.77
  5059.6  513.07  5156.8  515.35  5184.6  517.81  5243.9  527.43  5309.5  531.13
  5316.6   531.2  5379.7  538.74  5654.1  544.93  5807.7  547.94  5864.2  549.46
#Mann= 13 ,-1 , 0
  3521.6    .045       0  3636.2     .07       0  4659.9     .12       0
  4901.1      .1       0  4957.4     .05       0  5016.3      .1       0
  5059.6     .12       0  5156.8      .1       0  5184.6     .12       0
  5309.5    .035       0  5316.6     .07       0  5654.1    .035       0
  5807.7     .05       0
Bank Sta=4957.4,5016.3
XS Rating Curve= 0 ,0
Exp/Cntr=0.3,0.1

Type RM Length L Ch R = 1 ,41832   ,547,547,547
BEGIN DESCRIPTION:
ALLIGATOR CREEK 48.0
END DESCRIPTION:
XS GIS Cut Line= 3
      2307090.04     13776339.55        2306375.       13775525.
      2305623.01     13774803.08
#Sta/Elev= 30
  3915.5  545.32  4205.6   541.7  4340.4  536.23  4368.8  537.14    4383  535.37
  4467.5  533.93  4503.6  531.43  4779.7   524.2  4814.8  521.69  4864.4  512.29
  4886.9  510.92  4906.9  509.36  4935.3  510.85  4941.9  505.74  4943.3  504.84
  5000.9  505.74  5002.8   509.9  5013.4  512.16  5020.6  510.77  5046.6  513.19
    5247  519.19  5322.4  523.45  5416.5  533.26  5452.1  532.27  5501.4  536.63
  5593.6  540.68  5733.3  541.61  5904.7  543.58  6034.2  545.33  6041.8   545.4
#Mann= 10 ,-1 , 0
  3915.5     .07       0  4864.4     .12       0  4886.9      .1       0
  4941.9     .05       0  5000.9      .1       0  5046.6     .07       0
  5322.4    .035       0  5733.3     .05       0  5904.7    .035       0
  6034.2     .05       0
Bank Sta=4941.9,5000.9
XS Rating Curve= 0 ,0
Exp/Cntr=0.3,0.1

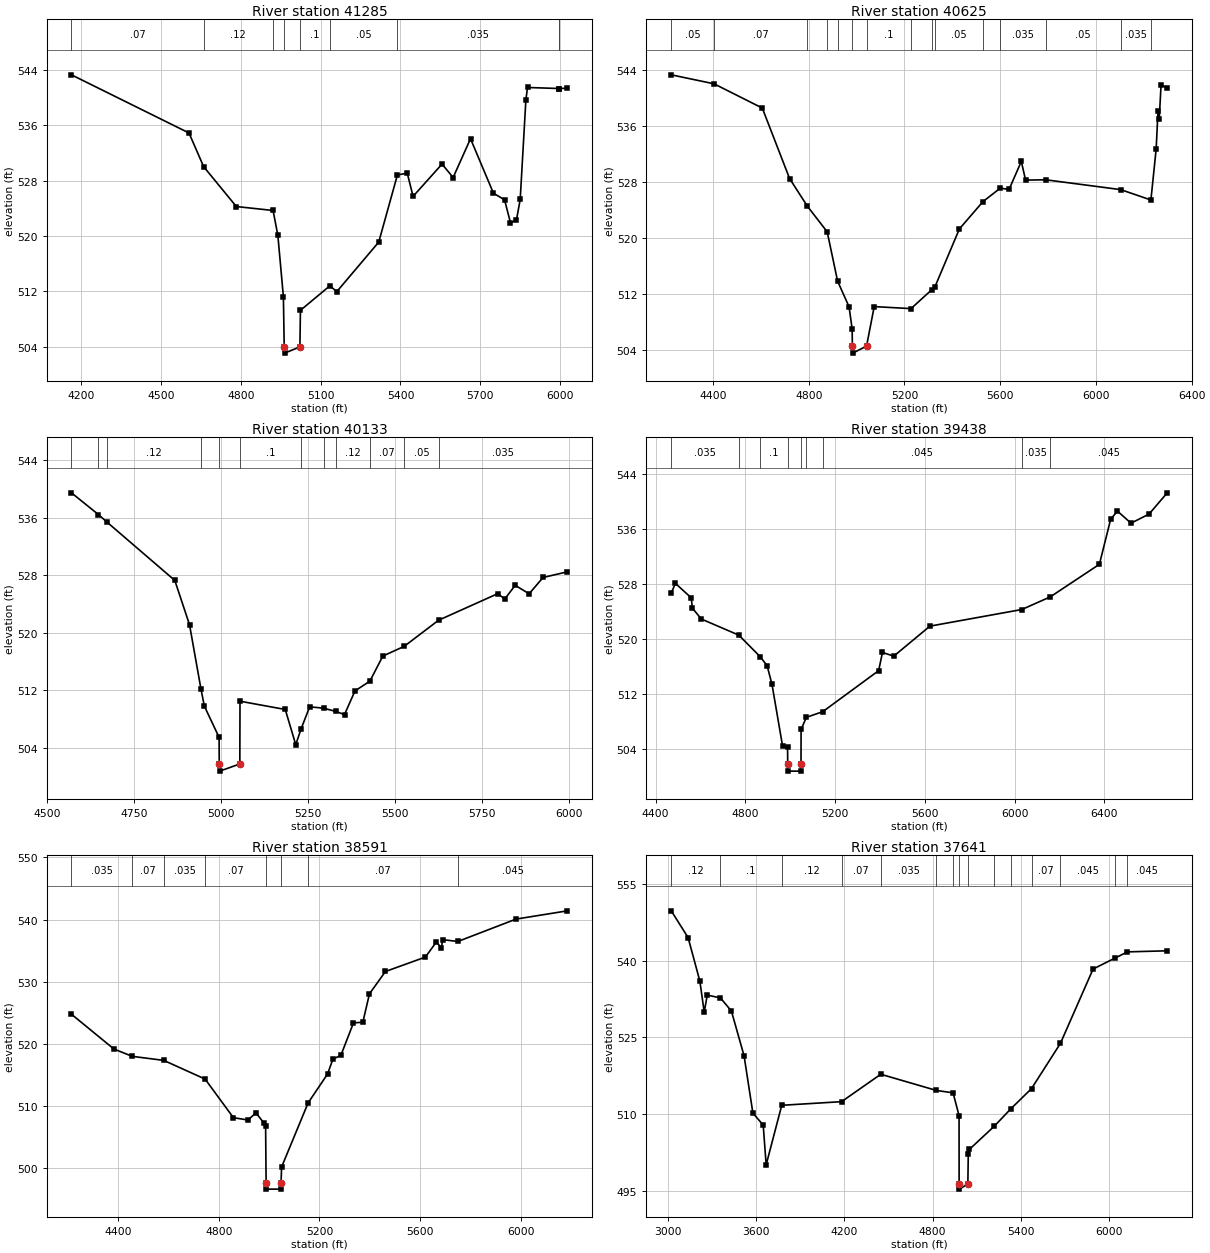
Type RM Length L Ch R = 1 ,41285   ,660,660,660
BEGIN DESCRIPTION:
ALLIGATOR CREEK 47.0
END DESCRIPTION:
XS GIS Cut Line= 3
      2307359.15     13775914.22        2306825.       13775275.
      2305979.47     13774681.94
#Sta/Elev= 30
  4162.5   543.3  4604.6  534.89  4659.7  530.02  4782.7  524.25  4920.9  523.68
  4938.9  520.07  4959.7  511.21  4962.8  503.95  4964.2  503.05  5021.8  503.95
  5023.8  509.24  5134.4  512.78  5160.7  511.95  5318.4  519.11  5388.6  528.82
  5425.7  529.07  5447.5  525.72  5556.4  530.39  5598.2  528.45  5663.6  534.06
  5749.9  526.18  5791.7  525.22  5813.9  521.91  5836.2  522.27  5850.5  525.27
  5871.9  539.69    5878  541.47  5996.1  541.32  5998.2  541.32  6028.3  541.37
#Mann= 9 ,-1 , 0
  4162.5     .07       0  4659.7     .12       0  4920.9      .1       0
  4962.8     .05       0  5021.8      .1       0  5134.4     .05       0
  5388.6    .035       0  5996.1     .05       0  5998.2    .035       0
Bank Sta=4962.8,5021.8
XS Rating Curve= 0 ,0
Exp/Cntr=0.3,0.1

Type RM Length L Ch R = 1 ,40625   ,492,492,492
BEGIN DESCRIPTION:
ALLIGATOR CREEK 46.0
END DESCRIPTION:
XS GIS Cut Line= 3
      2307801.81     13775471.45      2307367.81     13774907.26
      2306039.82     13774612.15
#Sta/Elev= 30
  4225.8  543.33  4404.4  542.05  4606.1  538.59  4720.2  528.53  4794.6  524.58
  4877.3  520.93  4920.8  513.89  4968.6  510.24  4981.5  507.08  4982.5  504.62
    4984  503.62  5041.7  504.62  5073.7  510.26  5227.5  509.97  5313.4  512.64
  5327.7   513.1  5429.6  521.34  5528.1  525.24  5600.5  527.16  5637.1  526.97
  5688.3  530.98  5706.1  528.31  5790.8  528.35  6103.6  526.95  6229.7  525.47
  6251.7  532.76  6259.3  538.13  6264.4  536.99  6272.2  541.91    6298  541.43
#Mann= 15 ,-1 , 0
  4225.8     .05       0  4404.4     .07       0  4794.6     .12       0
  4877.3     .07       0  4920.8      .1       0  4982.5     .05       0
  5041.7      .1       0  5227.5     .07       0  5313.4      .1       0
  5327.7     .05       0  5528.1     .07       0  5600.5    .035       0
  5790.8     .05       0  6103.6    .035       0  6229.7     .05       0
Bank Sta=4982.5,5041.7
XS Rating Curve= 0 ,0
Exp/Cntr=0.3,0.1

Type RM Length L Ch R = 1 ,40133   ,695,695,695
BEGIN DESCRIPTION:
ALLIGATOR CREEK 45.0
END DESCRIPTION:
XS GIS Cut Line= 3
      2307925.03     13774825.03        2307625.       13774525.
      2306624.95       13774575.
#Sta/Elev= 30
  4570.8   539.5  4648.2  536.48  4673.5   535.4  4867.8  527.31  4910.2  521.13
    4943   512.2  4952.7  509.82  4995.1  505.47  4995.5  501.77    4997  500.77
  5054.7  501.77  5055.2   510.5  5185.3  509.35  5215.4  504.45    5231  506.67
  5255.4  509.72  5295.4  509.53  5329.8  509.09  5355.6  508.64  5385.6  511.93
  5428.5  513.29  5465.7  516.78  5527.3  518.14    5626  521.77  5796.1  525.47
  5816.1  524.72  5846.2  526.63  5886.2  525.45  5926.3  527.72  5996.4  528.51
#Mann= 12 ,-1 , 0
  4570.8     .05       0  4648.2     .07       0  4673.5     .12       0
    4943      .1       0  4995.5     .05       0  5054.7      .1       0
    5231     .12       0  5295.4      .1       0  5329.8     .12       0
  5428.5     .07       0  5527.3     .05       0    5626    .035       0
Bank Sta=4995.5,5054.7
XS Rating Curve= 0 ,0
Exp/Cntr=0.3,0.1

Type RM Length L Ch R = 1 ,39438   ,847,847,847
BEGIN DESCRIPTION:
ALLIGATOR CREEK 44.0
END DESCRIPTION:
XS GIS Cut Line= 3
      2308383.47     13774056.57      2307958.09     13773926.35
      2306204.59     13773718.02
#Sta/Elev= 30
  4469.7  526.64    4488  528.06  4558.7  525.96    4564  524.44  4604.1  522.86
  4770.9  520.52  4865.5   517.4  4896.9  516.07  4918.6  513.37  4965.7  504.41
  4988.2  504.27  4988.7  501.72  4990.2  500.72  5046.5  500.72    5048  501.72
  5048.4  506.79  5071.9  508.55  5145.1  509.38  5394.1  515.35  5411.1     518
  5461.5  517.46  5622.6  521.83  6032.1  524.25    6159  526.09  6377.9  530.83
  6428.2  537.39  6458.4  538.58  6518.9  536.82  6599.4  538.15  6680.4  541.24
#Mann= 9 ,-1 , 0
  4469.7    .035       0  4770.9     .07       0  4865.5      .1       0
  4988.7     .05       0    5048      .1       0  5071.9    .035       0
  5145.1    .045       0  6032.1    .035       0    6159    .045       0
Bank Sta=4988.7,5048
XS Rating Curve= 0 ,0
Exp/Cntr=0.3,0.1

Type RM Length L Ch R = 1 ,38591   ,950,950,950
BEGIN DESCRIPTION:
ALLIGATOR CREEK 43.0
END DESCRIPTION:
XS GIS Cut Line= 3
      2308739.33     13773605.16      2308209.83     13773240.59
      2306951.17     13772823.93
#Sta/Elev= 30
  4215.6  524.77  4384.1  519.18  4456.9     518  4581.9  517.35  4746.1  514.34
  4858.4  508.13  4916.2  507.76  4947.8  508.91  4979.4  507.28  4986.2  506.79
  4988.2  497.64  4989.7  496.64  5046.1  496.64  5047.5  497.64  5049.6  500.19
  5154.9  510.51  5232.2  515.17  5253.3  517.56  5284.9  518.16    5335  523.39
    5372  523.48  5398.4  528.06  5461.8  531.65  5620.4  533.97  5664.1  536.41
  5683.8  535.44  5689.1  536.77  5749.3  536.48  5980.1  540.08  6184.3  541.41
#Mann= 8 ,-1 , 0
  4215.6    .035       0  4456.9     .07       0  4581.9    .035       0
  4746.1     .07       0  4988.2     .05       0  5047.5     .07       0
  5154.9     .07       0  5749.3    .045       0
Bank Sta=4988.2,5047.5
XS Rating Curve= 0 ,0
Exp/Cntr=0.3,0.1

Type RM Length L Ch R = 1 ,37641   ,1113,1113,1113
BEGIN DESCRIPTION:
ALLIGATOR CREEK 42.0
END DESCRIPTION:
XS GIS Cut Line= 3
      2310449.45     13772502.74      2308583.09     13772398.58
      2307081.36     13772311.77
#Sta/Elev= 30
  3023.1  549.76  3137.7  544.53  3217.9  535.99  3247.3  529.94  3267.9  533.28
  3357.8  532.72  3432.2  530.16  3518.3  521.41  3578.4  510.19  3648.5  507.85
  3668.6  500.08  3774.6  511.72  4181.5  512.43  4448.3  517.79  4826.8  514.62
  4939.7  514.16  4980.6  509.71    4981  496.32  4982.4  495.32  5040.4  496.32
  5043.3  502.22  5050.7  503.09  5219.8  507.62  5333.7  511.06  5473.3  514.98
  5669.9  523.83  5892.1  538.37  6037.9  540.47  6126.2  541.73  6396.6  541.94
#Mann= 15 ,-1 , 0
  3023.1     .12       0  3357.8      .1       0  3774.6     .12       0
  4181.5     .07       0  4448.3    .035       0  4826.8     .07       0
  4939.7      .1       0    4981     .05       0  5040.4      .1       0
  5219.8     .07       0  5333.7    .045       0  5473.3     .07       0
  5669.9    .045       0  6037.9    .035       0  6126.2    .045       0
Bank Sta=4981,5040.4
XS Rating Curve= 0 ,0
Exp/Cntr=0.3,0.1

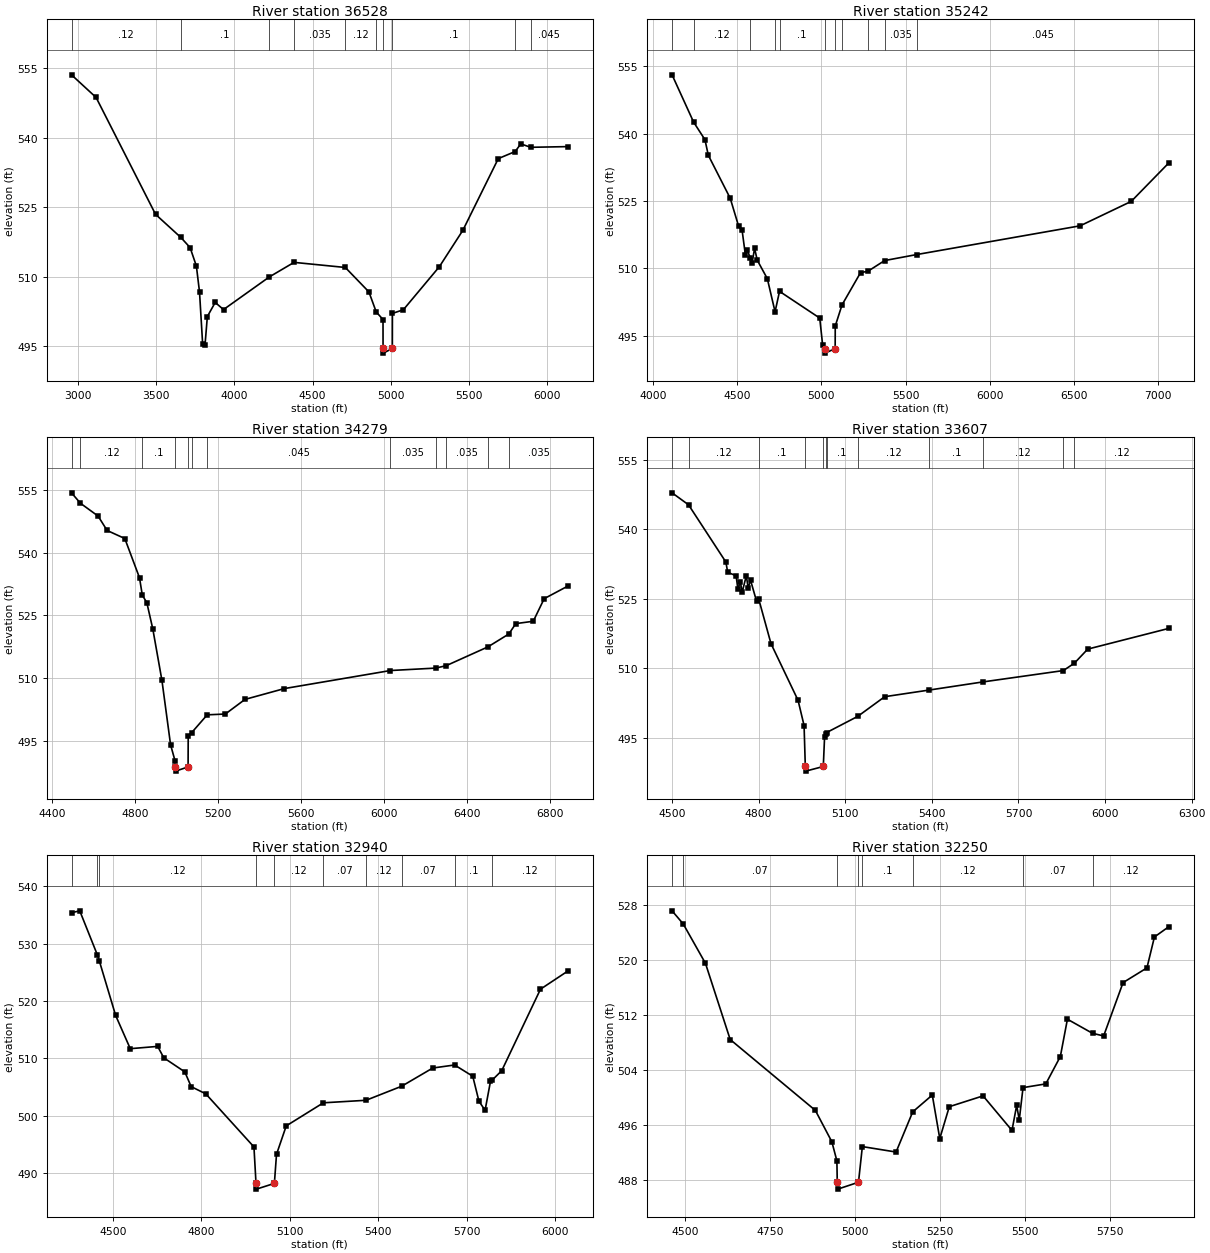
Type RM Length L Ch R = 1 ,36528   ,1286,1286,1286
BEGIN DESCRIPTION:
ALLIGATOR CREEK 41.0
END DESCRIPTION:
XS GIS Cut Line= 3
      2310310.54     13771513.16      2308695.94     13771374.27
      2307142.17     13771452.39
#Sta/Elev= 30
  2957.7  553.54    3115  548.66  3495.2  523.47    3657  518.49    3716  516.31
  3756.2  512.34  3776.3  506.75  3796.3  495.51  3811.4  495.27  3826.4  501.45
  3876.6  504.48  3929.9  502.95  4223.1  509.99  4380.9  513.12  4708.7  512.02
  4859.6  506.75  4906.2  502.44  4949.7   500.8    4950  494.56  4951.5  493.56
  5009.4  494.56  5009.8  502.12  5079.8  502.91  5310.1  512.19  5460.3  520.03
  5686.8  535.48  5794.9  537.01  5830.8  538.66  5893.7  537.92    6134  538.07
#Mann= 10 ,-1 , 0
  2957.7     .12       0    3657      .1       0  4223.1     .07       0
  4380.9    .035       0  4708.7     .12       0  4906.2      .1       0
    4950     .05       0  5009.4      .1       0  5794.9    .035       0
  5893.7    .045       0
Bank Sta=4950,5009.4
XS Rating Curve= 0 ,0
Exp/Cntr=0.3,0.1

Type RM Length L Ch R = 1 ,35242   ,963,963,963
BEGIN DESCRIPTION:
ALLIGATOR CREEK 40.0
END DESCRIPTION:
XS GIS Cut Line= 3
      2309459.87     13770193.71      2308652.54     13770237.12
      2306534.47     13770549.62
#Sta/Elev= 30
  4113.4  553.09  4241.3  542.56  4308.6  538.65  4328.6  535.18  4458.8  525.59
  4508.8  519.35  4528.9  518.56  4548.9  512.95  4558.9  514.15  4576.8   512.4
    4589  511.26  4603.5  514.45    4619  511.82  4679.1  507.68    4725  500.31
  4751.5  504.86  4990.2  498.91  5007.7  492.85  5019.7   492.1  5021.2   491.1
  5081.9   492.1  5082.4  497.14  5122.7  501.85  5232.8  509.04  5275.8  509.32
  5375.7  511.72  5566.5  513.06  6536.7  519.46    6840   524.9  7062.9  533.46
#Mann= 11 ,-1 , 0
  4113.4     .07       0  4241.3     .12       0  4576.8      .1       0
    4725     .12       0  4751.5      .1       0  5019.7     .05       0
  5081.9      .1       0  5122.7     .12       0  5275.8     .07       0
  5375.7    .035       0  5566.5    .045       0
Bank Sta=5019.7,5081.9
XS Rating Curve= 0 ,0
Exp/Cntr=0.3,0.1

Type RM Length L Ch R = 1 ,34279   ,672,672,672
BEGIN DESCRIPTION:
ALLIGATOR CREEK 39.0
END DESCRIPTION:
XS GIS Cut Line= 3
      2308775.02     13769124.98        2308375.       13769425.
      2306574.99       13770025.
#Sta/Elev= 30
  4492.6  554.25  4535.8  551.76  4620.8  548.71  4664.5  545.27  4749.9  543.35
  4820.8  533.99  4834.3  529.85  4856.2  528.04  4885.3   521.7  4929.1  509.49
  4970.8  494.14  4992.6  490.27  4993.1  488.86  4994.6  487.86  5055.3  488.86
  5055.9  496.23  5072.6  497.04  5147.6  501.29  5235.1  501.48  5329.9  504.97
  5519.7  507.55  6032.2  511.86  6250.3  512.44  6300.8  513.01  6502.5   517.5
  6603.3  520.57    6637  523.05  6721.3  523.61    6774     529    6890  532.05
#Mann= 12 ,-1 , 0
  4492.6     .07       0  4535.8     .12       0  4834.3      .1       0
  4993.1     .05       0  5055.3      .1       0  5072.6     .07       0
  5147.6    .045       0  6032.2    .035       0  6250.3    .045       0
  6300.8    .035       0  6502.5    .045       0  6603.3    .035       0
Bank Sta=4993.1,5055.3
XS Rating Curve= 0 ,0
Exp/Cntr=0.3,0.1

Type RM Length L Ch R = 1 ,33607   ,667,667,667
BEGIN DESCRIPTION:
ALLIGATOR CREEK 38.0
END DESCRIPTION:
XS GIS Cut Line= 3
        2308275.       13768725.        2307875.       13769025.
      2306874.96     13769725.02
#Sta/Elev= 30
    4500  547.89    4557  545.31  4686.5  532.94  4692.7  530.73  4721.9  529.99
  4728.1  527.05  4736.5  528.71  4742.7  526.41  4757.3     530  4763.5  527.38
  4771.9  529.01  4792.7  524.49  4800.3  524.93  4842.7  515.33  4936.5  503.09
  4957.3  497.66  4961.6  488.81  4963.1  487.81  5023.9  488.81  5028.3  495.13
  5032.9   495.8  5035.2  496.13  5143.2  499.63  5236.7  503.88  5391.4  505.32
  5578.2  507.08  5855.5  509.52  5893.7  511.11  5939.9  514.15  6220.7  518.62
#Mann= 12 ,-1 , 0
    4500    .035       0    4557     .12       0  4800.3      .1       0
  4961.6     .05       0  5023.9      .1       0  5032.9     .12       0
  5035.2      .1       0  5143.2     .12       0  5391.4      .1       0
  5578.2     .12       0  5855.5      .1       0  5893.7     .12       0
Bank Sta=4961.6,5023.9
XS Rating Curve= 0 ,0
Exp/Cntr=0.3,0.1

Type RM Length L Ch R = 1 ,32940   ,690,690,690
BEGIN DESCRIPTION:
ALLIGATOR CREEK 37.0
END DESCRIPTION:
XS GIS Cut Line= 3
      2307725.02     13768274.98        2307325.       13768775.
      2306324.97     13769075.01
#Sta/Elev= 30
  4359.9  535.38  4387.9  535.71  4447.2  528.08  4454.5  526.94  4509.6  517.48
  4559.2  511.69  4652.1  512.09  4672.9   510.1  4744.1  507.65  4765.7  505.08
  4815.3  503.82  4978.6  494.57  4985.6  488.22  4987.1  487.22  5047.9  488.22
  5055.1  493.28  5088.1  498.24    5214  502.26  5358.6   502.7  5479.6  505.15
  5584.9  508.32    5659  508.85  5720.6  506.89  5741.5  502.55  5762.4  500.95
  5780.7     506  5787.1  506.25  5818.9  507.86  5950.3  522.06  6044.3  525.26
#Mann= 10 ,-1 , 0
  4359.9     .12       0  4447.2     .07       0  4454.5     .12       0
  4985.6     .05       0  5047.9     .12       0    5214     .07       0
  5358.6     .12       0  5479.6     .07       0    5659      .1       0
  5787.1     .12       0
Bank Sta=4985.6,5047.9
XS Rating Curve= 0 ,0
Exp/Cntr=0.3,0.1

Type RM Length L Ch R = 1 ,32250   ,724,724,724
BEGIN DESCRIPTION:
ALLIGATOR CREEK 36.0
END DESCRIPTION:
XS GIS Cut Line= 3
      2307424.95     13768125.02        2306925.       13768325.
      2306325.01     13769024.98
#Sta/Elev= 30
  4462.1  527.11    4495   525.2  4560.3  519.48    4633  508.41  4883.4  498.11
  4931.9  493.55  4946.7  490.78  4947.8  487.67  4949.3  486.67  5010.2  487.67
  5021.6  492.85  5120.7  492.06  5169.7   497.9  5227.2  500.34  5249.2  494.02
  5277.2  498.65  5376.5  500.22  5461.5   495.2  5475.3  498.84  5482.9  496.72
    5494  501.42  5560.9  501.96  5603.7  505.94  5624.5  511.36  5698.4  509.31
    5731  508.93  5788.1  516.68  5858.3  518.82  5880.3  523.31  5922.5   524.8
#Mann= 8 ,-1 , 0
  4462.1    .035       0    4495     .07       0  4947.8     .05       0
  5010.2     .07       0  5021.6      .1       0  5169.7     .12       0
    5494     .07       0  5698.4     .12       0
Bank Sta=4947.8,5010.2
XS Rating Curve= 0 ,0
Exp/Cntr=0.3,0.1

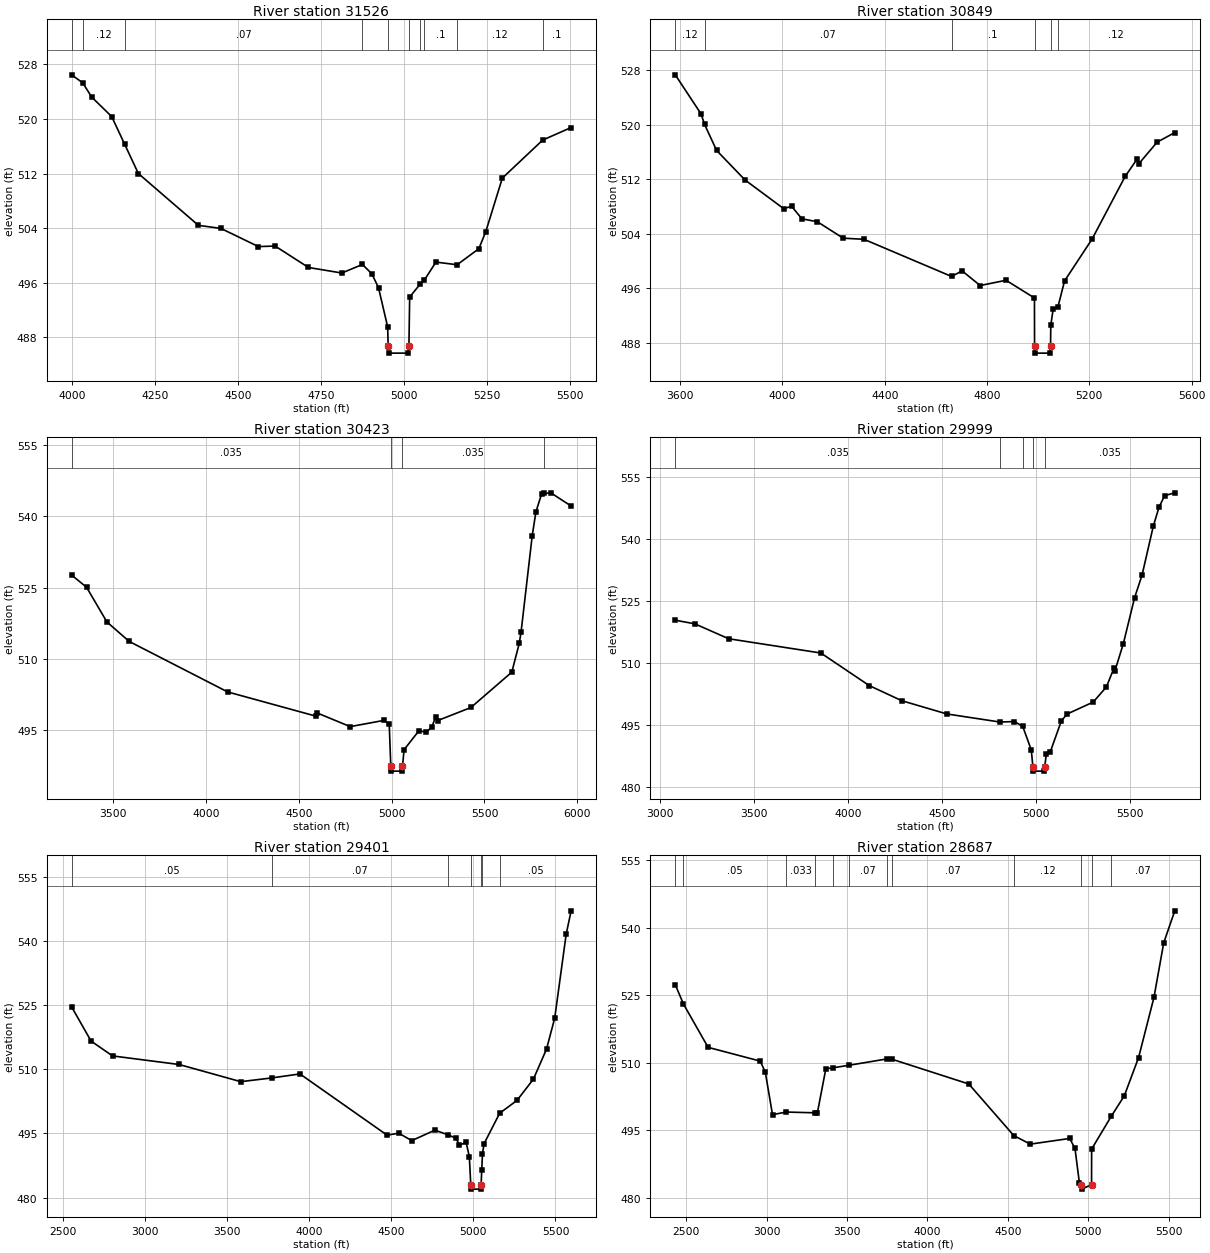
Type RM Length L Ch R = 1 ,31526   ,677,677,677
BEGIN DESCRIPTION:
ALLIGATOR CREEK 35.0
END DESCRIPTION:
XS GIS Cut Line= 3
      2307425.01       13767775.        2306425.       13767875.
        2306125.       13768275.
#Sta/Elev= 30
  3999.4  526.45  4032.9  525.27  4059.7   523.2    4120  520.34  4159.2  516.28
  4200.4     512  4381.3  504.41  4449.1  503.96  4562.2   501.3  4612.5  501.38
    4713  498.24  4813.5  497.43  4875.5  498.68  4903.9  497.32    4924  495.28
  4951.6  489.53  4953.1   486.7  4954.6   485.7  5014.1   485.7  5015.6   486.7
  5017.9  493.91  5048.6  495.75  5061.9  496.38  5097.1  499.03  5160.9  498.64
  5226.3  500.99  5247.1  503.47  5297.1  511.33  5418.8   516.9  5504.4  518.73
#Mann= 10 ,-1 , 0
  3999.4    .035       0  4032.9     .12       0  4159.2     .07       0
  4875.5      .1       0  4953.1     .05       0  5015.6      .1       0
  5048.6     .12       0  5061.9      .1       0  5160.9     .12       0
  5418.8      .1       0
Bank Sta=4953.1,5015.6
XS Rating Curve= 0 ,0
Exp/Cntr=0.3,0.1

Type RM Length L Ch R = 1 ,30849   ,426,426,426
BEGIN DESCRIPTION:
ALLIGATOR CREEK 34.0
END DESCRIPTION:
XS GIS Cut Line= 3
      2307325.05     13767274.99        2305925.       13767475.
      2305724.99     13767975.02
#Sta/Elev= 30
  3581.2   527.3  3682.3  521.55  3695.5  520.05  3742.9  516.21    3854  511.88
  4005.5  507.67  4035.8  508.04  4076.2  506.19  4136.8  505.76  4237.8  503.35
  4318.7  503.19  4661.4  497.74  4702.5  498.56  4773.2  496.41  4874.2  497.18
  4985.4  494.59  4985.8   487.5  4987.3   486.5  5046.8   486.5  5048.3   487.5
  5049.3  490.61  5058.7  492.98  5076.8  493.22  5103.2  497.09  5210.9  503.23
  5340.1  512.41  5387.2  514.97    5394  514.29  5465.3  517.44    5534  518.83
#Mann= 6 ,-1 , 0
  3581.2     .12       0  3695.5     .07       0  4661.4      .1       0
  4985.8     .05       0  5048.3      .1       0  5076.8     .12       0
Bank Sta=4985.8,5048.3
XS Rating Curve= 0 ,0
Exp/Cntr=0.3,0.1

Type RM Length L Ch R = 1 ,30423   ,424,424,424
BEGIN DESCRIPTION:
ALLIGATOR CREEK 33.0
END DESCRIPTION:
XS GIS Cut Line= 3
      2307395.09     13767190.37      2305772.35     13767177.59
      2304705.46     13767183.98
#Sta/Elev= 30
  3277.1  527.64  3357.2  525.09  3467.2  517.76  3587.2  513.66  4117.2  503.02
    4593  497.91    4598  498.61  4777.2  495.71  4957.2  497.01  4987.2  496.31
  4995.7  487.33  4997.2  486.33  5057.2  486.33  5058.7  487.33  5067.2  490.85
  5147.2  494.83  5187.2  494.53  5217.2  495.67  5237.2  497.76  5247.2  496.97
  5427.2  499.74  5647.3  507.19  5687.3  513.23  5697.3  515.69  5757.3  535.97
  5777.3  540.99  5807.3  544.68  5822.1  544.84  5857.3  544.98  5966.8   542.2
#Mann= 4 ,-1 , 0
  3277.1    .035       0  4995.7    .035       0  5058.7    .035       0
  5822.1     .12       0
Bank Sta=4995.7,5058.7
XS Rating Curve= 0 ,0
Exp/Cntr=0.3,0.1

Type RM Length L Ch R = 1 ,29999   ,598,598,598
BEGIN DESCRIPTION:
GER21677
END DESCRIPTION:
XS GIS Cut Line= 3
      2307388.66     13766922.04      2306289.83     13766845.38
      2304730.96     13766813.43
#Sta/Elev= 30
  3080.2   520.4  3184.1  519.53  3364.6  515.91  3855.7  512.45  4113.3  504.56
  4286.6  500.89  4526.6  497.68  4809.8  495.72  4886.7  495.84  4931.1  494.66
  4976.7  488.93  4985.2  484.82  4986.7  483.82  5046.7  483.82  5048.2  484.82
  5056.7  488.03  5076.7  488.36  5136.7  495.98  5166.7  497.64  5306.8  500.57
  5376.8  504.23  5416.1   508.7  5421.1  507.99  5466.8   514.7  5526.8  525.84
  5566.8  531.37  5626.8  543.25  5656.8  547.77  5686.9   550.6  5740.9  551.28
#Mann= 5 ,-1 , 0
  3080.2    .035       0  4809.8    .063       0  4931.1    .035       0
  4985.2    .035       0  5048.2    .035       0
Bank Sta=4985.2,5048.2
XS Rating Curve= 0 ,0
Exp/Cntr=0.3,0.1

Type RM Length L Ch R = 1 ,29401   ,714,714,714
BEGIN DESCRIPTION:
ALLIGATOR CREEK 32.0
END DESCRIPTION:
XS GIS Cut Line= 3
      2307663.42     13766468.45        2305225.       13766325.
      2304625.04       13766325.
#Sta/Elev= 30
  2552.7  524.63  2671.3  516.63  2801.6  513.16  3207.3  511.15  3582.9  507.13
  3770.6     508  3943.5  508.94  4474.4   494.6  4544.6  495.07  4624.7  493.33
  4764.9  495.77  4844.1  494.71  4895.2  493.86  4915.2  492.21  4955.3  492.97
  4975.3  489.56  4983.8  482.97  4985.3  481.97  5045.3  481.97  5046.8  482.97
  5050.8  486.42  5055.3   490.3  5065.3  492.64    5160  499.74  5265.3  502.74
  5365.3  507.71  5445.3  514.75  5495.3  522.02  5565.3  541.71  5595.3  547.13
#Mann= 7 ,-1 , 0
  2552.7     .05       0  3770.6     .07       0  4844.1     .12       0
  4983.8     .05       0  5046.8     .12       0  5050.8     .07       0
    5160     .05       0
Bank Sta=4983.8,5046.8
XS Rating Curve= 0 ,0
Exp/Cntr=0.3,0.1

Type RM Length L Ch R = 1 ,28687   ,674,674,674
BEGIN DESCRIPTION:
ALLIGATOR CREEK 31.0
END DESCRIPTION:
XS GIS Cut Line= 3
      2307680.27     13766426.34        2305225.       13765675.
      2304724.98     13765474.99
#Sta/Elev= 30
  2431.9  527.32  2482.9  523.02  2636.1   513.4  2960.3  510.34  2991.7  507.89
  3036.6  498.43    3121  499.02  3302.1  498.85  3315.9   498.9  3368.2  508.64
  3409.8  508.84  3512.7  509.42  3747.4  510.82  3778.6  510.77  4257.1  505.26
  4537.2  493.78  4639.7  491.89  4884.9  493.15  4917.6  490.92  4945.2  483.21
  4957.6  482.89  4959.1  481.89  5020.6  482.89  5021.1  490.79    5143  498.07
  5224.4  502.64  5313.2  511.14  5408.8  524.52  5469.4  536.63  5538.1  543.74
#Mann= 12 ,-1 , 0
  2431.9     .07       0  2482.9     .05       0    3121    .033       0
  3302.1     .07       0  3409.8     .05       0  3512.7     .07       0
  3747.4    .035       0  3778.6     .07       0  4537.2     .12       0
  4957.6     .05       0  5020.6     .12       0    5143     .07       0
Bank Sta=4957.6,5020.6
XS Rating Curve= 0 ,0
Exp/Cntr=0.3,0.1

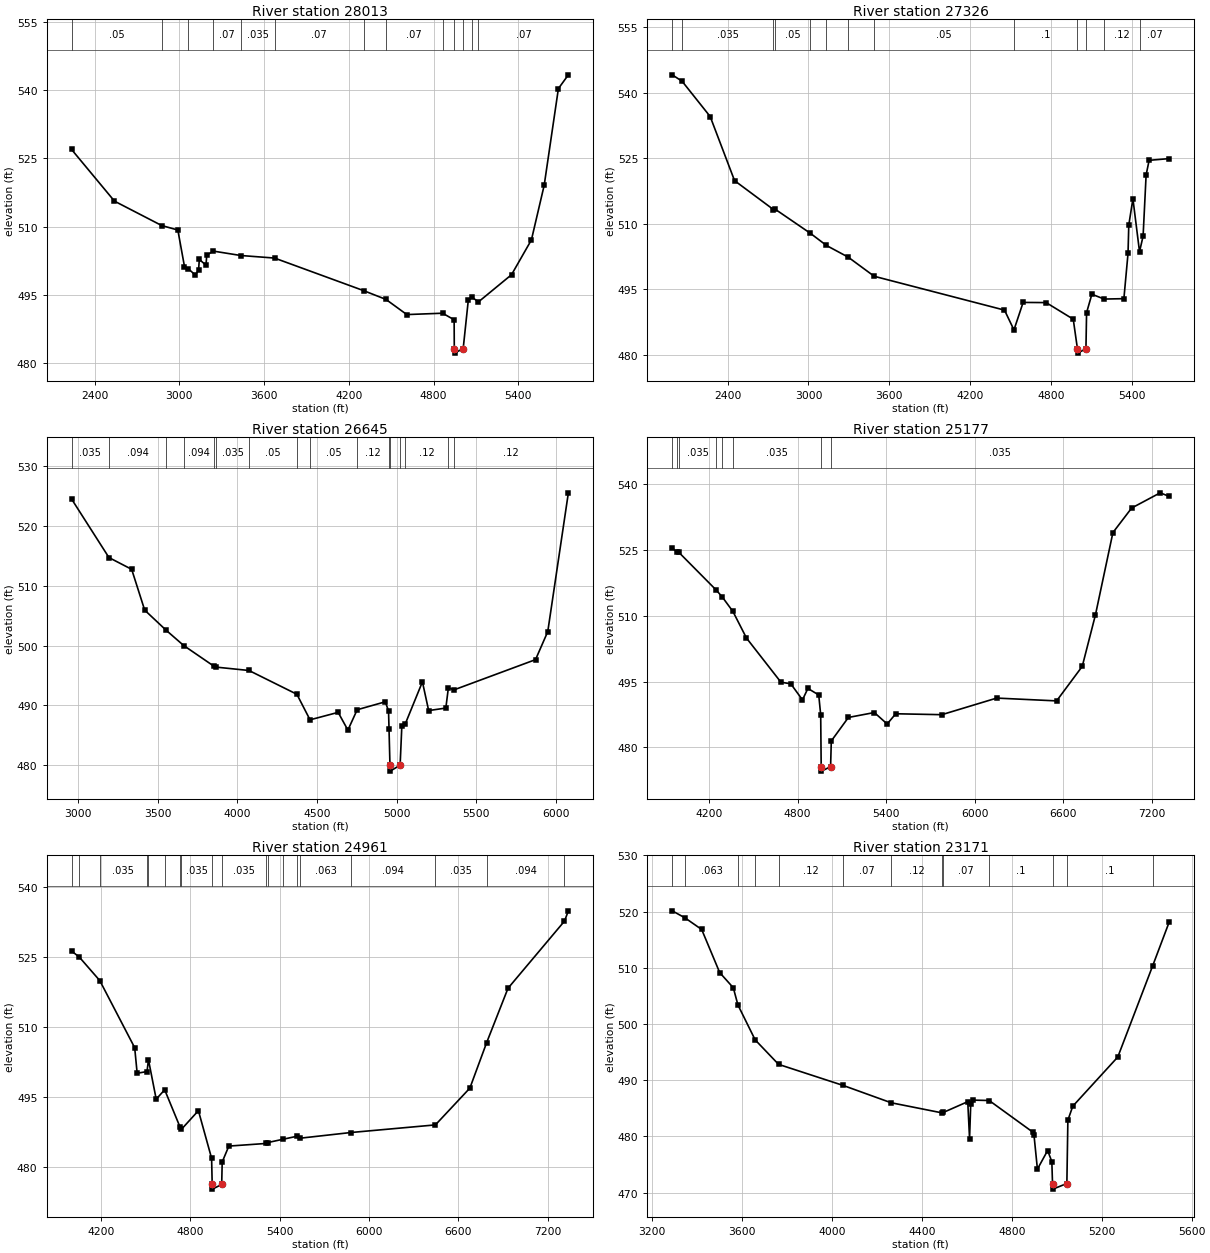
Type RM Length L Ch R = 1 ,28013   ,687,687,687
BEGIN DESCRIPTION:
ALLIGATOR CREEK 30.0
END DESCRIPTION:
XS GIS Cut Line= 3
      2307914.71     13766165.95        2305375.       13765075.
      2304624.76     13764994.06
#Sta/Elev= 30
  2235.8  526.98  2540.2  515.61  2874.9  510.25  2988.8  509.27  3035.9  501.24
  3064.3  500.72    3112  499.39  3135.5  500.43    3141  502.81  3188.1  501.54
  3193.5  503.74  3239.7  504.64  3434.5  503.67  3673.5  503.11  4305.4  495.94
  4462.9  494.02  4610.4  490.69  4863.6  490.99  4945.5  489.55  4946.6  483.22
  4948.1  482.22  5009.6  483.22  5045.8  493.85  5070.2  494.54  5117.8  493.48
  5351.9  499.45  5492.8   507.1  5583.3  519.11  5683.9  540.35  5754.5  543.37
#Mann= 13 ,-1 , 0
  2235.8     .05       0  2874.9     .07       0  3064.3    .033       0
  3239.7     .07       0  3434.5    .035       0  3673.5     .07       0
  4305.4    .035       0  4462.9     .07       0  4863.6     .12       0
  4946.6     .05       0  5009.6     .12       0  5070.2     .12       0
  5117.8     .07       0
Bank Sta=4946.6,5009.6
XS Rating Curve= 0 ,0
Exp/Cntr=0.3,0.1

Type RM Length L Ch R = 1 ,27326   ,681,681,681
BEGIN DESCRIPTION:
ALLIGATOR CREEK 29.0
END DESCRIPTION:
XS GIS Cut Line= 3
      2308424.98       13764775.        2305425.       13764475.
      2304824.97     13764775.02
#Sta/Elev= 30
  1989.4  544.11  2062.8  542.63  2270.8  534.57  2451.7   519.9  2740.1  513.29
  2754.6  513.33    3013  507.88  3133.4  505.07  3294.6   502.4  3487.6  498.02
  4454.1  490.28  4524.3  485.75  4592.3  492.04  4763.1     492  4964.1   488.2
  4995.2  481.44  4996.7  480.44  5058.3  481.44    5063  489.69  5102.2  493.91
  5193.9  492.81  5339.8   492.9  5370.5  503.26  5376.1  509.74  5406.8  515.74
  5455.8  503.64  5482.3  507.21  5504.7  521.21    5527  524.55  5675.2  524.94
#Mann= 13 ,-1 , 0
  1989.4     .07       0  2062.8    .035       0  2740.1    .094       0
  2754.6     .05       0    3013    .094       0  3133.4      .1       0
  3294.6    .094       0  3487.6     .05       0  4524.3      .1       0
  4995.2     .05       0  5058.3      .1       0  5193.9     .12       0
  5455.8     .07       0
Bank Sta=4995.2,5058.3
XS Rating Curve= 0 ,0
Exp/Cntr=0.3,0.1

Type RM Length L Ch R = 1 ,26645   ,1468,1468,1468
BEGIN DESCRIPTION:
ALLIGATOR CREEK 28.0
END DESCRIPTION:
XS GIS Cut Line= 3
      2307875.05     13764575.01        2305875.       13764175.
      2304874.99       13763775.
#Sta/Elev= 30
  2960.4  524.55  3195.3  514.73  3337.8  512.76  3419.4  505.93  3554.4  502.55
  3664.3     500  3855.8   496.5    3866  496.39  4073.8  495.82  4374.1  491.84
  4456.6  487.56  4632.9  488.81  4694.1  485.84  4752.4  489.25  4928.7  490.58
  4949.1  489.05  4952.1  485.99    4958  479.97  4959.5  478.97  5021.7  479.97
  5032.4   486.5  5054.5  486.91  5161.6  493.92  5200.7  489.11  5308.4  489.53
  5324.4  492.92    5360  492.58  5871.1  497.64  5947.8  502.33  6077.1  525.57
#Mann= 16 ,-1 , 0
  2960.4    .035       0  3195.3    .094       0  3554.4      .1       0
  3664.3    .094       0  3855.8     .05       0    3866    .035       0
  4073.8     .05       0  4374.1      .1       0  4456.6     .05       0
  4752.4     .12       0  4952.1      .1       0    4958     .05       0
  5021.7      .1       0  5054.5     .12       0  5324.4    .063       0
    5360     .12       0
Bank Sta=4958,5021.7
XS Rating Curve= 0 ,0
Exp/Cntr=0.3,0.1

Type RM Length L Ch R = 1 ,25177   ,216,216,216
BEGIN DESCRIPTION:
GER21676
END DESCRIPTION:
XS GIS Cut Line= 4
      2307867.85     13764545.46      2307350.36     13764315.46
      2305433.75     13763139.94      2304941.85     13762884.41
#Sta/Elev= 30
  3950.1  525.37  3984.5  524.48  3995.7  524.38  4246.8  515.87  4287.7  514.32
  4361.5  510.95  4453.6  504.89  4686.9  494.85  4753.9  494.48  4833.2  490.82
  4869.9  493.43  4943.4  491.94  4956.7  487.41    4960   475.6  4961.5   474.6
  5023.8   475.6  5028.6  481.47  5144.6  486.82  5320.4  487.94  5407.5  485.33
  5465.5  487.66  5777.9  487.45    6150  491.23  6556.2  490.59  6730.2  498.45
  6819.7  510.18  6938.1  528.91  7065.2   534.5  7258.6  537.96  7319.1  537.16
#Mann= 8 ,-1 , 0
  3950.1    .035       0  3984.5    .063       0  3995.7    .035       0
  4246.8    .094       0  4287.7    .063       0  4361.5    .035       0
    4960    .035       0  5023.8    .035       0
Bank Sta=4960,5023.8
XS Rating Curve= 0 ,0
Exp/Cntr=0.3,0.1

Type RM Length L Ch R = 1 ,24961   ,1790,1790,1790
BEGIN DESCRIPTION:
ALLIGATOR CREEK 27.0
END DESCRIPTION:
XS GIS Cut Line= 3
      2307861.48     13764341.03      2307273.69     13764040.75
      2305000.62     13762629.66
#Sta/Elev= 30
  4003.3  526.34  4055.1  525.06    4193  520.01  4427.4  505.63    4444  500.15
  4510.2  500.52  4519.9  503.05  4571.8  494.61  4628.8  496.61  4732.1  488.61
  4741.1  488.14  4855.2  492.14  4943.8  481.93  4947.7  476.33  4949.2  475.33
  5011.5  476.33  5014.9  481.15  5059.5  484.55    5312  485.12  5319.9   485.3
    5424  486.02  5515.9  486.65  5537.8  486.24  5879.3  487.46  6446.2  489.09
  6677.5  496.97  6789.9  506.69  6933.5  518.36  7312.8  532.75  7338.8  534.95
#Mann= 19 ,-1 , 0
  4003.3    .035       0  4055.1     .07       0    4193    .035       0
  4510.2     .12       0  4519.9    .035       0  4628.8    .063       0
  4732.1      .1       0  4741.1    .035       0  4947.7    .035       0
  5011.5    .035       0    5312    .063       0  5319.9    .035       0
    5424    .063       0  5515.9    .035       0  5537.8    .063       0
  5879.3    .094       0  6446.2    .035       0  6789.9    .094       0
  7312.8    .035       0
Bank Sta=4947.7,5011.5
XS Rating Curve= 0 ,0
Exp/Cntr=0.3,0.1

Type RM Length L Ch R = 1 ,23171   ,692,692,692
BEGIN DESCRIPTION:
ALLIGATOR CREEK 26.0
END DESCRIPTION:
XS GIS Cut Line= 3
      2307675.02     13763325.01        2306075.       13762725.
      2305775.01     13762325.02
#Sta/Elev= 30
  3290.9  520.14  3347.5  518.89  3421.8  516.82  3501.9  509.15  3562.4  506.45
  3582.9  503.39  3659.5  497.18  3763.6  492.82  4051.4  489.06  4263.9  485.99
  4491.3  484.18  4495.7  484.26  4604.6  486.18  4612.6  479.62  4617.9  485.76
  4625.9  486.46  4699.8  486.39  4892.9  480.79  4899.2  480.18  4914.3  474.18
  4959.7  477.49  4978.4  475.51  4981.4  471.62  4982.9  470.62  5045.2  471.62
  5049.7  482.89  5071.6  485.38  5271.6  494.13  5426.6  510.35  5499.7   518.1
#Mann= 13 ,-1 , 0
  3290.9    .094       0  3347.5    .063       0  3582.9     .12       0
  3659.5    .063       0  3763.6     .12       0  4051.4     .07       0
  4263.9     .12       0  4491.3      .1       0  4495.7     .07       0
  4699.8      .1       0  4981.4     .05       0  5045.2      .1       0
  5426.6     .12       0
Bank Sta=4981.4,5045.2
XS Rating Curve= 0 ,0
Exp/Cntr=0.3,0.1