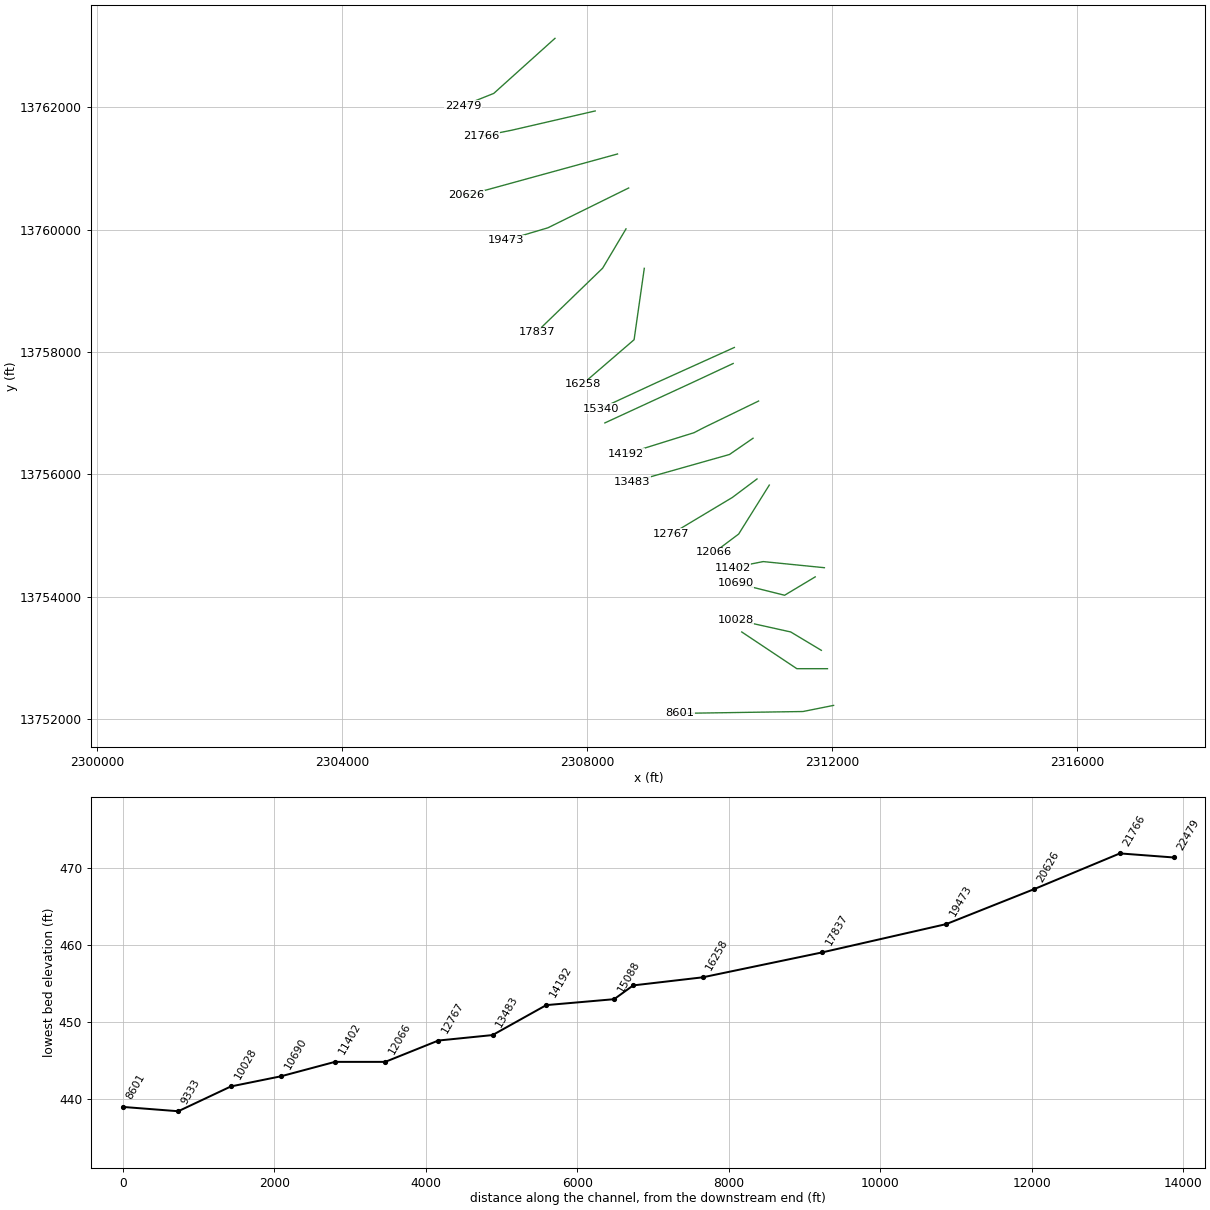
HEC-RAS study GERONIMO CREEK.prj: GERONIMO CREEK Base Level Engineering

--- GERONIMO CREEK.g01 (geometry) --- (continued)

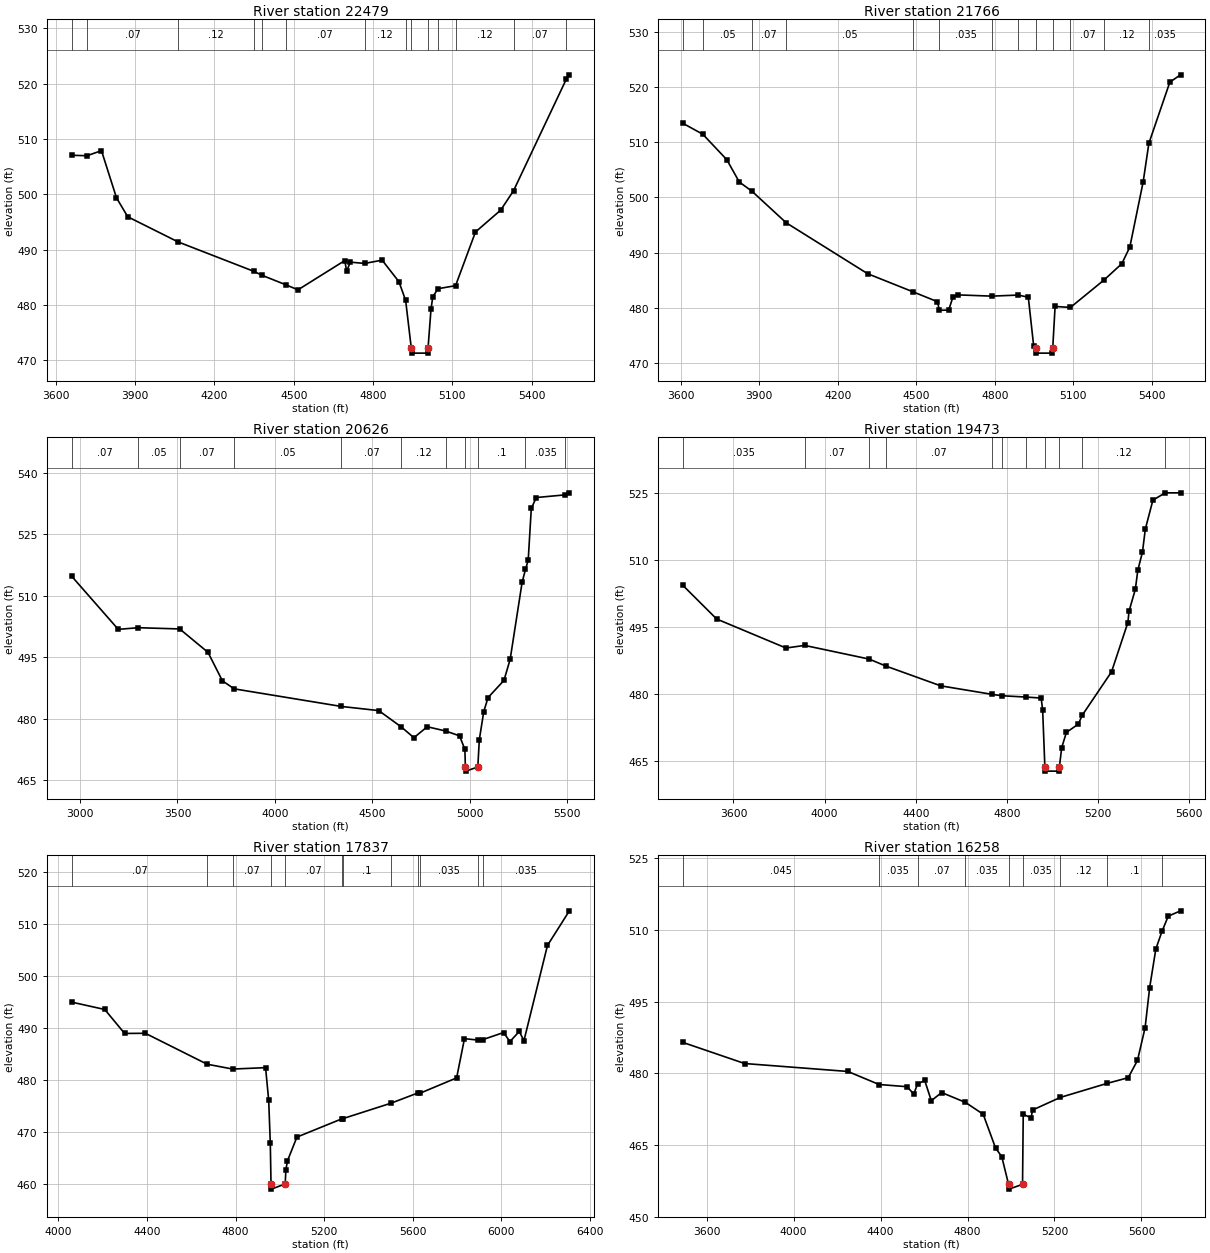
Type RM Length L Ch R = 1 ,22479   ,713,713,713
BEGIN DESCRIPTION:
ALLIGATOR CREEK 25.0
END DESCRIPTION:
XS GIS Cut Line= 3
      2307474.99       13763125.        2306475.       13762225.
      2305974.97     13762024.99
#Sta/Elev= 30
  3659.3  507.06  3717.7  506.98  3772.5   507.9  3829.3  499.38  3871.9  495.95
  4062.3  491.41  4349.1  486.09  4381.5  485.35    4470  483.66  4516.2  482.75
  4693.4  488.04  4700.1  486.12  4714.3  487.75  4768.4  487.52  4834.6  488.11
  4898.1  484.22  4923.5  480.85  4944.7  472.31  4946.2  471.31    5007  471.31
  5008.5  472.31  5019.5  479.23  5026.2  481.47  5045.9  482.95  5112.5   483.5
  5187.8   493.2  5283.3  497.15    5332  500.67  5531.8  520.84  5543.2   521.6
#Mann= 14 ,-1 , 0
  3659.3    .063       0  3717.7     .07       0  4062.3     .12       0
  4349.1     .07       0  4381.5     .12       0    4470     .07       0
  4768.4     .12       0  4923.5      .1       0  4944.7     .05       0
  5008.5      .1       0  5045.9     .07       0  5112.5     .12       0
    5332     .07       0  5531.8     .12       0
Bank Sta=4944.7,5008.5
XS Rating Curve= 0 ,0
Exp/Cntr=0.3,0.1

Type RM Length L Ch R = 1 ,21766   ,1140,1140,1140
BEGIN DESCRIPTION:
ALLIGATOR CREEK 24.0
END DESCRIPTION:
XS GIS Cut Line= 3
      2308131.66      13761938.5        2306775.       13761625.
      2306275.01       13761525.
#Sta/Elev= 30
  3607.2  513.43  3684.1  511.43  3775.7  506.83  3823.5  502.79  3871.8  501.13
  4002.6  495.42  4314.1   486.2  4487.2  482.93  4580.8  481.14  4587.6  479.59
  4623.5  479.62  4640.4  482.06  4660.9  482.37  4788.3  482.15  4888.7  482.34
  4927.8  481.96  4948.3  473.16  4957.4  472.84  4958.9  471.84  5019.8  471.84
  5021.3  472.84  5030.2  480.28    5089  480.11    5218   485.1  5285.2  488.02
  5315.8  491.03  5366.7  502.81  5388.5  509.78  5468.7  520.86  5509.5  522.18
#Mann= 13 ,-1 , 0
  3607.2    .035       0  3684.1     .05       0  3871.8     .07       0
  4002.6     .05       0  4487.2     .07       0  4587.6    .035       0
  4788.3     .07       0  4888.7     .12       0  4957.4     .05       0
  5021.3     .12       0    5089     .07       0    5218     .12       0
  5388.5    .035       0
Bank Sta=4957.4,5021.3
XS Rating Curve= 0 ,0
Exp/Cntr=0.3,0.1

Type RM Length L Ch R = 1 ,20626   ,1153,1153,1153
BEGIN DESCRIPTION:
X17995
END DESCRIPTION:
XS GIS Cut Line= 2
      2308496.24     13761235.37      2306031.03      13760558.3
#Sta/Elev= 30
    2956  514.77  3195.8  501.77  3298.9  502.17  3511.4  501.87  3656.6  496.16
  3730.7  489.21  3791.1  487.25  4342.1  482.95  4533.6  481.94  4649.6  477.94
  4714.1  475.33  4782.5     478  4877.5  476.96  4948.4  475.78  4975.9  472.47
  4978.4  468.17  4979.9  467.17  5042.3  468.17    5050  474.85  5072.8   481.7
  5094.8  485.12  5176.5  489.31  5208.4  494.47  5269.9  513.29    5287  516.38
    5301  518.63  5316.9  531.28  5342.5  533.94  5492.4   534.6  5512.5  535.09
#Mann= 11 ,-1 , 0
    2956     .07       0  3298.9     .05       0  3511.4     .07       0
  3791.1     .05       0  4342.1     .07       0  4649.6     .12       0
  4877.5      .1       0  4978.4     .05       0  5042.3      .1       0
    5287    .035       0  5492.4    .063       0
Bank Sta=4978.4,5042.3
XS Rating Curve= 0 ,0
Exp/Cntr=0.3,0.1

Type RM Length L Ch R = 1 ,19473   ,1636,1636,1636
BEGIN DESCRIPTION:
ALLIGATOR CREEK 23.0
END DESCRIPTION:
XS GIS Cut Line= 3
       2308678.6     13760679.83      2307359.13     13760028.78
      2306674.98     13759824.99
#Sta/Elev= 30
  3377.1  504.41  3526.1  496.82  3830.7   490.3  3912.2  490.89  4195.6  487.82
    4269  486.25  4509.8  481.81  4735.9  479.89    4778  479.59    4884  479.29
  4950.6  479.07  4957.1  476.39  4966.8  463.66  4968.3  462.66  5029.3  462.66
  5030.8  463.66  5040.6  467.92  5061.4  471.36  5113.6  473.21  5130.6  475.19
  5259.5  484.96  5331.1  496.01  5336.3  498.58    5364  503.49  5374.7  507.73
  5395.3  511.87  5407.8  517.01    5441   523.5  5495.1  525.15  5562.3  525.15
#Mann= 11 ,-1 , 0
  3377.1    .035       0  3912.2     .07       0  4195.6     .05       0
    4269     .07       0  4735.9     .05       0    4778     .12       0
    4884      .1       0  4966.8     .05       0  5030.8      .1       0
  5130.6     .12       0  5495.1    .063       0
Bank Sta=4966.8,5030.8
XS Rating Curve= 0 ,0
Exp/Cntr=0.3,0.1

Type RM Length L Ch R = 1 ,17837   ,1579,1579,1579
BEGIN DESCRIPTION:
ALLIGATOR CREEK 22.0
END DESCRIPTION:
XS GIS Cut Line= 3
      2308635.15     13760011.38      2308253.23     13759369.06
      2307174.98     13758324.98
#Sta/Elev= 30
  4059.3  494.97  4209.2  493.55  4298.9  488.94  4392.5  488.97  4671.7  483.02
    4787  482.09  4935.5  482.36  4949.6  476.07  4956.8  467.86  4960.1  459.99
  4961.6  458.99  5024.1  459.99  5027.3  462.75  5034.5  464.45    5077     469
    5282  472.55  5283.1  472.53  5503.8  475.55  5623.8   477.5  5632.9  477.44
  5798.3  480.39  5833.7  487.94  5893.4  487.67  5915.7  487.74  6010.5  489.12
  6038.8  487.37  6081.2  489.32  6102.3  487.55  6208.5  505.87  6307.5  512.53
#Mann= 12 ,-1 , 0
  4059.3     .07       0  4671.7    .045       0    4787     .07       0
  4960.1     .05       0  5024.1     .07       0    5282     .12       0
  5283.1      .1       0  5503.8    .035       0  5623.8     .07       0
  5632.9    .035       0  5893.4     .07       0  5915.7    .035       0
Bank Sta=4960.1,5024.1
XS Rating Curve= 0 ,0
Exp/Cntr=0.3,0.1

Type RM Length L Ch R = 1 ,16258   ,918,918,918
BEGIN DESCRIPTION:
ALLIGATOR CREEK 21.0
END DESCRIPTION:
XS GIS Cut Line= 3
      2308933.79       13759367.      2308767.12     13758200.31
      2307925.04     13757475.03
#Sta/Elev= 30
  3489.8  486.46  3774.7  482.03  4249.4  480.37  4393.3  477.64  4522.2  477.18
  4552.5  475.63  4570.1  477.75    4603  478.49  4633.3  474.25  4680.9  475.96
  4790.2   473.9  4871.9  471.42  4928.9  464.35  4957.4  462.55  4988.7  456.75
  4990.2  455.75    5053  456.75  5056.2  471.39  5092.4  470.69    5099   472.3
  5226.3  474.93  5441.5  477.87  5538.9  479.06  5581.7  482.68  5616.8  489.55
  5637.7  497.91  5666.2  506.01  5694.8  509.72  5723.2  512.86  5779.7  513.98
#Mann= 9 ,-1 , 0
  3489.8    .045       0  4393.3    .035       0  4570.1     .07       0
  4790.2    .035       0  4988.7    .035       0    5053    .035       0
  5226.3     .12       0  5441.5      .1       0  5694.8    .035       0
Bank Sta=4988.7,5053
XS Rating Curve= 0 ,0
Exp/Cntr=0.3,0.1

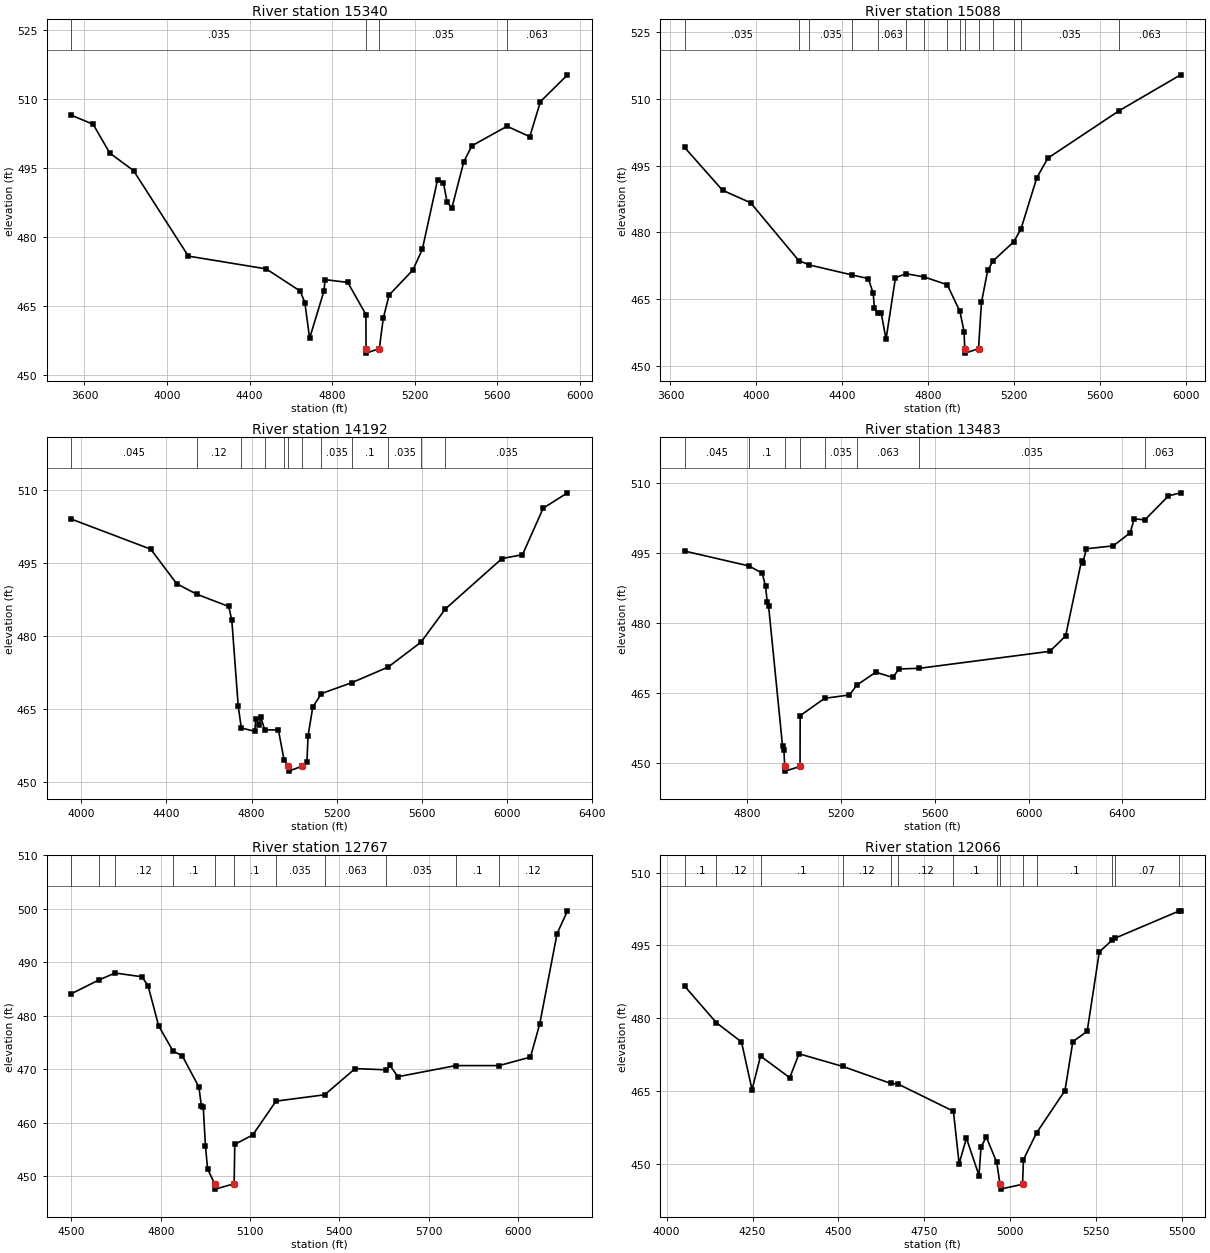
Type RM Length L Ch R = 1 ,15340   ,252,252,252
BEGIN DESCRIPTION:
ALLIGATOR CREEK 20.0
END DESCRIPTION:
XS GIS Cut Line= 3
      2310404.19     13758073.74       2309132.8     13757498.74
      2308219.28     13757075.67
#Sta/Elev= 30
  3537.2   506.4    3642  504.44  3722.9  498.18  3837.8  494.37    4103  475.79
  4480.2  473.01  4644.8  468.19  4667.4  465.69  4690.5  457.93  4759.8  468.18
  4765.5  470.67  4875.3  470.07  4963.2  463.08  4963.7   455.7  4965.2   454.7
    5028   455.7  5047.2  462.29  5075.6  467.34  5190.2  472.74  5236.1  477.23
  5310.3  492.43  5338.8  491.66  5356.2  487.56  5379.1  486.21  5437.1  496.29
  5476.3  499.77  5646.7  504.01  5756.7  501.75  5808.1  509.36  5939.3  515.19
#Mann= 4 ,-1 , 0
  3537.2    .035       0  4963.7    .035       0    5028    .035       0
  5646.7    .063       0
Bank Sta=4963.7,5028
XS Rating Curve= 0 ,0
Exp/Cntr=0.3,0.1

Type RM Length L Ch R = 1 ,15088   ,896,896,896
BEGIN DESCRIPTION:
ALLIGATOR CREEK 19.0
END DESCRIPTION:
XS GIS Cut Line= 3
      2310384.95     13757811.77      2309701.39     13757492.35
       2308289.7      13756840.8
#Sta/Elev= 30
  3665.7  499.07  3842.3  489.46  3973.1  486.65  4197.1  473.69  4246.1   472.7
  4445.5  470.45  4521.1  469.63    4544  466.32  4549.5  462.93  4567.5  461.95
  4581.4  461.83  4603.5     456  4647.5  469.84  4696.5  470.73  4781.5     470
  4888.5  468.26  4947.4  462.29  4966.9  457.74  4969.8  453.91  4971.3  452.91
  5034.1  453.91  5047.9  464.33  5077.1  471.51  5102.5  473.63  5198.3   477.9
  5231.7  480.77  5305.8   492.3  5357.2  496.67  5689.7  507.33    5975  515.36
#Mann= 15 ,-1 , 0
  3665.7    .035       0  4197.1      .1       0  4246.1    .035       0
  4445.5     .12       0  4567.5    .063       0  4696.5     .12       0
  4781.5    .035       0  4888.5    .063       0  4947.4      .1       0
  4969.8     .05       0  5034.1      .1       0  5102.5    .063       0
  5198.3     .12       0  5231.7    .035       0  5689.7    .063       0
Bank Sta=4969.8,5034.1
XS Rating Curve= 0 ,0
Exp/Cntr=0.3,0.1

Type RM Length L Ch R = 1 ,14192   ,709,709,709
BEGIN DESCRIPTION:
GER21675
END DESCRIPTION:
XS GIS Cut Line= 4
      2310800.23     13757198.47      2309905.83     13756764.04
      2309746.11     13756680.99      2308640.85     13756335.99
#Sta/Elev= 30
  3953.3  504.05    4326  497.86    4448  490.75  4541.2   488.6  4692.9  486.06
  4707.3  483.17  4737.3  465.57  4751.7  461.05  4814.6  460.33  4820.1  462.82
  4837.1  461.71  4842.7  463.35  4861.6  460.66  4926.3  460.62  4952.5  454.52
  4972.4  453.14  4973.9  452.14  5037.9  453.14  5060.2  453.96  5065.8  459.45
  5087.9  465.33  5128.6  468.12  5272.3  470.38  5441.9  473.57  5596.6   478.7
  5711.8  485.57  5977.4  495.93  6073.8  496.72  6171.3  506.31  6285.5  509.47
#Mann= 12 ,-1 , 0
  3953.3    .045       0  4541.2     .12       0  4751.7      .1       0
  4861.6     .12       0  4952.5      .1       0  4972.4     .05       0
  5037.9      .1       0  5128.6    .035       0  5272.3      .1       0
  5441.9    .035       0  5596.6      .1       0  5711.8    .035       0
Bank Sta=4972.4,5037.9
XS Rating Curve= 0 ,0
Exp/Cntr=0.3,0.1

Type RM Length L Ch R = 1 ,13483   ,716,716,716
BEGIN DESCRIPTION:
ALLIGATOR CREEK 18.0
END DESCRIPTION:
XS GIS Cut Line= 3
      2310709.55     13756590.25        2310325.       13756325.
      2308738.35     13755876.42
#Sta/Elev= 30
  4532.5   495.4  4807.4  492.21  4863.8  490.65  4878.2  487.82  4884.7  484.59
  4890.8  483.66  4950.3  453.67  4956.4  452.75  4959.5  449.25    4961  448.25
    5025  449.25  5025.6  460.13  5129.7  463.85    5236  464.57  5267.7  466.71
  5348.3  469.44  5421.4  468.32  5446.5  470.14  5533.7  470.28  6090.8  473.92
  6157.9  477.22  6225.9  493.37  6231.1  492.88  6246.7   495.9    6361  496.51
  6433.7  499.33  6450.4  502.31  6496.2  502.09  6596.7  507.23  6648.5  507.88
#Mann= 8 ,-1 , 0
  4532.5    .045       0  4807.4      .1       0  4959.5     .05       0
    5025      .1       0  5129.7    .035       0  5267.7    .063       0
  5533.7    .035       0  6496.2    .063       0
Bank Sta=4959.5,5025
XS Rating Curve= 0 ,0
Exp/Cntr=0.3,0.1

Type RM Length L Ch R = 1 ,12767   ,701,701,701
BEGIN DESCRIPTION:
ALLIGATOR CREEK 17.0
END DESCRIPTION:
XS GIS Cut Line= 3
      2310775.02     13755925.01        2310375.       13755625.
      2309375.01     13755025.01
#Sta/Elev= 30
    4500  484.13  4591.5  486.67  4646.5  487.99  4736.5  487.29  4757.3   485.6
  4792.7  478.12  4841.2  473.37  4871.9  472.52  4928.1  466.65  4936.5  463.02
  4942.7  462.85    4950  455.64  4957.3   451.3  4980.9  448.54  4982.4  447.54
  5046.4  448.54  5048.6  455.92  5108.9  457.68  5187.1  464.01  5350.5   465.2
  5452.9   470.1  5557.8  469.87  5569.5   470.7  5596.7  468.58  5790.8  470.66
  5936.2  470.66  6041.8  472.25  6072.9  478.45  6131.2  495.37  6166.2  499.63
#Mann= 11 ,-1 , 0
    4500      .1       0  4591.5    .045       0  4646.5     .12       0
  4841.2      .1       0  4980.9     .05       0  5046.4      .1       0
  5187.1    .035       0  5350.5    .063       0  5557.8    .035       0
  5790.8      .1       0  5936.2     .12       0
Bank Sta=4980.9,5046.4
XS Rating Curve= 0 ,0
Exp/Cntr=0.3,0.1

Type RM Length L Ch R = 1 ,12066   ,664,664,664
BEGIN DESCRIPTION:
ALLIGATOR CREEK 16.0
END DESCRIPTION:
XS GIS Cut Line= 3
      2310974.98     13755824.96        2310475.       13755025.
      2310074.96     13754724.97
#Sta/Elev= 30
  4052.3  486.61  4144.8  479.07  4217.9   475.1  4248.6  465.27  4273.3  472.19
  4358.3  467.74  4385.4  472.66  4512.5  470.06  4651.8  466.57  4673.8  466.42
  4834.6  460.82  4851.2     450  4872.4  455.29    4909  447.57  4914.9  453.46
  4930.2  455.52  4960.7  450.29  4970.1  445.77  4971.6  444.77  5035.7  445.77
  5038.4  450.85  5076.6  456.37  5159.2  465.09  5182.1  475.17  5223.8   477.3
  5259.2  493.69    5296  496.04  5303.9  496.46  5492.4  502.13  5495.7  502.13
#Mann= 14 ,-1 , 0
  4052.3      .1       0  4144.8     .12       0  4273.3      .1       0
  4512.5     .12       0  4651.8      .1       0  4673.8     .12       0
  4834.6      .1       0  4960.7     .12       0  4970.1     .05       0
  5035.7     .12       0  5076.6      .1       0    5296     .12       0
  5303.9     .07       0  5492.4     .12       0
Bank Sta=4970.1,5035.7
XS Rating Curve= 0 ,0
Exp/Cntr=0.3,0.1

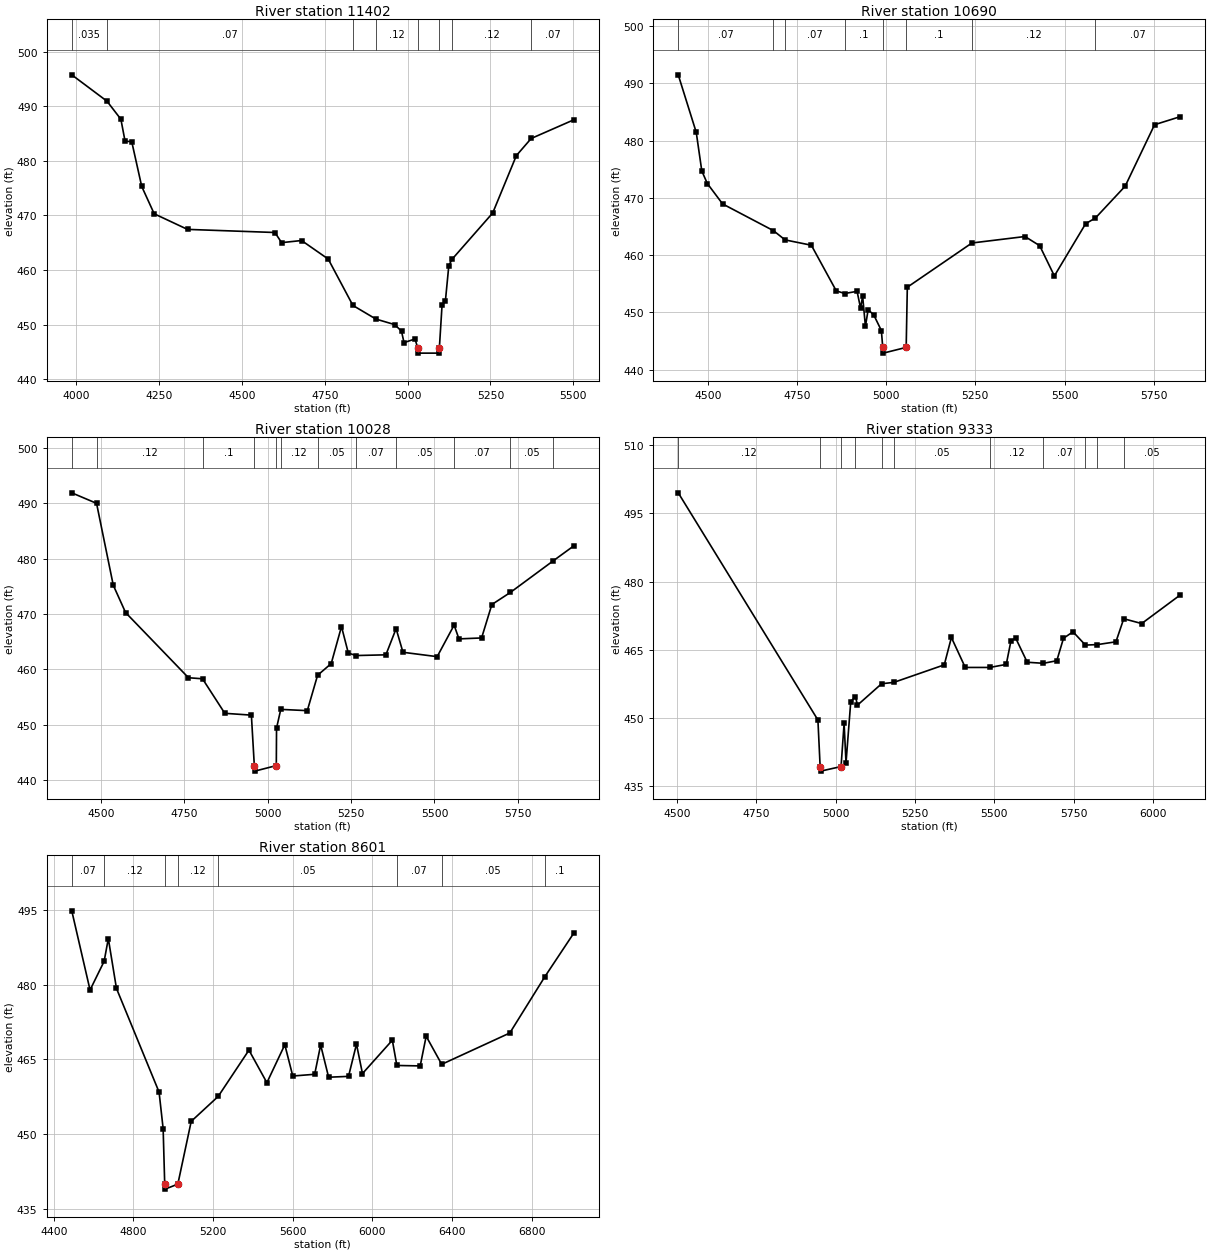
Type RM Length L Ch R = 1 ,11402   ,712,712,712
BEGIN DESCRIPTION:
ALLIGATOR CREEK 15.0
END DESCRIPTION:
XS GIS Cut Line= 3
        2311875.       13754475.        2310875.       13754575.
      2310374.99       13754475.
#Sta/Elev= 30
  3986.6  495.78  4092.8  490.95  4134.8  487.64  4147.4  483.61  4167.5  483.54
  4197.6  475.33  4235.3  470.31  4335.8  467.45  4599.6  466.88  4619.7  465.02
    4680  465.41  4760.4  462.01  4834.9  453.51  4904.4  451.01  4961.4  449.99
  4981.5  448.78  4989.1  446.69  5022.2  447.37  5030.2  445.77  5031.7  444.77
  5094.3  444.77  5095.8  445.77  5103.8  453.52    5114  454.37  5124.2  460.78
  5133.5  461.94  5256.7  470.46  5328.1  480.98  5372.7  484.11  5501.5  487.54
#Mann= 8 ,-1 , 0
  3986.6    .035       0  4092.8     .07       0  4834.9      .1       0
  4904.4     .12       0  5030.2     .05       0  5095.8     .12       0
  5133.5     .12       0  5372.7     .07       0
Bank Sta=5030.2,5095.8
XS Rating Curve= 0 ,0
Exp/Cntr=0.3,0.1

Type RM Length L Ch R = 1 ,10690   ,662,662,662
BEGIN DESCRIPTION:
ALLIGATOR CREEK 14.0
END DESCRIPTION:
XS GIS Cut Line= 3
      2311724.98     13754324.99        2311225.       13754025.
      2310424.99       13754225.
#Sta/Elev= 30
  4416.9  491.49  4467.4  481.44    4483   474.7  4498.5  472.51  4541.3  468.95
  4683.9  464.28  4716.4  462.67  4790.1  461.74    4860  453.77  4883.7  453.31
  4918.3  453.69  4928.1  450.76  4933.9  452.85  4941.7  447.59  4949.4  450.48
    4965  449.58  4986.4  446.85  4990.3   443.9  4991.8   442.9    5056   443.9
  5059.2  454.41  5240.3  462.13  5389.1  463.26  5430.3  461.66  5471.5  456.38
  5559.2   465.5  5586.6  466.49    5670  472.05  5752.4  482.78  5824.6  484.19
#Mann= 8 ,-1 , 0
  4416.9     .07       0  4683.9     .12       0  4716.4     .07       0
  4883.7      .1       0  4990.3     .05       0    5056      .1       0
  5240.3     .12       0  5586.6     .07       0
Bank Sta=4990.3,5056
XS Rating Curve= 0 ,0
Exp/Cntr=0.3,0.1

Type RM Length L Ch R = 1 ,10028   ,695,695,695
BEGIN DESCRIPTION:
ALLIGATOR CREEK 13.0
END DESCRIPTION:
XS GIS Cut Line= 3
      2311824.99       13753125.        2311325.       13753425.
      2310425.04     13753624.99
#Sta/Elev= 30
  4412.7  491.88    4487  489.98  4537.1  475.18    4574  470.24  4762.5  458.46
  4804.6  458.27  4871.4  452.03  4951.1   451.7  4959.9  442.58  4961.4  441.58
  5025.8  442.58  5026.5  449.35  5039.2  452.74  5118.7  452.51  5149.5   458.9
  5190.4  461.02  5221.2  467.71  5241.6  462.93  5264.6  462.47  5354.3   462.6
  5384.9  467.33  5405.5  463.06    5508  462.27  5558.8  467.97  5573.3  465.48
  5641.2  465.65  5671.9  471.69  5727.3  473.87  5853.9   479.5  5917.7   482.3
#Mann= 12 ,-1 , 0
  4412.7     .07       0    4487     .12       0  4804.6      .1       0
  4959.9     .05       0  5025.8      .1       0  5039.2     .12       0
  5149.5     .05       0  5264.6     .07       0  5384.9     .05       0
  5558.8     .07       0  5727.3     .05       0  5853.9     .12       0
Bank Sta=4959.9,5025.8
XS Rating Curve= 0 ,0
Exp/Cntr=0.3,0.1

Type RM Length L Ch R = 1 ,9333    ,732,732,732
BEGIN DESCRIPTION:
ALLIGATOR CREEK 12.0
END DESCRIPTION:
XS GIS Cut Line= 3
      2311924.97       13752825.        2311425.       13752825.
      2310525.03     13753424.98
#Sta/Elev= 30
  4504.6  499.48  4944.6  449.59  4951.6  439.36  4953.1  438.36  5017.5  439.36
  5027.1  448.86  5033.1  440.19  5048.1  453.65    5063  454.71  5069.2  452.85
  5145.2  457.55  5183.7  457.85  5342.6   461.7  5365.1  467.71  5408.7  461.13
  5486.2  461.13  5537.9   461.8  5552.9  467.04  5567.9  467.53    5604  462.27
  5655.1  462.04  5697.1  462.61  5718.2  467.54  5748.2  468.96  5787.3  466.04
  5825.1  466.15  5883.4  466.76    5908  471.83  5964.5  470.77  6086.2  477.06
#Mann= 11 ,-1 , 0
  4504.6     .12       0  4951.6     .05       0  5017.5     .12       0
    5063     .07       0  5145.2      .1       0  5183.7     .05       0
  5486.2     .12       0  5655.1     .07       0  5787.3     .12       0
  5825.1     .07       0    5908     .05       0
Bank Sta=4951.6,5017.5
XS Rating Curve= 0 ,0
Exp/Cntr=0.3,0.1

Type RM Length L Ch R = 1 ,8601    ,695,695,695
BEGIN DESCRIPTION:
ALLIGATOR CREEK 11.0
END DESCRIPTION:
XS GIS Cut Line= 3
        2312025.       13752225.        2311525.       13752125.
      2309513.43     13752094.67
#Sta/Elev= 30
  4490.2   494.8    4582   478.9  4652.7  484.66  4673.8  489.23  4714.6  479.23
  4928.7   458.4  4949.1  451.07    4957  439.92  4958.5  438.92  5022.9  439.92
  5090.1  452.53  5225.5  457.53  5380.1  466.83  5470.2  460.29  5560.2  467.91
  5600.2  461.63  5710.2  461.98  5740.2  467.86  5780.2  461.39  5880.2  461.56
  5920.2  468.04  5950.2  462.12  6100.2  468.82    6123  463.75  6240.2  463.66
  6270.2  469.62  6348.2  463.98  6690.3  470.27  6865.6  481.53  7011.9  490.34
#Mann= 8 ,-1 , 0
  4490.2     .07       0  4652.7     .12       0    4957     .05       0
  5022.9     .12       0  5225.5     .05       0    6123     .07       0
  6348.2     .05       0  6865.6      .1       0
Bank Sta=4957,5022.9
XS Rating Curve= 0 ,0
Exp/Cntr=0.3,0.1