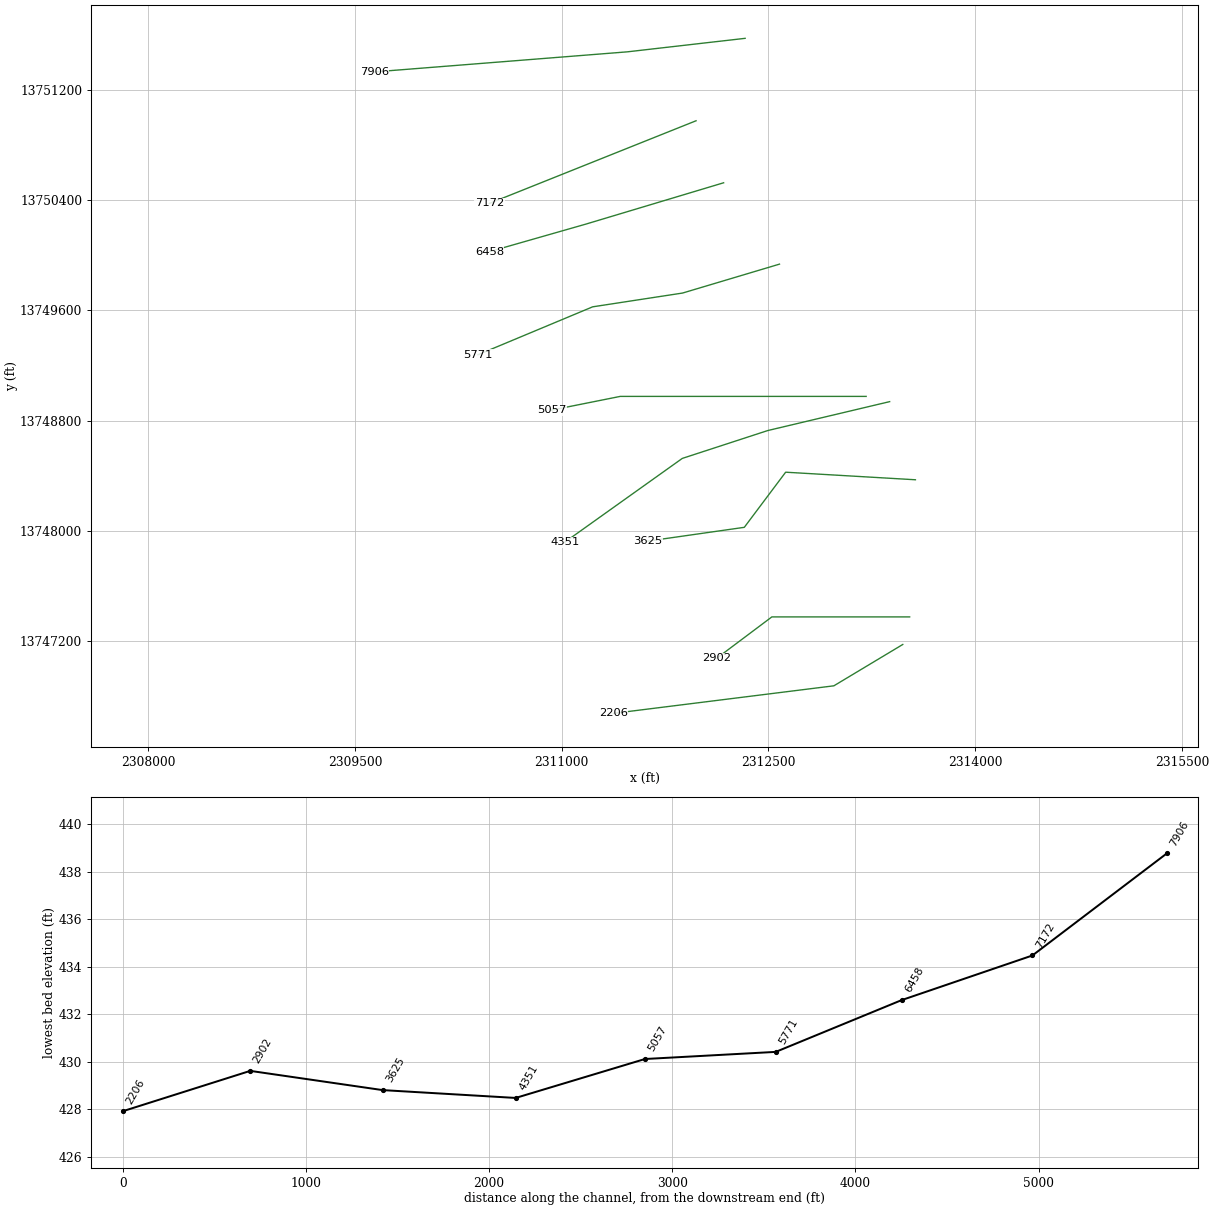
HEC-RAS study GERONIMO CREEK.prj: GERONIMO CREEK Base Level Engineering

--- GERONIMO CREEK.g01 (geometry) --- (continued)

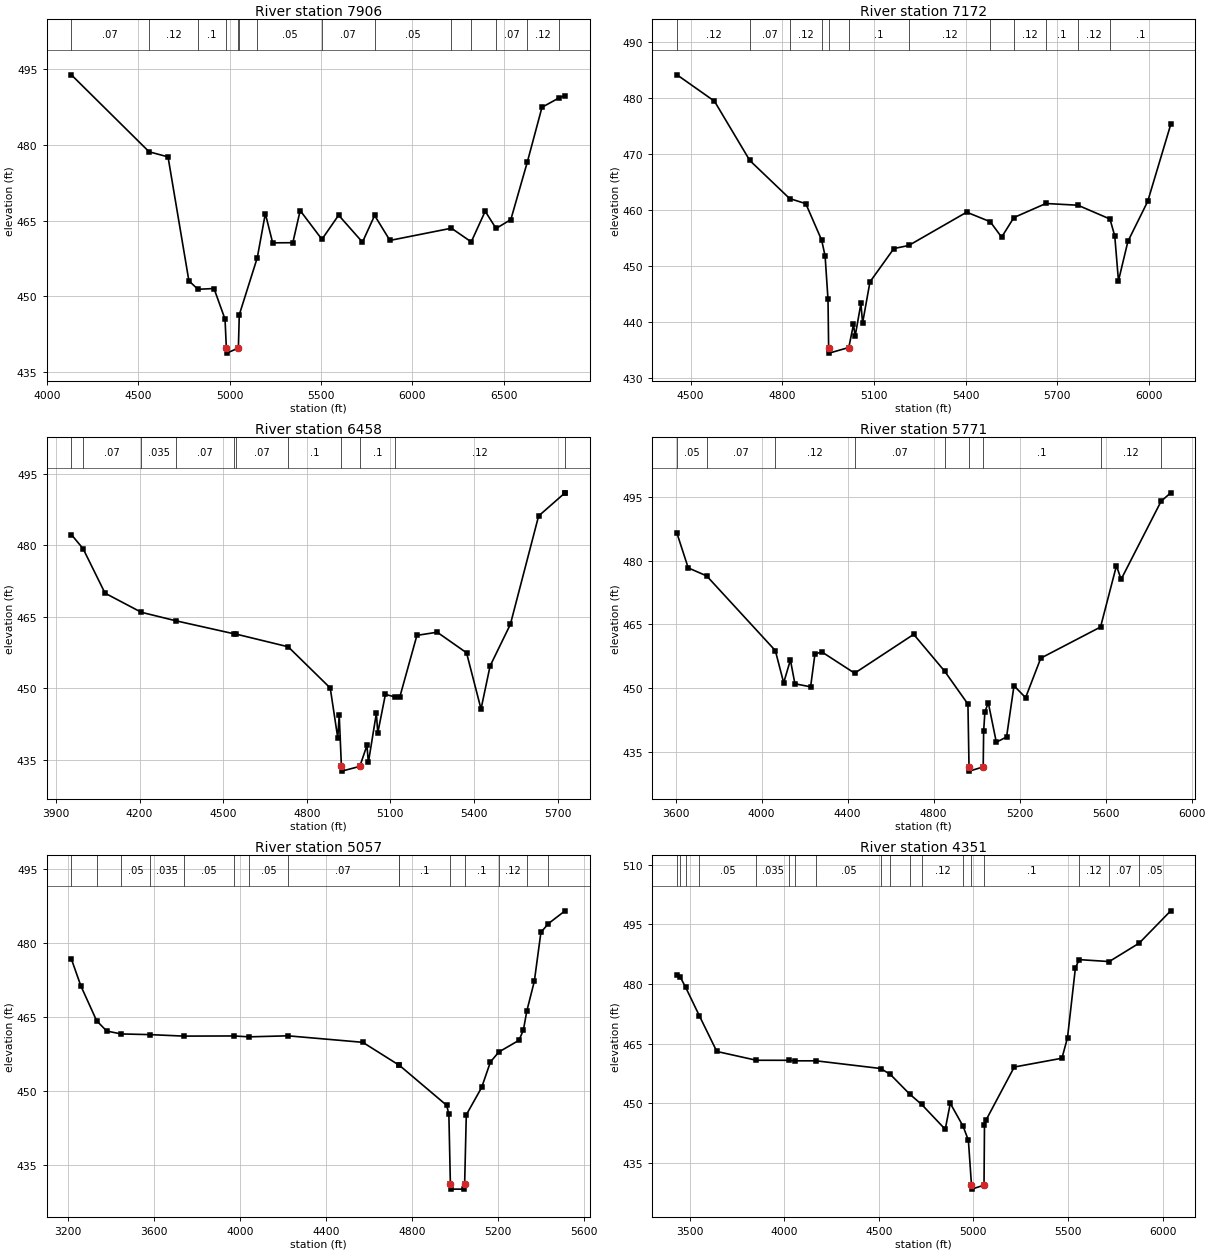
Type RM Length L Ch R = 1 ,7906    ,734,734,734
BEGIN DESCRIPTION:
ALLIGATOR CREEK 10.0
END DESCRIPTION:
XS GIS Cut Line= 3
      2312330.99     13751573.12        2311475.       13751475.
      2309639.06     13751329.42
#Sta/Elev= 30
  4133.6  493.92  4559.4  478.67    4663  477.66  4777.2   453.1  4826.6  451.43
  4914.7  451.58  4975.1   445.5  4982.3  439.78  4983.8  438.78  5048.2  439.78
  5053.1  446.37  5151.7  457.69  5195.8  466.43  5235.9  460.63  5346.3  460.66
  5386.4  467.03  5505.6  461.33  5597.1  466.11  5727.5  460.77  5794.2  466.05
    5878  461.11  6214.7  463.53  6323.2  460.82  6399.6  466.89  6459.2  463.48
    6540  465.24  6629.9  476.59  6710.6  487.49    6804  489.35  6836.9  489.81
#Mann= 14 ,-1 , 0
  4133.6     .07       0  4559.4     .12       0  4826.6      .1       0
  4982.3     .05       0  5048.2      .1       0  5053.1     .07       0
  5151.7     .05       0  5505.6     .07       0  5794.2     .05       0
  6214.7     .07       0  6323.2     .05       0  6459.2     .07       0
  6629.9     .12       0    6804     .07       0
Bank Sta=4982.3,5048.2
XS Rating Curve= 0 ,0
Exp/Cntr=0.3,0.1

Type RM Length L Ch R = 1 ,7172    ,714,714,714
BEGIN DESCRIPTION:
ALLIGATOR CREEK 9.0
END DESCRIPTION:
XS GIS Cut Line= 3
      2311974.98     13750974.99        2311475.       13750775.
      2310475.03     13750375.01
#Sta/Elev= 30
  4455.8  484.12  4578.3  479.42    4694  468.84  4824.3  462.05  4877.2  461.14
  4929.1  454.63  4940.4   451.8  4949.9  444.05  4951.9  435.48  4953.4  434.48
  5017.9  435.48  5033.3   439.6  5038.7  437.49  5057.6  443.35    5063  439.83
  5087.2  447.19  5165.3  453.13    5214  453.68  5403.6  459.62  5480.7  457.92
    5518  455.16    5558  458.66  5662.9  461.17  5767.7  460.86  5872.5   458.4
  5888.2  455.37  5900.3  447.38  5931.3  454.42  5995.9  461.53  6071.3  475.26
#Mann= 12 ,-1 , 0
  4455.8     .12       0    4694     .07       0  4824.3     .12       0
  4929.1      .1       0  4951.9     .05       0  5017.9      .1       0
    5214     .12       0  5480.7     .07       0    5558     .12       0
  5662.9      .1       0  5767.7     .12       0  5872.5      .1       0
Bank Sta=4951.9,5017.9
XS Rating Curve= 0 ,0
Exp/Cntr=0.3,0.1

Type RM Length L Ch R = 1 ,6458    ,687,687,687
BEGIN DESCRIPTION:
ALLIGATOR CREEK 8.0
END DESCRIPTION:
XS GIS Cut Line= 3
        2312175.       13750525.        2311175.       13750225.
      2310475.04     13750025.01
#Sta/Elev= 30
  3955.1  482.29  3997.1  479.34    4076  469.98  4206.1  465.97    4331  464.17
  4539.5  461.44  4544.4  461.41  4733.3  458.72  4884.3  450.06  4911.3  439.58
  4916.5  444.38  4924.4   433.6  4925.9   432.6  4990.4   433.6    5016  437.99
  5021.2  434.42  5049.8  444.73    5055  440.64  5082.3  448.72  5117.7  448.17
  5134.3  448.24  5195.4  461.12  5268.2  461.78  5373.5  457.46  5425.5  445.64
    5458  454.68  5530.8  463.43  5632.2   486.2    5727  491.06  5727.1  491.06
#Mann= 11 ,-1 , 0
  3955.1     .12       0  3997.1     .07       0  4206.1    .035       0
    4331     .07       0  4539.5    .035       0  4544.4     .07       0
  4733.3      .1       0  4924.4     .05       0  4990.4      .1       0
  5117.7     .12       0    5727     .05       0
Bank Sta=4924.4,4990.4
XS Rating Curve= 0 ,0
Exp/Cntr=0.3,0.1

Type RM Length L Ch R = 1 ,5771    ,714,714,714
BEGIN DESCRIPTION:
ALLIGATOR CREEK 7.0
END DESCRIPTION:
XS GIS Cut Line= 4
      2312580.37     13749934.74      2311877.42     13749724.99
        2311225.       13749625.      2310392.14     13749277.14
#Sta/Elev= 30
  3606.4  486.44  3658.5  478.31  3744.2  476.43  4063.7  458.82  4102.5  451.23
  4133.8  456.61  4154.7  451.01  4227.7  450.28  4247.9  458.01  4279.9  458.51
  4432.5   453.5  4707.3  462.65  4850.8  453.99  4959.5  446.21  4964.5  431.42
    4966  430.42  5030.5  431.42  5032.5   439.8  5038.4  444.41  5054.2  446.53
  5091.5  437.23  5139.1  438.47  5173.7  450.54  5227.6  447.73  5298.2  457.04
  5576.2  464.38  5650.2  478.82  5671.9  475.61  5857.8  494.01  5902.6     496
#Mann= 9 ,-1 , 0
  3606.4     .05       0  3744.2     .07       0  4063.7     .12       0
  4432.5     .07       0  4850.8      .1       0  4964.5     .05       0
  5030.5      .1       0  5576.2     .12       0  5857.8     .07       0
Bank Sta=4964.5,5030.5
XS Rating Curve= 0 ,0
Exp/Cntr=0.3,0.1

Type RM Length L Ch R = 1 ,5057    ,706,706,706
BEGIN DESCRIPTION:
ALLIGATOR CREEK 6.0
END DESCRIPTION:
XS GIS Cut Line= 4
      2313209.11       13748975.        2311925.       13748975.
        2311425.       13748975.      2310925.02       13748875.
#Sta/Elev= 30
  3216.2  476.75  3260.3   471.3  3333.6  464.24  3380.3  462.15  3447.2  461.56
    3582  461.42  3738.5  461.12  3971.5  461.15    4042  460.97  4222.1  461.18
  4570.3  459.86  4737.6  455.27  4739.7  455.23  4960.3  447.09  4970.3  445.28
  4977.4  431.12  4978.9  430.12  5042.1  430.12  5043.6  431.12  5051.3  445.17
  5122.7  450.72  5163.5  455.89  5202.8  457.91  5296.1  460.27  5316.5  462.35
    5333   466.3  5367.4  472.22    5398  482.14  5432.8  483.91  5510.2   486.5
#Mann= 15 ,-1 , 0
  3216.2     .05       0  3333.6    .035       0  3447.2     .05       0
    3582    .035       0  3738.5     .05       0  3971.5    .035       0
    4042     .05       0  4222.1     .07       0  4737.6     .12       0
  4739.7      .1       0  4977.4     .05       0  5043.6      .1       0
  5202.8     .12       0    5333      .1       0  5432.8     .12       0
Bank Sta=4977.4,5043.6
XS Rating Curve= 0 ,0
Exp/Cntr=0.3,0.1

Type RM Length L Ch R = 1 ,4351    ,726,726,726
BEGIN DESCRIPTION:
ALLIGATOR CREEK 5.0
END DESCRIPTION:
XS GIS Cut Line= 4
      2313379.74     13748936.98      2312495.35     13748727.22
        2311875.       13748525.      2311021.37     13747916.53
#Sta/Elev= 30
  3433.5  482.25  3451.1  481.72  3478.7  479.24  3551.4  472.06  3643.9  463.07
  3852.9  460.86  4028.1  460.85  4059.3  460.72  4168.9  460.72  4509.6  458.79
  4560.8  457.32  4663.3  452.36    4727  449.75  4851.3  443.51    4878  450.04
  4945.9  444.26  4973.7  440.75  4990.1  429.48  4991.6  428.48  5056.3  429.48
  5058.8  444.69  5067.4  445.87  5216.2  459.16  5468.2  461.37  5497.7  466.56
  5539.5   484.1  5559.6  486.15  5718.1  485.66  5876.5  490.29  6043.2  498.41
#Mann= 18 ,-1 , 0
  3433.5    .035       0  3451.1     .05       0  3478.7     .07       0
  3551.4     .05       0  3852.9    .035       0  4028.1     .05       0
  4059.3    .035       0  4168.9     .05       0  4509.6     .07       0
  4560.8     .05       0  4663.3     .07       0    4727     .12       0
  4945.9      .1       0  4990.1     .05       0  5056.3      .1       0
  5559.6     .12       0  5718.1     .07       0  5876.5     .05       0
Bank Sta=4990.1,5056.3
XS Rating Curve= 0 ,0
Exp/Cntr=0.3,0.1

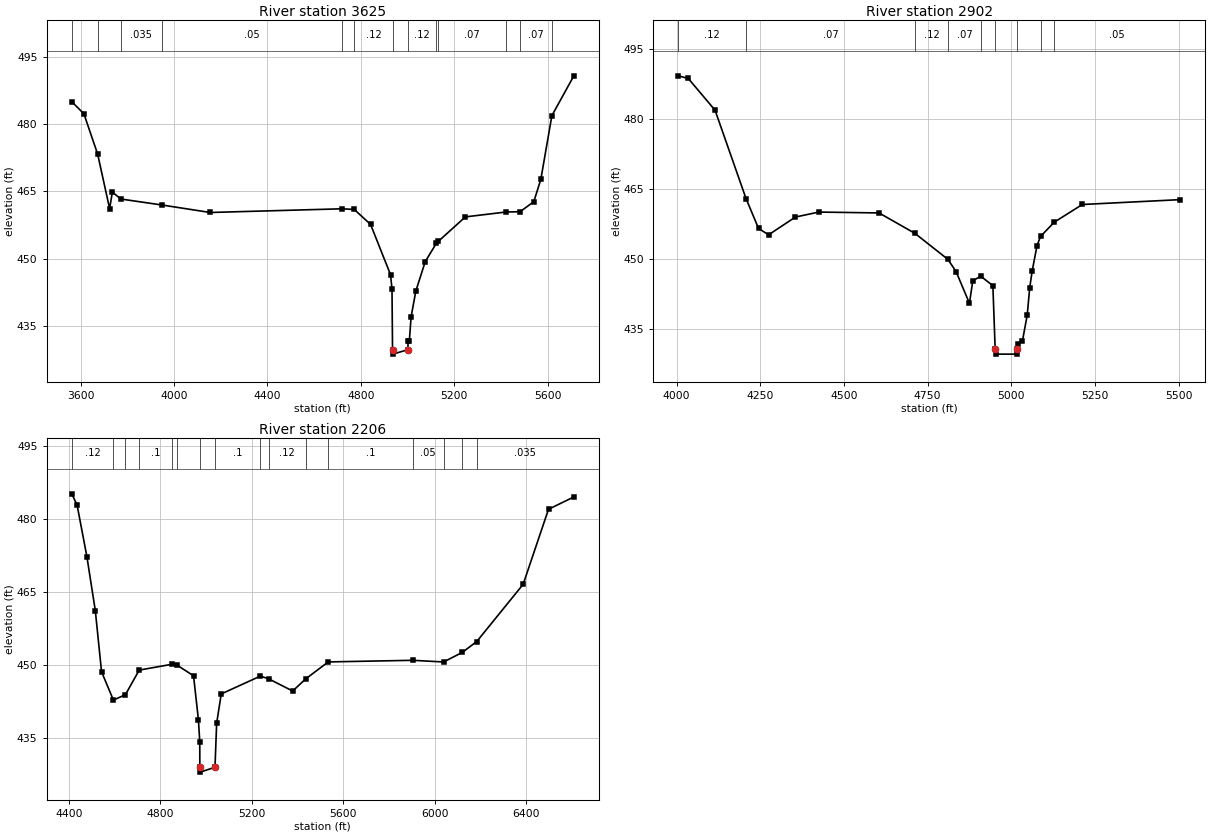
Type RM Length L Ch R = 1 ,3625    ,723,723,723
BEGIN DESCRIPTION:
ALLIGATOR CREEK 4.0
END DESCRIPTION:
XS GIS Cut Line= 4
      2313566.83     13748370.07        2312625.       13748425.
        2312325.       13748025.      2311625.04     13747925.01
#Sta/Elev= 30
  3562.1  484.96    3614  482.28    3673  473.29  3724.2  461.17  3735.9  464.84
  3772.9  463.31  3947.8  461.99  4154.9  460.32  4719.5  461.14    4772     461
    4842  457.66  4927.4  446.48  4933.7  443.31    4936  429.81  4937.5  428.81
  5002.2  429.81  5002.4  431.83  5008.1  431.83  5015.6  437.13  5035.8  442.84
  5076.2  449.41  5123.2  453.42  5132.1   453.9    5248  459.34  5423.1  460.43
  5482.1  460.49  5540.9  462.71  5571.2  467.68  5618.5  481.86  5712.6  490.72
#Mann= 13 ,-1 , 0
  3562.1    .035       0    3673     .07       0  3772.9    .035       0
  3947.8     .05       0  4719.5     .07       0    4772     .12       0
    4936     .05       0  5002.2     .12       0  5123.2     .12       0
  5132.1     .07       0  5423.1     .05       0  5482.1     .07       0
  5618.5     .12       0
Bank Sta=4936,5002.2
XS Rating Curve= 0 ,0
Exp/Cntr=0.3,0.1

Type RM Length L Ch R = 1 ,2902    ,696,696,696
BEGIN DESCRIPTION:
ALLIGATOR CREEK 3.0
END DESCRIPTION:
XS GIS Cut Line= 3
      2313525.04       13747375.        2312525.       13747375.
      2312125.03     13747075.02
#Sta/Elev= 30
    4005  489.21    4035  488.64    4115  481.85  4207.5  462.93    4245  456.53
    4275  455.17    4355  458.97    4425  460.04    4605  459.85  4712.1  455.48
  4810.6  449.91    4835  447.31    4875   440.5    4885  445.34    4909  446.29
    4945  444.28  4951.9  430.62  4953.4  429.62  5016.7  429.62  5018.2  430.62
  5018.6  431.79  5033.2  432.39  5047.7  438.01    5055  443.79  5062.3  447.37
  5076.9  452.85  5087.3  454.81  5128.5  457.88  5212.3  461.66    5505   462.7
#Mann= 9 ,-1 , 0
    4005     .12       0  4207.5     .07       0  4712.1     .12       0
  4810.6     .07       0    4909     .12       0  4951.9     .05       0
  5018.2     .12       0  5087.3     .12       0  5128.5     .05       0
Bank Sta=4951.9,5018.2
XS Rating Curve= 0 ,0
Exp/Cntr=0.3,0.1

Type RM Length L Ch R = 1 ,2206    ,0,0,0
BEGIN DESCRIPTION:
ALLIGATOR CREEK 2.0
END DESCRIPTION:
XS GIS Cut Line= 3
      2313474.97     13747174.98        2312975.       13746875.
      2311375.01       13746675.
#Sta/Elev= 30
  4412.8  485.09  4436.1  482.78  4478.9   472.2  4515.8  461.07    4543  448.55
  4594.8  442.72  4647.4  443.83  4707.7  448.88  4852.8  450.09  4871.2  449.96
  4945.3  447.71  4966.7  438.65  4972.5  434.07  4972.8  428.92  4974.3  427.92
  5039.1  428.92  5046.3  437.94  5066.4  443.98  5237.7  447.65  5274.4  447.07
  5378.8  444.58  5435.4  447.06  5534.3  450.56  5902.8  450.89  6038.8  450.55
  6120.3  452.51  6183.7  454.75  6386.6   466.5  6497.5  481.92  6608.3  484.45
#Mann= 16 ,-1 , 0
  4412.8     .12       0  4594.8      .1       0  4647.4     .07       0
  4707.7      .1       0  4852.8     .07       0  4871.2      .1       0
  4972.8     .05       0  5039.1      .1       0  5237.7     .07       0
  5274.4     .12       0  5435.4     .07       0  5534.3      .1       0
  5902.8     .05       0  6038.8     .07       0  6120.3     .05       0
  6183.7    .035       0
Bank Sta=4972.8,5039.1
XS Rating Curve= 0 ,0
Exp/Cntr=0.3,0.1

Chan Stop Cuts=-1
Use User Specified Reach Order=0
Composite Channel Slope=5