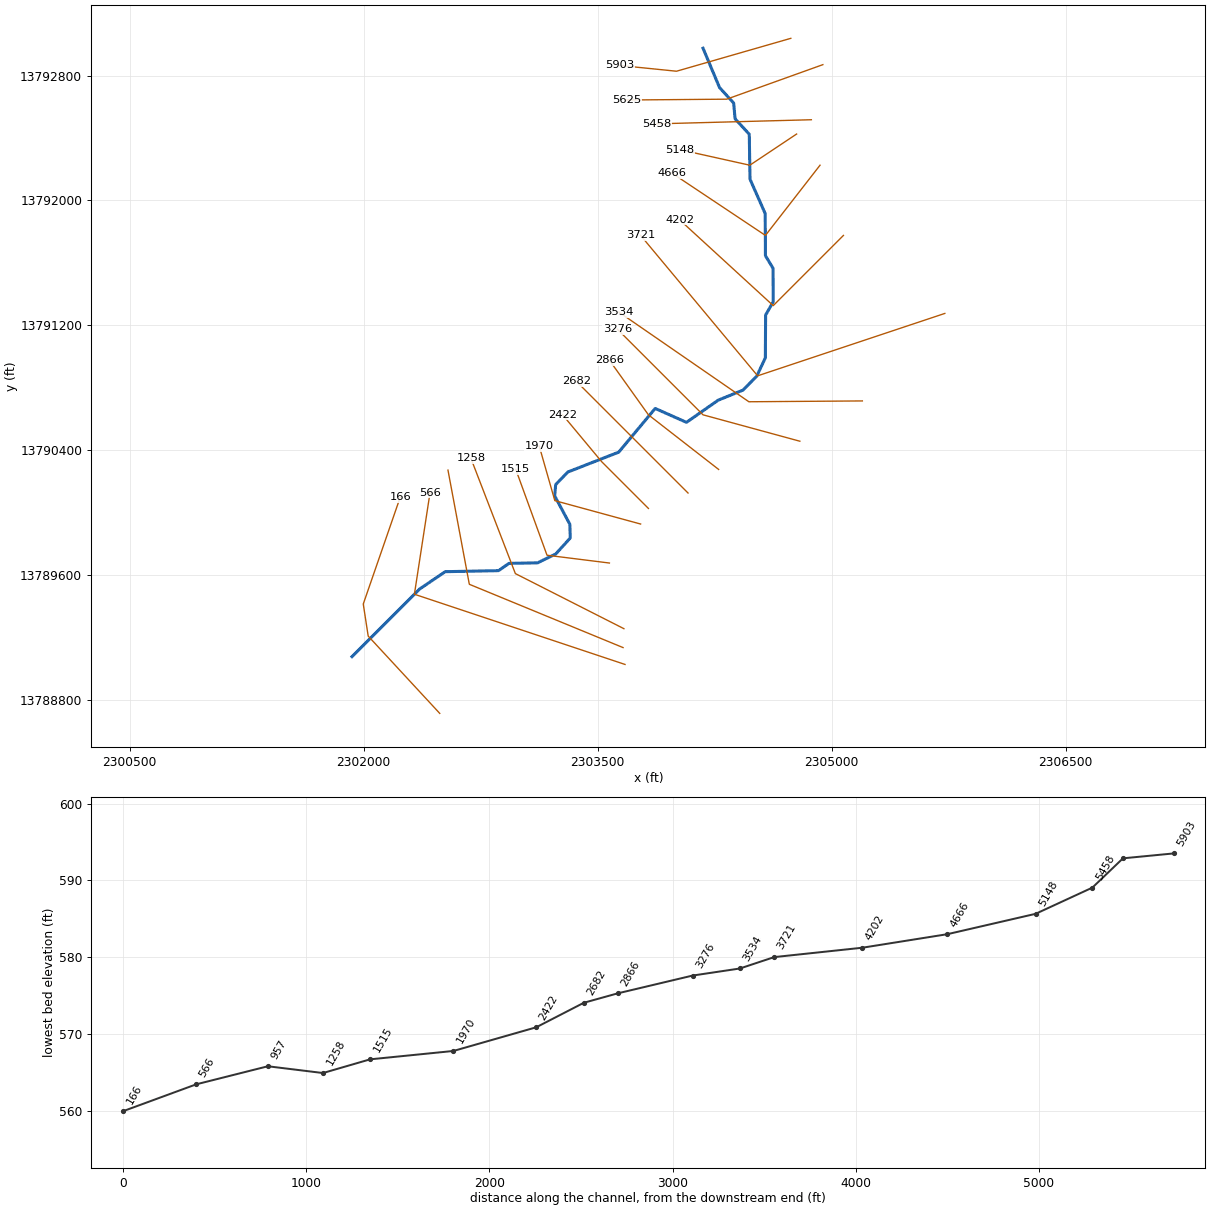
--- GERONIMO TRIBUTARY 10.prj (project) ---

Proj Title=GERONIMO TRIBUTARY 10 Base Level Engineering
Current Plan=p01
Default Exp/Contr=0.3,0.1
English Units
Geom File=g01
Flow File=f01
Plan File=p01
BEGIN DESCRIPTION:
GERONIMO TRIBUTARY 10
END DESCRIPTION:

--- GERONIMO TRIBUTARY 10.p01 (plan) ---

Plan Title=Multiple Run
Short Identifier=Multiple
Geom File=g01
Flow File=f01
Subcritical Flow
K Sum by GR= 0
Std Step Tol= 0.01
Critical Tol= 0.01
Num of Std Step Trials= 20
Max Error Tol= 0.3
Flow Tol Ratio= 0.001
Split Flow NTrial= 30
Split Flow Tol= 0.02
Split Flow Ratio= 0.02
Log Output Level= 0
Friction Slope Method= 1
Unsteady Friction Slope Method= 2
Unsteady Bridges Friction Slope Method= 1
Parabolic Critical Depth
Global Vel Dist=  1 , 1 , 1
Global Log Level= 0
CheckData=True
Encroach Param= -1, 0, 0, 0
BEGIN DESCRIPTION:
Multiple Run
END DESCRIPTION:

--- GERONIMO TRIBUTARY 10.f01 (steady flow) ---

Flow Title=Multiple
Number of Profiles=7
Profile Names=10-year,25-year,50-year,1pct_min,100-year,1pct_plu,500-year
River Rch & RM= GERONIMO TRIBUTA,Reach-1,5903
     456     719     952     610    1218    2430    1975
Boundary for River Rch & Prof#=GERONIMO TRIBUTA,Reach-1,1
Up Type=0
Dn Type=3
Dn Slope=0.005
Boundary for River Rch & Prof#=GERONIMO TRIBUTA,Reach-1,2
Up Type=0
Dn Type=3
Dn Slope=0.005
Boundary for River Rch & Prof#=GERONIMO TRIBUTA,Reach-1,3
Up Type=0
Dn Type=3
Dn Slope=0.005
Boundary for River Rch & Prof#=GERONIMO TRIBUTA,Reach-1,4
Up Type=0
Dn Type=3
Dn Slope=0.005
Boundary for River Rch & Prof#=GERONIMO TRIBUTA,Reach-1,5
Up Type=0
Dn Type=3
Dn Slope=0.005
Boundary for River Rch & Prof#=GERONIMO TRIBUTA,Reach-1,6
Up Type=0
Dn Type=3
Dn Slope=0.005
Boundary for River Rch & Prof#=GERONIMO TRIBUTA,Reach-1,7
Up Type=0
Dn Type=3
Dn Slope=0.005

--- GERONIMO TRIBUTARY 10.g01 (geometry) ---

Geom Title=Existing Conditions

River Reach=GERONIMO TRIBUTA,Reach-1
Reach XY= 30
      2304175.00     13792975.00      2304280.85     13792722.71
      2304371.37     13792623.50      2304380.54     13792522.58
      2304471.45     13792423.53      2304476.22     13792135.50
      2304573.78     13791914.50      2304575.07     13791645.03
      2304623.78     13791564.50      2304625.20     13791349.92
      2304576.22     13791264.50      2304574.49     13790990.21
      2304519.18     13790872.69      2304431.07     13790783.13
      2304272.71     13790719.15      2304068.89     13790576.79
      2303868.27     13790665.89      2303634.71     13790385.75
      2303308.29     13790258.37      2303230.39     13790177.44
      2303224.39     13790104.95      2303321.33     13789923.41
      2303324.07     13789835.47      2303231.08     13789733.13
      2303114.50     13789676.20      2302930.94     13789672.74
      2302864.50     13789626.22      2302522.55     13789619.53
      2302358.33     13789508.35      2301925.00     13789075.00

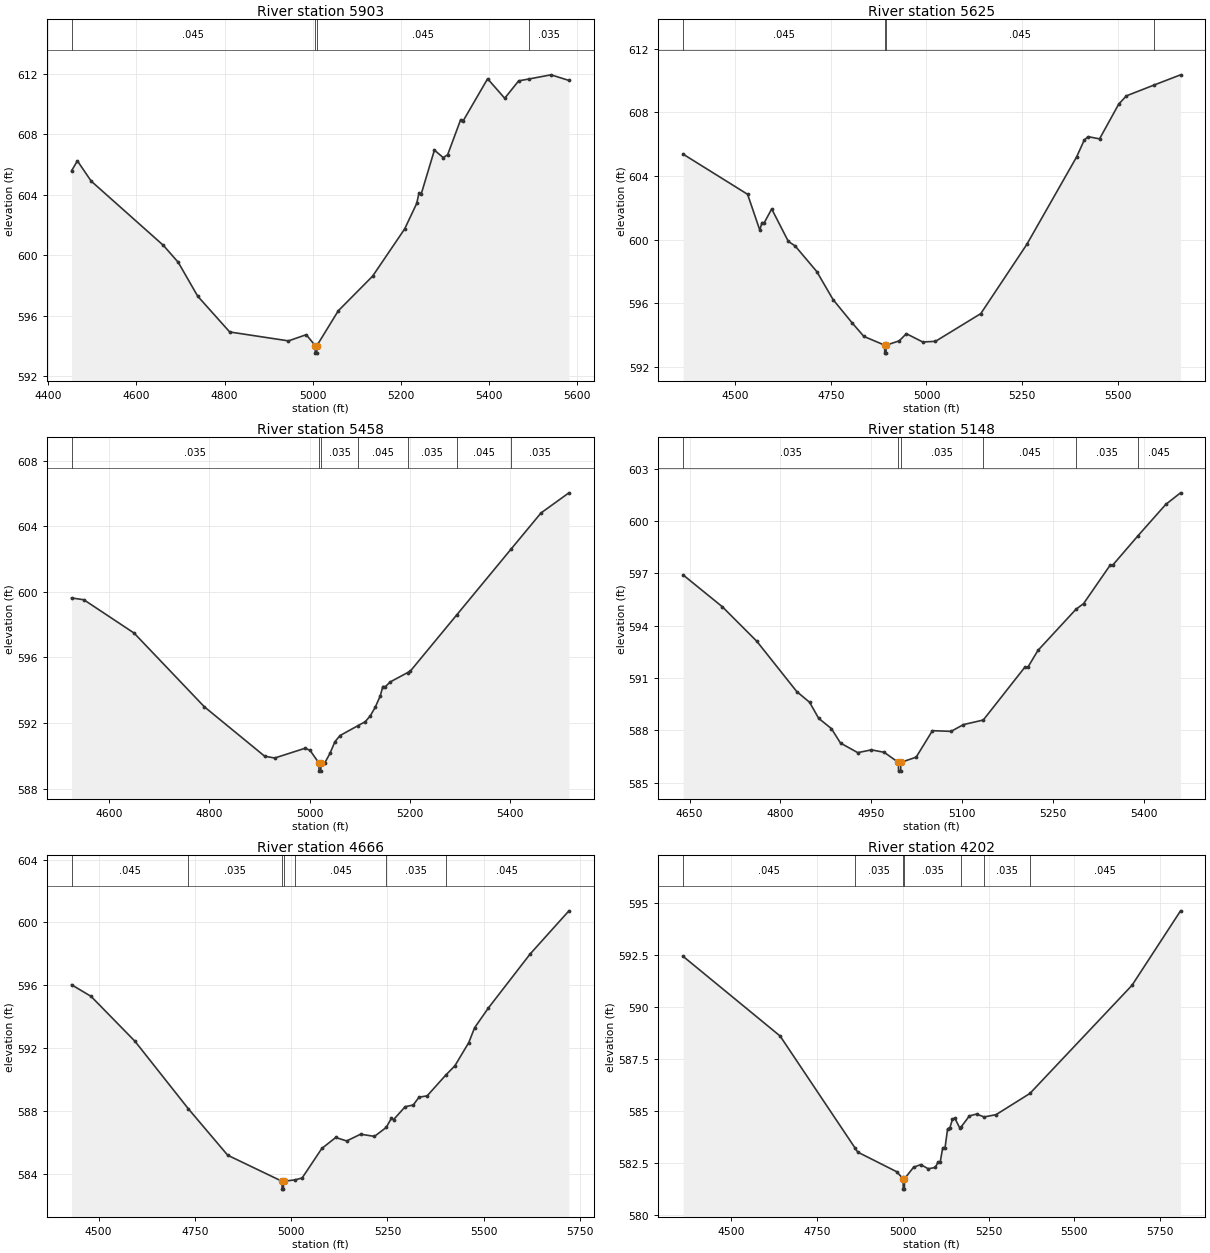
Type RM Length L Ch R = 1,5903,278,278,278
BEGIN DESCRIPTION:
A18970
END DESCRIPTION:
XS GIS Cut Line= 3
      2304737.74     13793038.25      2304005.16     13792827.43
      2303641.54     13792864.32
#Sta/Elev= 30
  4453.1  605.58  4466.4  606.24  4497.6  604.90  4661.3  600.65  4695.0  599.53
  4739.1  597.29  4811.7  594.92  4945.0  594.33  4985.3  594.74  5005.5  594.02
  5005.7  593.52  5009.2  593.52  5009.5  594.02  5057.9  596.32  5135.7  598.61
  5208.3  601.73  5235.7  603.42  5240.8  604.09  5245.8  604.03  5275.9  606.95
  5296.0  606.45  5306.0  606.65  5335.5  608.97  5340.6  608.86  5396.5  611.67
  5435.3  610.38  5466.9  611.53  5491.2  611.66  5540.2  611.93  5580.9  611.56
#Mann=4,-1,0
  4453.1   0.045       0  5005.5   0.045       0  5009.5   0.045       0
  5491.2   0.035       0
Bank Sta=5005.5,5009.5
Exp/Cntr=0.3,0.1

Type RM Length L Ch R = 1,5625,167,167,167
BEGIN DESCRIPTION:
GERONIMO TRIBUTARY 10 11.0
END DESCRIPTION:
XS GIS Cut Line= 3
      2304943.30     13792869.61      2304326.64     13792648.24
      2303683.65     13792642.97
#Sta/Elev= 30
  4364.9  605.37  4533.1  602.85  4565.0  600.60  4570.6  601.08  4575.9  601.04
  4596.0  601.93  4639.3  599.90  4657.5  599.60  4713.7  598.00  4756.2  596.24
  4805.9  594.78  4836.6  593.93  4890.8  593.38  4891.0  592.88  4894.5  592.88
  4894.8  593.38  4928.8  593.65  4947.5  594.10  4990.3  593.58  5023.4  593.62
  5141.7  595.36  5261.7  599.70  5391.7  605.19  5411.7  606.25  5421.7  606.47
  5451.7  606.33  5501.7  608.51  5521.7  609.03  5594.1  609.71  5663.1  610.35
#Mann=4,-1,0
  4364.9   0.045       0  4890.8   0.045       0  4894.8   0.045       0
  5594.1   0.035       0
Bank Sta=4890.8,4894.8
Exp/Cntr=0.3,0.1

Type RM Length L Ch R = 1,5458,310,310,310
BEGIN DESCRIPTION:
A18971
END DESCRIPTION:
XS GIS Cut Line= 2
      2304869.46     13792516.49      2303879.31     13792490.15
#Sta/Elev= 30
  4526.0  599.63  4550.5  599.52  4650.5  597.49  4790.6  592.99  4910.6  589.98
  4930.6  589.87  4990.6  590.46  5000.6  590.35  5018.6  589.57  5018.9  589.07
  5022.4  589.07  5022.6  589.57  5030.6  589.59  5040.6  590.15  5050.6  590.87
  5060.7  591.24  5096.8  591.85  5110.7  592.08  5120.7  592.43  5130.7  592.96
  5140.7  593.65  5145.9  594.23  5150.9  594.22  5160.7  594.51  5195.3  595.08
  5200.7  595.17  5293.7  598.62  5402.1  602.64  5460.8  604.81  5516.5  606.04
#Mann=7,-1,0
  4526.0   0.035       0  5018.6   0.035       0  5022.6   0.035       0
  5096.8   0.045       0  5195.3   0.035       0  5293.7   0.045       0
  5402.1   0.035       0
Bank Sta=5018.6,5022.6
Exp/Cntr=0.3,0.1

Type RM Length L Ch R = 1,5148,482,482,482
BEGIN DESCRIPTION:
GERONIMO TRIBUTARY 10 10.0
END DESCRIPTION:
XS GIS Cut Line= 3
      2304774.96     13792424.98      2304475.00     13792225.00
      2304024.99     13792325.00
#Sta/Elev= 30
  4639.4  596.91  4704.0  595.09  4761.0  593.11  4827.1  590.22  4848.2  589.61
  4863.2  588.69  4884.2  588.10  4899.3  587.27  4927.8  586.72  4950.3  586.88
  4971.4  586.74  4994.9  586.16  4995.2  585.66  4998.7  585.66  4998.9  586.16
  5024.2  586.46  5051.1  587.98  5081.9  587.94  5102.4  588.33  5135.1  588.59
  5203.5  591.61  5208.6  591.61  5225.3  592.58  5288.1  594.94  5300.8  595.27
  5344.4  597.46  5349.5  597.50  5390.9  599.17  5436.6  600.96  5460.9  601.62
#Mann=6,-1,0
  4639.4   0.035       0  4994.9   0.035       0  4998.9   0.035       0
  5135.1   0.045       0  5288.1   0.035       0  5390.9   0.045       0
Bank Sta=4994.9,4998.9
Exp/Cntr=0.3,0.1

Type RM Length L Ch R = 1,4666,464,464,464
BEGIN DESCRIPTION:
GERONIMO TRIBUTARY 10 9.0
END DESCRIPTION:
XS GIS Cut Line= 3
      2304925.00     13792225.01      2304575.00     13791775.00
      2303975.00     13792175.00
#Sta/Elev= 30
  4429.9  596.03  4480.6  595.29  4594.6  592.43  4733.4  588.12  4835.3  585.17
  4976.3  583.51  4976.5  583.01  4980.0  583.01  4980.3  583.51  5010.1  583.60
  5028.5  583.72  5079.6  585.60  5115.7  586.30  5144.2  586.08  5180.3  586.51
  5216.3  586.37  5246.8  586.94  5259.9  587.51  5265.9  587.44  5296.0  588.26
  5317.0  588.37  5332.0  588.87  5353.0  588.95  5400.8  590.26  5425.1  590.87
  5461.2  592.35  5476.2  593.29  5512.3  594.56  5620.4  597.99  5721.1  600.74
#Mann=7,-1,0
  4429.9   0.045       0  4733.4   0.035       0  4976.3   0.035       0
  4980.3   0.035       0  5010.1   0.045       0  5246.8   0.035       0
  5400.8   0.045       0
Bank Sta=4976.3,4980.3
Exp/Cntr=0.3,0.1

Type RM Length L Ch R = 1,4202,481,481,481
BEGIN DESCRIPTION:
GERONIMO TRIBUTARY 10 8.0
END DESCRIPTION:
XS GIS Cut Line= 3
      2305074.97     13791774.97      2304625.00     13791325.00
      2304024.99     13791875.01
#Sta/Elev= 30
  4359.2  592.44  4642.0  588.61  4860.7  583.22  4868.3  583.03  4981.4  582.09
  5000.6  581.75  5000.9  581.25  5004.4  581.25  5004.6  581.75  5031.0  582.30
  5052.0  582.43  5073.6  582.23  5094.5  582.29  5101.9  582.54  5108.7  582.55
  5116.1  583.24  5122.9  583.25  5130.3  584.15  5137.1  584.21  5144.5  584.61
  5151.2  584.67  5165.4  584.20  5169.3  584.23  5193.8  584.77  5214.8  584.86
  5236.6  584.72  5271.5  584.83  5370.3  585.85  5668.0  591.05  5809.5  594.63
#Mann=7,-1,0
  4359.2   0.045       0  4860.7   0.035       0  5000.6   0.035       0
  5004.6   0.035       0  5169.3   0.045       0  5236.6   0.035       0
  5370.3   0.045       0
Bank Sta=5000.6,5004.6
Exp/Cntr=0.3,0.1

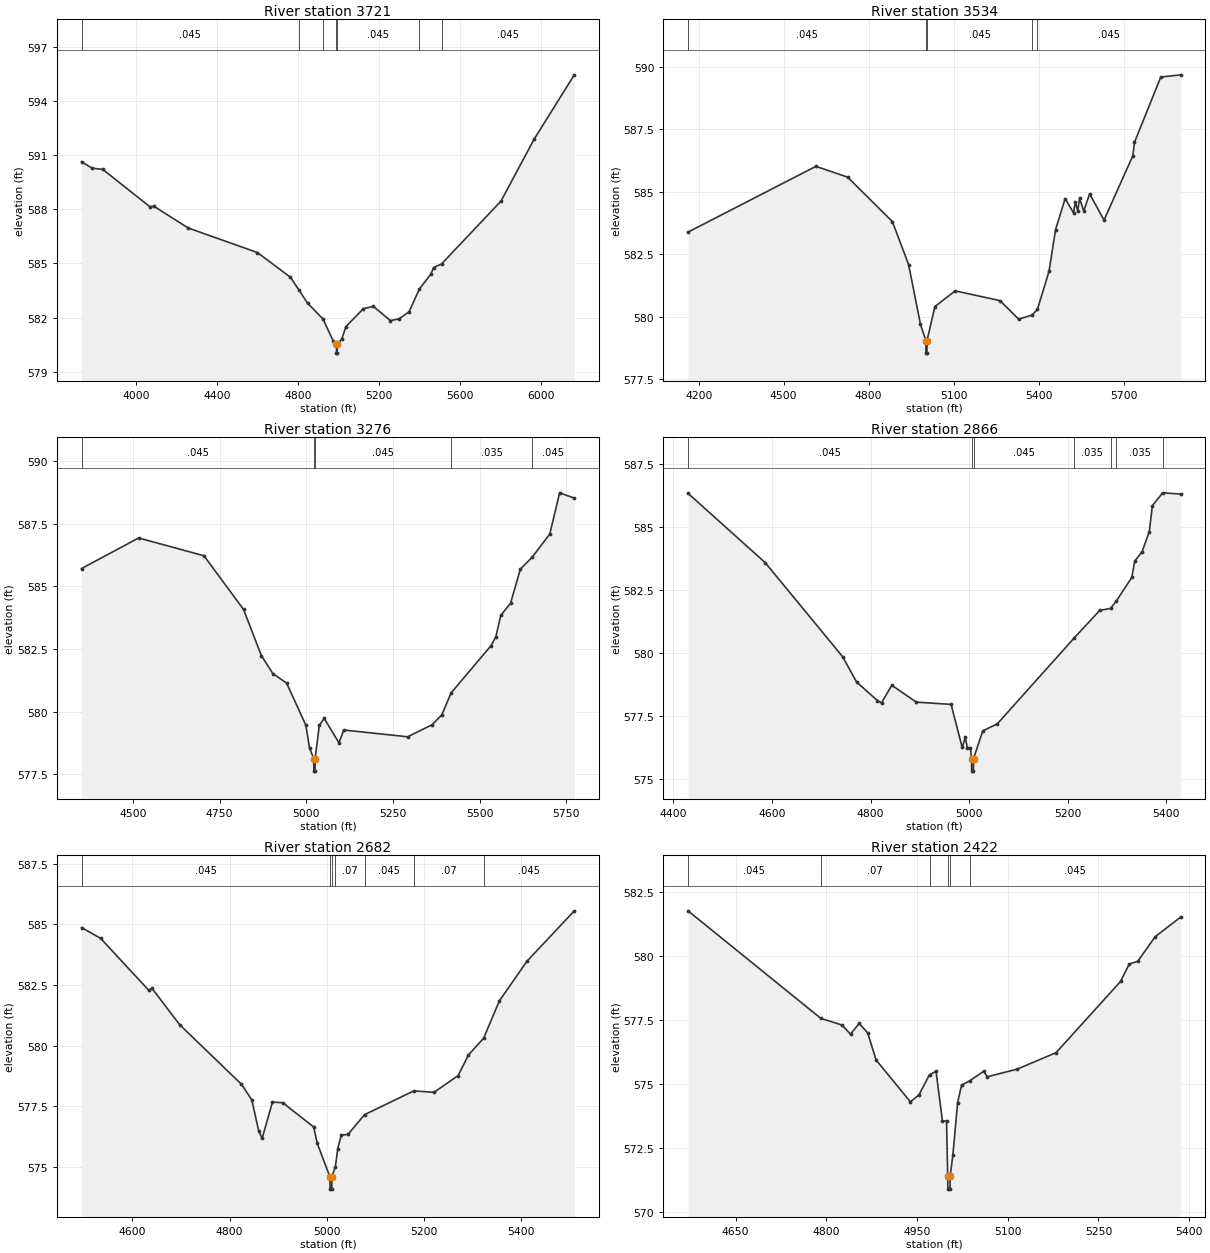
Type RM Length L Ch R = 1,3721,187,187,187
BEGIN DESCRIPTION:
GERONIMO TRIBUTARY 10 7.0
END DESCRIPTION:
XS GIS Cut Line= 3
      2305724.98     13791274.99      2304525.00     13790875.00
      2303775.02     13791774.98
#Sta/Elev= 30
  3730.1  590.62  3782.8  590.27  3835.5  590.20  4067.4  588.14  4088.5  588.16
  4257.1  586.96  4599.7  585.60  4763.1  584.23  4805.7  583.51  4847.4  582.80
  4923.7  581.92  4973.9  580.72  4990.4  580.53  4990.6  580.03  4994.1  580.03
  4994.4  580.53  5016.5  580.80  5037.3  581.50  5123.2  582.49  5172.7  582.62
  5257.3  581.83  5300.2  581.93  5349.7  582.32  5400.8  583.59  5456.4  584.39
  5470.8  584.77  5510.2  584.97  5804.0  588.45  5968.0  591.88  6166.5  595.44
#Mann=7,-1,0
  3730.1   0.045       0  4805.7   0.035       0  4923.7   0.045       0
  4990.4   0.045       0  4994.4   0.045       0  5400.8    0.07       0
  5510.2   0.045       0
Bank Sta=4990.4,4994.4
Exp/Cntr=0.3,0.1

Type RM Length L Ch R = 1,3534,258,258,258
BEGIN DESCRIPTION:
A18969
END DESCRIPTION:
XS GIS Cut Line= 3
      2305196.28     13790714.05      2304468.94     13790708.78
      2303636.23     13791283.25
#Sta/Elev= 30
  4162.5  583.39  4613.8  586.02  4725.4  585.59  4883.8  583.81  4941.0  582.09
  4982.9  579.70  5002.0  579.05  5002.2  578.55  5005.7  578.55  5006.0  579.05
  5033.6  580.41  5105.3  581.04  5263.5  580.65  5329.1  579.91  5376.5  580.07
  5395.7  580.30  5436.6  581.83  5459.6  583.49  5493.4  584.73  5523.1  584.16
  5529.2  584.59  5538.0  584.24  5544.1  584.74  5559.0  584.24  5579.9  584.92
  5630.6  583.87  5732.1  586.44  5738.1  586.98  5830.8  589.59  5901.5  589.68
#Mann=5,-1,0
  4162.5   0.045       0  5002.0   0.045       0  5006.0   0.045       0
  5376.5   0.035       0  5395.7   0.045       0
Bank Sta=5002,5006
Exp/Cntr=0.3,0.1

Type RM Length L Ch R = 1,3276,410,410,410
BEGIN DESCRIPTION:
GERONIMO TRIBUTARY 10 6.0
END DESCRIPTION:
XS GIS Cut Line= 3
      2304795.68     13790455.82      2304175.00     13790625.00
      2303625.03     13791174.97
#Sta/Elev= 30
  4351.9  585.71  4516.6  586.93  4704.9  586.22  4819.0  584.08  4870.8  582.23
  4903.6  581.52  4943.4  581.14  4998.8  579.46  5009.4  578.55  5021.5  578.13
  5021.8  577.63  5025.3  577.63  5025.5  578.13  5037.6  579.46  5051.8  579.73
  5094.2  578.76  5108.4  579.27  5292.2  579.00  5362.9  579.48  5391.2  579.88
  5417.6  580.75  5532.6  582.63  5546.8  582.99  5560.9  583.84  5589.2  584.33
  5617.5  585.69  5651.4  586.16  5702.3  587.09  5730.6  588.73  5773.0  588.52
#Mann=5,-1,0
  4351.9   0.045       0  5021.5   0.045       0  5025.5   0.045       0
  5417.6   0.035       0  5651.4   0.045       0
Bank Sta=5021.5,5025.5
Exp/Cntr=0.3,0.1

Type RM Length L Ch R = 1,2866,184,184,184
BEGIN DESCRIPTION:
GERONIMO TRIBUTARY 10 5.0
END DESCRIPTION:
XS GIS Cut Line= 3
      2304275.03     13790274.98      2303825.00     13790625.00
      2303575.03     13790974.96
#Sta/Elev= 30
  4429.5  586.34  4586.1  583.59  4743.5  579.85  4771.6  578.85  4814.1  578.11
  4822.3  578.02  4843.1  578.72  4892.8  578.05  4963.4  577.96  4986.1  576.25
  4992.4  576.65  4996.5  576.24  5002.7  576.24  5005.0  575.81  5005.3  575.31
  5008.8  575.31  5009.0  575.81  5027.9  576.91  5057.4  577.19  5213.5  580.60
  5265.1  581.69  5287.1  581.77  5299.1  582.07  5330.2  583.00  5336.3  583.65
  5351.1  584.02  5365.8  584.82  5372.0  585.85  5393.0  586.36  5429.7  586.31
#Mann=7,-1,0
  4429.5   0.045       0  5005.0   0.045       0  5009.0   0.045       0
  5213.5   0.035       0  5287.1    0.07       0  5299.1   0.035       0
  5393.0   0.045       0
Bank Sta=5005,5009
Exp/Cntr=0.3,0.1

Type RM Length L Ch R = 1,2682,260,260,260
BEGIN DESCRIPTION:
A18968
END DESCRIPTION:
XS GIS Cut Line= 2
      2304078.94     13790123.79      2303362.43     13790840.30
#Sta/Elev= 30
  4495.6  584.87  4534.6  584.43  4633.6  582.29  4640.7  582.36  4697.2  580.87
  4824.5  578.41  4845.7  577.77  4859.9  576.49  4866.9  576.18  4888.2  577.68
  4909.4  577.65  4973.0  576.65  4980.1  575.99  5006.4  574.59  5006.6  574.09
  5010.1  574.09  5010.4  574.59  5017.5  575.01  5022.5  575.76  5029.6  576.31
  5043.7  576.35  5077.6  577.16  5178.9  578.14  5220.5  578.08  5270.0  578.77
  5291.2  579.62  5322.4  580.31  5354.8  581.85  5411.4  583.48  5508.9  585.56
#Mann=7,-1,0
  4495.6   0.045       0  5006.4   0.045       0  5010.4   0.045       0
  5017.5    0.07       0  5077.6   0.045       0  5178.9    0.07       0
  5322.4   0.045       0
Bank Sta=5006.4,5010.4
Exp/Cntr=0.3,0.1

Type RM Length L Ch R = 1,2422,452,452,452
BEGIN DESCRIPTION:
GERONIMO TRIBUTARY 10 4.0
END DESCRIPTION:
XS GIS Cut Line= 3
      2303825.01     13790024.99      2303525.00     13790325.00
      2303274.99     13790625.01
#Sta/Elev= 30
  4571.3  581.77  4790.9  577.57  4825.9  577.31  4840.0  576.95  4854.2  577.37
  4868.3  577.01  4882.4  575.94  4939.0  574.31  4953.1  574.58  4970.6  575.37
  4981.4  575.50  4992.0  573.56  4998.8  573.56  5000.7  571.40  5001.0  570.90
  5004.5  570.90  5004.7  571.40  5009.2  572.22  5017.1  574.28  5023.6  574.96
  5037.0  575.13  5060.0  575.50  5066.5  575.29  5116.0  575.59  5179.8  576.23
  5286.5  579.01  5300.8  579.69  5315.1  579.80  5343.8  580.76  5386.1  581.53
#Mann=6,-1,0
  4571.3   0.045       0  4790.9    0.07       0  4970.6     0.1       0
  5000.7    0.05       0  5004.7     0.1       0  5037.0   0.045       0
Bank Sta=5000.7,5004.7
Exp/Cntr=0.3,0.1

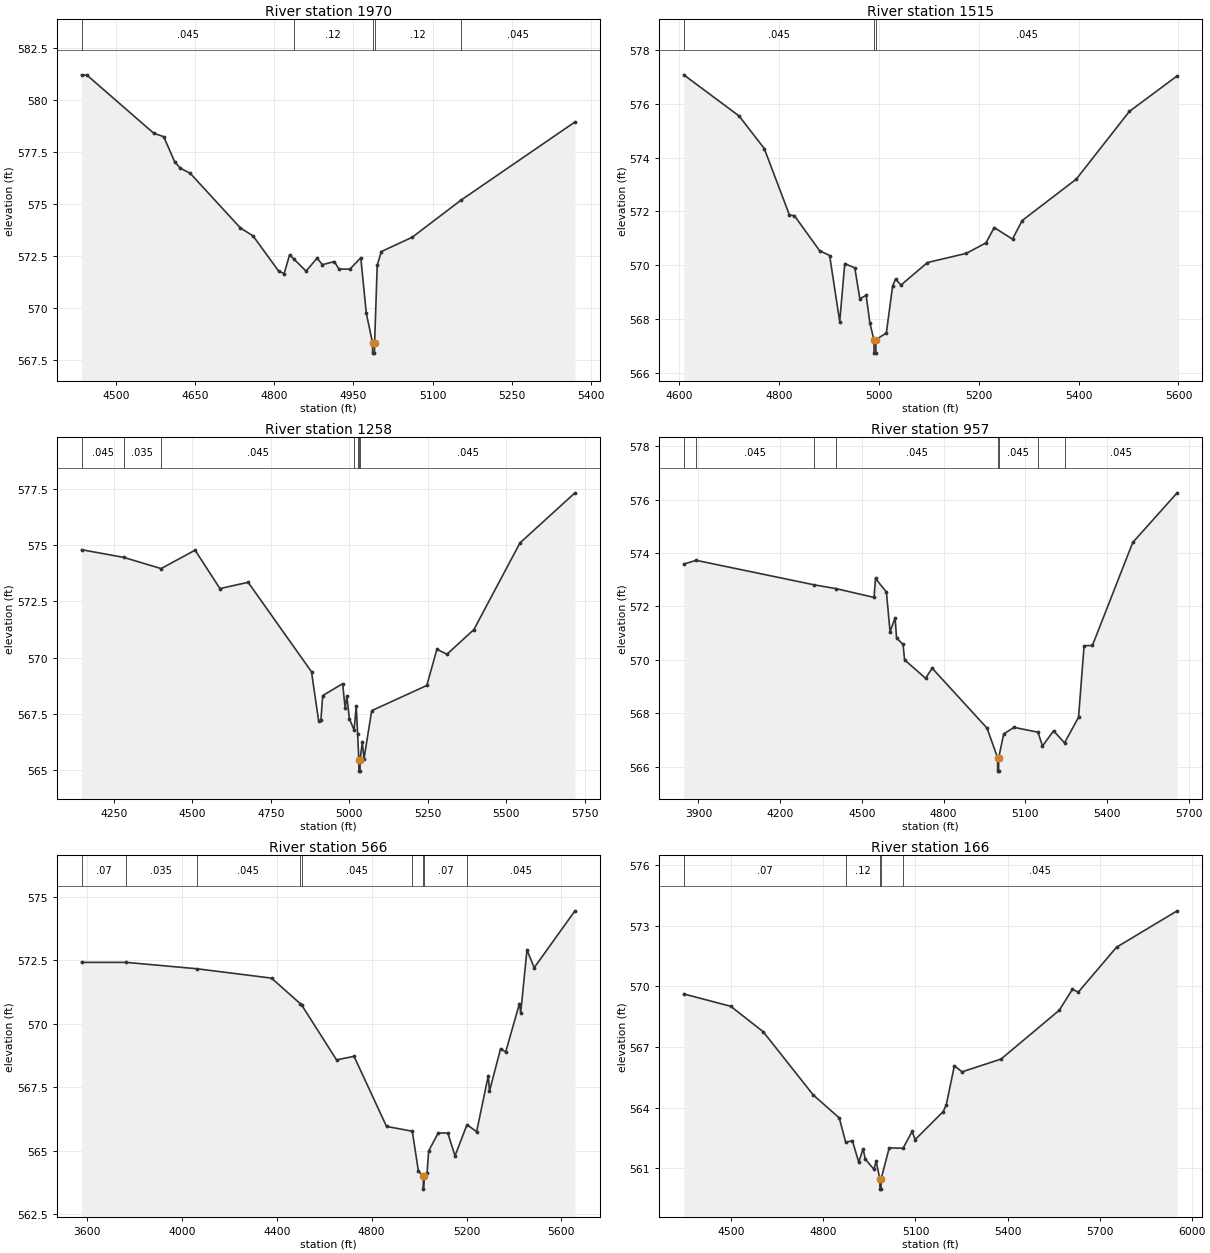
Type RM Length L Ch R = 1,1970,455,455,455
BEGIN DESCRIPTION:
GERONIMO TRIBUTARY 10 3.0
END DESCRIPTION:
XS GIS Cut Line= 3
      2303774.99     13789925.00      2303225.00     13790075.00
      2303124.99     13790425.02
#Sta/Elev= 30
  4435.3  581.22  4445.7  581.20  4571.8  578.41  4590.8  578.24  4611.5  577.04
  4621.9  576.73  4640.9  576.48  4735.9  573.85  4760.1  573.46  4808.4  571.77
  4818.8  571.65  4829.2  572.56  4837.6  572.34  4860.3  571.77  4881.0  572.39
  4891.4  572.08  4913.8  572.23  4922.5  571.87  4943.2  571.86  4963.9  572.41
  4974.3  569.75  4986.1  568.32  4986.3  567.82  4989.8  567.82  4990.1  568.32
  4995.0  572.05  5002.8  572.71  5061.3  573.40  5153.3  575.18  5369.4  578.95
#Mann=5,-1,0
  4435.3   0.045       0  4837.6    0.12       0  4986.1    0.05       0
  4990.1    0.12       0  5153.3   0.045       0
Bank Sta=4986.1,4990.1
Exp/Cntr=0.3,0.1

Type RM Length L Ch R = 1,1515,257,257,257
BEGIN DESCRIPTION:
GERONIMO TRIBUTARY 10 2.0
END DESCRIPTION:
XS GIS Cut Line= 3
      2303574.98     13789675.00      2303175.00     13789725.00
      2302975.01     13790274.97
#Sta/Elev= 30
  4609.1  577.08  4719.9  575.55  4770.3  574.34  4820.7  571.87  4830.8  571.84
  4881.2  570.54  4901.3  570.36  4921.5  567.90  4931.6  570.06  4951.7  569.90
  4961.8  568.75  4974.4  568.88  4982.0  567.84  4990.0  567.23  4990.3  566.73
  4993.8  566.73  4994.0  567.23  5014.9  567.48  5027.5  569.23  5033.5  569.49
  5044.1  569.26  5097.3  570.10  5175.1  570.44  5214.4  570.83  5231.0  571.40
  5267.6  570.97  5286.9  571.66  5395.3  573.20  5501.7  575.72  5597.4  577.04
#Mann=3,-1,0
  4609.1   0.045       0  4990.0   0.045       0  4994.0   0.045       0
Bank Sta=4990,4994
Exp/Cntr=0.3,0.1

Type RM Length L Ch R = 1,1258,301,301,301
BEGIN DESCRIPTION:
A18967
END DESCRIPTION:
XS GIS Cut Line= 3
      2303667.85     13789254.19      2302972.18     13789607.30
      2302687.58     13790345.16
#Sta/Elev= 30
  4147.3  574.80  4280.9  574.46  4400.6  573.96  4508.7  574.78  4587.9  573.07
  4677.6  573.35  4879.4  569.37  4901.9  567.20  4909.4  567.22  4915.0  568.31
  4978.6  568.84  4986.5  567.75  4991.9  568.27  5000.0  567.28  5015.0  566.78
  5021.9  567.85  5026.2  566.61  5030.2  565.45  5030.4  564.95  5033.9  564.95
  5034.2  565.45  5041.1  566.25  5046.5  565.50  5071.1  567.64  5246.5  568.76
  5278.7  570.37  5310.8  570.15  5396.6  571.25  5543.1  575.10  5718.3  577.33
#Mann=7,-1,0
  4147.3   0.045       0  4280.9   0.035       0  4400.6   0.045       0
  5015.0   0.035       0  5026.2   0.045       0  5030.2   0.045       0
  5034.2   0.045       0
Bank Sta=5030.2,5034.2
Exp/Cntr=0.3,0.1

Type RM Length L Ch R = 1,957,391,391,391
BEGIN DESCRIPTION:
A18966
END DESCRIPTION:
XS GIS Cut Line= 3
      2303662.63     13789132.96      2302677.05     13789538.78
      2302540.16     13790270.63
#Sta/Elev= 30
  3846.4  573.59  3892.1  573.73  4325.7  572.81  4405.2  572.67  4544.6  572.34
  4550.0  573.05  4590.0  572.54  4603.3  571.06  4621.8  571.57  4627.2  570.82
  4651.2  570.58  4656.6  570.00  4733.8  569.31  4757.8  569.69  4959.3  567.44
  4997.9  566.33  4998.2  565.83  5001.7  565.83  5001.9  566.33  5020.3  567.22
  5057.7  567.47  5146.1  567.29  5162.7  566.77  5203.4  567.34  5243.6  566.89
  5295.0  567.85  5315.3  570.53  5345.9  570.54  5493.9  574.40  5656.8  576.26
#Mann=8,-1,0
  3846.4    0.07       0  3892.1   0.045       0  4325.7   0.035       0
  4405.2   0.045       0  4997.9   0.045       0  5001.9   0.045       0
  5146.1   0.035       0  5243.6   0.045       0
Bank Sta=4997.9,5001.9
Exp/Cntr=0.3,0.1

Type RM Length L Ch R = 1,566,400,400,400
BEGIN DESCRIPTION:
GERONIMO TRIBUTARY 10 1.0
END DESCRIPTION:
XS GIS Cut Line= 3
      2303675.00     13789025.00      2302325.00     13789475.00
      2302425.00     13790125.02
#Sta/Elev= 30
  3576.6  572.41  3764.4  572.41  4061.5  572.16  4377.7  571.79  4498.1  570.79
  4504.2  570.74  4651.8  568.57  4725.6  568.71  4862.6  565.95  4971.3  565.76
  4997.0  564.19  5017.9  563.98  5018.1  563.48  5021.9  563.98  5033.8  564.13
  5040.1  564.98  5080.6  565.69  5121.0  565.69  5151.4  564.79  5202.0  566.02
  5242.5  565.74  5291.8  567.95  5296.8  567.34  5343.6  569.01  5365.1  568.88
  5423.3  570.79  5428.4  570.42  5454.9  572.90  5485.3  572.20  5657.3  574.44
#Mann=9,-1,0
  3576.6    0.07       0  3764.4   0.035       0  4061.5   0.045       0
  4498.1   0.035       0  4504.2   0.045       0  4971.3    0.07       0
  5017.9    0.05       0  5021.9    0.07       0  5202.0   0.045       0
Bank Sta=5017.9,5021.9
Exp/Cntr=0.3,0.1

Type RM Length L Ch R = 1,166,0,0,0
BEGIN DESCRIPTION:
A18965
END DESCRIPTION:
XS GIS Cut Line= 4
      2302487.35     13788711.32      2302028.81     13789206.76
      2301997.18     13789412.30      2302234.36     13790097.48
#Sta/Elev= 30
  4344.7  569.63  4497.8  569.02  4603.8  567.76  4766.5  564.64  4851.6  563.50
  4872.7  562.29  4894.1  562.38  4915.1  561.31  4929.2  561.98  4936.1  561.47
  4964.4  560.96  4971.8  561.35  4983.9  560.48  4984.2  559.98  4987.7  559.98
  4987.9  560.48  5014.3  562.02  5059.4  562.00  5088.8  562.83  5098.9  562.43
  5190.0  563.81  5200.1  564.13  5226.6  566.08  5251.8  565.78  5378.7  566.41
  5568.3  568.82  5611.6  569.86  5630.6  569.72  5755.2  571.94  5952.8  573.74
#Mann=5,-1,0
  4344.7    0.07       0  4872.7    0.12       0  4983.9    0.05       0
  4987.9    0.12       0  5059.4   0.045       0
Bank Sta=4983.9,4987.9
Exp/Cntr=0.3,0.1

Chan Stop Cuts=-1