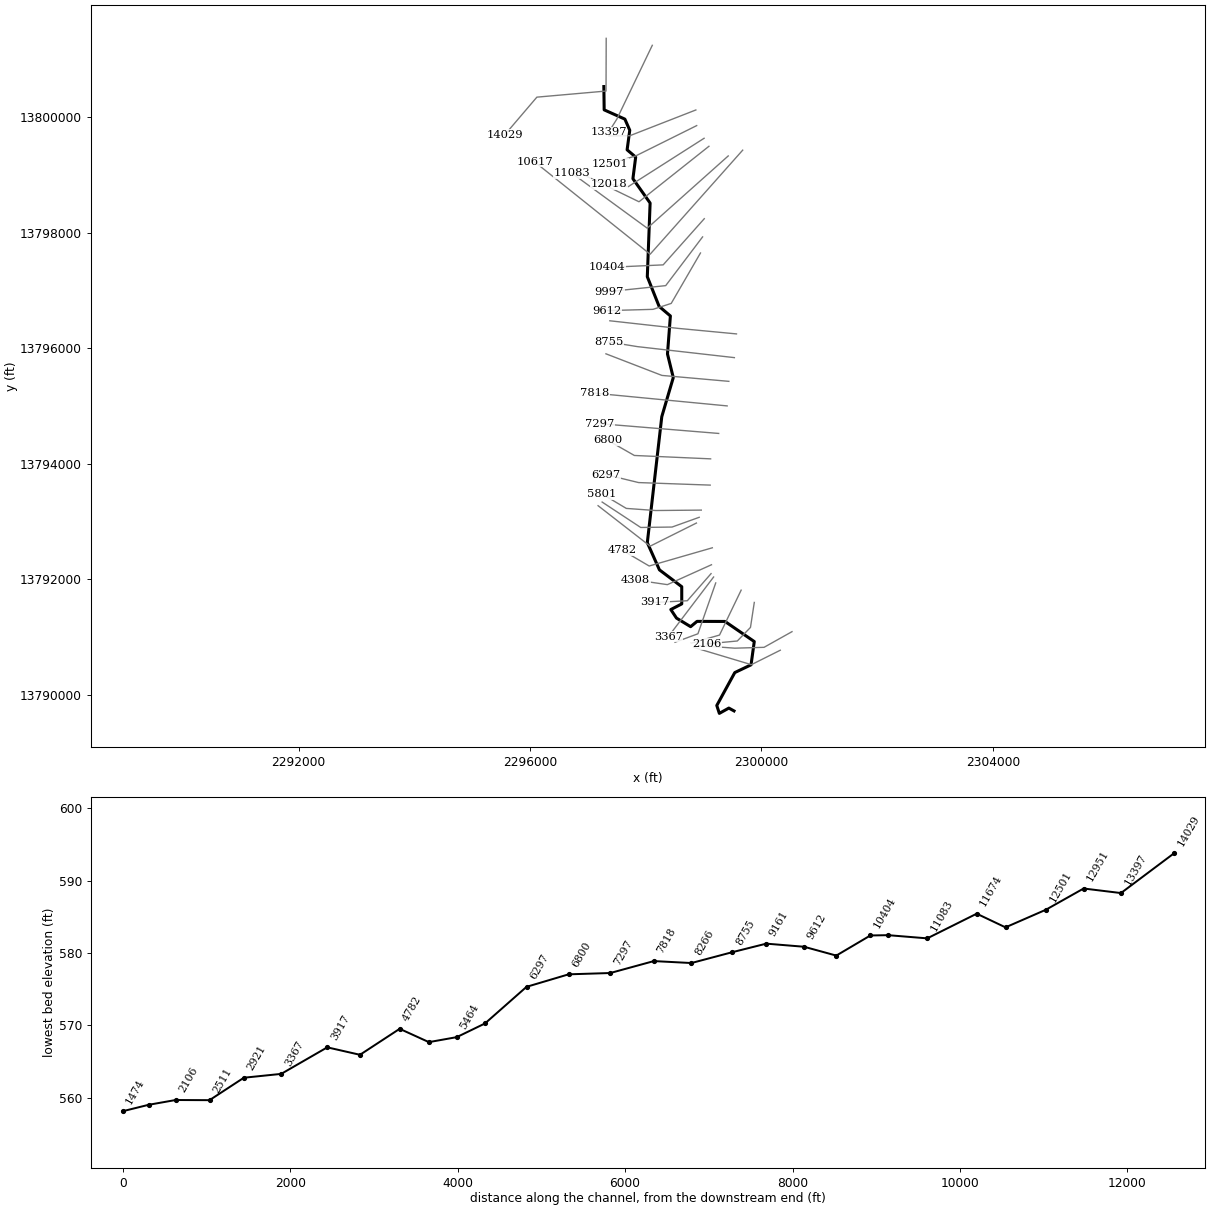
--- GERONIMO TRIBUTARY 11.prj (project) ---

Proj Title=GERONIMO TRIBUTARY 11 Base Level Engineering
Current Plan=p01
Default Exp/Contr=0.3,0.1
English Units
Geom File=g01
Flow File=f01
Plan File=p01
Y Axis Title=Elevation
X Axis Title(PF)=Main Channel Distance
X Axis Title(XS)=Station
BEGIN DESCRIPTION:
GERONIMO TRIBUTARY 11
END DESCRIPTION:
DSS Export Rating Curves= 0
DSS Export Rating Curve Sorted= 0
DSS Export Volume Flow Curves= 0
DXF OffsetX= 0
DXF OffsetY= 0
DXF ScaleX= 1
DXF ScaleY= 10

--- GERONIMO TRIBUTARY 11.p01 (plan) ---

Plan Title=Multiple Run
Short Identifier=Multiple
Geom File=g01
Flow File=f01
Subcritical Flow
K Sum by GR= 0
Std Step Tol= 0.01
Critical Tol= 0.01
Num of Std Step Trials= 20
Max Error Tol= 0.3
Flow Tol Ratio= 0.001
Split Flow NTrial= 30
Split Flow Tol= 0.02
Split Flow Ratio= 0.02
Log Output Level= 0
Friction Slope Method= 1
Unsteady Friction Slope Method= 2
Unsteady Bridges Friction Slope Method= 1
Parabolic Critical Depth
Global Vel Dist=  1 , 1 , 1
Global Log Level= 0
CheckData=True
Encroach Param= -1, 0, 0, 0
BEGIN DESCRIPTION:
Multiple Run
END DESCRIPTION:

--- GERONIMO TRIBUTARY 11.f01 (steady flow) ---

Flow Title=Multiple
Number of Profiles=7
Profile Names=10-year,25-year,50-year,1pct_min,100-year,1pct_plu,500-year
River Rch & RM= GERONIMO TRIBUTA,Reach-1,14029
     701    1141    1542    1010    2015    4021    3408
River Rch & RM= GERONIMO TRIBUTA,Reach-1,13397
    1263    2112    2905    1932    3854    7690    6724
River Rch & RM= GERONIMO TRIBUTA,Reach-1,9161
    1646    2762    3808    2533    5054   10083    8825
River Rch & RM= GERONIMO TRIBUTA,Reach-1,1784
    1722    2892    3988    2652    5292   10559    9242
Boundary for River Rch & Prof#=GERONIMO TRIBUTA,Reach-1,1
Up Type=0
Dn Type=3
Dn Slope=0.005
Boundary for River Rch & Prof#=GERONIMO TRIBUTA,Reach-1,2
Up Type=0
Dn Type=3
Dn Slope=0.005
Boundary for River Rch & Prof#=GERONIMO TRIBUTA,Reach-1,3
Up Type=0
Dn Type=3
Dn Slope=0.005
Boundary for River Rch & Prof#=GERONIMO TRIBUTA,Reach-1,4
Up Type=0
Dn Type=3
Dn Slope=0.005
Boundary for River Rch & Prof#=GERONIMO TRIBUTA,Reach-1,5
Up Type=0
Dn Type=3
Dn Slope=0.005
Boundary for River Rch & Prof#=GERONIMO TRIBUTA,Reach-1,6
Up Type=0
Dn Type=3
Dn Slope=0.005
Boundary for River Rch & Prof#=GERONIMO TRIBUTA,Reach-1,7
Up Type=0
Dn Type=3
Dn Slope=0.005

--- GERONIMO TRIBUTARY 11.g01 (geometry) ---

Geom Title=Existing Conditions
Program Version=4.10

River Reach=GERONIMO TRIBUTA,Reach-1
Reach XY= 30
        2297275.       13800525.      2297280.46       13800122.
      2297638.63     13799961.54      2297722.75     13799769.06
      2297676.97     13799430.68      2297825.09     13799305.12
      2297777.25     13798930.94      2298074.62     13798509.84
      2298026.06     13797235.44      2298230.42     13796722.33
      2298425.08     13796556.89       2298374.8     13795899.92
      2298474.92     13795490.39      2298276.22      13794814.5
      2298026.22      13792635.5      2298235.76      13792165.3
      2298621.46     13791873.54      2298621.56     13791576.22
      2298432.48     13791478.62      2298530.62     13791330.62
      2298775.08      13791182.3      2298885.43     13791273.94
      2299369.07     13791272.76        2299875.       13790925.
      2299819.29     13790522.42      2299538.47     13790388.57
      2299227.16     13789819.02       2299271.3     13789682.65
      2299435.62     13789774.34        2299525.       13789725.

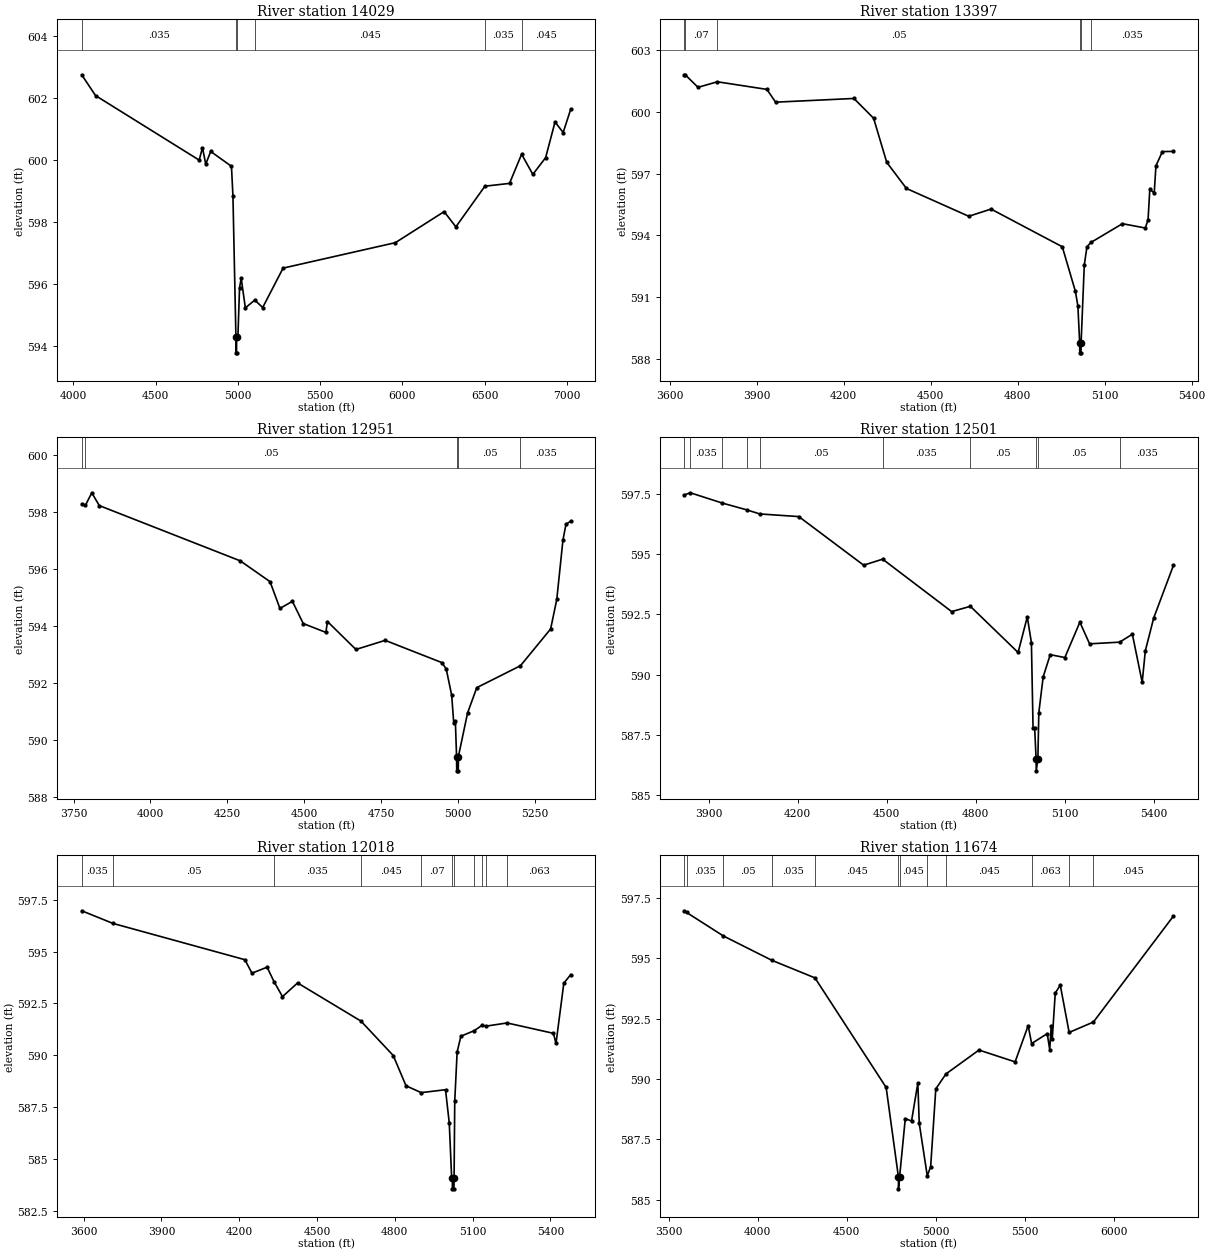
Type RM Length L Ch R = 1 ,14029   ,632,632,632
BEGIN DESCRIPTION:
GERONIMO TRIBUTARY 11 10.0
END DESCRIPTION:
XS GIS Cut Line= 4
      2297315.49     13801359.15      2297312.63     13800447.34
      2296117.09     13800341.85      2295558.75     13799686.69
#Sta/Elev= 30
  4050.4  602.74  4134.6  602.07  4764.6  599.99  4784.6  600.39  4804.6  599.86
  4834.6  600.27  4960.9  599.79  4969.9  598.83    4988  594.28  4988.2  593.78
  4991.7  593.78    4992  594.28    5000  594.29    5010  595.88  5020.1  596.18
  5045.4  595.23  5102.6  595.48  5150.6  595.24  5274.7  596.51  5957.3  597.33
  6253.6  598.33    6325  597.84  6501.5  599.15  6651.1  599.24  6724.7  600.18
  6792.8  599.53  6870.7  600.07  6927.8  601.22  6977.2  600.88  7023.2  601.63
#Mann= 6 ,-1 , 0
  4050.4    .035       0    4988    .035       0    4992    .035       0
  5102.6    .045       0  6501.5    .035       0  6724.7    .045       0
Bank Sta=4988,4992
XS Rating Curve= 0 ,0
Exp/Cntr=0.3,0.1

Type RM Length L Ch R = 1 ,13397   ,446,446,446
BEGIN DESCRIPTION:
GERONIMO TRIBUTARY 11 9.0
END DESCRIPTION:
XS GIS Cut Line= 3
      2298112.28     13801238.56      2297501.89      13799966.6
      2297355.68     13799732.67
#Sta/Elev= 30
  3650.2   601.8  3653.1   601.8  3697.3  601.19  3763.8  601.46  3934.9  601.09
  3964.7  600.47  4234.9  600.65  4302.8  599.69  4348.1  597.55  4416.1  596.28
    4631  594.93  4707.9  595.28  4953.6  593.45  4998.9  591.28  5007.4  590.57
  5013.5   588.8  5013.9   588.3  5018.2   588.3  5018.5   588.8  5029.5  592.57
  5038.7  593.45  5052.4  593.66  5161.1  594.57  5240.1  594.36  5249.5  594.77
  5255.4  596.24  5270.7  596.06  5276.6  597.38  5298.8  598.07  5336.9  598.08
#Mann= 6 ,-1 , 0
  3650.2    .045       0  3653.1     .07       0  3763.8     .05       0
  5013.5     .05       0  5018.5     .05       0  5052.4    .035       0
Bank Sta=5013.5,5018.5
XS Rating Curve= 0 ,0
Exp/Cntr=0.3,0.1

Type RM Length L Ch R = 1 ,12951   ,450,450,450
BEGIN DESCRIPTION:
GERONIMO TRIBUTARY 11 8.0
END DESCRIPTION:
XS GIS Cut Line= 3
      2298865.18      13800120.1        2297725.       13799675.
       2297359.7     13799670.55
#Sta/Elev= 30
  3776.5   598.3  3788.7  598.25  3809.3  598.69  3833.8  598.24    4292   596.3
  4388.6  595.57  4420.8  594.63  4461.3  594.88  4496.5   594.1    4570  593.79
  4575.3  594.17  4667.7  593.19  4762.8  593.51  4946.8  592.73  4961.1  592.51
    4979  591.58  4985.6   590.6  4990.9  590.67  4994.8  589.43  4995.3  588.93
  5000.3  588.93  5000.7  589.43  5030.5  590.96  5060.5  591.85  5202.5  592.62
  5300.5  593.91  5320.5  594.95  5340.5  597.03  5350.5  597.59  5365.8  597.69
#Mann= 5 ,-1 , 0
  3776.5    .045       0  3788.7     .05       0  4994.8     .05       0
  5000.7     .05       0  5202.5    .035       0
Bank Sta=4994.8,5000.7
XS Rating Curve= 0 ,0
Exp/Cntr=0.3,0.1

Type RM Length L Ch R = 1 ,12501   ,483,483,483
BEGIN DESCRIPTION:
GERONIMO TRIBUTARY 11 7.0
END DESCRIPTION:
XS GIS Cut Line= 3
      2298879.83     13799849.65        2297825.       13799325.
      2297373.97     13799191.75
#Sta/Elev= 30
  3818.2  597.47  3838.2  597.56  3946.6  597.13  4028.5  596.85  4072.6  596.68
    4204  596.57  4422.4  594.55  4486.5   594.8  4719.1  592.62  4782.1  592.84
  4943.1  590.92    4974   592.4  4987.9  591.33  4993.5  587.77  4998.9  587.77
  5003.7   586.5  5004.2     586  5009.7   586.5  5012.9  588.42  5027.6  589.91
  5051.4  590.83  5100.6  590.71  5151.3  592.18    5184  591.28  5285.4  591.35
  5328.2  591.68  5361.3  589.68  5371.9  590.99    5400  592.35  5466.6  594.54
#Mann= 10 ,-1 , 0
  3818.2    .045       0  3838.2    .035       0  3946.6     .05       0
  4028.5    .035       0  4072.6     .05       0  4486.5    .035       0
  4782.1     .05       0  5003.7     .05       0  5009.7     .05       0
  5285.4    .035       0
Bank Sta=5003.7,5009.7
XS Rating Curve= 0 ,0
Exp/Cntr=0.3,0.1

Type RM Length L Ch R = 1 ,12018   ,344,344,344
BEGIN DESCRIPTION:
GERONIMO TRIBUTARY 11 6.0
END DESCRIPTION:
XS GIS Cut Line= 3
      2299007.76     13799630.36       2297695.6     13798793.36
      2297368.63     13798832.57
#Sta/Elev= 30
  3592.5  596.97  3713.3  596.36  4221.9  594.61    4249  593.96  4307.5  594.25
  4334.2  593.55  4366.8  592.83    4425  593.49  4669.3  591.65  4793.8  589.99
  4843.1  588.53  4901.7   588.2  4995.4  588.34  5009.8  586.74  5019.1  584.08
  5021.6  584.06  5022.1  583.56  5027.9  583.56  5028.4  584.06    5031   587.8
  5040.2  590.16  5054.7  590.92  5106.5  591.19  5135.4  591.44  5153.4  591.41
  5232.9  591.56  5411.4  591.06  5421.4  590.57  5451.6  593.48  5478.2  593.89
#Mann= 11 ,-1 , 0
  3592.5    .035       0  3713.3     .05       0  4334.2    .035       0
  4669.3    .045       0  4901.7     .07       0  5021.6     .05       0
  5028.4     .07       0  5106.5    .045       0  5135.4     .07       0
  5153.4    .045       0  5232.9    .063       0
Bank Sta=5021.6,5028.4
XS Rating Curve= 0 ,0
Exp/Cntr=0.3,0.1

Type RM Length L Ch R = 1 ,11674   ,591,591,591
BEGIN DESCRIPTION:
A18994
END DESCRIPTION:
XS GIS Cut Line= 3
      2299091.45     13799491.98      2297882.65     13798532.27
      2296800.02     13799058.95
#Sta/Elev= 30
    3589  596.97  3601.4   596.9  3807.3  595.93  4079.8  594.92  4322.5  594.19
  4722.6  589.65  4791.3  585.95  4791.8  585.45  4798.1  585.95    4830  588.36
  4865.2  588.26  4900.4  589.83  4908.5  588.16  4953.5  585.99  4972.6  586.37
  5001.4  589.59  5058.4  590.21  5244.1   591.2    5447  590.71  5520.3  592.21
  5539.8  591.47  5627.4  591.88  5641.4  591.22    5650  592.21  5655.6  591.64
  5672.5  593.56  5700.7  593.89  5750.6  591.93  5886.7  592.36  6336.4  596.75
#Mann= 12 ,-1 , 0
    3589    .045       0  3601.4    .035       0  3807.3     .05       0
  4079.8    .035       0  4322.5    .045       0  4791.3     .05       0
  4798.1    .045       0  4953.5     .07       0  5058.4    .045       0
  5539.8    .063       0  5750.6    .035       0  5886.7    .045       0
Bank Sta=4791.3,4798.1
XS Rating Curve= 0 ,0
Exp/Cntr=0.3,0.1

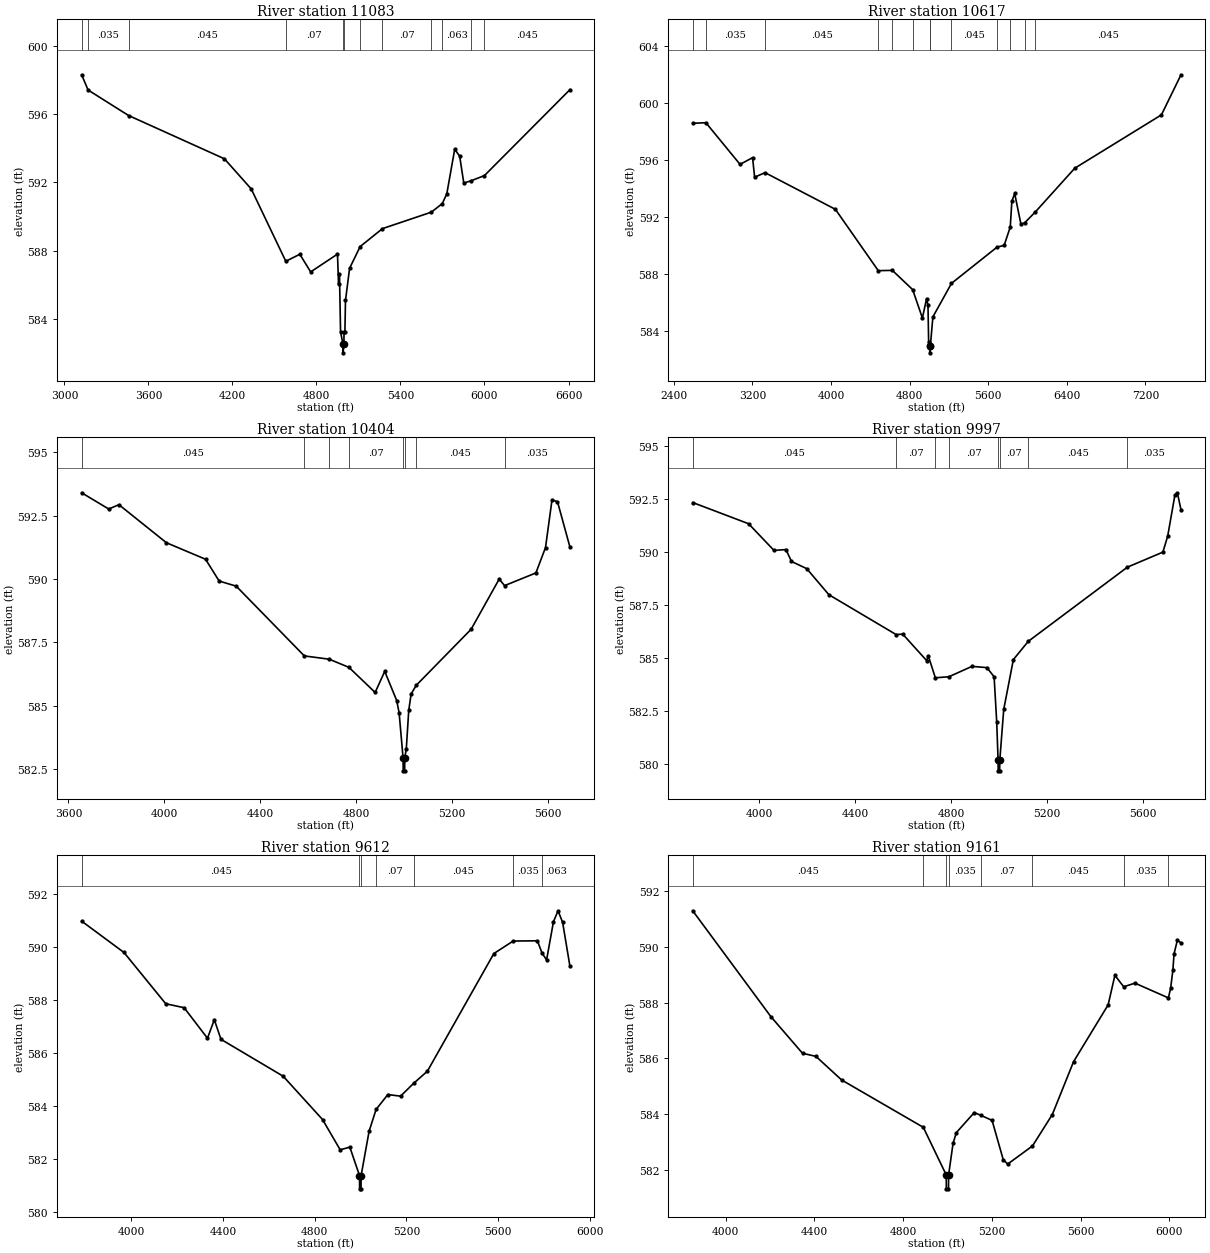
Type RM Length L Ch R = 1 ,11083   ,466,466,466
BEGIN DESCRIPTION:
GERONIMO TRIBUTARY 11 5.0
END DESCRIPTION:
XS GIS Cut Line= 3
      2299425.03     13799325.02        2298025.       13798075.
      2296724.99       13799025.
#Sta/Elev= 30
  3123.1  598.29    3169   597.4  3458.1  595.91  4142.7  593.38  4334.1  591.62
  4581.1  587.39    4681   587.8  4758.8  586.77  4950.2  587.81  4957.7  586.06
  4964.4  586.64    4972  583.27  4989.4  582.54  4989.9  582.04  4996.3  582.54
  4996.6  583.25  5003.1  583.25  5007.3   585.1  5036.6  586.98  5111.9  588.25
  5271.5   589.3    5620  590.26  5698.4  590.76  5730.7  591.33  5787.3  593.94
  5822.8  593.53  5852.1  591.96  5905.7   592.1  5999.6   592.4  6610.1  597.42
#Mann= 12 ,-1 , 0
  3123.1    .045       0    3169    .035       0  3458.1    .045       0
  4581.1     .07       0  4989.4     .05       0  4996.3     .07       0
  5111.9    .045       0  5271.5     .07       0    5620    .035       0
  5698.4    .063       0  5905.7    .035       0  5999.6    .045       0
Bank Sta=4989.4,4996.3
XS Rating Curve= 0 ,0
Exp/Cntr=0.3,0.1

Type RM Length L Ch R = 1 ,10617   ,213,213,213
BEGIN DESCRIPTION:
GERONIMO TRIBUTARY 11 4.0
END DESCRIPTION:
XS GIS Cut Line= 3
      2299675.01     13799425.01        2298075.       13797625.
      2296074.98     13799225.01
#Sta/Elev= 30
  2591.9  598.57    2726  598.61  3073.6  595.69  3201.1  596.16    3222  594.79
    3328  595.11    4044  592.54  4480.4  588.24  4623.7  588.26  4830.4  586.91
  4929.6  584.92  4972.2  586.28  4986.4  585.81  4993.1  583.21  5003.9  582.98
  5004.4  582.48  5010.9  582.98  5036.2     585  5225.7  587.35  5689.3  589.89
  5761.4  590.01  5823.8   591.3  5839.8  593.09  5868.7  593.65  5932.7  591.49
  5969.7  591.59  6078.4  592.35  6480.2  595.42  7362.2  599.16  7561.5  601.97
#Mann= 13 ,-1 , 0
  2591.9    .045       0    2726    .035       0    3328    .045       0
  4480.4     .07       0  4623.7    .045       0  4830.4     .07       0
  5003.9     .05       0  5010.9     .07       0  5225.7    .045       0
  5689.3    .035       0  5823.8    .063       0  5969.7    .035       0
  6078.4    .045       0
Bank Sta=5003.9,5010.9
XS Rating Curve= 0 ,0
Exp/Cntr=0.3,0.1

Type RM Length L Ch R = 1 ,10404   ,407,407,407
BEGIN DESCRIPTION:
A18993
END DESCRIPTION:
XS GIS Cut Line= 3
      2299010.87     13798239.19      2298300.24     13797440.66
      2297333.19      13797396.7
#Sta/Elev= 30
  3655.1   593.4  3768.1  592.76  3810.7  592.93  4008.9  591.43    4172  590.78
  4228.8  589.92  4299.9  589.72    4584  586.97    4688  586.84    4770  586.52
  4879.5  585.53  4919.5  586.36  4969.5  585.21  4979.6  584.72  4996.1  582.94
  4996.6  582.44  5002.6  582.44  5003.1  582.94  5009.6  583.32  5019.6  584.82
  5029.6  585.47  5050.8  585.81  5279.9  588.02  5397.1     590  5419.4  589.74
  5550.1  590.24  5590.2  591.24  5617.3  593.12  5640.2  593.05  5692.1  591.26
#Mann= 8 ,-1 , 0
  3655.1    .045       0    4584     .07       0    4688    .045       0
    4770     .07       0  4996.1     .05       0  5003.1     .07       0
  5050.8    .045       0  5419.4    .035       0
Bank Sta=4996.1,5003.1
XS Rating Curve= 0 ,0
Exp/Cntr=0.3,0.1

Type RM Length L Ch R = 1 ,9997    ,385,385,385
BEGIN DESCRIPTION:
A18992
END DESCRIPTION:
XS GIS Cut Line= 3
      2298981.61     13797924.22       2298344.2     13797081.67
      2297369.88     13796979.11
#Sta/Elev= 30
  3723.2  592.32  3956.1  591.32  4062.2  590.06  4112.1   590.1    4135  589.54
  4198.7   589.2  4291.1  587.97  4571.4  586.09    4599  586.11  4698.9  584.86
  4705.2   585.1    4735  584.05  4791.7   584.1  4887.8  584.59  4949.8  584.53
    4980   584.1  4990.9  581.97  4996.6  580.16  4997.1  579.66  5003.2  579.66
  5003.7  580.16  5020.2  582.56  5060.4  584.91  5122.5  585.77  5535.8  589.27
  5683.9  589.98    5704  590.74  5734.1  592.68  5744.2  592.78  5759.4  591.98
#Mann= 8 ,-1 , 0
  3723.2    .045       0  4571.4     .07       0    4735    .045       0
  4791.7     .07       0  4996.6     .05       0  5003.7     .07       0
  5122.5    .045       0  5535.8    .035       0
Bank Sta=4996.6,5003.7
XS Rating Curve= 0 ,0
Exp/Cntr=0.3,0.1

Type RM Length L Ch R = 1 ,9612    ,451,451,451
BEGIN DESCRIPTION:
A18991
END DESCRIPTION:
XS GIS Cut Line= 4
      2298944.96      13797645.8      2298439.44     13796773.97
      2298124.41      13796671.4      2297333.21     13796649.43
#Sta/Elev= 30
  3782.7  590.96  3967.4  589.78  4149.6  587.85  4229.9   587.7  4331.8  586.55
  4361.6  587.25  4390.6  586.51  4662.1  585.12  4833.8  583.49  4910.8  582.35
  4952.9  582.45  4995.1  581.38  4995.6  580.88  5001.7  580.88  5002.2  581.38
    5037  583.05  5067.5  583.87  5118.8  584.43  5174.3  584.37    5231  584.85
  5291.3  585.31  5581.4  589.74  5665.5  590.21  5771.5  590.22  5791.4  589.76
  5811.5   589.5  5841.5  590.94  5861.5  591.35  5881.5  590.91  5913.3  589.26
#Mann= 7 ,-1 , 0
  3782.7    .045       0  4995.1    .045       0  5002.2    .045       0
  5067.5     .07       0    5231    .045       0  5665.5    .035       0
  5791.4    .063       0
Bank Sta=4995.1,5002.2
XS Rating Curve= 0 ,0
Exp/Cntr=0.3,0.1

Type RM Length L Ch R = 1 ,9161    ,406,406,406
BEGIN DESCRIPTION:
A18990
END DESCRIPTION:
XS GIS Cut Line= 3
      2299567.66     13796246.49      2298563.99     13796341.72
      2297378.56     13796473.44
#Sta/Elev= 30
    3852   591.3    4204   587.5  4346.9  586.18  4407.1  586.07  4523.5  585.22
  4891.4  583.52  4994.7  581.81  4995.2  581.31  5004.9  581.31  5005.4  581.81
  5025.4  582.94  5040.3  583.33    5121  584.05    5151  583.95  5201.3  583.77
  5251.6  582.36  5271.7   582.2  5383.4  582.85  5472.9  583.98  5568.7  585.88
  5724.5  587.92  5754.9  588.98  5794.6  588.57  5845.4   588.7  5996.1  588.17
  6006.2  588.52  6016.2  589.16  6021.5  589.75  6036.4  590.24  6052.9  590.15
#Mann= 8 ,-1 , 0
    3852    .045       0  4891.4    .035       0  4994.7    .035       0
  5005.4    .035       0    5151     .07       0  5383.4    .045       0
  5794.6    .035       0  5996.1    .063       0
Bank Sta=4994.7,5005.4
XS Rating Curve= 0 ,0
Exp/Cntr=0.3,0.1

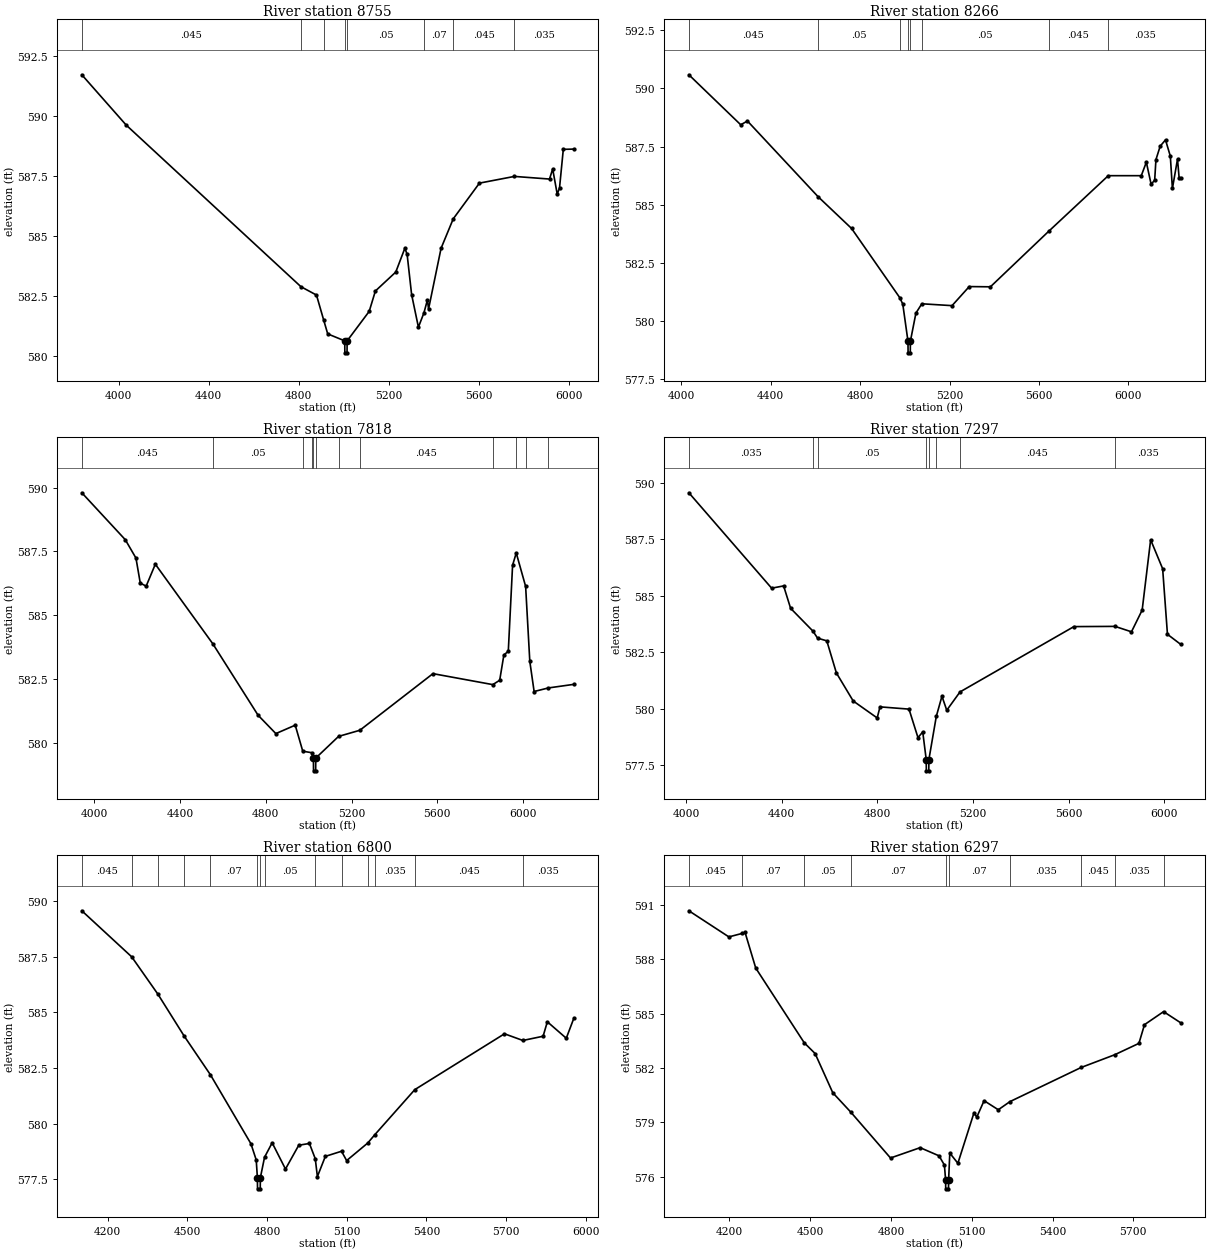
Type RM Length L Ch R = 1 ,8755    ,489,489,489
BEGIN DESCRIPTION:
A18989
END DESCRIPTION:
XS GIS Cut Line= 3
      2299531.06     13795836.21      2297853.34      13796026.7
      2297362.51     13796107.28
#Sta/Elev= 30
  3836.4  591.73  4033.7  589.63  4809.9  582.89  4879.1  582.54  4911.3  581.49
    4929  580.92  5004.6  580.63  5005.1  580.13  5014.8  580.13  5015.3  580.63
  5113.3  581.86  5140.8  582.71  5231.4   583.5  5271.6  584.49  5281.7  584.25
  5301.8  582.56    5332   581.2  5356.6   581.8  5372.1  582.34  5377.1  581.96
  5432.6  584.49  5486.7  585.72  5603.1  587.21  5758.5  587.49  5914.5  587.38
  5928.6   587.8  5948.8  586.75    5959  587.01  5975.8  588.62  6022.3  588.63
#Mann= 8 ,-1 , 0
  3836.4    .045       0  4809.9    .035       0  4911.3     .05       0
  5004.6     .05       0  5015.3     .05       0  5356.6     .07       0
  5486.7    .045       0  5758.5    .035       0
Bank Sta=5004.6,5015.3
XS Rating Curve= 0 ,0
Exp/Cntr=0.3,0.1

Type RM Length L Ch R = 1 ,8266    ,448,448,448
BEGIN DESCRIPTION:
A18988
END DESCRIPTION:
XS GIS Cut Line= 3
      2299435.83     13795425.94      2298278.27     13795528.51
      2297311.23     13795902.14
#Sta/Elev= 30
  4035.1  590.59  4266.8  588.44    4297   588.6  4612.2  585.35  4762.3  583.98
  4977.2  581.01  4991.1  580.73  5014.4  579.13  5014.9  578.63  5024.7  578.63
  5025.2  579.13  5049.9  580.34  5076.3  580.74  5211.4  580.66  5288.2  581.48
  5382.9  581.47  5642.5  583.85  5909.7  586.25  6057.2  586.25  6079.8  586.83
  6101.2  585.88  6117.1  586.06  6122.7  586.94  6141.7  587.52  6165.5  587.79
    6187  587.09  6196.3   585.7  6219.1  586.96  6226.2  586.17  6233.9  586.13
#Mann= 8 ,-1 , 0
  4035.1    .045       0  4612.2     .05       0  4977.2    .035       0
  5014.4    .035       0  5025.2    .035       0  5076.3     .05       0
  5642.5    .045       0  5909.7    .035       0
Bank Sta=5014.4,5025.2
XS Rating Curve= 0 ,0
Exp/Cntr=0.3,0.1

Type RM Length L Ch R = 1 ,7818    ,521,521,521
BEGIN DESCRIPTION:
A18987
END DESCRIPTION:
XS GIS Cut Line= 2
      2299406.52     13795001.02      2297120.76     13795220.81
#Sta/Elev= 30
  3940.9   589.8  4143.8  587.96  4193.6  587.24  4213.7  586.26  4241.2  586.14
    4284     587  4552.4  583.88  4763.6  581.08  4846.6  580.36    4937  580.69
  4972.2  579.67  5014.7  579.61  5021.9   579.4  5022.4   578.9  5032.4   578.9
  5032.9   579.4  5139.3  580.25  5238.6  580.49  5579.9  582.71  5859.2  582.28
  5891.4  582.45  5910.9  583.44  5931.6  583.59  5951.6  586.96  5968.7  587.44
  6012.5  586.13    6032  583.19  6052.1  582.01    6119  582.15  6237.2  582.29
#Mann= 12 ,-1 , 0
  3940.9    .045       0  4552.4     .05       0  4972.2    .035       0
  5014.7     .05       0  5021.9    .035       0  5032.9     .05       0
  5139.3    .035       0  5238.6    .045       0  5859.2    .035       0
  5968.7    .063       0  6012.5    .035       0    6119     .05       0
Bank Sta=5021.9,5032.9
XS Rating Curve= 0 ,0
Exp/Cntr=0.3,0.1

Type RM Length L Ch R = 1 ,7297    ,497,497,497
BEGIN DESCRIPTION:
A18986
END DESCRIPTION:
XS GIS Cut Line= 2
      2299259.96     13794524.82      2297209.27     13794693.27
#Sta/Elev= 30
  4011.7  589.55  4357.8  585.33    4408  585.43  4437.2  584.44  4530.7  583.43
    4550  583.12  4588.6     583  4628.7  581.58    4699  580.34  4799.3  579.59
  4811.1  580.08  4932.4  579.98  4969.9  578.72  4989.9  578.97  5004.4  577.75
  5004.9  577.25  5015.1  577.25  5015.6  577.75  5046.6  579.66  5070.2  580.55
  5090.3  579.93  5145.7  580.74  5622.1  583.63    5794  583.64  5862.9   583.4
  5907.6  584.36  5943.1  587.47  5993.3  586.19  6013.4  583.29  6069.3  582.84
#Mann= 8 ,-1 , 0
  4011.7    .035       0  4530.7    .045       0    4550     .05       0
  5004.4     .05       0  5015.6     .05       0  5046.6    .035       0
  5145.7    .045       0    5794    .035       0
Bank Sta=5004.4,5015.6
XS Rating Curve= 0 ,0
Exp/Cntr=0.3,0.1

Type RM Length L Ch R = 1 ,6800    ,503,503,503
BEGIN DESCRIPTION:
A18985
END DESCRIPTION:
XS GIS Cut Line= 3
      2299120.74     13794085.25      2297802.06     13794143.86
      2297340.49     13794407.61
#Sta/Elev= 30
  4103.3  589.57    4291   587.5  4389.7  585.82  4488.4  583.94  4587.2   582.2
  4739.7   579.1  4759.7  578.37  4764.1  577.57  4764.6  577.07  4774.8  577.07
  4775.3  577.57    4791  578.49  4819.7  579.14  4869.8  577.96  4919.8  579.03
  4959.9  579.11    4982  578.42  4989.9  577.62  5019.9  578.53  5080.8  578.76
    5100  578.34  5179.5  579.13  5205.8   579.5  5356.6  581.53  5694.1  584.04
  5763.3  583.74  5839.5  583.93  5855.4  584.58  5926.7  583.84  5954.9  584.73
#Mann= 14 ,-1 , 0
  4103.3    .045       0    4291    .035       0  4389.7     .07       0
  4488.4    .035       0  4587.2     .07       0  4764.1    .035       0
  4775.3     .07       0    4791     .05       0    4982    .035       0
  5080.8     .07       0  5179.5    .045       0  5205.8    .035       0
  5356.6    .045       0  5763.3    .035       0
Bank Sta=4764.1,4775.3
XS Rating Curve= 0 ,0
Exp/Cntr=0.3,0.1

Type RM Length L Ch R = 1 ,6297    ,496,496,496
BEGIN DESCRIPTION:
A18984
END DESCRIPTION:
XS GIS Cut Line= 3
      2299113.48     13793631.02      2297875.32     13793674.98
      2297303.87     13793814.18
#Sta/Elev= 30
  4049.2  590.67  4197.8  589.23  4246.5  589.42  4257.8  589.48  4297.6  587.51
  4477.8  583.39    4518   582.8  4583.6  580.64  4651.1  579.56  4798.1  577.04
  4908.2  577.61  4978.3  577.16  4998.3  576.65  5002.6  575.84  5003.1  575.34
  5013.4  575.34  5013.9  575.84  5018.3  577.31  5048.3  576.75  5108.3  579.54
  5118.4  579.29  5145.6   580.2  5198.4   579.7  5241.8  580.15    5506  582.03
  5630.3  582.73  5720.7  583.36  5741.3  584.39  5812.3  585.11  5876.3  584.49
#Mann= 10 ,-1 , 0
  4049.2    .045       0  4246.5     .07       0  4477.8     .05       0
  4651.1     .07       0  5002.6     .05       0  5013.9     .07       0
  5241.8    .035       0    5506    .045       0  5630.3    .035       0
  5812.3     .07       0
Bank Sta=5002.6,5013.9
XS Rating Curve= 0 ,0
Exp/Cntr=0.3,0.1

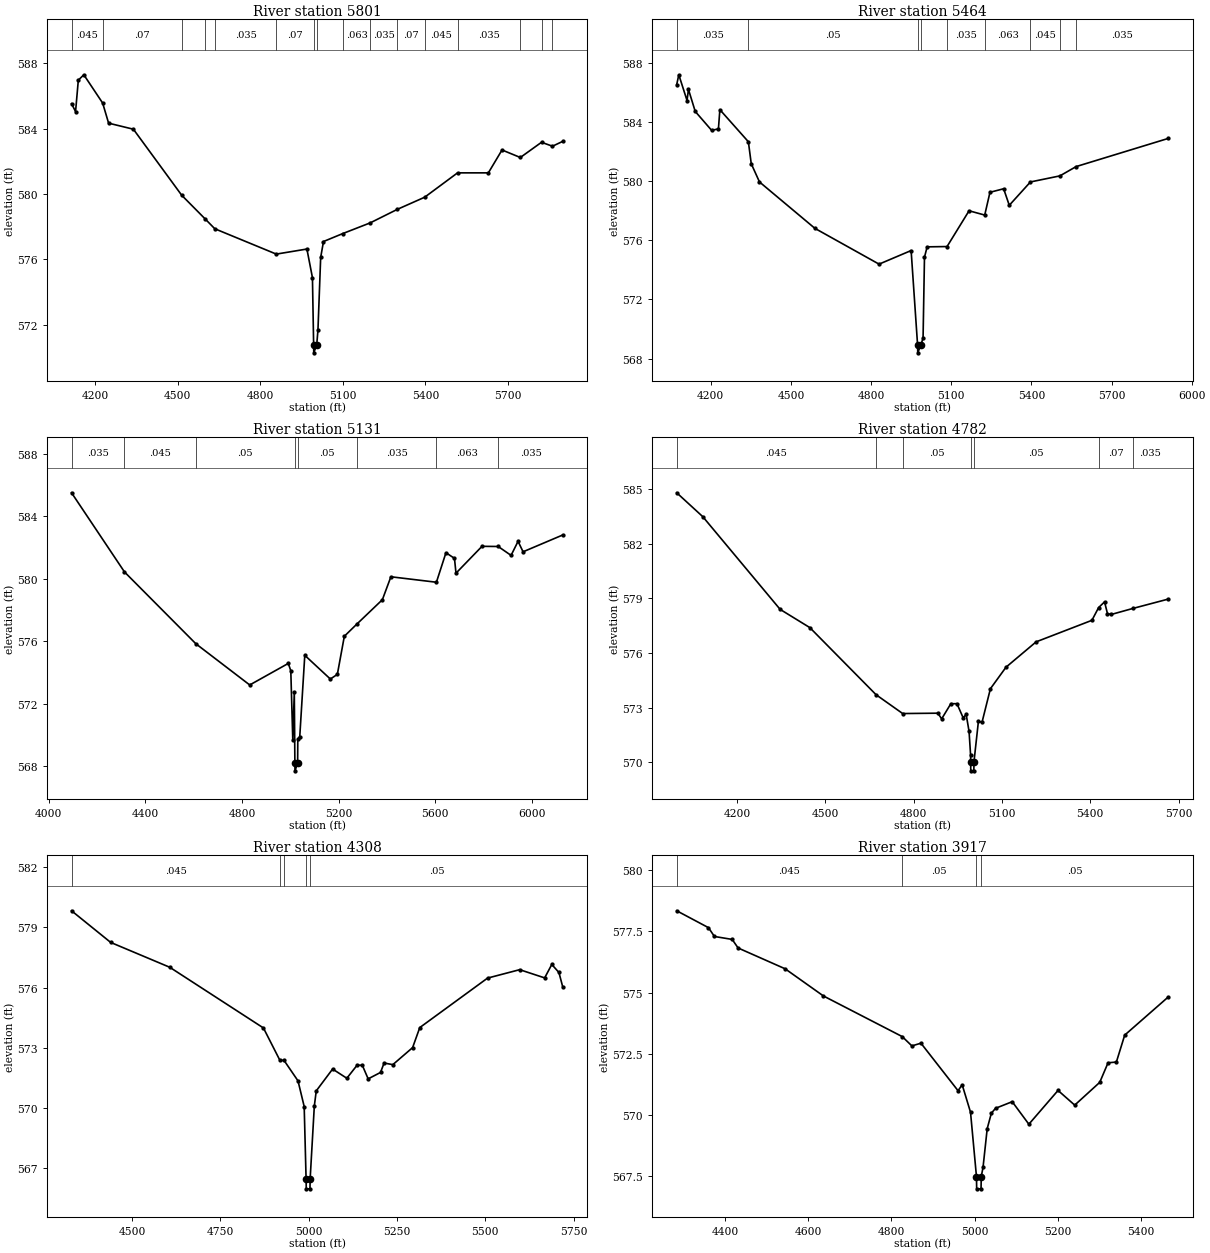
Type RM Length L Ch R = 1 ,5801    ,337,337,337
BEGIN DESCRIPTION:
A18983
END DESCRIPTION:
XS GIS Cut Line= 4
       2298959.6     13793198.77      2298168.37     13793191.45
      2297662.86     13793228.08      2297245.31     13793477.15
#Sta/Elev= 30
  4114.9  585.52  4129.5  585.04  4139.5  586.96  4159.5  587.29  4227.9  585.56
  4249.5  584.33  4339.5  583.96    4515  579.92  4600.2  578.47  4635.2  577.87
  4858.5  576.32  4969.7  576.63  4989.8  574.88  4994.1  570.78  4994.6  570.28
  5005.4  570.78  5009.8  571.67  5019.7  576.12  5029.9  577.09  5100.5  577.58
  5199.5  578.23  5298.4  579.06  5397.4   579.8  5516.8  581.29  5628.7  581.29
  5678.3  582.69  5744.8  582.23  5821.7  583.16  5861.6  582.92  5899.2  583.22
#Mann= 16 ,-1 , 0
  4114.9    .045       0  4227.9     .07       0    4515    .035       0
  4600.2     .07       0  4635.2    .035       0  4858.5     .07       0
  4994.1     .05       0  5005.4     .07       0  5100.5    .063       0
  5199.5    .035       0  5298.4     .07       0  5397.4    .045       0
  5516.8    .035       0  5744.8     .07       0  5821.7    .035       0
  5861.6     .07       0
Bank Sta=4994.1,5005.4
XS Rating Curve= 0 ,0
Exp/Cntr=0.3,0.1

Type RM Length L Ch R = 1 ,5464    ,333,333,333
BEGIN DESCRIPTION:
A18982
END DESCRIPTION:
XS GIS Cut Line= 4
      2298922.98     13793074.23      2298454.09     13792905.72
      2297911.95      13792898.4      2297245.26     13793337.98
#Sta/Elev= 30
  4072.5  586.54  4080.3   587.2  4111.1  585.46  4116.4  586.21  4141.8  584.72
  4203.2  583.44  4228.6  583.54    4234  584.84  4340.7  582.67  4351.5  581.18
  4382.3  579.95  4589.8  576.81  4829.9  574.39  4949.9  575.31  4974.2  568.89
  4974.7  568.39  4985.6  568.89  4994.6  569.38  4999.9  574.86  5009.9  575.56
  5084.4  575.58  5166.8     578  5225.4  577.71    5245  579.25  5296.2  579.49
  5317.3  578.37  5396.5  579.95  5506.7  580.36  5567.6  580.99  5911.5  582.89
#Mann= 9 ,-1 , 0
  4072.5    .035       0  4340.7     .05       0  4974.2     .05       0
  4985.6     .05       0  5084.4    .035       0  5225.4    .063       0
  5396.5    .045       0  5506.7    .063       0  5567.6    .035       0
Bank Sta=4974.2,4985.6
XS Rating Curve= 0 ,0
Exp/Cntr=0.3,0.1

Type RM Length L Ch R = 1 ,5131    ,349,349,349
BEGIN DESCRIPTION:
GERONIMO TRIBUTARY 11 2.0
END DESCRIPTION:
XS GIS Cut Line= 3
      2298875.02     13792975.01        2298075.       13792575.
      2297175.02     13793274.99
#Sta/Elev= 30
  4094.4  585.51  4313.6  580.44  4609.2  575.84  4832.3   573.2    4992  574.58
  5002.4  574.11  5010.6  569.69  5016.9  572.75  5019.3   568.2  5019.8   567.7
  5030.7   568.2  5031.4  569.74  5039.5  569.89  5060.3   575.1  5166.2  573.58
  5195.2  573.88  5224.1  576.32  5275.3  577.09  5381.6  578.66  5416.9  580.13
  5605.4  579.78  5644.9  581.67  5680.2  581.31  5686.5  580.36  5794.2  582.08
  5861.2  582.07  5914.6   581.5  5943.5   582.4  5964.3  581.73    6129  582.81
#Mann= 8 ,-1 , 0
  4094.4    .035       0  4313.6    .045       0  4609.2     .05       0
  5019.3     .05       0  5030.7     .05       0  5275.3    .035       0
  5605.4    .063       0  5861.2    .035       0
Bank Sta=5019.3,5030.7
XS Rating Curve= 0 ,0
Exp/Cntr=0.3,0.1

Type RM Length L Ch R = 1 ,4782    ,474,474,474
BEGIN DESCRIPTION:
A18981
END DESCRIPTION:
XS GIS Cut Line= 3
      2299150.09     13792546.74      2298058.48     13792231.71
       2297598.5     13792501.86
#Sta/Elev= 30
  3994.7  584.78  4083.3  583.47  4346.1  578.39  4447.1  577.39  4672.3  573.71
  4762.6  572.68    4882   572.7  4895.1  572.39  4926.3  573.22  4947.1  573.22
    4968  572.45  4978.4  572.63  4988.2   571.7  4993.4  570.39  4993.5  570.04
    4994  569.54  5004.4  569.54  5004.9  570.04    5020  572.26  5032.2   572.2
  5060.7  574.04  5113.7  575.22  5216.1  576.61  5405.7  577.79  5428.5  578.49
  5448.6   578.8  5458.5  578.16  5471.2  578.11  5544.7  578.44  5664.3  578.95
#Mann= 7 ,-1 , 0
  3994.7    .045       0  4672.3    .035       0  4762.6     .05       0
  4993.5     .05       0  5004.9     .05       0  5428.5     .07       0
  5544.7    .035       0
Bank Sta=4993.5,5004.9
XS Rating Curve= 0 ,0
Exp/Cntr=0.3,0.1

Type RM Length L Ch R = 1 ,4308    ,391,391,391
BEGIN DESCRIPTION:
A18980
END DESCRIPTION:
XS GIS Cut Line= 3
      2299135.47     13792253.71      2298373.51     13791909.36
      2297824.05     13791989.95
#Sta/Elev= 30
  4328.2  579.83  4439.1  578.25  4606.4  577.01  4871.7  573.98  4918.2  572.37
  4930.1  572.36  4969.6  571.34  4987.1  570.06  4992.5  566.45    4993  565.95
  5003.5  565.95    5004  566.45  5015.8  570.08  5021.3  570.84  5067.6  571.93
  5107.9  571.47  5136.9  572.12  5151.7  572.12  5168.3  571.44  5203.3  571.76
  5213.4  572.23  5238.2  572.15  5294.2     573  5314.5     574  5506.5  576.47
  5597.5  576.89  5668.2  576.48  5688.4  577.15  5708.6  576.75  5719.7  576.01
#Mann= 5 ,-1 , 0
  4328.2    .045       0  4918.2    .035       0  4930.1     .05       0
  4992.5     .05       0    5004     .05       0
Bank Sta=4992.5,5004
XS Rating Curve= 0 ,0
Exp/Cntr=0.3,0.1

Type RM Length L Ch R = 1 ,3917    ,550,550,550
BEGIN DESCRIPTION:
A18979
END DESCRIPTION:
XS GIS Cut Line= 3
      2299128.13     13792099.87      2298717.84     13791630.96
      2298161.08     13791601.66
#Sta/Elev= 30
  4284.4  578.34  4360.7  577.65    4375  577.29  4417.7  577.17  4431.9  576.82
  4544.9  575.97  4636.9  574.86  4826.3   573.2  4849.5  572.82  4871.3  572.93
  4960.4  570.99  4970.4  571.23  4990.4  570.11  5004.7  567.48  5005.2  566.98
  5015.7  566.98  5016.2  567.48  5020.5  567.86  5030.5  569.44  5040.5  570.07
  5050.5  570.27  5090.6  570.54  5130.6  569.62  5200.7     571  5240.8   570.4
  5300.9  571.33  5320.9  572.13  5340.9  572.16  5360.9  573.26    5465  574.81
#Mann= 4 ,-1 , 0
  4284.4    .045       0  4826.3     .05       0  5004.7     .05       0
  5016.2     .05       0
Bank Sta=5004.7,5016.2
XS Rating Curve= 0 ,0
Exp/Cntr=0.3,0.1

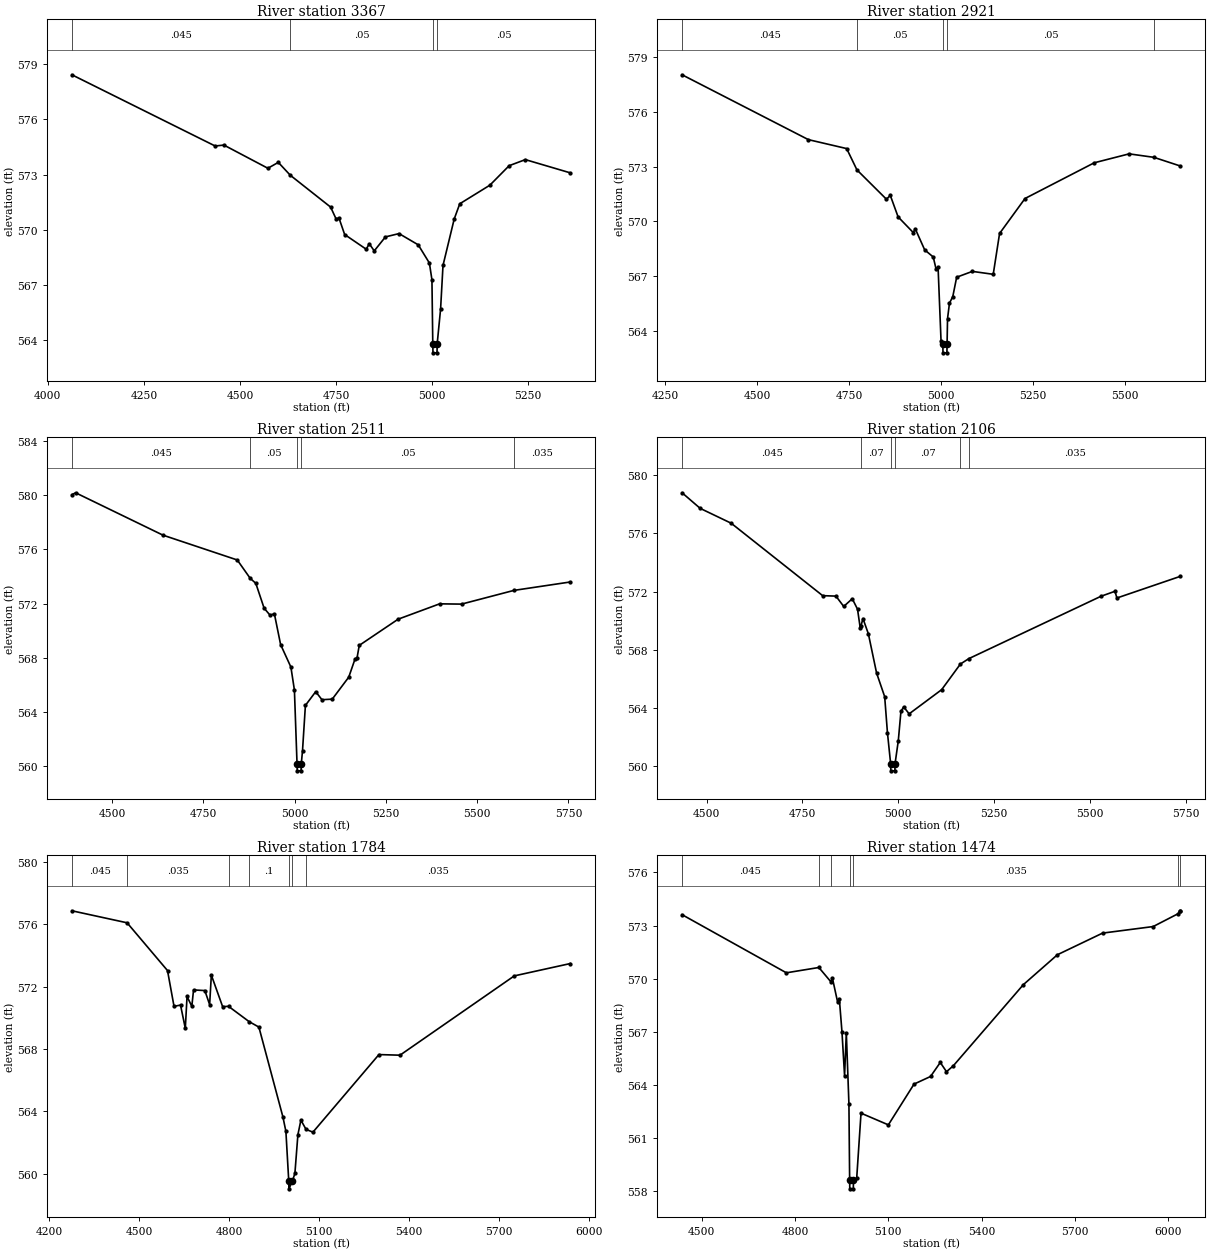
Type RM Length L Ch R = 1 ,3367    ,446,446,446
BEGIN DESCRIPTION:
A18978
END DESCRIPTION:
XS GIS Cut Line= 2
      2299172.05     13792041.21      2298388.18     13791008.26
#Sta/Elev= 30
  4062.9  578.42  4435.6  574.55  4458.4   574.6  4572.8  573.34  4599.9  573.66
  4631.1  572.96    4736  571.23  4749.7  570.61    4758  570.62  4772.5  569.74
  4828.7  568.94  4836.5  569.24  4849.5  568.85  4878.6  569.61    4914  569.79
  4963.9  569.18    4993  568.19  4999.6  567.28  5001.8  563.81  5002.3  563.31
  5012.8  563.31  5013.3  563.81  5022.1  565.69  5028.4  568.06  5057.5  570.58
    5072  571.41  5150.3  572.42  5200.5  573.48  5242.6  573.81  5359.6  573.09
#Mann= 4 ,-1 , 0
  4062.9    .045       0  4631.1     .05       0  5001.8     .05       0
  5013.3     .05       0
Bank Sta=5001.8,5013.3
XS Rating Curve= 0 ,0
Exp/Cntr=0.3,0.1

Type RM Length L Ch R = 1 ,2921    ,410,410,410
BEGIN DESCRIPTION:
A18977
END DESCRIPTION:
XS GIS Cut Line= 3
      2299208.71      13791938.7      2298900.99     13791059.52
      2298505.34     13790912.98
#Sta/Elev= 30
  4296.9  578.04  4639.9  574.48  4743.8  573.99  4771.7  572.82  4851.8  571.21
  4862.3  571.42  4883.5  570.24  4924.7  569.38    4930  569.59  4955.7  568.43
  4978.9  568.04  4986.7  567.37    4992  567.49  5000.1  563.42  5004.9  563.28
  5005.4  562.78    5016  562.78  5016.5  563.28  5017.7  564.66    5023  565.51
  5031.9  565.86  5042.5  566.93  5085.1  567.25  5141.8  567.09    5159  569.33
  5228.1  571.25  5416.1  573.21  5510.8   573.7  5577.9  573.51  5650.3  573.03
#Mann= 5 ,-1 , 0
  4296.9    .045       0  4771.7     .05       0  5004.9     .05       0
  5016.5     .05       0  5577.9    .035       0
Bank Sta=5004.9,5016.5
XS Rating Curve= 0 ,0
Exp/Cntr=0.3,0.1

Type RM Length L Ch R = 1 ,2511    ,405,405,405
BEGIN DESCRIPTION:
A18976
END DESCRIPTION:
XS GIS Cut Line= 3
      2299648.29     13791814.16      2299274.63     13791037.54
      2298791.11     13790898.34
#Sta/Elev= 30
  4390.3  580.02  4400.5  580.16  4639.6  577.04  4843.2  575.21  4878.6  573.86
    4894  573.49  4916.7  571.66  4933.1  571.14  4944.8  571.25  4961.9  568.98
  4990.1  567.32  4999.7  565.63  5006.9  560.18  5007.4  559.68    5018  559.68
  5018.5  560.18  5021.9  561.17  5029.8   564.5    5058  565.51  5075.1  564.92
  5103.3  564.96  5148.5  566.58  5165.6  567.91  5171.1  567.98  5177.3  568.92
  5283.8  570.85  5397.4  571.98  5457.4  571.96  5600.8  572.97  5755.3  573.59
#Mann= 5 ,-1 , 0
  4390.3    .045       0  4878.6     .05       0  5006.9     .05       0
  5018.5     .05       0  5600.8    .035       0
Bank Sta=5006.9,5018.5
XS Rating Curve= 0 ,0
Exp/Cntr=0.3,0.1

Type RM Length L Ch R = 1 ,2106    ,322,322,322
BEGIN DESCRIPTION:
A18975
END DESCRIPTION:
XS GIS Cut Line= 4
      2299875.38     13791601.66      2299809.45     13791169.41
      2299582.33     13790934.97      2299048.74      13790883.8
#Sta/Elev= 30
  4436.3  578.78  4483.5  577.71  4564.4  576.69  4802.9  571.72  4837.5  571.69
  4857.8  570.98  4880.1  571.51  4893.8  570.79    4901  569.48  4902.7  569.64
    4908  570.15  4922.1   569.1  4943.5  566.41  4964.6  564.79  4971.8  562.32
  4980.1   560.2  4980.6   559.7  4991.2   559.7  4991.7   560.2  5000.1  561.76
    5007  563.78  5014.2  564.09  5028.4  563.61  5113.2  565.27  5162.1  567.03
  5184.1   567.4  5528.8  571.68  5565.1  572.02  5570.2  571.56    5736  573.05
#Mann= 6 ,-1 , 0
  4436.3    .045       0  4902.7     .07       0  4980.1     .05       0
  4991.7     .07       0  5162.1     .05       0  5184.1    .035       0
Bank Sta=4980.1,4991.7
XS Rating Curve= 0 ,0
Exp/Cntr=0.3,0.1

Type RM Length L Ch R = 1 ,1784    ,310,310,310
BEGIN DESCRIPTION:
A18974
END DESCRIPTION:
XS GIS Cut Line= 4
      2300527.45     13791096.16      2300043.89     13790825.08
      2299538.38     13790810.42      2298938.77      13790854.3
#Sta/Elev= 30
  4276.7  576.85  4460.7  576.08  4595.4  573.02  4617.1  570.73  4638.8  570.81
  4654.7  569.32  4660.5  571.36  4676.4  570.73  4682.2  571.78  4719.8  571.74
  4735.8  570.84  4741.5  572.73  4779.1  570.71  4798.8  570.73  4867.4  569.75
    4900   569.4    4980  563.65    4990  562.72  4999.5  559.54    5000  559.04
  5011.8  559.54    5020  560.03    5030  562.51    5040  563.44  5057.1  562.85
  5080.1  562.67  5300.1  567.64  5370.3   567.6  5751.3  572.68    5938  573.47
#Mann= 7 ,-1 , 0
  4276.7    .045       0  4460.7    .035       0  4798.8    .045       0
  4867.4      .1       0  4999.5     .05       0  5011.8      .1       0
  5057.1    .035       0
Bank Sta=4999.5,5011.8
XS Rating Curve= 0 ,0
Exp/Cntr=0.3,0.1

Type RM Length L Ch R = 1 ,1474    ,412,412,412
BEGIN DESCRIPTION:
GERONIMO TRIBUTARY 11 1.0
END DESCRIPTION:
XS GIS Cut Line= 3
      2300324.97     13790774.99        2299825.       13790525.
      2298825.01       13790825.
#Sta/Elev= 30
  4436.9  573.62  4772.3  570.34  4876.8  570.64  4915.1  569.84  4920.4  570.04
  4937.2  568.68  4942.8  568.84  4951.2  566.99  4959.5  564.53  4965.1  566.96
  4973.5  562.94  4975.8  558.65  4976.3  558.15  4987.6  558.15  4988.1  558.65
  4998.5  558.75  5012.4  562.42  5100.3  561.76  5182.9  564.06    5236  564.49
  5267.3  565.28  5287.3  564.76  5309.1  565.09  5534.4  569.67  5644.1  571.36
  5789.3  572.58    5952  572.95  6031.7  573.67  6039.2  573.84  6039.9  573.84
#Mann= 7 ,-1 , 0
  4436.9    .045       0  4876.8      .1       0  4915.1    .035       0
  4975.8    .035       0  4988.1    .035       0  6031.7     .07       0
  6039.2    .035       0
Bank Sta=4975.8,4988.1
XS Rating Curve= 0 ,0
Exp/Cntr=0.3,0.1