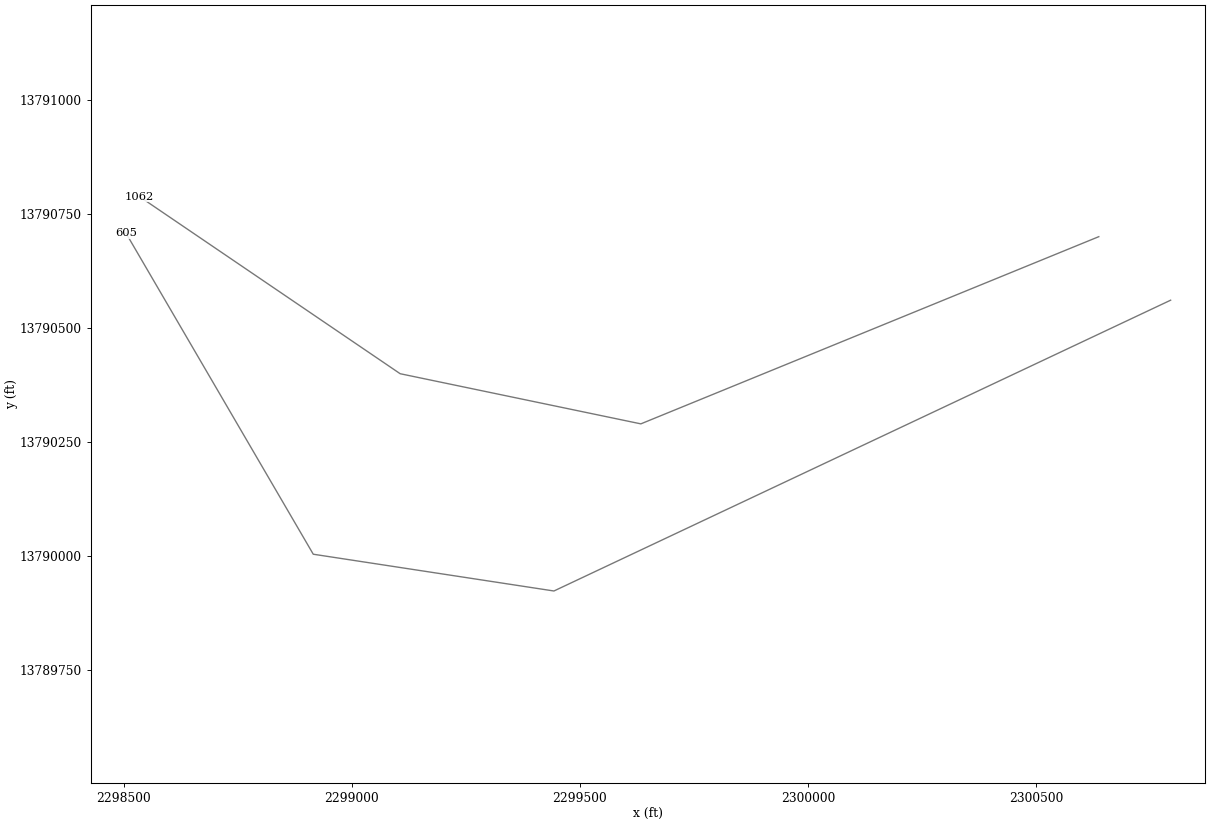
HEC-RAS study GERONIMO TRIBUTARY 11.prj: GERONIMO TRIBUTARY 11 Base Level Engineering

--- GERONIMO TRIBUTARY 11.g01 (geometry) --- (continued)

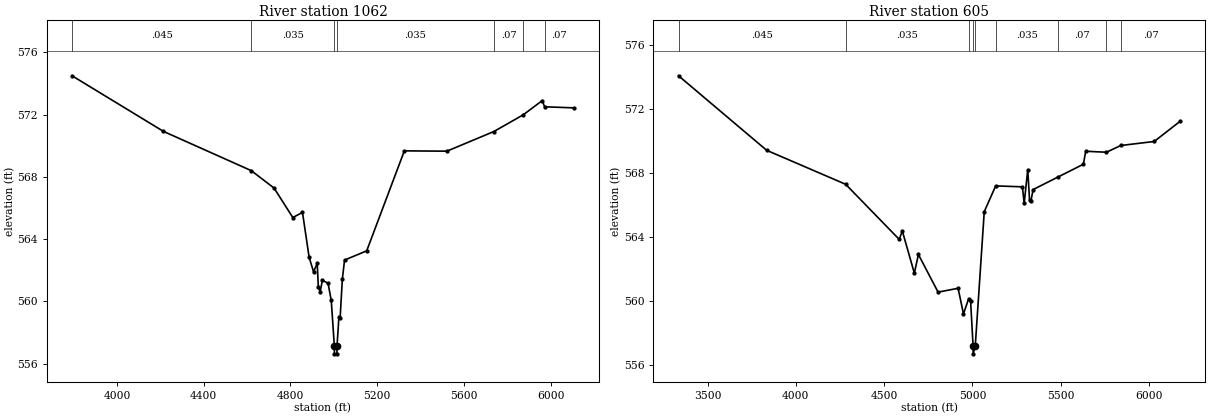
Type RM Length L Ch R = 1 ,1062    ,457,457,457
BEGIN DESCRIPTION:
A18973
END DESCRIPTION:
XS GIS Cut Line= 4
      2300637.35     13790700.55      2299633.62     13790290.26
      2299106.13     13790400.16      2298534.64     13790788.47
#Sta/Elev= 30
  3793.1  574.49  4214.5  570.92  4619.6   568.4  4724.8  567.28  4811.1  565.39
  4855.7  565.72  4886.3  562.84  4906.7  561.91  4923.6  562.44  4928.7  560.96
  4937.3  560.62  4947.5  561.37  4973.7  561.16  4988.4  560.07  5002.6  557.14
  5003.1  556.64  5014.5  556.64    5015  557.14  5023.7     559  5029.3  558.94
  5039.5  561.43  5049.7  562.66  5151.8  563.25  5325.5  569.67  5521.6  569.65
    5738  570.91  5873.3  571.98  5961.6   572.9  5972.1   572.5  6107.2  572.43
#Mann= 7 ,-1 , 0
  3793.1    .045       0  4619.6    .035       0  5002.6    .035       0
    5015    .035       0    5738     .07       0  5873.3    .035       0
  5972.1     .07       0
Bank Sta=5002.6,5015
XS Rating Curve= 0 ,0
Exp/Cntr=0.3,0.1

Type RM Length L Ch R = 1 ,605     ,0,0,0
BEGIN DESCRIPTION:
A18972
END DESCRIPTION:
XS GIS Cut Line= 4
      2300794.81     13790561.32      2299443.14     13789923.95
      2298915.65     13790004.54      2298505.35      13790707.9
#Sta/Elev= 30
  3335.4  574.05  3834.6   569.4  4281.9  567.28  4585.6  563.84  4602.9  564.37
  4671.2  561.73    4694   562.9  4805.6  560.55    4919  560.79  4949.3  559.19
  4978.7  560.14  4989.8  559.98  5003.8   557.2  5004.3   556.7  5016.2   557.2
  5067.1  565.57  5131.8  567.18  5283.1  567.12  5293.3   566.1  5313.5  568.19
  5323.6  566.29    5331  566.21  5343.8  566.95  5485.9  567.74  5628.5  568.53
  5641.8  569.34  5759.3  569.28  5840.4   569.7  6029.6  569.95  6177.7  571.22
#Mann= 9 ,-1 , 0
  3335.4    .045       0  4281.9    .035       0  4978.7     .07       0
  5003.8     .05       0  5016.2     .07       0  5131.8    .035       0
  5485.9     .07       0  5759.3    .035       0  5840.4     .07       0
Bank Sta=5003.8,5016.2
XS Rating Curve= 0 ,0
Exp/Cntr=0.3,0.1

Chan Stop Cuts=-1
Use User Specified Reach Order=0
Composite Channel Slope=5