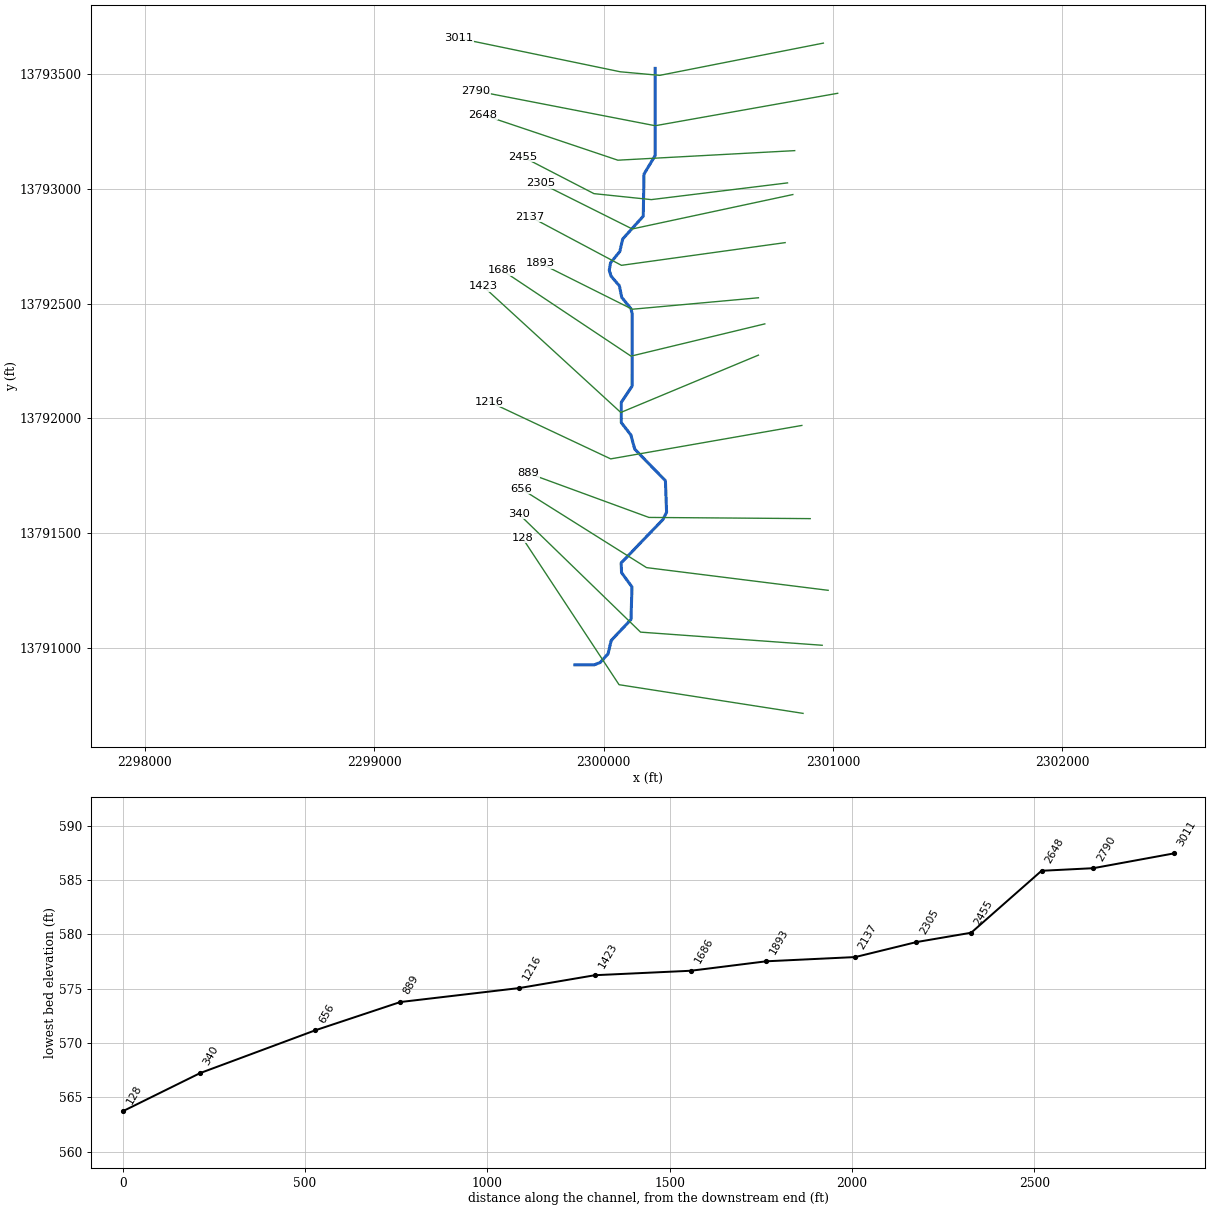
--- GERONIMO TRIBUTARY 12.prj (project) ---

Proj Title=GERONIMO TRIBUTARY 12 Base Level Engineering
Current Plan=p01
Default Exp/Contr=0.3,0.1
English Units
Geom File=g01
Flow File=f01
Plan File=p01
BEGIN DESCRIPTION:
GERONIMO TRIBUTARY 12
END DESCRIPTION:

--- GERONIMO TRIBUTARY 12.p01 (plan) ---

Plan Title=Multiple Run
Short Identifier=Multiple
Geom File=g01
Flow File=f01
Subcritical Flow
K Sum by GR= 0
Std Step Tol= 0.01
Critical Tol= 0.01
Num of Std Step Trials= 20
Max Error Tol= 0.3
Flow Tol Ratio= 0.001
Split Flow NTrial= 30
Split Flow Tol= 0.02
Split Flow Ratio= 0.02
Log Output Level= 0
Friction Slope Method= 1
Unsteady Friction Slope Method= 2
Unsteady Bridges Friction Slope Method= 1
Parabolic Critical Depth
Global Vel Dist=  1 , 1 , 1
Global Log Level= 0
CheckData=True
Encroach Param= -1, 0, 0, 0
BEGIN DESCRIPTION:
Multiple Run
END DESCRIPTION:

--- GERONIMO TRIBUTARY 12.f01 (steady flow) ---

Flow Title=Multiple
Number of Profiles=7
Profile Names=10-year,25-year,50-year,1pct_min,100-year,1pct_plu,500-year
River Rch & RM= GERONIMO TRIBUTA,Reach-1,3011
     360     561     737     471     939    1874    1507
Boundary for River Rch & Prof#=GERONIMO TRIBUTA,Reach-1,1
Up Type=0
Dn Type=3
Dn Slope=0.005
Boundary for River Rch & Prof#=GERONIMO TRIBUTA,Reach-1,2
Up Type=0
Dn Type=3
Dn Slope=0.005
Boundary for River Rch & Prof#=GERONIMO TRIBUTA,Reach-1,3
Up Type=0
Dn Type=3
Dn Slope=0.005
Boundary for River Rch & Prof#=GERONIMO TRIBUTA,Reach-1,4
Up Type=0
Dn Type=3
Dn Slope=0.005
Boundary for River Rch & Prof#=GERONIMO TRIBUTA,Reach-1,5
Up Type=0
Dn Type=3
Dn Slope=0.005
Boundary for River Rch & Prof#=GERONIMO TRIBUTA,Reach-1,6
Up Type=0
Dn Type=3
Dn Slope=0.005
Boundary for River Rch & Prof#=GERONIMO TRIBUTA,Reach-1,7
Up Type=0
Dn Type=3
Dn Slope=0.005

--- GERONIMO TRIBUTARY 12.g01 (geometry) ---

Geom Title=Existing Conditions

River Reach=GERONIMO TRIBUTA,Reach-1
Reach XY= 30
      2300225.00     13793525.00      2300224.93     13793145.03
      2300176.22     13793064.49      2300172.93     13792880.86
      2300083.16     13792781.05      2300070.75     13792726.74
      2300030.33     13792677.20      2300024.70     13792645.18
      2300032.76     13792619.06      2300068.84     13792577.20
      2300079.19     13792526.74      2300119.29     13792477.35
      2300124.94     13792454.97      2300124.48     13792140.22
      2300077.17     13792069.02      2300077.14     13791980.97
      2300118.85     13791927.17      2300135.76     13791865.32
      2300269.55     13791727.45      2300274.64     13791590.16
      2300258.57     13791558.24      2300076.62     13791368.97
      2300078.34     13791326.75      2300123.77     13791264.50
      2300119.53     13791122.56      2300033.18     13791031.02
      2300019.27     13790972.43      2299985.18     13790935.29
      2299960.11     13790925.05      2299875.00     13790925.00

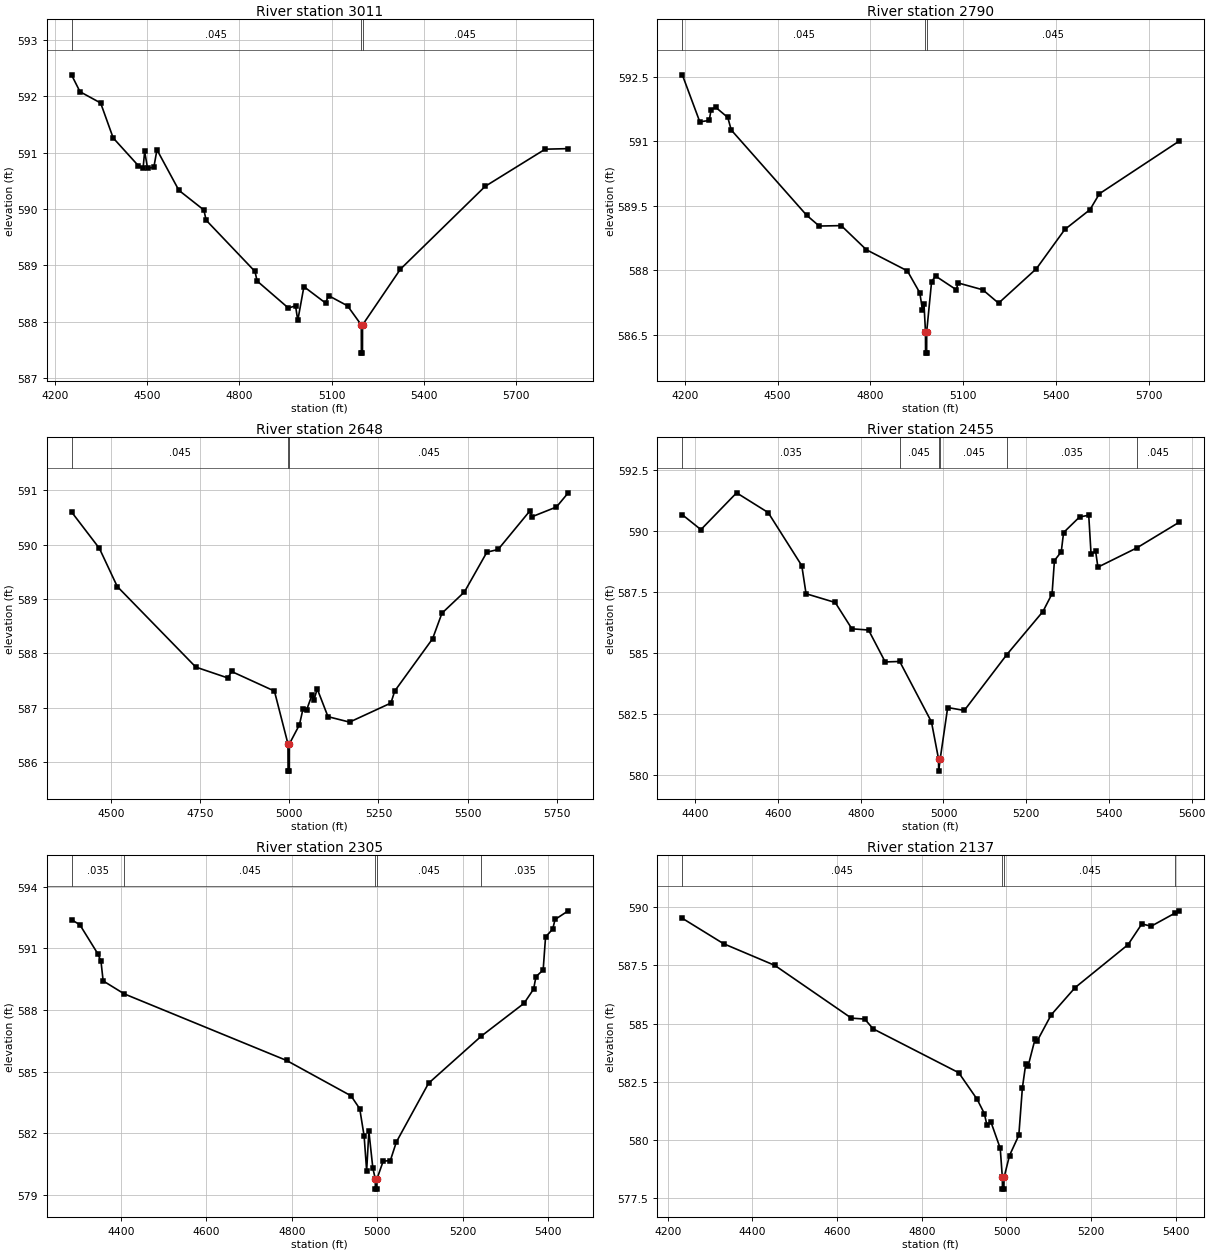
Type RM Length L Ch R = 1,3011,221,221,221
BEGIN DESCRIPTION:
A19003
END DESCRIPTION:
XS GIS Cut Line= 4
      2300958.10     13793635.18      2300244.55     13793494.55
      2300072.67     13793510.18      2299369.79     13793655.96
#Sta/Elev= 30
  4253.1  592.38  4280.8  592.08  4348.0  591.88  4388.8  591.26  4470.3  590.77
  4486.2  590.72  4491.3  591.02  4500.9  590.72  4521.3  590.74  4531.4  591.05
  4602.8  590.33  4684.3  589.98  4691.5  589.80  4850.6  588.89  4857.6  588.72
  4959.5  588.24  4982.7  588.28  4990.0  588.02  5010.0  588.62  5080.3  588.33
  5090.4  588.46  5152.0  588.28  5196.9  587.94  5197.2  587.44  5200.7  587.44
  5200.9  587.94  5324.2  588.93  5600.2  590.40  5795.7  591.06  5870.8  591.07
#Mann=3,-1,0
  4253.1   0.045       0  5196.9   0.045       0  5200.9   0.045       0
Bank Sta=5196.9,5200.9
Exp/Cntr=0.3,0.1

Type RM Length L Ch R = 1,2790,142,142,142
BEGIN DESCRIPTION:
GERONIMO TRIBUTARY 12 5.0
END DESCRIPTION:
XS GIS Cut Line= 3
      2301020.55     13793416.42      2300225.00     13793275.00
      2299442.42     13793426.85
#Sta/Elev= 30
  4192.0  592.54  4248.4  591.45  4278.9  591.48  4284.9  591.73  4299.2  591.79
  4338.9  591.55  4350.0  591.26  4593.8  589.28  4634.4  589.03  4705.5  589.04
  4786.7  588.48  4919.1  587.99  4959.4  587.48  4968.0  587.08  4973.0  587.21
  4977.7  586.58  4978.0  586.08  4981.5  586.08  4981.7  586.58  4997.5  587.74
  5010.2  587.87  5077.6  587.55  5082.7  587.71  5163.0  587.55  5213.9  587.24
  5336.2  588.04  5427.9  588.95  5509.3  589.41  5539.9  589.78  5797.2  591.00
#Mann=3,-1,0
  4192.0   0.045       0  4977.7   0.045       0  4981.7   0.045       0
Bank Sta=4977.7,4981.7
Exp/Cntr=0.3,0.1

Type RM Length L Ch R = 1,2648,193,193,193
BEGIN DESCRIPTION:
A19002
END DESCRIPTION:
XS GIS Cut Line= 3
      2300833.13     13793166.43      2300062.25     13793124.76
      2299473.74     13793322.67
#Sta/Elev= 30
  4389.3  590.60  4467.5  589.93  4517.6  589.23  4737.9  587.75  4828.1  587.55
  4838.1  587.67  4958.3  587.31  4996.3  586.34  4996.6  585.84  5000.1  585.84
  5000.3  586.34  5028.4  586.69  5038.4  586.98  5048.4  586.96  5063.8  587.24
  5068.8  587.14  5078.4  587.35  5108.5  586.84  5169.0  586.74  5285.0  587.09
  5295.6  587.31  5401.8  588.27  5428.1  588.74  5491.1  589.13  5554.1  589.86
  5585.6  589.91  5674.9  590.62  5680.2  590.51  5749.2  590.69  5782.2  590.95
#Mann=3,-1,0
  4389.3   0.045       0  4996.3   0.045       0  5000.3   0.045       0
Bank Sta=4996.3,5000.3
Exp/Cntr=0.3,0.1

Type RM Length L Ch R = 1,2455,150,150,150
BEGIN DESCRIPTION:
A19001
END DESCRIPTION:
XS GIS Cut Line= 4
      2300801.83     13793025.80      2300208.09     13792952.89
      2299958.09     13792978.93      2299645.94     13793140.20
#Sta/Elev= 30
  4368.7  590.66  4413.6  590.05  4499.9  591.56  4576.2  590.75  4657.5  588.57
  4667.8  587.42  4738.3  587.06  4778.6  585.98  4818.9  585.93  4859.2  584.62
  4894.2  584.64  4971.0  582.16  4988.1  580.64  4988.4  580.14  4992.1  580.64
  5010.2  582.75  5050.4  582.63  5153.1  584.92  5240.5  586.69  5262.6  587.42
  5268.3  588.78  5284.8  589.14  5290.4  589.93  5329.1  590.57  5351.2  590.64
  5356.9  589.03  5367.8  589.17  5373.4  588.51  5467.5  589.30  5569.6  590.35
#Mann=6,-1,0
  4368.7   0.035       0  4894.2   0.045       0  4988.1   0.045       0
  4992.1   0.045       0  5153.1   0.035       0  5467.5   0.045       0
Bank Sta=4988.1,4992.1
Exp/Cntr=0.3,0.1

Type RM Length L Ch R = 1,2305,168,168,168
BEGIN DESCRIPTION:
GERONIMO TRIBUTARY 12 4.0
END DESCRIPTION:
XS GIS Cut Line= 3
      2300824.96     13792974.99      2300125.00     13792825.00
      2299724.97     13793025.01
#Sta/Elev= 30
  4284.2  592.39  4303.8  592.14  4345.5  590.74  4353.2  590.37  4358.3  589.41
  4407.6  588.78  4787.8  585.54  4938.7  583.82  4959.1  583.19  4969.4  581.86
  4975.3  580.17  4980.5  582.10  4989.8  580.30  4995.5  579.78  4995.7  579.28
  4999.2  579.28  4999.5  579.78  5014.0  580.64  5030.8  580.67  5044.8  581.57
  5120.2  584.43  5244.1  586.73  5343.8  588.32  5366.2  589.01  5371.8  589.62
  5388.6  589.94  5394.2  591.55  5410.9  591.93  5416.5  592.40  5447.3  592.82
#Mann=5,-1,0
  4284.2   0.035       0  4407.6   0.045       0  4995.5   0.045       0
  4999.5   0.045       0  5244.1   0.035       0
Bank Sta=4995.5,4999.5
Exp/Cntr=0.3,0.1

Type RM Length L Ch R = 1,2137,244,244,244
BEGIN DESCRIPTION:
A19000
END DESCRIPTION:
XS GIS Cut Line= 3
      2300791.47     13792765.39      2300077.88     13792666.43
      2299678.40     13792879.14
#Sta/Elev= 30
  4234.5  589.51  4331.9  588.42  4453.0  587.49  4633.7  585.23  4665.1  585.19
  4685.2  584.77  4887.2  582.89  4930.7  581.75  4947.7  581.14  4953.8  580.64
  4963.2  580.78  4985.2  579.65  4990.2  578.40  4990.4  577.90  4993.9  577.90
  4994.2  578.40  5007.1  579.34  5029.1  580.21  5037.5  582.24  5045.4  583.26
  5051.1  583.18  5067.4  584.33  5073.0  584.27  5105.5  585.37  5162.1  586.54
  5287.0  588.38  5319.6  589.27  5341.6  589.17  5397.7  589.73  5407.5  589.83
#Mann=4,-1,0
  4234.5   0.045       0  4990.2   0.045       0  4994.2   0.045       0
  5397.7   0.035       0
Bank Sta=4990.2,4994.2
Exp/Cntr=0.3,0.1

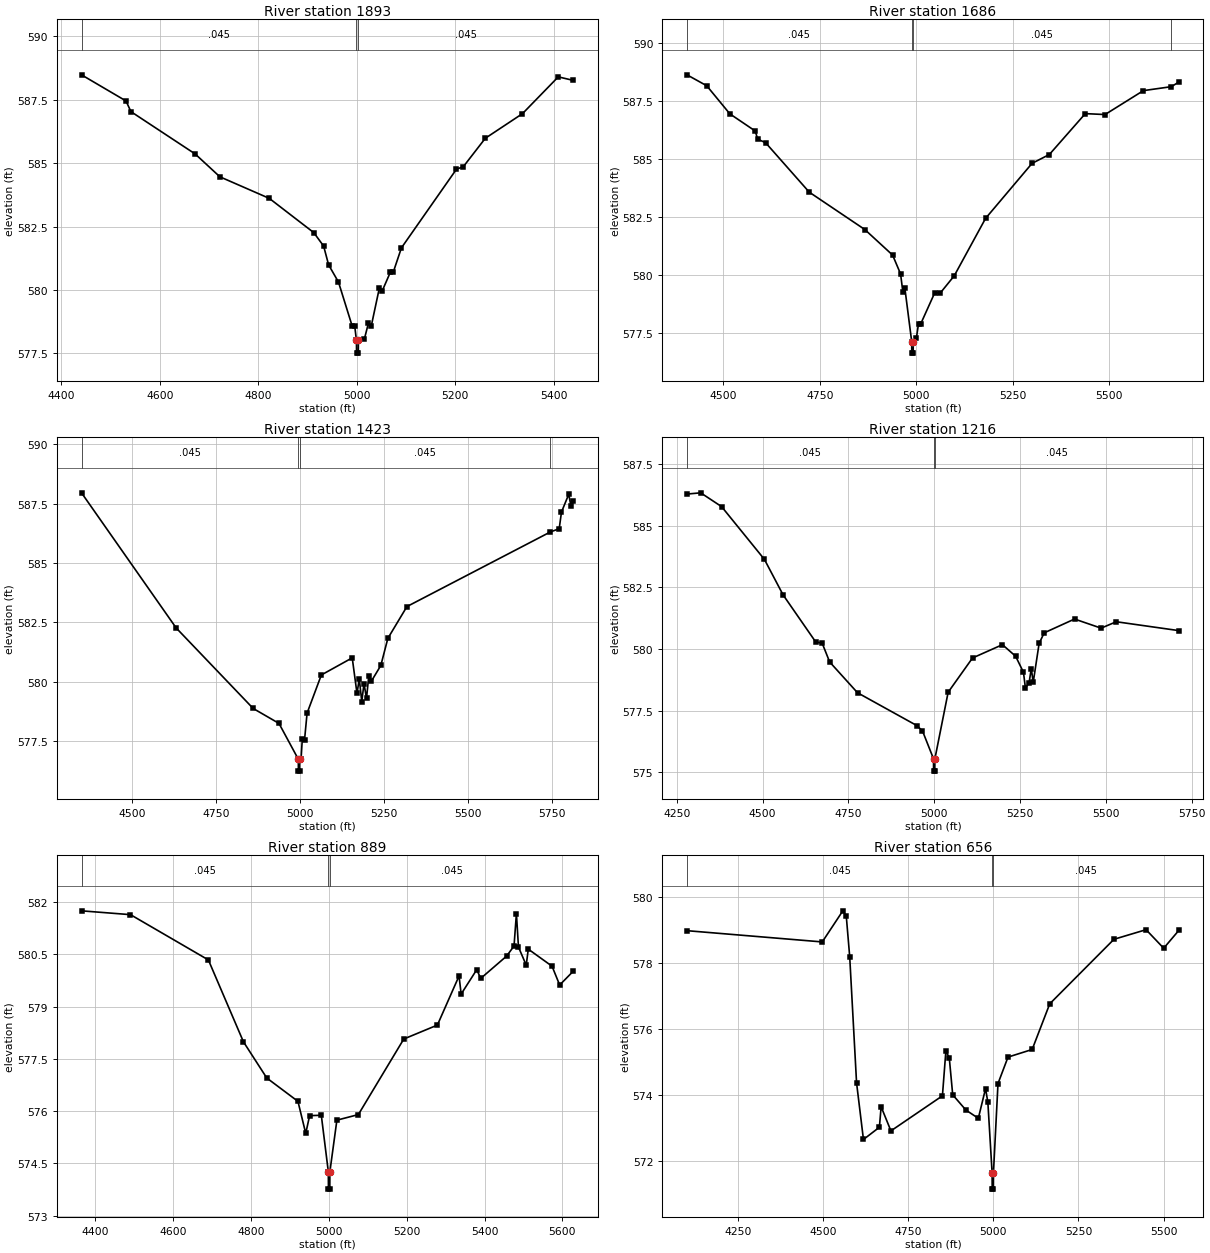
Type RM Length L Ch R = 1,1893,207,207,207
BEGIN DESCRIPTION:
GERONIMO TRIBUTARY 12 3.0
END DESCRIPTION:
XS GIS Cut Line= 3
      2300675.02     13792525.00      2300125.00     13792475.00
      2299725.00     13792675.00
#Sta/Elev= 30
  4440.8  588.48  4531.2  587.45  4541.2  587.03  4671.8  585.36  4722.0  584.46
  4822.4  583.61  4912.8  582.26  4932.8  581.73  4942.9  580.99  4963.0  580.31
  4990.6  578.59  4995.9  578.59  4999.5  578.01  4999.7  577.51  5003.2  577.51
  5003.5  578.01  5015.4  578.05  5023.8  578.69  5029.4  578.56  5046.2  580.09
  5051.8  579.96  5068.6  580.71  5074.1  580.69  5090.9  581.66  5202.7  584.76
  5216.7  584.86  5261.4  585.98  5336.9  586.95  5409.6  588.40  5440.3  588.26
#Mann=3,-1,0
  4440.8   0.045       0  4999.5   0.045       0  5003.5   0.045       0
Bank Sta=4999.5,5003.5
Exp/Cntr=0.3,0.1

Type RM Length L Ch R = 1,1686,263,263,263
BEGIN DESCRIPTION:
A18999
END DESCRIPTION:
XS GIS Cut Line= 3
      2300702.88     13792411.22      2300119.55     13792270.59
      2299558.53     13792644.60
#Sta/Elev= 30
  4405.6  588.62  4456.7  588.15  4516.6  586.94  4582.5  586.20  4588.6  585.85
  4609.1  585.70  4722.3  583.57  4866.3  581.96  4938.3  580.86  4958.9  580.05
  4964.8  579.28  4969.9  579.45  4987.7  577.14  4988.0  576.64  4991.5  576.64
  4991.7  577.14  5000.0  577.30  5005.4  577.91  5011.4  577.91  5047.2  579.23
  5061.9  579.23  5098.0  579.97  5179.1  582.44  5299.6  584.81  5344.4  585.19
  5437.5  586.95  5488.6  586.91  5588.0  587.94  5660.4  588.11  5679.9  588.31
#Mann=4,-1,0
  4405.6   0.045       0  4987.7   0.045       0  4991.7   0.045       0
  5660.4   0.035       0
Bank Sta=4987.7,4991.7
Exp/Cntr=0.3,0.1

Type RM Length L Ch R = 1,1423,207,207,207
BEGIN DESCRIPTION:
GERONIMO TRIBUTARY 12 2.0
END DESCRIPTION:
XS GIS Cut Line= 3
      2300674.99     13792275.00      2300075.00     13792025.00
      2299475.02     13792574.98
#Sta/Elev= 30
  4348.9  587.95  4630.6  582.26  4859.7  578.87  4936.6  578.24  4994.2  576.73
  4994.4  576.23  4997.9  576.23  4998.2  576.73  5002.3  576.73  5006.0  577.58
  5012.8  577.56  5020.2  578.67  5062.7  580.28  5154.6  581.00  5168.8  579.50
  5175.6  580.12  5183.0  579.16  5189.7  579.92  5197.1  579.29  5203.9  580.25
  5211.3  580.01  5239.7  580.68  5260.6  581.82  5317.4  583.16  5744.0  586.30
  5770.6  586.44  5777.4  587.14  5799.0  587.89  5805.7  587.38  5812.8  587.59
#Mann=4,-1,0
  4348.9   0.045       0  4994.2   0.045       0  4998.2   0.045       0
  5744.0   0.035       0
Bank Sta=4994.2,4998.2
Exp/Cntr=0.3,0.1

Type RM Length L Ch R = 1,1216,327,327,327
BEGIN DESCRIPTION:
A18998
END DESCRIPTION:
XS GIS Cut Line= 3
      2300864.29     13791968.50      2300031.00     13791822.68
      2299500.01     13792072.56
#Sta/Elev= 30
  4280.0  586.29  4319.9  586.34  4380.8  585.78  4505.5  583.64  4559.9  582.20
  4654.9  580.29  4673.8  580.24  4695.5  579.48  4776.7  578.23  4949.3  576.90
  4966.0  576.68  4998.1  575.55  4998.3  575.05  5001.8  575.05  5002.1  575.55
  5040.7  578.25  5111.7  579.64  5198.9  580.18  5237.3  579.71  5260.1  579.06
  5265.7  578.43  5276.3  578.62  5282.9  579.21  5288.5  578.65  5305.7  580.23
  5320.5  580.66  5408.9  581.22  5486.3  580.85  5530.5  581.11  5712.8  580.75
#Mann=3,-1,0
  4280.0   0.045       0  4998.1   0.045       0  5002.1   0.045       0
Bank Sta=4998.1,5002.1
Exp/Cntr=0.3,0.1

Type RM Length L Ch R = 1,889,233,233,233
BEGIN DESCRIPTION:
A18997
END DESCRIPTION:
XS GIS Cut Line= 3
      2300900.81     13791562.26      2300197.67     13791567.47
      2299671.90     13791760.08
#Sta/Elev= 30
  4365.0  581.75  4490.8  581.64  4690.8  580.34  4780.8  577.99  4840.8  576.95
  4920.8  576.28  4940.8  575.36  4950.8  575.87  4980.8  575.88  4998.8  574.26
  4999.1  573.76  5002.6  573.76  5002.8  574.26  5020.8  575.74  5075.9  575.90
  5192.6  578.07  5278.9  578.47  5334.5  579.88  5339.9  579.36  5379.9  580.06
  5390.2  579.81  5456.6  580.45  5475.7  580.74  5481.8  581.67  5487.1  580.71
  5507.0  580.19  5512.3  580.65  5573.3  580.16  5592.9  579.62  5628.1  580.02
#Mann=3,-1,0
  4365.0   0.045       0  4998.8   0.045       0  5002.8   0.045       0
Bank Sta=4998.8,5002.8
Exp/Cntr=0.3,0.1

Type RM Length L Ch R = 1,656,316,316,316
BEGIN DESCRIPTION:
A18996
END DESCRIPTION:
XS GIS Cut Line= 3
      2300978.89     13791249.76      2300187.25     13791348.72
      2299640.41     13791692.45
#Sta/Elev= 30
  4101.2  578.97  4498.2  578.63  4558.6  579.57  4568.7  579.41  4578.8  578.18
  4598.9  574.37  4619.1  572.66  4665.9  573.03  4671.0  573.65  4699.7  572.92
  4850.9  573.98  4861.0  575.33  4871.0  575.13  4881.1  574.01  4919.8  573.55
  4956.3  573.30  4977.5  574.20  4984.3  573.78  4996.7  571.66  4997.0  571.16
  5000.5  571.16  5000.7  571.66  5014.0  574.35  5043.4  575.15  5114.3  575.38
  5165.9  576.76  5354.4  578.71  5448.6  579.00  5500.4  578.44  5544.9  578.98
#Mann=3,-1,0
  4101.2   0.045       0  4996.7   0.045       0  5000.7   0.045       0
Bank Sta=4996.7,5000.7
Exp/Cntr=0.3,0.1

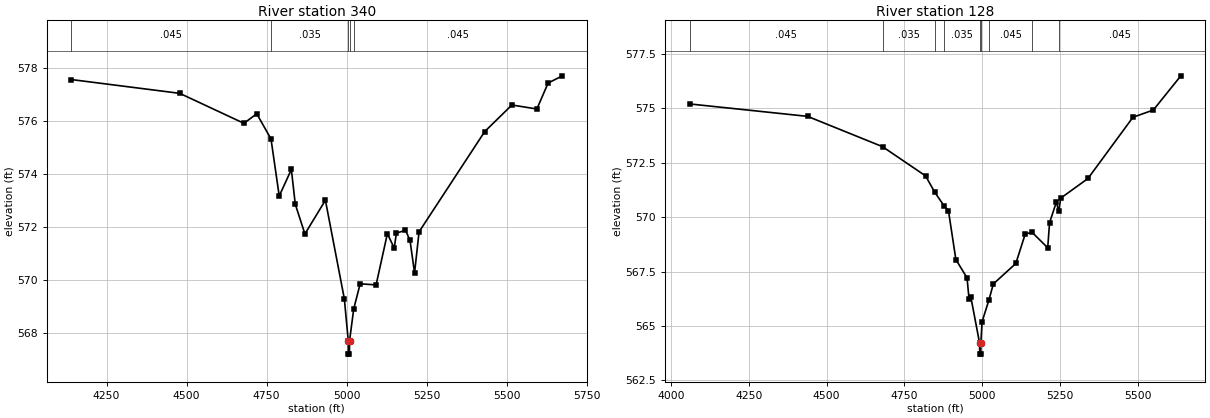
Type RM Length L Ch R = 1,340,212,212,212
BEGIN DESCRIPTION:
A18995
END DESCRIPTION:
XS GIS Cut Line= 3
      2300952.92     13791010.17      2300161.21     13791067.47
      2299629.97     13791583.09
#Sta/Elev= 30
  4139.6  577.57  4478.4  577.05  4678.9  575.92  4719.0  576.28  4763.5  575.33
  4789.2  573.18  4827.1  574.18  4839.3  572.87  4869.4  571.75  4933.4  573.02
  4992.6  569.30  5004.8  567.72  5005.0  567.22  5008.5  567.22  5008.8  567.72
  5021.9  568.93  5042.0  569.87  5091.7  569.83  5126.9  571.76  5148.2  571.22
  5155.2  571.78  5183.5  571.89  5197.6  571.51  5211.8  570.28  5225.9  571.83
  5431.0  575.61  5515.8  576.61  5593.8  576.46  5629.0  577.44  5673.7  577.71
#Mann=5,-1,0
  4139.6   0.045       0  4763.5   0.035       0  5004.8   0.035       0
  5008.8   0.035       0  5021.9   0.045       0
Bank Sta=5004.8,5008.8
Exp/Cntr=0.3,0.1

Type RM Length L Ch R = 1,128,0,0,0
BEGIN DESCRIPTION:
GERONIMO TRIBUTARY 12 1.0
END DESCRIPTION:
XS GIS Cut Line= 3
      2300869.57     13790713.30      2300067.46     13790838.30
      2299645.61     13791478.89
#Sta/Elev= 30
  4059.7  575.19  4438.8  574.62  4679.6  573.23  4817.9  571.89  4847.5  571.14
  4877.6  570.51  4891.5  570.30  4915.4  568.05  4951.3  567.21  4957.6  566.26
  4963.5  566.33  4991.7  564.21  4992.0  563.71  4995.5  563.71  4995.7  564.21
  4999.7  565.20  5021.8  566.20  5035.8  566.93  5108.1  567.87  5138.3  569.22
  5160.2  569.30  5210.6  568.59  5216.5  569.74  5238.7  570.70  5245.4  570.26
  5252.7  570.87  5340.0  571.77  5484.6  574.58  5550.0  574.91  5638.5  576.48
#Mann=9,-1,0
  4059.7   0.045       0  4679.6   0.035       0  4847.5   0.045       0
  4877.6   0.035       0  4991.7   0.035       0  4995.7   0.035       0
  5021.8   0.045       0  5160.2    0.07       0  5245.4   0.045       0
Bank Sta=4991.7,4995.7
Exp/Cntr=0.3,0.1

Chan Stop Cuts=-1