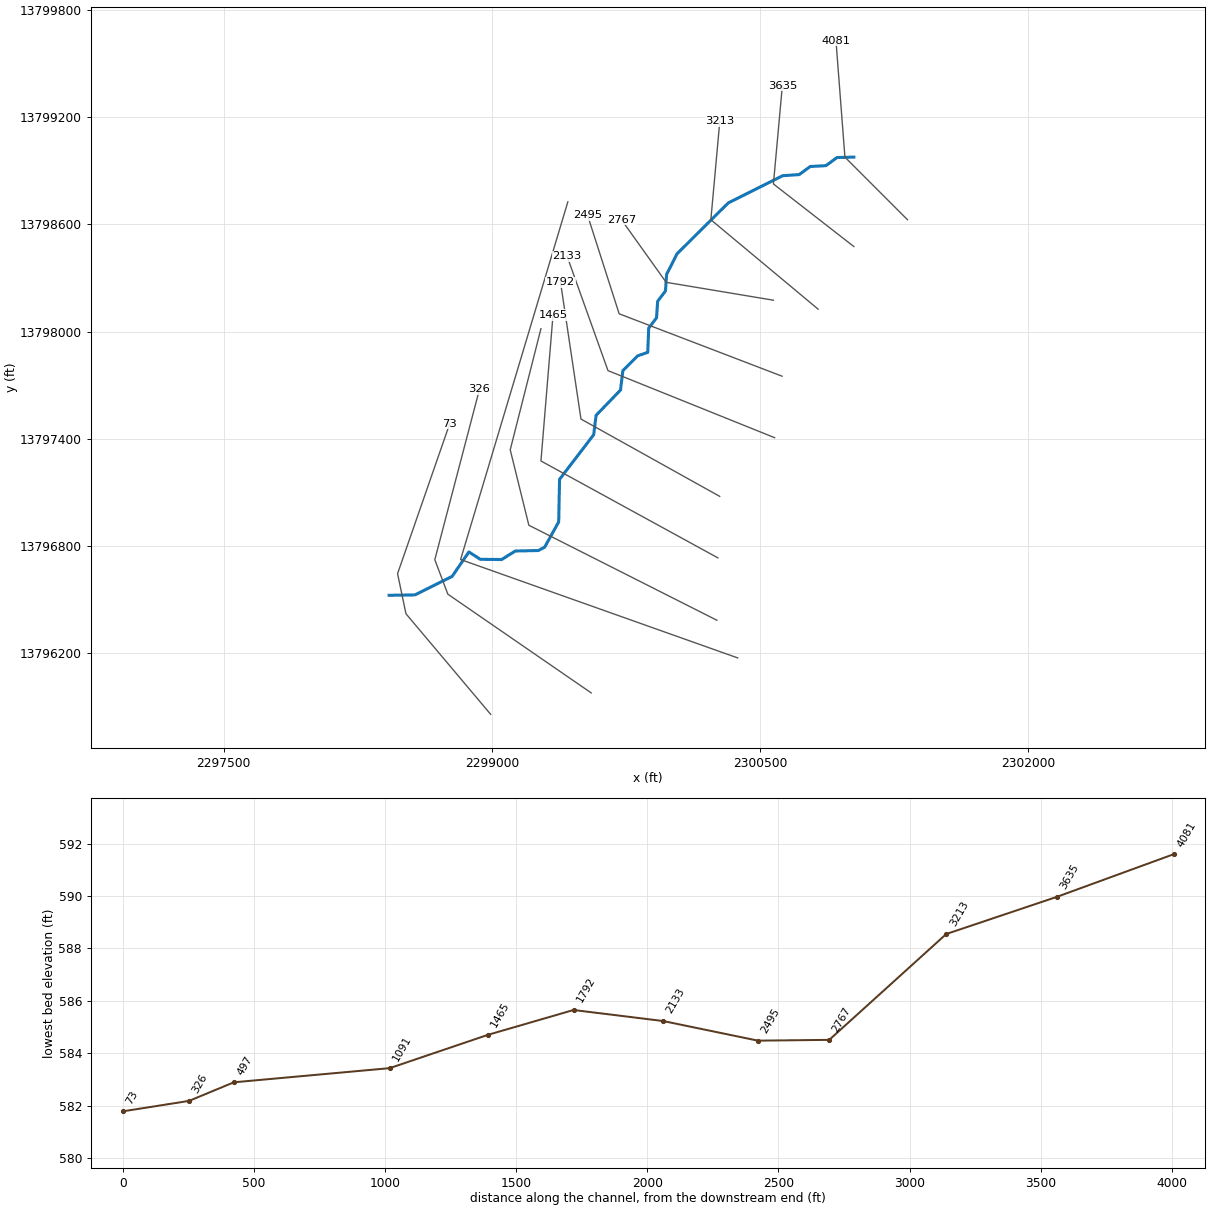
--- GERONIMO TRIBUTARY 13.prj (project) ---

Proj Title=GERONIMO TRIBUTARY 13 Base Level Engineering
Current Plan=p01
Default Exp/Contr=0.3,0.1
English Units
Geom File=g01
Flow File=f01
Plan File=p01
BEGIN DESCRIPTION:
GERONIMO TRIBUTARY 13
END DESCRIPTION:

--- GERONIMO TRIBUTARY 13.p01 (plan) ---

Plan Title=Multiple Run
Short Identifier=Multiple
Geom File=g01
Flow File=f01
Subcritical Flow
K Sum by GR= 0
Std Step Tol= 0.01
Critical Tol= 0.01
Num of Std Step Trials= 20
Max Error Tol= 0.3
Flow Tol Ratio= 0.001
Split Flow NTrial= 30
Split Flow Tol= 0.02
Split Flow Ratio= 0.02
Log Output Level= 0
Friction Slope Method= 1
Unsteady Friction Slope Method= 2
Unsteady Bridges Friction Slope Method= 1
Parabolic Critical Depth
Global Vel Dist=  1 , 1 , 1
Global Log Level= 0
CheckData=True
Encroach Param= -1, 0, 0, 0
BEGIN DESCRIPTION:
Multiple Run
END DESCRIPTION:

--- GERONIMO TRIBUTARY 13.f01 (steady flow) ---

Flow Title=Multiple
Number of Profiles=7
Profile Names=10-year,25-year,50-year,1pct_min,100-year,1pct_plu,500-year
River Rch & RM= GERONIMO TRIBUTA,Reach-1,4081
     811    1335    1819    1201    2396    4780    4115
River Rch & RM= GERONIMO TRIBUTA,Reach-1,1465
     920    1520    2076    1372    2737    5461    4715
Boundary for River Rch & Prof#=GERONIMO TRIBUTA,Reach-1,1
Up Type=0
Dn Type=3
Dn Slope=0.005
Boundary for River Rch & Prof#=GERONIMO TRIBUTA,Reach-1,2
Up Type=0
Dn Type=3
Dn Slope=0.005
Boundary for River Rch & Prof#=GERONIMO TRIBUTA,Reach-1,3
Up Type=0
Dn Type=3
Dn Slope=0.005
Boundary for River Rch & Prof#=GERONIMO TRIBUTA,Reach-1,4
Up Type=0
Dn Type=3
Dn Slope=0.005
Boundary for River Rch & Prof#=GERONIMO TRIBUTA,Reach-1,5
Up Type=0
Dn Type=3
Dn Slope=0.005
Boundary for River Rch & Prof#=GERONIMO TRIBUTA,Reach-1,6
Up Type=0
Dn Type=3
Dn Slope=0.005
Boundary for River Rch & Prof#=GERONIMO TRIBUTA,Reach-1,7
Up Type=0
Dn Type=3
Dn Slope=0.005

--- GERONIMO TRIBUTARY 13.g01 (geometry) ---

Geom Title=Existing Conditions

River Reach=GERONIMO TRIBUTA,Reach-1
Reach XY= 30
      2301025.00     13798975.00      2300930.87     13798972.90
      2300869.03     13798927.33      2300780.97     13798922.65
      2300719.03     13798877.35      2300626.58     13798871.17
      2300322.70     13798719.17      2300035.76     13798434.68
      2299977.33     13798319.03      2299971.15     13798226.60
      2299927.35     13798169.03      2299921.14     13798076.60
      2299877.27     13798019.05      2299871.92     13797883.31
      2299815.60     13797864.10      2299732.86     13797781.19
      2299719.48     13797672.57      2299582.86     13797531.17
      2299569.46     13797422.58      2299378.55     13797173.53
      2299373.80     13796935.50      2299295.55     13796794.44
      2299259.96     13796775.34      2299130.94     13796772.73
      2299054.96     13796725.05      2298935.43     13796726.38
      2298871.33     13796767.31      2298777.55     13796630.73
      2298569.09     13796527.20      2298425.00     13796525.00

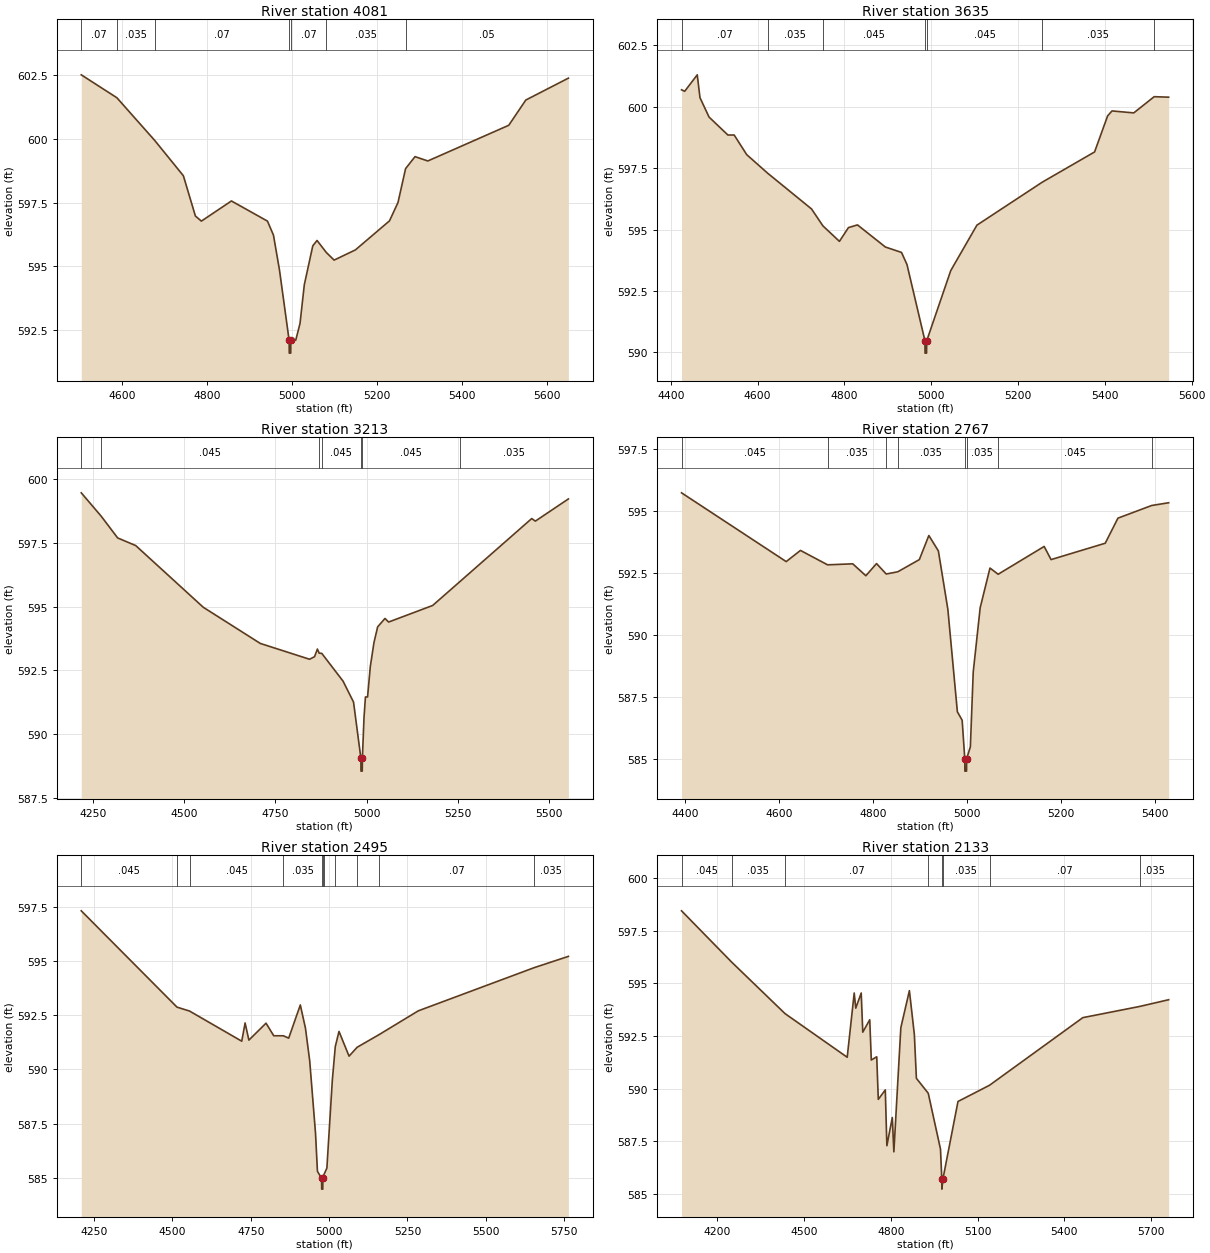
Type RM Length L Ch R = 1,4081,446,446,446
BEGIN DESCRIPTION:
GERONIMO TRIBUTARY 13 5.0
END DESCRIPTION:
XS GIS Cut Line= 3
      2301325.00     13798625.00      2300975.00     13798975.00
      2300925.00     13799625.01
#Sta/Elev= 30
  4504.4  602.52  4588.3  601.62  4677.6  599.94  4744.8  598.56  4773.1  596.98
  4787.2  596.78  4857.9  597.57  4942.8  596.78  4956.9  596.23  4971.1  594.86
  4993.8  592.10  4994.1  591.60  4997.6  591.60  4997.8  592.10  5009.4  592.11
  5019.4  592.76  5029.5  594.28  5049.5  595.81  5059.5  596.02  5081.3  595.55
  5099.7  595.25  5149.8  595.65  5230.1  596.79  5250.1  597.51  5268.0  598.84
  5290.2  599.31  5320.3  599.14  5510.9  600.54  5551.0  601.53  5651.3  602.39
#Mann=7,-1,0
  4504.4    0.07       0  4588.3   0.035       0  4677.6    0.07       0
  4993.8    0.05       0  4997.8    0.07       0  5081.3   0.035       0
  5268.0    0.05       0
Bank Sta=4993.8,4997.8
Exp/Cntr=0.3,0.1

Type RM Length L Ch R = 1,3635,422,422,422
BEGIN DESCRIPTION:
GERONIMO TRIBUTARY 13 4.0
END DESCRIPTION:
XS GIS Cut Line= 3
      2301025.01     13798474.99      2300575.00     13798825.00
      2300625.00     13799375.03
#Sta/Elev= 30
  4424.6  600.69  4431.9  600.63  4460.8  601.30  4467.1  600.37  4488.0  599.58
  4531.4  598.85  4545.9  598.85  4574.8  598.05  4622.7  597.30  4724.1  595.84
  4750.4  595.15  4788.4  594.52  4809.2  595.08  4830.0  595.19  4894.3  594.29
  4931.4  594.07  4944.0  593.58  4985.5  590.47  4985.7  589.97  4989.2  589.97
  4989.5  590.47  5044.9  593.33  5105.2  595.18  5255.8  596.93  5376.3  598.16
  5406.4  599.63  5416.4  599.83  5466.6  599.75  5513.6  600.41  5547.0  600.39
#Mann=7,-1,0
  4424.6    0.07       0  4622.7   0.035       0  4750.4   0.045       0
  4985.5   0.045       0  4989.5   0.045       0  5255.8   0.035       0
  5513.6   0.045       0
Bank Sta=4985.5,4989.5
Exp/Cntr=0.3,0.1

Type RM Length L Ch R = 1,3213,446,446,446
BEGIN DESCRIPTION:
GERONIMO TRIBUTARY 13 3.0
END DESCRIPTION:
XS GIS Cut Line= 3
      2300825.02     13798124.99      2300225.00     13798625.00
      2300275.00     13799174.99
#Sta/Elev= 30
  4218.9  599.47  4273.6  598.55  4318.5  597.70  4368.0  597.40  4552.8  594.98
  4709.0  593.56  4843.7  592.94  4857.4  593.04  4865.2  593.34  4870.0  593.18
  4877.2  593.17  4935.5  592.08  4964.1  591.26  4984.3  589.05  4984.5  588.55
  4988.0  588.55  4988.3  589.05  4992.8  590.66  4996.7  591.46  5002.5  591.46
  5010.0  592.65  5020.0  593.59  5030.1  594.21  5050.2  594.54  5060.2  594.40
  5180.7  595.05  5256.3  596.00  5451.8  598.46  5461.8  598.36  5552.2  599.23
#Mann=7,-1,0
  4218.9   0.035       0  4273.6   0.045       0  4870.0   0.035       0
  4877.2   0.045       0  4984.3   0.045       0  4988.3   0.045       0
  5256.3   0.035       0
Bank Sta=4984.3,4988.3
Exp/Cntr=0.3,0.1

Type RM Length L Ch R = 1,2767,272,272,272
BEGIN DESCRIPTION:
GERONIMO TRIBUTARY 13 2.0
END DESCRIPTION:
XS GIS Cut Line= 3
      2300575.02     13798175.00      2299975.00     13798275.00
      2299725.01     13798624.99
#Sta/Elev= 30
  4391.7  595.72  4614.8  592.95  4645.2  593.40  4703.0  592.82  4756.7  592.86
  4784.6  592.38  4807.4  592.87  4828.0  592.45  4852.7  592.54  4898.6  593.03
  4918.9  594.00  4939.2  593.38  4959.4  591.03  4979.7  586.90  4989.9  586.56
  4995.5  585.01  4995.7  584.51  4999.2  584.51  4999.5  585.01  5007.4  585.49
  5013.5  588.50  5028.3  591.09  5049.2  592.69  5066.6  592.44  5164.7  593.56
  5179.4  593.03  5294.9  593.69  5322.0  594.70  5393.9  595.21  5430.1  595.32
#Mann=8,-1,0
  4391.7   0.045       0  4703.0   0.035       0  4828.0   0.045       0
  4852.7   0.035       0  4995.5   0.035       0  4999.5   0.035       0
  5066.6   0.045       0  5393.9    0.07       0
Bank Sta=4995.5,4999.5
Exp/Cntr=0.3,0.1

Type RM Length L Ch R = 1,2495,362,362,362
BEGIN DESCRIPTION:
A19010
END DESCRIPTION:
XS GIS Cut Line= 3
      2300623.39     13797750.11      2299711.98     13798099.05
      2299535.08     13798650.55
#Sta/Elev= 30
  4208.9  597.31  4514.5  592.87  4554.5  592.69  4721.2  591.30  4731.9  592.14
  4744.0  591.35  4798.7  592.13  4823.4  591.55  4854.1  591.55  4871.1  591.44
  4908.2  592.97  4924.6  591.90  4938.2  590.39  4956.7  587.06  4962.9  585.30
  4976.1  584.98  4976.4  584.48  4979.9  584.48  4980.1  584.98  4983.0  585.13
  4993.0  585.45  5010.3  589.49  5019.8  591.05  5031.7  591.75  5063.8  590.61
  5089.6  591.02  5159.3  591.60  5284.9  592.70  5654.8  594.69  5764.0  595.21
#Mann=11,-1,0
  4208.9   0.045       0  4514.5   0.035       0  4554.5   0.045       0
  4854.1   0.035       0  4976.1    0.05       0  4980.1   0.035       0
  4983.0    0.07       0  5019.8   0.035       0  5089.6   0.045       0
  5159.3    0.07       0  5654.8   0.035       0
Bank Sta=4976.1,4980.1
Exp/Cntr=0.3,0.1

Type RM Length L Ch R = 1,2133,341,341,341
BEGIN DESCRIPTION:
A19009
END DESCRIPTION:
XS GIS Cut Line= 3
      2300581.74     13797406.35      2299649.48     13797781.34
      2299420.66     13798420.99
#Sta/Elev= 30
  4076.5  598.44  4249.5  596.01  4434.4  593.56  4649.3  591.49  4673.5  594.54
  4678.9  593.82  4697.7  594.54  4703.1  592.68  4727.2  593.27  4732.6  591.36
  4751.4  591.51  4756.8  589.49  4781.0  589.94  4786.4  587.29  4805.2  588.63
  4810.6  587.00  4834.7  592.89  4864.3  594.65  4881.4  592.58  4888.5  590.49
  4929.5  589.78  4971.8  587.13  4976.3  585.73  4976.6  585.23  4980.5  585.73
  5032.3  589.39  5141.3  590.16  5464.0  593.37  5660.1  593.90  5760.7  594.22
#Mann=8,-1,0
  4076.5   0.045       0  4249.5   0.035       0  4434.4    0.07       0
  4929.5   0.035       0  4976.3   0.035       0  4980.5   0.035       0
  5141.3    0.07       0  5660.1   0.035       0
Bank Sta=4976.3,4980.5
Exp/Cntr=0.3,0.1

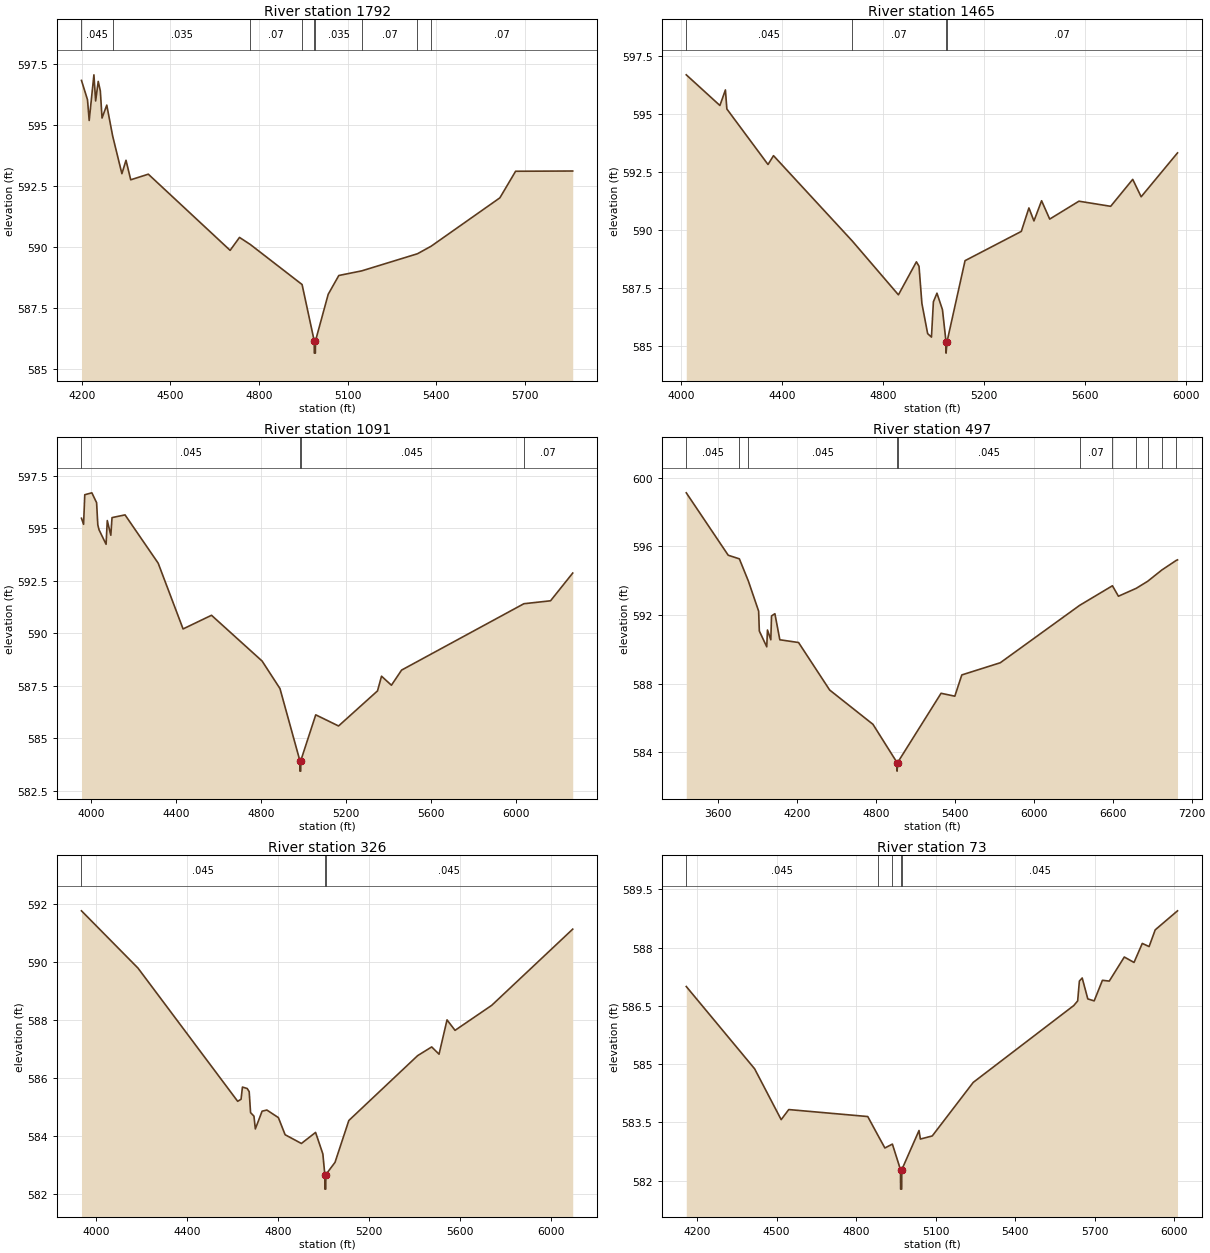
Type RM Length L Ch R = 1,1792,327,327,327
BEGIN DESCRIPTION:
A19008
END DESCRIPTION:
XS GIS Cut Line= 3
      2300274.49     13797078.21      2299498.44     13797510.51
      2299383.85     13798276.15
#Sta/Elev= 30
  4199.4  596.82  4219.8  596.03  4225.5  595.18  4241.5  597.05  4247.3  595.98
  4256.1  596.78  4263.2  596.39  4269.0  595.28  4285.0  595.81  4305.0  594.54
  4336.2  593.00  4350.1  593.55  4366.1  592.75  4425.6  592.98  4702.5  589.86
  4734.2  590.39  4770.8  590.10  4946.0  588.46  4987.1  586.15  4987.4  585.65
  4991.0  585.65  4991.3  586.15  5034.4  588.06  5070.3  588.83  5148.0  589.02
  5336.4  589.72  5382.8  590.03  5615.3  592.01  5668.6  593.10  5861.9  593.11
#Mann=9,-1,0
  4199.4   0.045       0  4305.0   0.035       0  4770.8    0.07       0
  4946.0   0.035       0  4987.1   0.035       0  4991.3   0.035       0
  5148.0    0.07       0  5336.4   0.035       0  5382.8    0.07       0
Bank Sta=4987.1,4991.3
Exp/Cntr=0.3,0.1

Type RM Length L Ch R = 1,1465,374,374,374
BEGIN DESCRIPTION:
A19007
END DESCRIPTION:
XS GIS Cut Line= 3
      2300264.06     13796734.47      2299274.48     13797276.13
      2299342.03     13798091.91
#Sta/Elev= 30
  4020.0  596.68  4153.3  595.36  4175.1  596.03  4180.8  595.21  4343.9  592.82
  4365.7  593.20  4678.4  589.52  4860.7  587.21  4931.9  588.63  4942.3  588.44
  4953.7  586.84  4976.5  585.54  4991.6  585.39  4999.3  586.91  5013.4  587.28
  5035.2  586.57  5049.2  585.20  5049.5  584.70  5053.5  585.20  5124.7  588.68
  5347.7  589.94  5377.8  590.95  5397.8  590.39  5428.0  591.26  5460.2  590.47
  5576.0  591.24  5701.8  591.02  5789.2  592.18  5822.6  591.43  5966.7  593.32
#Mann=4,-1,0
  4020.0   0.045       0  4678.4    0.07       0  5049.2    0.05       0
  5053.5    0.07       0
Bank Sta=5049.2,5053.5
Exp/Cntr=0.3,0.1

Type RM Length L Ch R = 1,1091,594,594,594
BEGIN DESCRIPTION:
A19006
END DESCRIPTION:
XS GIS Cut Line= 4
      2300258.83     13796385.52      2299206.77     13796916.76
      2299102.60     13797338.63      2299274.48     13798015.73
#Sta/Elev= 30
  3954.7  595.47  3964.6  595.18  3970.2  596.59  4003.6  596.68  4025.9  596.21
  4031.5  595.16  4037.4  594.92  4070.5  594.23  4076.1  595.36  4092.8  594.66
  4098.4  595.50  4159.7  595.63  4315.7  593.33  4432.8  590.20  4566.6  590.85
  4804.8  588.67  4888.8  587.36  4982.4  583.93  4982.7  583.43  4986.5  583.43
  4986.8  583.93  5057.1  586.11  5164.5  585.58  5347.8  587.25  5366.7  587.95
  5413.3  587.52  5461.1  588.24  6036.6  591.40  6162.1  591.54  6266.4  592.86
#Mann=4,-1,0
  3954.7   0.045       0  4982.4   0.045       0  4986.8   0.045       0
  6036.6    0.07       0
Bank Sta=4982.4,4986.8
Exp/Cntr=0.3,0.1

Type RM Length L Ch R = 1,497,171,171,171
BEGIN DESCRIPTION:
GERONIMO TRIBUTARY 13 1.0
END DESCRIPTION:
XS GIS Cut Line= 3
      2300374.97     13796175.01      2298825.00     13796725.00
      2299424.99     13798724.98
#Sta/Elev= 30
  3359.5  599.12  3678.3  595.48  3762.9  595.27  3831.5  593.97  3909.3  592.22
  3914.6  591.06  3971.0  590.14  3976.4  591.12  4001.9  590.55  4007.2  591.94
  4032.8  592.07  4070.4  590.55  4212.7  590.39  4449.0  587.62  4778.0  585.62
  4960.9  583.39  4961.2  582.89  4965.4  583.39  5295.6  587.43  5400.0  587.26
  5453.1  588.50  5745.4  589.21  6349.0  592.56  6597.6  593.70  6643.3  593.09
  6778.2  593.55  6865.3  593.96  6973.1  594.62  7082.7  595.18  7092.2  595.21
#Mann=11,-1,0
  3359.5   0.045       0  3762.9   0.035       0  3831.5   0.045       0
  4960.9   0.045       0  4965.4   0.045       0  6349.0    0.07       0
  6597.6   0.035       0  6778.2    0.07       0  6865.3   0.035       0
  6973.1    0.07       0  7082.7   0.035       0
Bank Sta=4960.9,4965.4
Exp/Cntr=0.3,0.1

Type RM Length L Ch R = 1,326,253,253,253
BEGIN DESCRIPTION:
A19005
END DESCRIPTION:
XS GIS Cut Line= 4
      2299555.75     13795979.24      2298753.65     13796531.34
      2298680.73     13796724.05      2298930.36     13797675.77
#Sta/Elev= 30
  3933.9  591.75  4182.9  589.78  4621.9  585.20  4636.8  585.27  4642.9  585.69
  4663.8  585.64  4672.6  585.53  4678.7  584.81  4693.6  584.69  4699.7  584.25
  4729.4  584.86  4750.4  584.90  4801.1  584.64  4830.9  584.05  4902.6  583.75
  4965.0  584.13  4997.1  583.39  5005.7  582.68  5006.0  582.18  5009.9  582.18
  5010.2  582.68  5050.6  583.10  5111.5  584.54  5414.5  586.77  5476.5  587.07
  5508.8  586.82  5544.0  588.00  5579.3  587.64  5740.8  588.50  6097.6  591.12
#Mann=3,-1,0
  3933.9   0.045       0  5005.7   0.045       0  5010.2   0.045       0
Bank Sta=5005.7,5010.2
Exp/Cntr=0.3,0.1

Type RM Length L Ch R = 1,73,0,0,0
BEGIN DESCRIPTION:
A19004
END DESCRIPTION:
XS GIS Cut Line= 4
      2298993.20     13795859.50      2298519.27     13796421.97
      2298472.40     13796645.93      2298764.05     13797484.42
#Sta/Elev= 30
  4159.5  587.00  4417.2  584.88  4517.3  583.57  4545.9  583.83  4843.7  583.65
  4881.8  583.17  4908.3  582.84  4936.6  582.94  4967.2  582.28  4967.6  581.78
  4971.7  581.78  4972.0  582.28  5037.0  583.29  5042.1  583.07  5086.9  583.15
  5241.4  584.53  5620.5  586.51  5635.2  586.63  5641.6  587.14  5652.2  587.22
  5673.4  586.68  5697.4  586.63  5728.5  587.16  5754.3  587.14  5811.0  587.76
  5847.6  587.62  5878.7  588.11  5904.5  588.03  5927.5  588.46  6011.6  588.95
#Mann=5,-1,0
  4159.5   0.045       0  4881.8   0.035       0  4936.6   0.045       0
  4967.2   0.045       0  4972.0   0.045       0
Bank Sta=4967.2,4972
Exp/Cntr=0.3,0.1

Chan Stop Cuts=-1