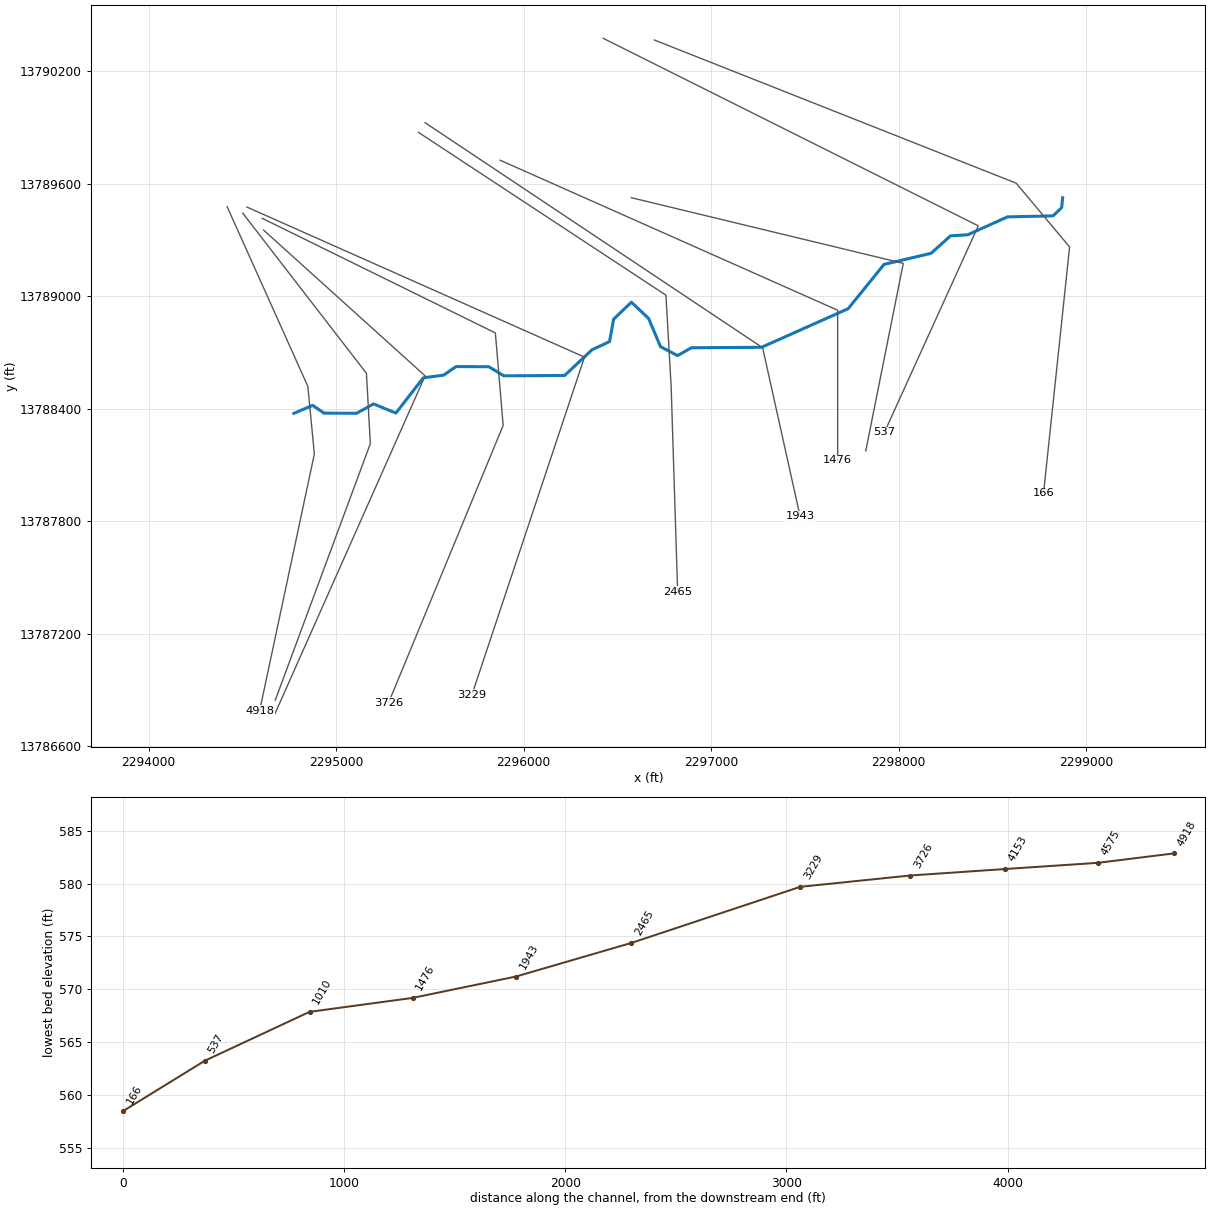
--- GERONIMO TRIBUTARY 16.prj (project) ---

Proj Title=GERONIMO TRIBUTARY 16 Base Level Engineering
Current Plan=p01
Default Exp/Contr=0.3,0.1
English Units
Geom File=g01
Flow File=f01
Plan File=p01
Y Axis Title=Elevation
X Axis Title(PF)=Main Channel Distance
X Axis Title(XS)=Station
BEGIN DESCRIPTION:
GERONIMO TRIBUTARY 16
END DESCRIPTION:
DSS Export Rating Curves= 0
DSS Export Rating Curve Sorted= 0
DSS Export Volume Flow Curves= 0
DXF OffsetX= 0
DXF OffsetY= 0
DXF ScaleX= 1
DXF ScaleY= 10

--- GERONIMO TRIBUTARY 16.p01 (plan) ---

Plan Title=Multiple Run
Short Identifier=Multiple
Geom File=g01
Flow File=f01
Subcritical Flow
K Sum by GR= 0
Std Step Tol= 0.01
Critical Tol= 0.01
Num of Std Step Trials= 20
Max Error Tol= 0.3
Flow Tol Ratio= 0.001
Split Flow NTrial= 30
Split Flow Tol= 0.02
Split Flow Ratio= 0.02
Log Output Level= 0
Friction Slope Method= 1
Unsteady Friction Slope Method= 2
Unsteady Bridges Friction Slope Method= 1
Parabolic Critical Depth
Global Vel Dist=  1 , 1 , 1
Global Log Level= 0
CheckData=True
Encroach Param= -1, 0, 0, 0
BEGIN DESCRIPTION:
Multiple Run
END DESCRIPTION:

--- GERONIMO TRIBUTARY 16.f01 (steady flow) ---

Flow Title=Multiple
Number of Profiles=7
Profile Names=10-year,25-year,50-year,1pct_min,100-year,1pct_plu,500-year
River Rch & RM= GERONIMO TRIBUTA,Reach-1,4918
     442     684     892     563    1123    2240    1761
River Rch & RM= GERONIMO TRIBUTA,Reach-1,4153
     638    1010    1339     858    1711    3415    2770
Boundary for River Rch & Prof#=GERONIMO TRIBUTA,Reach-1,1
Up Type=0
Dn Type=3
Dn Slope=0.005
Boundary for River Rch & Prof#=GERONIMO TRIBUTA,Reach-1,2
Up Type=0
Dn Type=3
Dn Slope=0.005
Boundary for River Rch & Prof#=GERONIMO TRIBUTA,Reach-1,3
Up Type=0
Dn Type=3
Dn Slope=0.005
Boundary for River Rch & Prof#=GERONIMO TRIBUTA,Reach-1,4
Up Type=0
Dn Type=3
Dn Slope=0.005
Boundary for River Rch & Prof#=GERONIMO TRIBUTA,Reach-1,5
Up Type=0
Dn Type=3
Dn Slope=0.005
Boundary for River Rch & Prof#=GERONIMO TRIBUTA,Reach-1,6
Up Type=0
Dn Type=3
Dn Slope=0.005
Boundary for River Rch & Prof#=GERONIMO TRIBUTA,Reach-1,7
Up Type=0
Dn Type=3
Dn Slope=0.005

--- GERONIMO TRIBUTARY 16.g01 (geometry) ---

Geom Title=Existing Conditions

River Reach=GERONIMO TRIBUTA,Reach-1
Reach XY= 30
      2294775.00     13788375.00      2294874.96     13788417.69
      2294935.43     13788376.37      2295109.79     13788375.54
      2295200.00     13788425.39      2295319.15     13788376.55
      2295465.19     13788564.49      2295573.40     13788578.86
      2295640.22     13788624.48      2295814.49     13788623.78
      2295895.03     13788575.07      2296219.15     13788577.06
      2296365.34     13788714.21      2296458.70     13788757.87
      2296480.53     13788877.45      2296575.00     13788967.94
      2296666.86     13788881.09      2296730.59     13788730.55
      2296821.65     13788683.03      2296894.98     13788724.82
      2297269.06     13788727.26      2297731.07     13788933.13
      2297922.56     13789169.48      2298173.50     13789228.62
      2298276.50     13789321.38      2298369.02     13789327.36
      2298580.94     13789422.74      2298823.74     13789428.37
      2298869.87     13789472.05      2298875.00     13789525.00

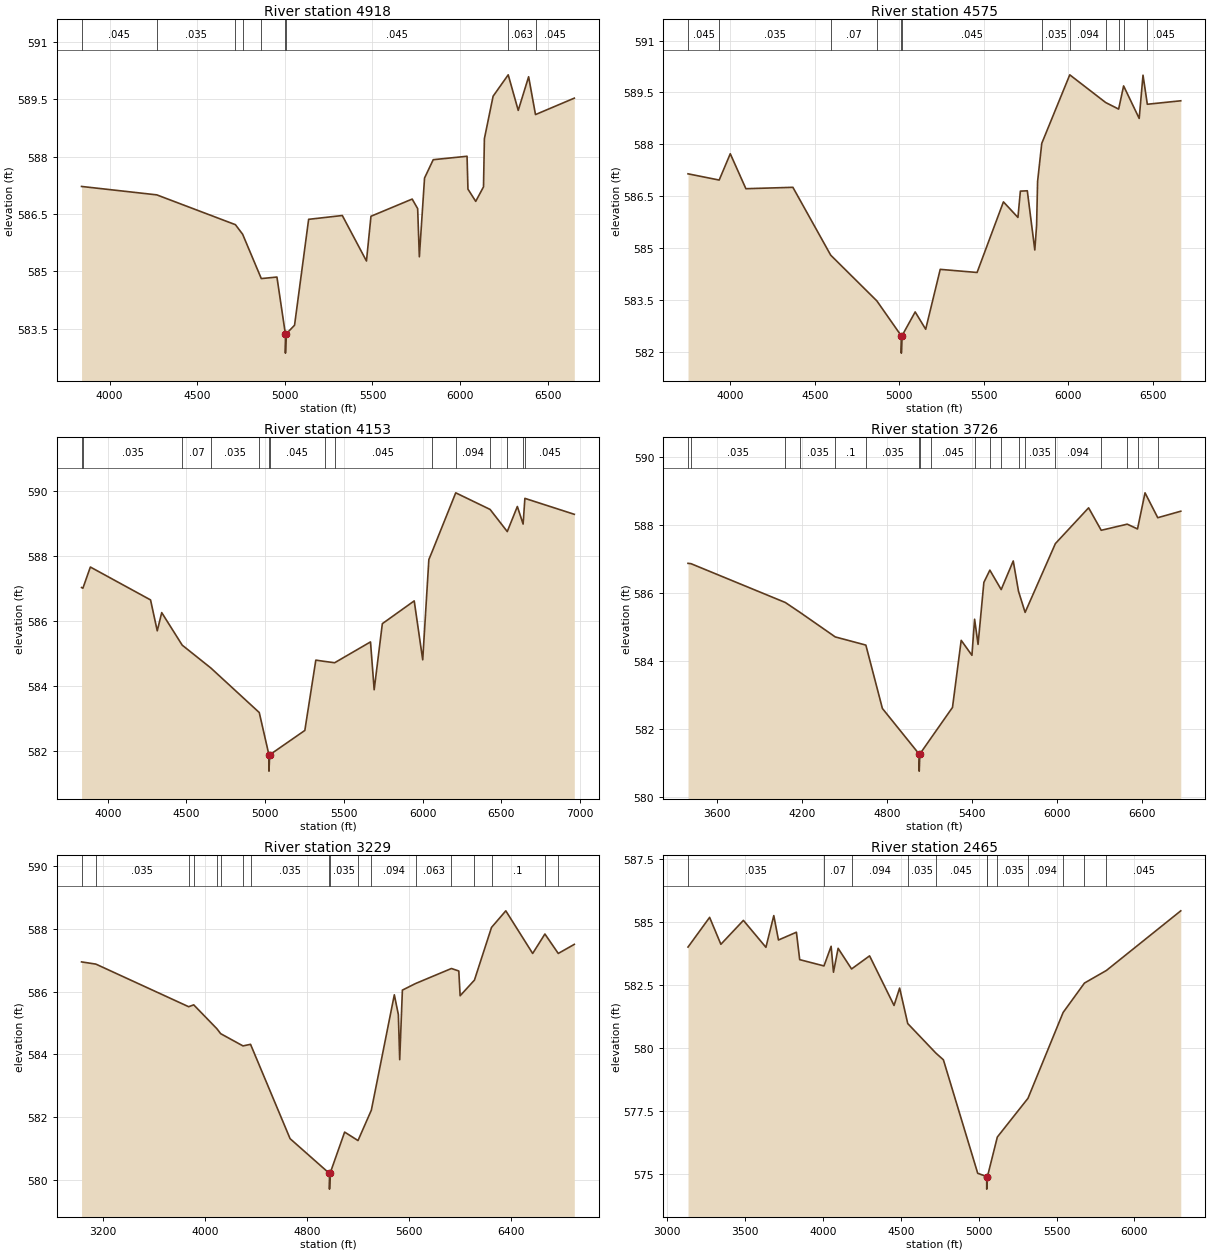
Type RM Length L Ch R = 1,4918,343,343,343
BEGIN DESCRIPTION:
A19012
END DESCRIPTION:
XS GIS Cut Line= 4
      2294419.00     13789477.55      2294849.57     13788519.18
      2294884.30     13788158.07      2294592.63     13786790.04
#Sta/Elev= 30
  3839.8  587.22  4269.1  587.00  4718.0  586.22  4759.1  585.97  4865.6  584.81
  4954.9  584.85  5003.1  583.36  5003.4  582.86  5007.2  583.36  5055.4  583.59
  5135.8  586.36  5327.9  586.46  5465.8  585.27  5491.5  586.44  5726.7  586.89
  5758.0  586.64  5767.6  585.38  5797.3  587.44  5846.8  587.92  6039.9  588.01
  6045.0  587.15  6089.4  586.83  6133.8  587.21  6138.9  588.47  6188.5  589.58
  6274.8  590.14  6332.0  589.21  6391.3  590.09  6430.5  589.10  6652.0  589.53
#Mann=9,-1,0
  3839.8   0.045       0  4269.1   0.035       0  4718.0    0.07       0
  4759.1   0.035       0  4865.6   0.045       0  5003.1   0.045       0
  5007.2   0.045       0  6274.8   0.063       0  6430.5   0.045       0
Bank Sta=5003.1,5007.2
Exp/Cntr=0.3,0.1

Type RM Length L Ch R = 1,4575,422,422,422
BEGIN DESCRIPTION:
A19013
END DESCRIPTION:
XS GIS Cut Line= 4
      2294502.35     13789442.80      2295162.07     13788588.63
      2295182.91     13788213.63      2294675.97     13786845.59
#Sta/Elev= 30
  3750.6  587.15  3934.9  586.97  4000.5  587.73  4092.8  586.72  4370.8  586.76
  4594.4  584.80  4867.1  583.48  5011.7  582.47  5012.0  581.97  5015.8  582.47
  5093.9  583.16  5156.0  582.66  5242.0  584.39  5459.9  584.30  5615.7  586.34
  5701.5  585.89  5715.9  586.65  5756.9  586.66  5801.2  584.95  5811.9  585.66
  5817.7  586.93  5842.4  588.03  6008.0  590.01  6220.2  589.21  6297.0  589.02
  6326.4  589.69  6418.5  588.75  6441.1  590.00  6466.6  589.16  6664.4  589.26
#Mann=12,-1,0
  3750.6   0.045       0  3934.9   0.035       0  4594.4    0.07       0
  4867.1   0.045       0  5011.7   0.045       0  5015.8   0.045       0
  5842.4   0.035       0  6008.0   0.094       0  6220.2   0.063       0
  6297.0   0.045       0  6326.4   0.063       0  6466.6   0.045       0
Bank Sta=5011.7,5015.8
Exp/Cntr=0.3,0.1

Type RM Length L Ch R = 1,4153,427,427,427
BEGIN DESCRIPTION:
GERONIMO TRIBUTARY 16 7.0
END DESCRIPTION:
XS GIS Cut Line= 3
      2294613.43     13789352.55      2295475.00     13788575.00
      2294675.01     13786775.02
#Sta/Elev= 30
  3833.4  587.02  3841.9  587.00  3889.4  587.65  4271.7  586.64  4314.3  585.69
  4342.7  586.25  4472.9  585.25  4654.4  584.55  4962.3  583.18  5023.8  581.88
  5024.1  581.38  5028.4  581.88  5251.8  582.63  5321.6  584.79  5378.1  584.75
  5441.3  584.71  5669.0  585.35  5692.3  583.88  5744.2  585.91  5946.7  586.61
  6000.7  584.80  6039.7  587.88  6057.7  588.09  6210.4  589.93  6428.7  589.42
  6537.8  588.74  6601.9  589.51  6638.5  588.97  6649.7  589.76  6963.7  589.27
#Mann=15,-1,0
  3833.4   0.045       0  3841.9   0.035       0  4472.9    0.07       0
  4654.4   0.035       0  4962.3   0.045       0  5023.8   0.045       0
  5028.4   0.045       0  5378.1   0.035       0  5441.3   0.045       0
  6057.7   0.035       0  6210.4   0.094       0  6428.7   0.063       0
  6537.8   0.094       0  6638.5   0.063       0  6649.7   0.045       0
Bank Sta=5023.8,5028.4
Exp/Cntr=0.3,0.1

Type RM Length L Ch R = 1,3726,497,497,497
BEGIN DESCRIPTION:
A19014
END DESCRIPTION:
XS GIS Cut Line= 4
      2294606.54     13789415.01      2295849.57     13788803.91
      2295891.24     13788310.85      2295280.12     13786831.66
#Sta/Elev= 30
  3393.9  586.87  3414.9  586.86  4081.4  585.72  4185.0  585.43  4433.8  584.71
  4650.0  584.47  4766.8  582.61  5026.5  581.27  5026.8  580.77  5031.1  581.27
  5110.0  581.74  5261.9  582.64  5323.4  584.61  5399.2  584.17  5418.0  585.23
  5442.5  584.49  5483.5  586.31  5525.8  586.67  5605.9  586.10  5691.0  586.94
  5728.2  586.05  5774.9  585.43  5988.7  587.45  6223.4  588.50  6312.4  587.84
  6496.1  588.02  6568.7  587.88  6621.8  588.94  6711.7  588.21  6874.3  588.40
#Mann=19,-1,0
  3393.9   0.045       0  3414.9   0.035       0  4081.4    0.07       0
  4185.0   0.035       0  4433.8     0.1       0  4650.0   0.035       0
  5026.5   0.035       0  5031.1   0.035       0  5110.0   0.045       0
  5418.0   0.035       0  5525.8   0.063       0  5605.9   0.035       0
  5728.2   0.094       0  5774.9   0.035       0  5988.7   0.094       0
  6312.4   0.035       0  6496.1   0.063       0  6568.7   0.035       0
  6711.7   0.045       0
Bank Sta=5026.5,5031.1
Exp/Cntr=0.3,0.1

Type RM Length L Ch R = 1,3229,764,764,764
BEGIN DESCRIPTION:
GERONIMO TRIBUTARY 16 6.0
END DESCRIPTION:
XS GIS Cut Line= 3
      2294525.04     13789474.98      2296325.00     13788675.00
      2295725.00     13786874.99
#Sta/Elev= 30
  3030.5  586.95  3142.8  586.88  3871.3  585.52  3910.7  585.58  4092.1  584.82
  4122.4  584.66  4297.4  584.27  4356.7  584.32  4667.1  581.31  4976.0  580.20
  4976.3  579.70  4980.7  580.20  5095.1  581.52  5200.1  581.25  5304.8  582.22
  5485.1  585.90  5516.7  585.27  5527.3  583.83  5548.4  586.05  5651.5  586.26
  5933.5  586.74  5991.1  586.66  6001.6  585.87  6113.9  586.37  6247.8  588.05
  6360.0  588.58  6570.8  587.22  6666.9  587.84  6771.7  587.22  6897.6  587.51
#Mann=18,-1,0
  3030.5   0.045       0  3142.8   0.035       0  3871.3    0.07       0
  3910.7   0.035       0  4092.1    0.07       0  4122.4   0.035       0
  4297.4     0.1       0  4356.7   0.035       0  4976.0   0.035       0
  4980.7   0.035       0  5200.1   0.045       0  5304.8   0.094       0
  5651.5   0.063       0  5933.5   0.094       0  6113.9   0.035       0
  6247.8     0.1       0  6666.9   0.063       0  6771.7   0.045       0
Bank Sta=4976,4980.7
Exp/Cntr=0.3,0.1

Type RM Length L Ch R = 1,2465,522,522,522
BEGIN DESCRIPTION:
A19015
END DESCRIPTION:
XS GIS Cut Line= 4
      2295439.82     13789873.37      2296759.30     13789005.29
      2296787.07     13788519.18      2296821.80     13787421.96
#Sta/Elev= 30
  3133.9  584.01  3272.6  585.19  3344.9  584.12  3489.5  585.07  3634.1  584.00
  3684.7  585.26  3714.7  584.29  3829.9  584.60  3851.0  583.51  4007.0  583.26
  4052.8  584.04  4067.9  583.01  4097.7  583.96  4184.1  583.14  4299.8  583.66
  4456.8  581.69  4492.7  582.38  4544.8  580.97  4726.4  579.79  4773.7  579.53
  4994.1  575.02  5051.7  574.89  5052.1  574.39  5056.6  574.89  5120.1  576.46
  5316.9  578.00  5542.5  581.41  5679.6  582.58  5820.5  583.08  6298.0  585.45
#Mann=12,-1,0
  3133.9   0.035       0  4007.0    0.07       0  4184.1   0.094       0
  4544.8   0.035       0  4726.4   0.045       0  5051.7   0.045       0
  5056.6   0.045       0  5120.1   0.035       0  5316.9   0.094       0
  5542.5    0.12       0  5679.6   0.035       0  5820.5   0.045       0
Bank Sta=5051.7,5056.6
Exp/Cntr=0.3,0.1

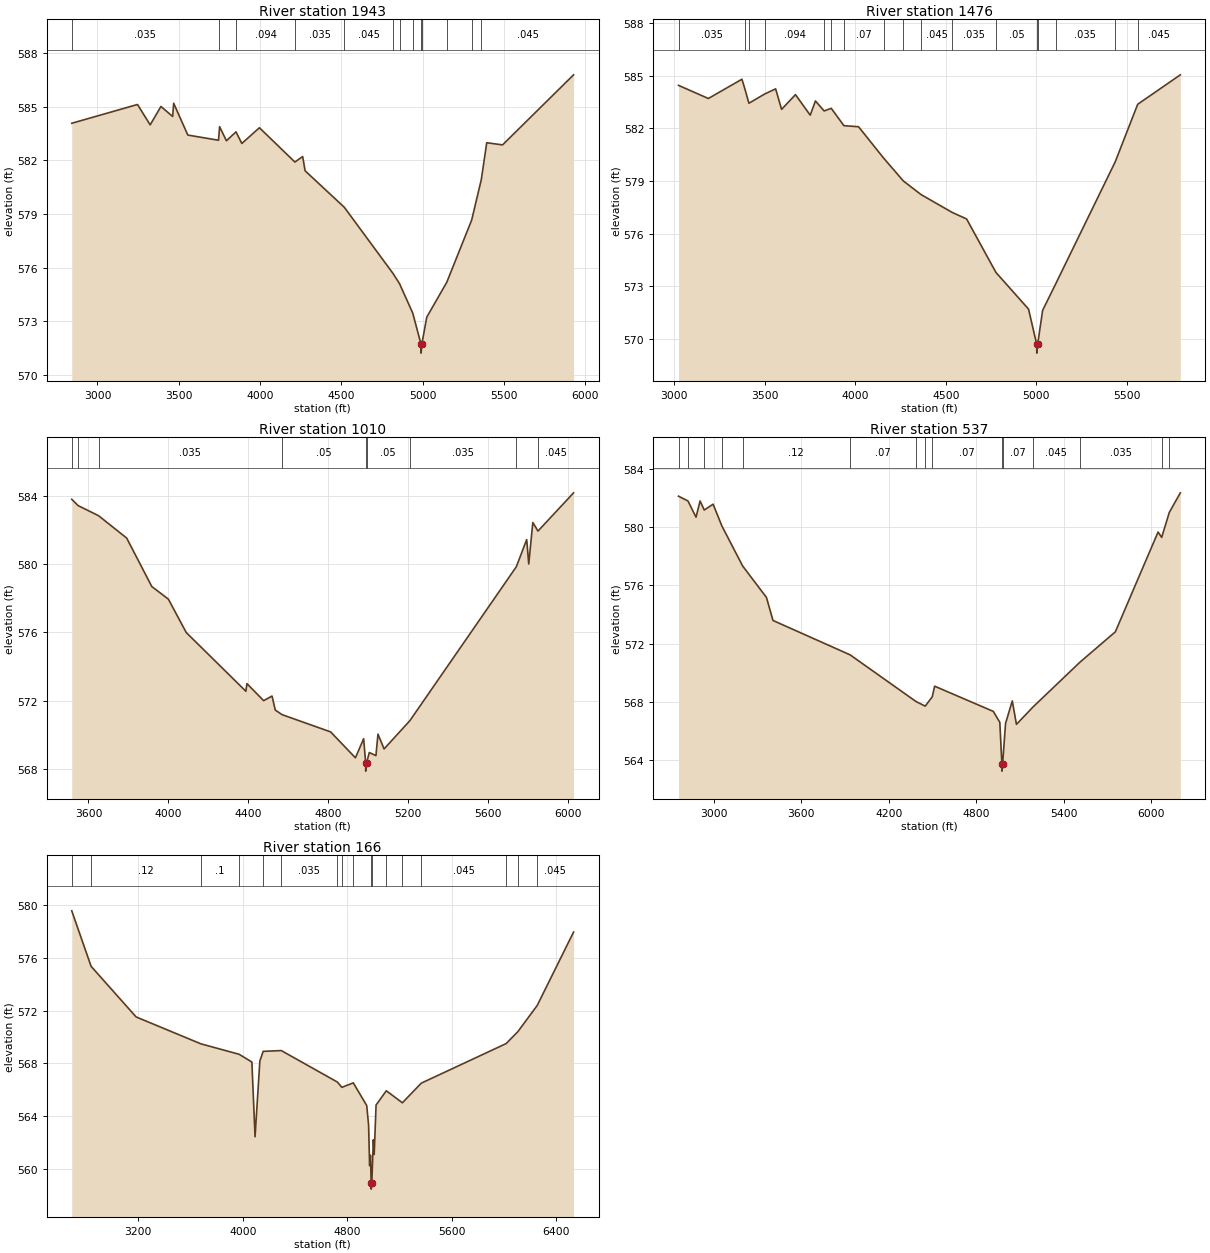
Type RM Length L Ch R = 1,1943,467,467,467
BEGIN DESCRIPTION:
GERONIMO TRIBUTARY 16 4.0
END DESCRIPTION:
XS GIS Cut Line= 3
      2295475.01     13789925.00      2297275.00     13788725.00
      2297475.01     13787824.98
#Sta/Elev= 30
  2841.8  584.07  3245.9  585.12  3324.0  583.98  3390.1  585.01  3462.2  584.45
  3468.3  585.19  3555.4  583.41  3744.3  583.12  3750.7  583.88  3792.8  583.09
  3851.6  583.59  3887.4  582.94  3995.6  583.82  4213.8  581.90  4261.5  582.21
  4276.5  581.41  4517.5  579.37  4817.6  575.66  4857.4  575.09  4938.3  573.45
  4989.1  571.71  4989.5  571.21  4994.1  571.71  5024.3  573.22  5147.3  575.17
  5300.4  578.65  5359.8  580.92  5393.1  582.98  5490.4  582.86  5927.1  586.78
#Mann=13,-1,0
  2841.8   0.035       0  3744.3    0.07       0  3851.6   0.094       0
  4213.8   0.035       0  4517.5   0.045       0  4817.6   0.035       0
  4857.4   0.045       0  4938.3    0.05       0  4989.1    0.05       0
  4994.1    0.05       0  5147.3   0.045       0  5300.4    0.07       0
  5359.8   0.045       0
Bank Sta=4989.1,4994.1
Exp/Cntr=0.3,0.1

Type RM Length L Ch R = 1,1476,466,466,466
BEGIN DESCRIPTION:
GERONIMO TRIBUTARY 16 3.0
END DESCRIPTION:
XS GIS Cut Line= 3
      2295875.01     13789725.00      2297675.00     13788925.00
      2297675.00     13788124.96
#Sta/Elev= 30
  3025.2  584.46  3190.0  583.71  3375.4  584.81  3392.3  584.23  3413.9  583.44
  3501.5  583.97  3561.4  584.26  3594.2  583.09  3670.8  583.93  3752.2  582.76
  3781.0  583.57  3829.1  583.00  3868.4  583.15  3938.3  582.16  4019.0  582.10
  4156.8  580.32  4266.0  579.01  4364.1  578.23  4534.6  577.22  4615.4  576.84
  4777.4  573.79  4957.3  571.70  5002.4  569.69  5002.8  569.19  5007.5  569.69
  5035.0  571.63  5106.7  573.13  5435.3  580.09  5559.7  583.38  5795.0  585.06
#Mann=17,-1,0
  3025.2   0.035       0  3392.3   0.094       0  3413.9   0.035       0
  3501.5   0.094       0  3829.1   0.063       0  3868.4   0.035       0
  3938.3    0.07       0  4156.8   0.045       0  4266.0   0.035       0
  4364.1   0.045       0  4534.6   0.035       0  4777.4    0.05       0
  5002.4    0.05       0  5007.5    0.05       0  5106.7   0.035       0
  5435.3    0.07       0  5559.7   0.045       0
Bank Sta=5002.4,5007.5
Exp/Cntr=0.3,0.1

Type RM Length L Ch R = 1,1010,473,473,473
BEGIN DESCRIPTION:
GERONIMO TRIBUTARY 16 2.0
END DESCRIPTION:
XS GIS Cut Line= 3
      2296574.97     13789525.01      2298025.00     13789175.00
      2297825.00     13788174.98
#Sta/Elev= 30
  3516.5  583.80  3548.6  583.43  3650.6  582.84  3791.3  581.53  3917.0  578.69
  4000.0  577.95  4089.7  575.99  4388.0  572.55  4393.1  573.00  4476.9  572.00
  4518.8  572.27  4535.0  571.45  4569.0  571.18  4812.0  570.17  4936.2  568.65
  4977.3  569.77  4987.3  568.37  4987.7  567.87  4992.4  568.37  5005.6  568.96
  5038.8  568.78  5049.0  570.04  5079.6  569.17  5208.9  570.83  5741.6  579.85
  5793.4  581.44  5803.6  580.01  5824.0  582.44  5849.9  581.94  6028.0  584.18
#Mann=9,-1,0
  3516.5   0.094       0  3548.6   0.063       0  3650.6   0.035       0
  4569.0    0.05       0  4987.3    0.05       0  4992.4    0.05       0
  5208.9   0.035       0  5741.6    0.07       0  5849.9   0.045       0
Bank Sta=4987.3,4992.4
Exp/Cntr=0.3,0.1

Type RM Length L Ch R = 1,537,371,371,371
BEGIN DESCRIPTION:
GERONIMO TRIBUTARY 16 1.0
END DESCRIPTION:
XS GIS Cut Line= 3
      2296424.97     13790375.01      2298425.00     13789375.00
      2297925.00     13788275.00
#Sta/Elev= 30
  2757.2  582.12  2822.3  581.79  2877.4  580.68  2905.4  581.79  2934.0  581.17
  2994.8  581.57  3054.3  580.09  3197.4  577.33  3361.0  575.17  3405.7  573.59
  3935.1  571.23  4387.0  568.03  4450.8  567.71  4498.8  568.35  4515.3  569.08
  4917.8  567.35  4962.6  566.60  4976.8  563.75  4977.2  563.25  4981.9  563.75
  5002.1  566.53  5048.2  568.07  5076.8  566.46  5189.2  567.64  5513.1  570.73
  5755.6  572.81  6048.9  579.66  6073.7  579.29  6125.7  581.00  6201.6  582.35
#Mann=15,-1,0
  2757.2   0.035       0  2822.3   0.063       0  2934.0   0.035       0
  3054.3     0.1       0  3197.4    0.12       0  3935.1    0.07       0
  4387.0    0.12       0  4450.8     0.1       0  4498.8    0.07       0
  4976.8    0.05       0  4981.9    0.07       0  5189.2   0.045       0
  5513.1   0.035       0  6073.7    0.07       0  6125.7   0.045       0
Bank Sta=4976.8,4981.9
Exp/Cntr=0.3,0.1

Type RM Length L Ch R = 1,166,0,0,0
BEGIN DESCRIPTION:
A19011
END DESCRIPTION:
XS GIS Cut Line= 4
      2296696.82     13790366.40      2298627.35     13789602.52
      2298912.07     13789262.24      2298773.19     13787949.82
#Sta/Elev= 30
  2691.8  579.58  2839.9  575.37  3184.5  571.53  3680.1  569.49  3972.2  568.70
  4070.0  568.11  4094.3  562.44  4130.9  568.18  4156.3  568.92  4295.1  568.98
  4724.5  566.59  4758.3  566.19  4845.9  566.53  4948.7  564.81  4963.0  563.33
  4970.8  560.25  4977.3  561.04  4982.5  558.97  4982.9  558.47  4987.6  558.97
  4999.4  562.21  5005.9  561.10  5020.2  564.85  5098.7  565.93  5221.4  565.02
  5366.4  566.51  6015.6  569.51  6105.4  570.42  6253.1  572.40  6531.4  577.97
#Mann=17,-1,0
  2691.8     0.1       0  2839.9    0.12       0  3680.1     0.1       0
  3972.2    0.12       0  4156.3     0.1       0  4295.1   0.035       0
  4724.5     0.1       0  4758.3   0.035       0  4845.9     0.1       0
  4982.5    0.05       0  4987.6     0.1       0  5098.7    0.07       0
  5221.4   0.035       0  5366.4   0.045       0  6015.6    0.07       0
  6105.4   0.035       0  6253.1   0.045       0
Bank Sta=4982.5,4987.6
Exp/Cntr=0.3,0.1

Chan Stop Cuts=-1