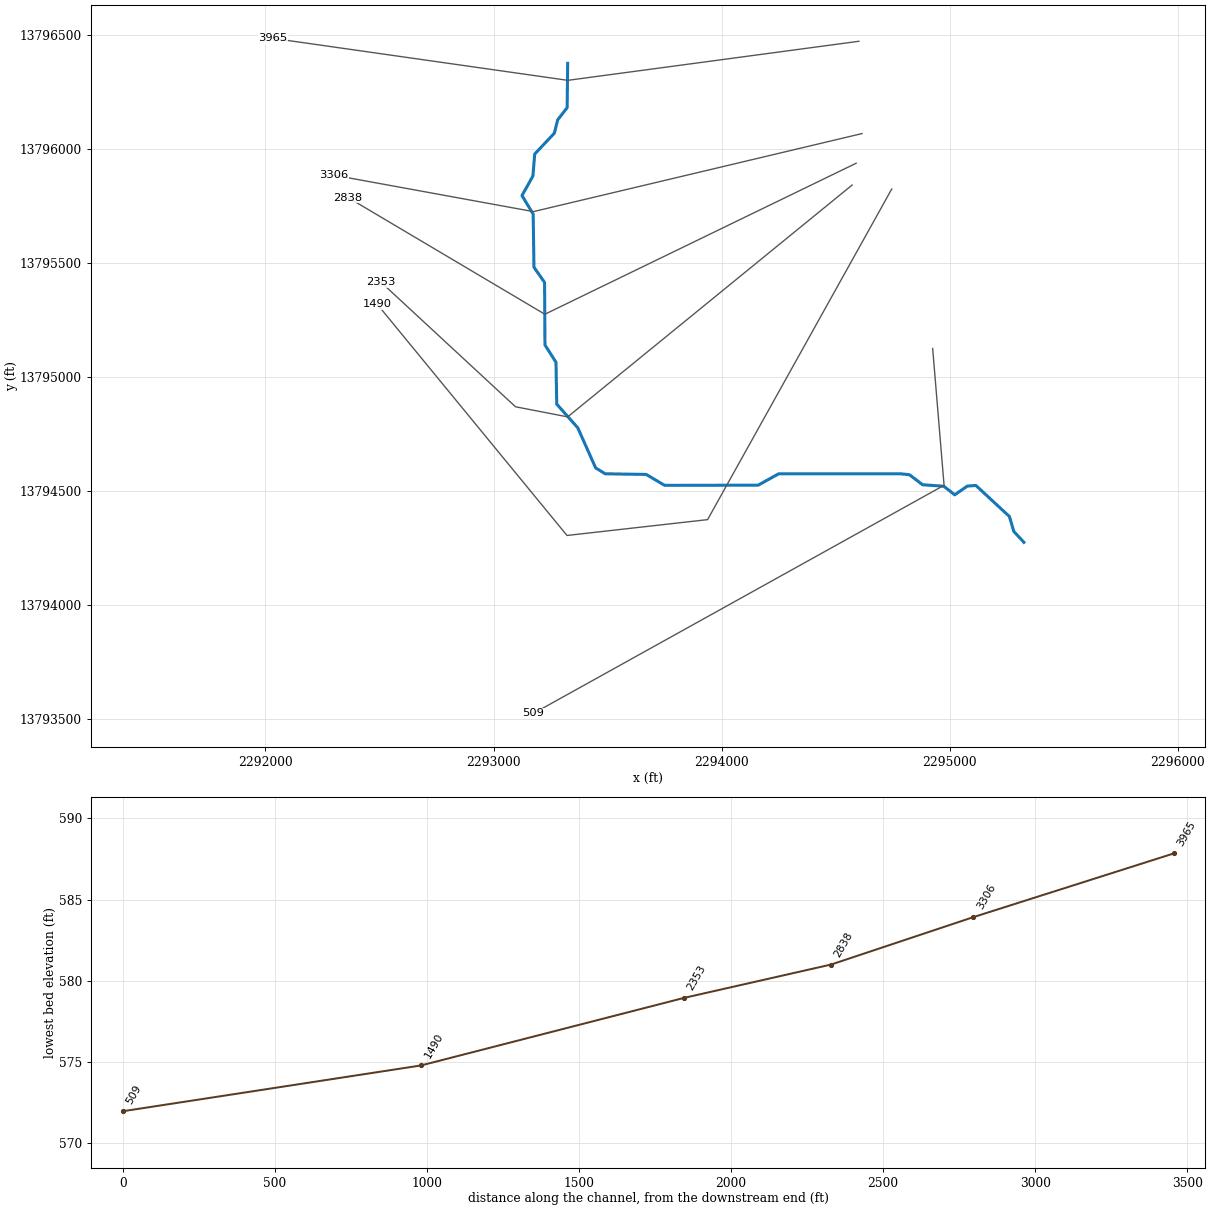
--- GERONIMO TRIBUTARY 17.prj (project) ---

Proj Title=GERONIMO TRIBUTARY 17 Base Level Engineering
Current Plan=p01
Default Exp/Contr=0.3,0.1
English Units
Geom File=g01
Flow File=f01
Plan File=p01
BEGIN DESCRIPTION:
GERONIMO TRIBUTARY 17
END DESCRIPTION:

--- GERONIMO TRIBUTARY 17.p01 (plan) ---

Plan Title=Multiple Run
Short Identifier=Multiple
Geom File=g01
Flow File=f01
Subcritical Flow
K Sum by GR= 0
Std Step Tol= 0.01
Critical Tol= 0.01
Num of Std Step Trials= 20
Max Error Tol= 0.3
Flow Tol Ratio= 0.001
Split Flow NTrial= 30
Split Flow Tol= 0.02
Split Flow Ratio= 0.02
Log Output Level= 0
Friction Slope Method= 1
Unsteady Friction Slope Method= 2
Unsteady Bridges Friction Slope Method= 1
Parabolic Critical Depth
Global Vel Dist=  1 , 1 , 1
Global Log Level= 0
CheckData=True
Encroach Param= -1, 0, 0, 0
BEGIN DESCRIPTION:
Multiple Run
END DESCRIPTION:

--- GERONIMO TRIBUTARY 17.f01 (steady flow) ---

Flow Title=Multiple
Number of Profiles=7
Profile Names=10-year,25-year,50-year,1pct_min,100-year,1pct_plu,500-year
River Rch & RM= GERONIMO TRIBUTA,Reach-1,3965
     667    1075    1442     937    1870    3730    3111
River Rch & RM= GERONIMO TRIBUTA,Reach-1,1490
     880    1438    1948    1277    2547    5082    4315
Boundary for River Rch & Prof#=GERONIMO TRIBUTA,Reach-1,1
Up Type=0
Dn Type=3
Dn Slope=0.005
Boundary for River Rch & Prof#=GERONIMO TRIBUTA,Reach-1,2
Up Type=0
Dn Type=3
Dn Slope=0.005
Boundary for River Rch & Prof#=GERONIMO TRIBUTA,Reach-1,3
Up Type=0
Dn Type=3
Dn Slope=0.005
Boundary for River Rch & Prof#=GERONIMO TRIBUTA,Reach-1,4
Up Type=0
Dn Type=3
Dn Slope=0.005
Boundary for River Rch & Prof#=GERONIMO TRIBUTA,Reach-1,5
Up Type=0
Dn Type=3
Dn Slope=0.005
Boundary for River Rch & Prof#=GERONIMO TRIBUTA,Reach-1,6
Up Type=0
Dn Type=3
Dn Slope=0.005
Boundary for River Rch & Prof#=GERONIMO TRIBUTA,Reach-1,7
Up Type=0
Dn Type=3
Dn Slope=0.005

--- GERONIMO TRIBUTARY 17.g01 (geometry) ---

Geom Title=Existing Conditions

River Reach=GERONIMO TRIBUTA,Reach-1
Reach XY= 30
      2293325.00     13796375.00      2293322.77     13796180.92
      2293281.14     13796127.17      2293266.84     13796068.95
      2293180.54     13795977.42      2293172.62     13795880.97
      2293124.72     13795795.18      2293173.76     13795714.50
      2293177.26     13795480.94      2293223.78     13795414.50
      2293225.52     13795140.22      2293273.78     13795064.49
      2293277.07     13794880.86      2293369.15     13794777.29
      2293447.80     13794601.03      2293490.03     13794575.33
      2293669.06     13794572.74      2293749.92     13794524.80
      2294159.78     13794525.52      2294249.92     13794575.20
      2294785.19     13794575.45      2294823.44     13794571.22
      2294880.98     13794527.35      2294973.50     13794520.91
      2295021.71     13794483.10      2295076.65     13794521.43
      2295114.36     13794524.35      2295261.43     13794388.23
      2295280.71     13794322.65      2295325.00     13794275.00

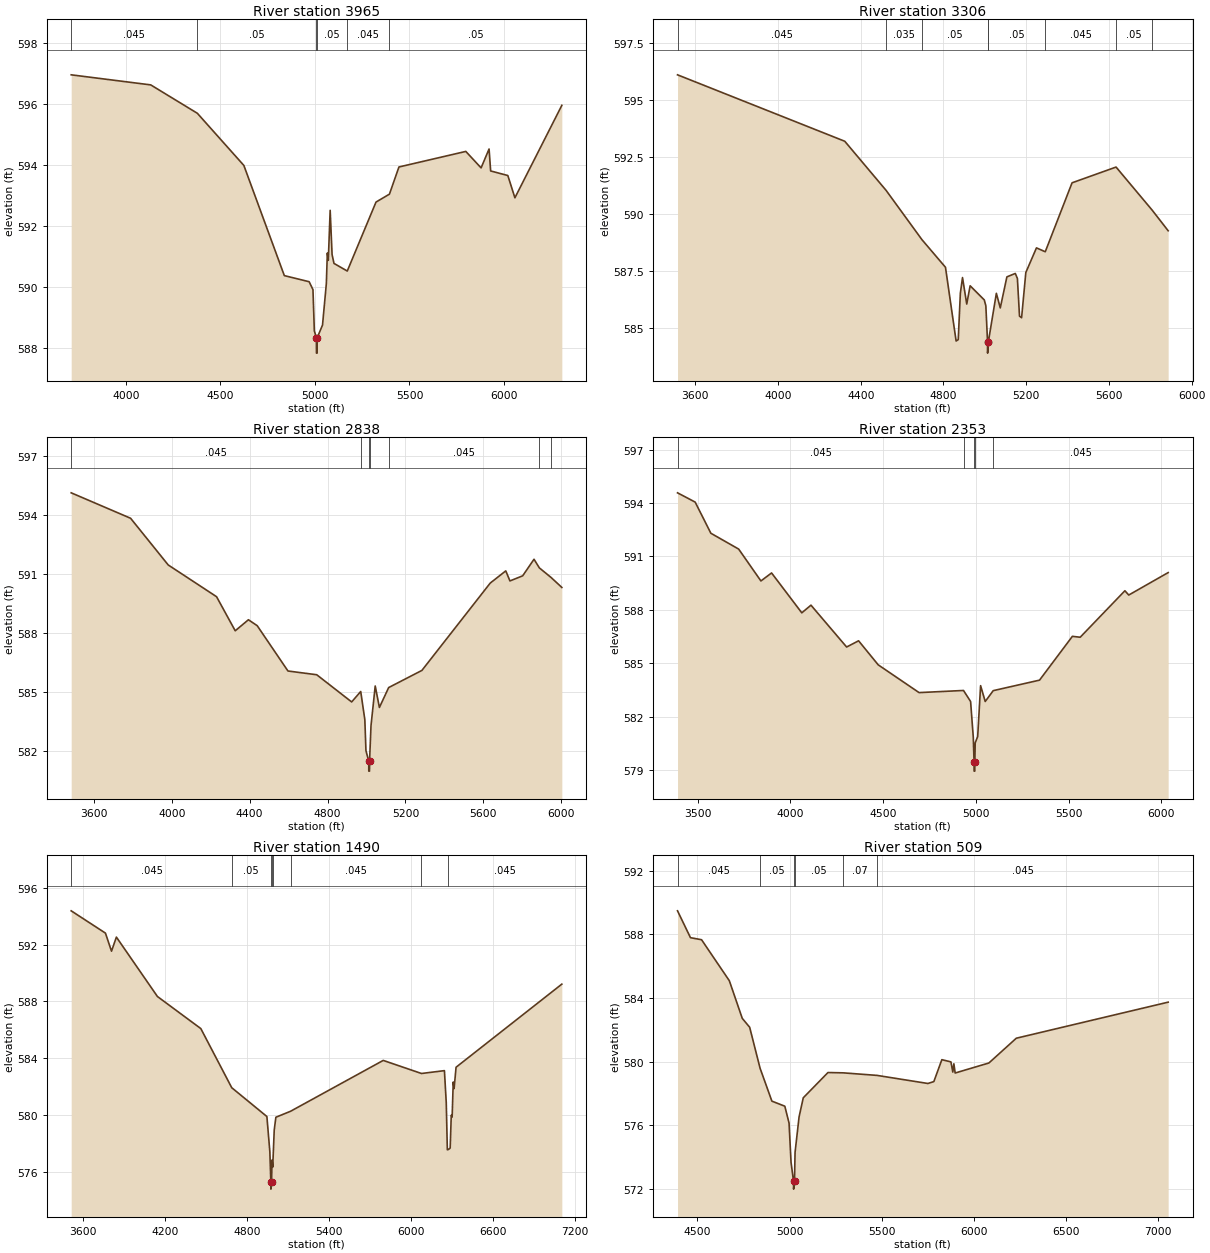
Type RM Length L Ch R = 1,3965,659,659,659
BEGIN DESCRIPTION:
GERONIMO TRIBUTARY 17 5.0
END DESCRIPTION:
XS GIS Cut Line= 3
      2294601.81     13796471.85      2293325.66     13796300.56
      2292032.39     13796484.70
#Sta/Elev= 30
  3711.8  596.96  4132.3  596.63  4378.7  595.70  4624.7  593.99  4838.6  590.38
  4969.8  590.18  4990.0  589.92  4997.2  588.57  5008.2  588.34  5008.4  587.84
  5011.9  587.84  5012.2  588.34  5040.5  588.76  5060.7  590.12  5066.0  591.12
  5071.1  590.88  5080.9  592.52  5091.0  591.07  5101.1  590.78  5171.3  590.53
  5323.3  592.79  5394.3  593.05  5444.5  593.94  5798.0  594.45  5878.8  593.91
  5921.0  594.53  5929.3  593.81  6020.2  593.66  6057.6  592.93  6305.7  595.96
#Mann=6,-1,0
  3711.8   0.045       0  4378.7    0.05       0  5008.2    0.05       0
  5012.2    0.05       0  5171.3   0.045       0  5394.3    0.05       0
Bank Sta=5008.2,5012.2
Exp/Cntr=0.3,0.1

Type RM Length L Ch R = 1,3306,468,468,468
BEGIN DESCRIPTION:
GERONIMO TRIBUTARY 17 4.0
END DESCRIPTION:
XS GIS Cut Line= 3
      2294615.46     13796067.20      2293175.00     13795725.00
      2292297.96     13795885.17
#Sta/Elev= 30
  3514.3  596.11  4322.9  593.20  4522.6  591.05  4696.0  588.89  4809.8  587.68
  4861.2  584.45  4871.5  584.51  4881.7  586.54  4892.1  587.23  4912.6  586.07
  4929.0  586.87  4997.4  586.25  5005.0  585.99  5013.1  584.42  5013.4  583.92
  5017.2  584.42  5055.8  586.54  5074.7  585.90  5106.7  587.26  5147.3  587.41
  5157.5  587.19  5167.7  585.54  5177.8  585.47  5198.2  587.45  5249.7  588.53
  5292.2  588.36  5421.8  591.38  5634.5  592.07  5809.3  590.18  5886.4  589.28
#Mann=8,-1,0
  3514.3   0.045       0  4522.6   0.035       0  4696.0    0.05       0
  5013.1    0.05       0  5017.2    0.05       0  5292.2   0.045       0
  5634.5    0.05       0  5809.3   0.035       0
Bank Sta=5013.1,5017.2
Exp/Cntr=0.3,0.1

Type RM Length L Ch R = 1,2838,485,485,485
BEGIN DESCRIPTION:
GERONIMO TRIBUTARY 17 3.0
END DESCRIPTION:
XS GIS Cut Line= 3
      2294589.38     13795936.98      2293225.00     13795275.00
      2292362.11     13795786.71
#Sta/Elev= 30
  3483.5  595.12  3788.5  593.83  3981.8  591.46  4230.0  589.85  4325.9  588.12
  4393.6  588.68  4438.7  588.38  4596.7  586.08  4744.4  585.89  4923.8  584.51
  4970.4  585.04  4991.5  583.61  4997.2  582.04  5011.6  581.50  5011.8  581.00
  5015.4  581.00  5015.7  581.50  5023.2  583.31  5044.8  585.32  5066.3  584.23
  5113.9  585.24  5284.6  586.11  5635.4  590.54  5715.3  591.16  5736.7  590.65
  5802.2  590.91  5860.3  591.75  5887.9  591.31  5947.4  590.83  6003.2  590.32
#Mann=7,-1,0
  3483.5   0.045       0  4970.4   0.035       0  5011.6   0.035       0
  5015.7   0.035       0  5113.9   0.045       0  5887.9    0.05       0
  5947.4   0.045       0
Bank Sta=5011.6,5015.7
Exp/Cntr=0.3,0.1

Type RM Length L Ch R = 1,2353,863,863,863
BEGIN DESCRIPTION:
GERONIMO TRIBUTARY 17 2.0
END DESCRIPTION:
XS GIS Cut Line= 4
      2294572.01     13795841.48      2293325.00     13794825.00
      2293096.33     13794869.27      2292506.05     13795416.15
#Sta/Elev= 30
  3391.1  594.57  3486.2  594.05  3570.9  592.30  3721.0  591.41  3840.9  589.62
  3898.4  590.07  4061.4  587.83  4110.9  588.26  4303.2  585.91  4367.7  586.26
  4473.5  584.91  4694.0  583.35  4933.6  583.47  4971.9  582.85  4986.3  580.85
  4990.6  579.44  4990.9  578.94  4994.5  578.94  4994.8  579.44  4996.7  580.53
  5010.1  580.88  5025.8  583.74  5050.8  582.85  5094.0  583.46  5343.7  584.05
  5520.9  586.51  5563.1  586.46  5804.1  589.07  5825.0  588.83  6037.5  590.09
#Mann=5,-1,0
  3391.1   0.045       0  4933.6   0.035       0  4990.6   0.035       0
  4994.8   0.035       0  5094.0   0.045       0
Bank Sta=4990.6,4994.8
Exp/Cntr=0.3,0.1

Type RM Length L Ch R = 1,1490,981,981,981
BEGIN DESCRIPTION:
GERONIMO TRIBUTARY 17 1.5
END DESCRIPTION:
XS GIS Cut Line= 4
      2294745.63     13795824.12      2293938.34     13794374.48
      2293322.02     13794305.03      2292489.60     13795319.55
#Sta/Elev= 30
  3513.0  594.38  3763.8  592.81  3808.1  591.54  3843.9  592.53  4144.2  588.35
  4462.0  586.09  4688.2  581.93  4945.6  579.90  4967.3  577.42  4974.5  575.29
  4974.9  574.79  4979.7  575.29  4983.3  576.84  4988.3  576.34  4999.3  578.95
  5011.4  579.85  5118.8  580.27  5797.3  583.85  6077.3  582.93  6245.2  583.13
  6258.7  580.87  6266.6  577.56  6274.7  577.58  6287.4  577.68  6295.3  579.99
  6301.8  579.86  6309.7  582.33  6316.1  581.87  6330.5  583.37  7104.8  589.22
#Mann=8,-1,0
  3513.0   0.045       0  4688.2    0.05       0  4974.5   0.035       0
  4979.7    0.05       0  4988.3   0.035       0  5118.8   0.045       0
  6077.3   0.035       0  6274.7   0.045       0
Bank Sta=4974.5,4979.7
Exp/Cntr=0.3,0.1

Type RM Length L Ch R = 1,509,0,0,0
BEGIN DESCRIPTION:
GERONIMO TRIBUTARY 17 1.0
END DESCRIPTION:
XS GIS Cut Line= 3
      2294925.00     13795124.99      2294975.00     13794525.00
      2293175.00     13793525.00
#Sta/Elev= 30
  4392.1  589.49  4462.3  587.80  4522.5  587.67  4673.1  585.09  4743.3  582.72
  4783.4  582.16  4839.9  579.58  4903.9  577.51  4974.1  577.19  4997.0  576.13
  5007.9  573.65  5021.3  572.47  5021.7  571.97  5026.6  572.47  5029.6  574.28
  5051.4  576.52  5074.2  577.72  5208.1  579.31  5290.7  579.29  5474.1  579.13
  5750.3  578.62  5782.4  578.74  5825.8  580.12  5875.0  579.98  5885.3  579.34
  5891.0  579.86  5897.9  579.28  6080.9  579.91  6229.6  581.47  7053.3  583.74
#Mann=6,-1,0
  4392.1   0.045       0  4839.9    0.05       0  5021.3    0.05       0
  5026.6    0.05       0  5290.7    0.07       0  5474.1   0.045       0
Bank Sta=5021.3,5026.6
Exp/Cntr=0.3,0.1

Chan Stop Cuts=-1