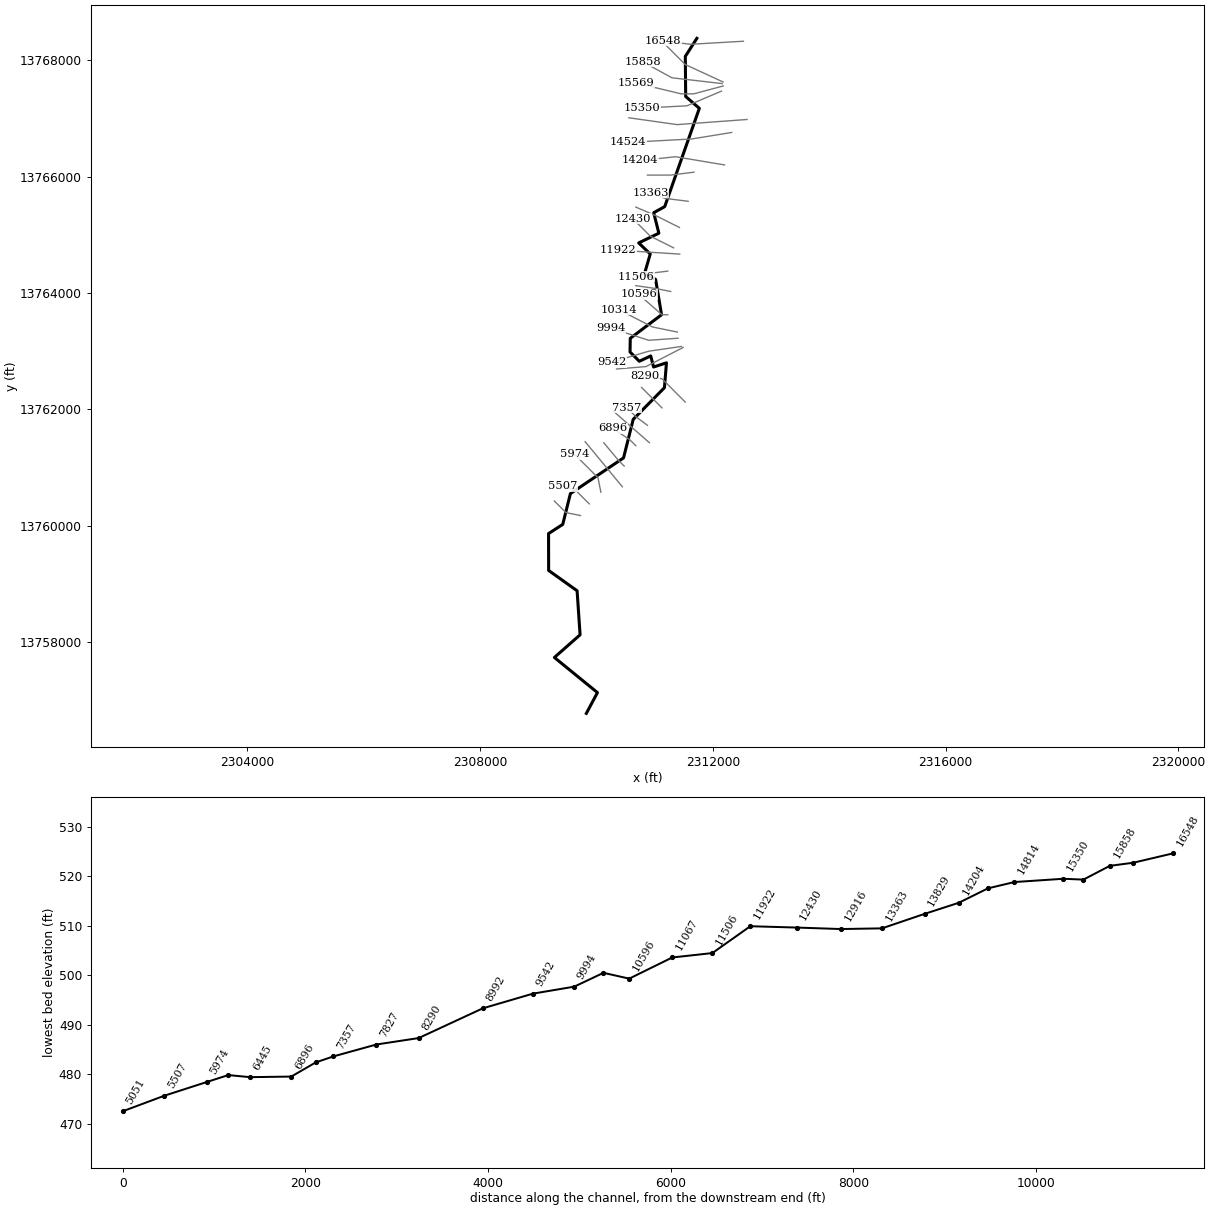
--- GERONIMO TRIBUTARY 2.prj (project) ---

Proj Title=GERONIMO TRIBUTARY 2 Base Level Engineering
Current Plan=p01
Default Exp/Contr=0.3,0.1
English Units
Geom File=g01
Flow File=f01
Plan File=p01
Y Axis Title=Elevation
X Axis Title(PF)=Main Channel Distance
X Axis Title(XS)=Station
BEGIN DESCRIPTION:
GERONIMO TRIBUTARY 2
END DESCRIPTION:
DSS Export Rating Curves= 0
DSS Export Rating Curve Sorted= 0
DSS Export Volume Flow Curves= 0
DXF OffsetX= 0
DXF OffsetY= 0
DXF ScaleX= 1
DXF ScaleY= 10

--- GERONIMO TRIBUTARY 2.p01 (plan) ---

Plan Title=Multiple Run
Short Identifier=Multiple
Geom File=g01
Flow File=f01
Subcritical Flow
K Sum by GR= 0
Std Step Tol= 0.01
Critical Tol= 0.01
Num of Std Step Trials= 20
Max Error Tol= 0.3
Flow Tol Ratio= 0.001
Split Flow NTrial= 30
Split Flow Tol= 0.02
Split Flow Ratio= 0.02
Log Output Level= 0
Friction Slope Method= 1
Unsteady Friction Slope Method= 2
Unsteady Bridges Friction Slope Method= 1
Parabolic Critical Depth
Global Vel Dist=  1 , 1 , 1
Global Log Level= 0
CheckData=True
Encroach Param= -1, 0, 0, 0
BEGIN DESCRIPTION:
Multiple Run
END DESCRIPTION:

--- GERONIMO TRIBUTARY 2.f01 (steady flow) ---

Flow Title=Multiple
Number of Profiles=7
Profile Names=10-year,25-year,50-year,1pct_min,100-year,1pct_plu,500-year
River Rch & RM= GERONIMO TRIBUTA,Reach-1,16548
     585     936    1249     807    1611    3213    2654
River Rch & RM= GERONIMO TRIBUTA,Reach-1,15569
     701    1132    1520     987    1969    3929    3278
River Rch & RM= GERONIMO TRIBUTA,Reach-1,13363
     781    1265    1703    1108    2211    4413    3696
River Rch & RM= GERONIMO TRIBUTA,Reach-1,7827
    1131    1872    2556    1685    3363    6710    5773
River Rch & RM= GERONIMO TRIBUTA,Reach-1,5974
    1354    2258    3098    2052    4093    8168    7088
Boundary for River Rch & Prof#=GERONIMO TRIBUTA,Reach-1,1
Up Type=0
Dn Type=3
Dn Slope=0.005
Boundary for River Rch & Prof#=GERONIMO TRIBUTA,Reach-1,2
Up Type=0
Dn Type=3
Dn Slope=0.005
Boundary for River Rch & Prof#=GERONIMO TRIBUTA,Reach-1,3
Up Type=0
Dn Type=3
Dn Slope=0.005
Boundary for River Rch & Prof#=GERONIMO TRIBUTA,Reach-1,4
Up Type=0
Dn Type=3
Dn Slope=0.005
Boundary for River Rch & Prof#=GERONIMO TRIBUTA,Reach-1,5
Up Type=0
Dn Type=3
Dn Slope=0.005
Boundary for River Rch & Prof#=GERONIMO TRIBUTA,Reach-1,6
Up Type=0
Dn Type=3
Dn Slope=0.005
Boundary for River Rch & Prof#=GERONIMO TRIBUTA,Reach-1,7
Up Type=0
Dn Type=3
Dn Slope=0.005

--- GERONIMO TRIBUTARY 2.g01 (geometry) ---

Geom Title=Existing Conditions
Program Version=4.10

River Reach=GERONIMO TRIBUTA,Reach-1
Reach XY= 30
        2311725.       13768375.      2311526.05     13768064.57
      2311532.75     13767375.09      2311767.25     13767171.97
      2311172.08     13765482.98      2310982.59     13765378.35
      2311071.57     13765026.22      2310724.86     13764859.59
      2310923.39     13764668.97      2310826.04     13764335.11
      2311015.85     13764231.77      2311117.69      13763624.9
      2310580.04     13763219.92      2310576.05     13762985.43
      2310735.64     13762825.55      2310931.69     13762917.55
      2310980.67     13762726.88      2311202.18     13762799.21
      2311167.31     13762371.33      2310630.73     13761827.55
      2310464.37       13761165.      2309551.18     13760551.87
      2309419.48     13760022.56      2309175.53     13759864.55
      2309177.05     13759230.84      2309666.16     13758881.95
      2309717.47     13758124.99      2309275.74     13757735.69
      2310016.01     13757132.07        2309825.       13756775.

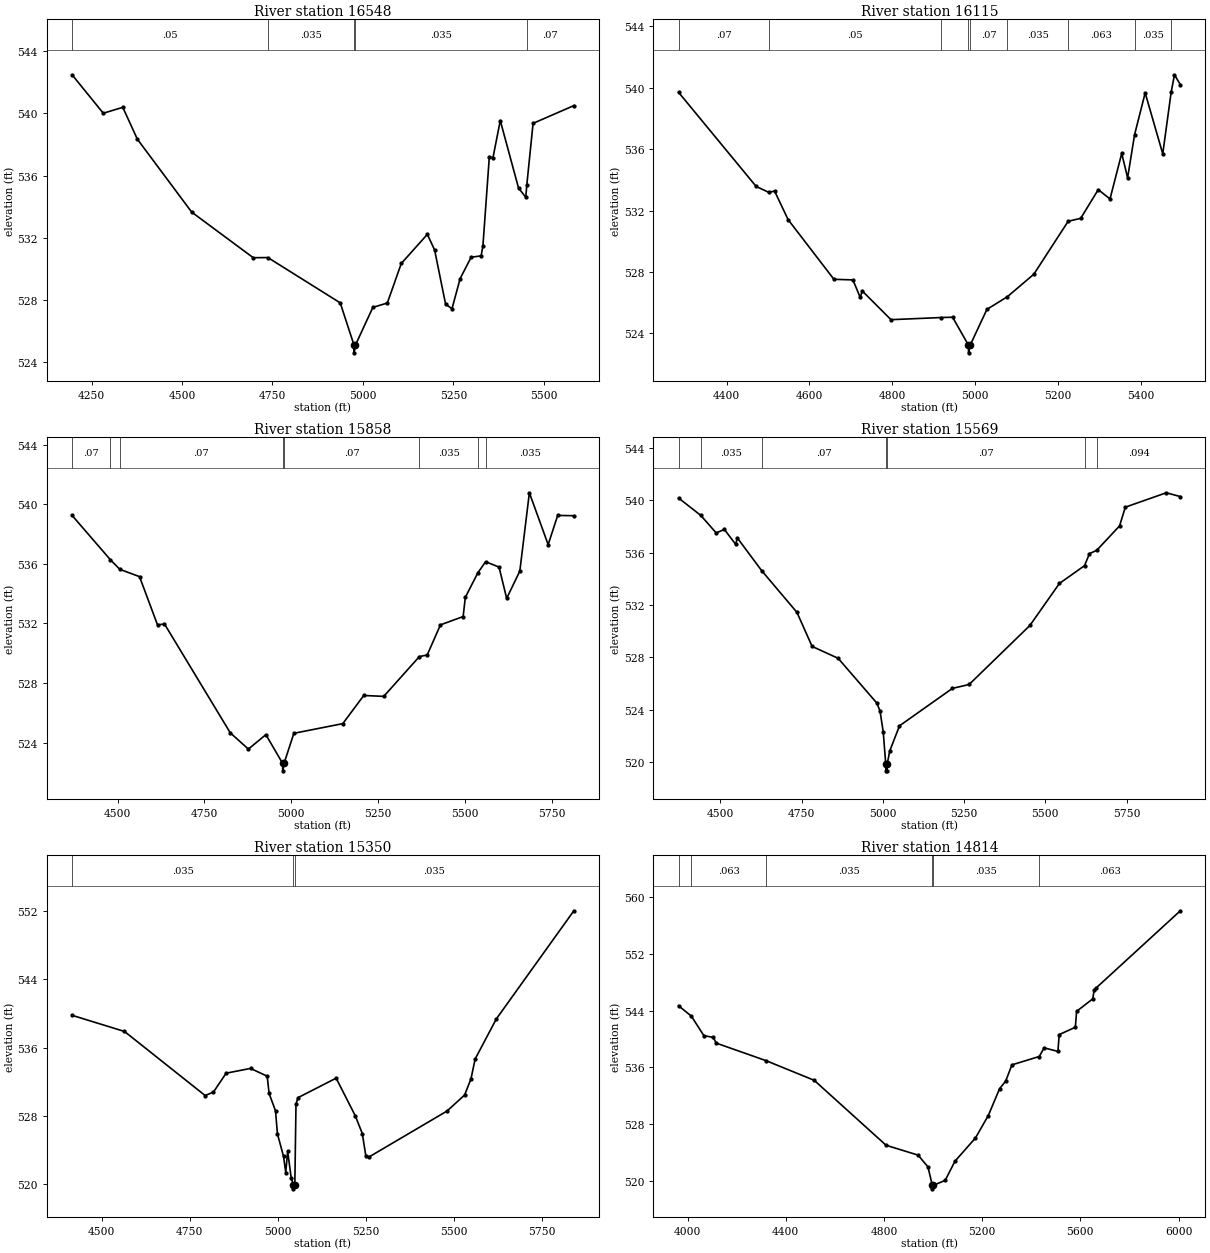
Type RM Length L Ch R = 1 ,16548   ,433,433,433
BEGIN DESCRIPTION:
GERONIMO TRIBUTARY 2 30.0
END DESCRIPTION:
XS GIS Cut Line= 3
      2312525.01       13768325.      2311613.07     13768272.74
      2311143.17     13768331.48
#Sta/Elev= 30
  4196.2  542.47  4282.5     540  4336.4  540.38  4376.5  538.34  4526.8  533.65
    4697  530.72  4737.4  530.73  4937.4  527.82  4975.5  525.11  4975.7  524.61
  4979.5  525.11  5027.6  527.53  5067.6  527.81  5106.2  530.35  5178.2  532.22
  5198.4  531.21  5228.6  527.74  5246.3  527.44  5268.9  529.38  5299.2  530.75
  5326.9  530.84  5331.9   531.5  5349.6  537.22  5359.6  537.14  5379.8  539.53
  5430.2   535.2  5450.3   534.6  5453.2  535.41  5470.5  539.35  5583.2  540.49
#Mann= 5 ,-1 , 0
  4196.2     .05       0  4737.4    .035       0  4975.5    .035       0
  4979.5    .035       0  5453.2     .07       0
Bank Sta=4975.5,4979.5
XS Rating Curve= 0 ,0
Exp/Cntr=0.3,0.1

Type RM Length L Ch R = 1 ,16115   ,257,257,257
BEGIN DESCRIPTION:
GERONIMO TRIBUTARY 2 29.0
END DESCRIPTION:
XS GIS Cut Line= 3
      2312174.97     13767625.01        2311525.       13767925.
      2311175.02     13768274.98
#Sta/Elev= 30
  4284.1   539.7  4471.3  533.57    4502  533.18  4515.8  533.27  4548.4  531.41
    4659  527.52  4704.9  527.48  4722.3  526.35  4727.8  526.75  4796.7  524.89
    4918  525.03  4945.4  525.05  4983.7  523.23  4983.9  522.73  4987.8  523.23
  5028.2  525.56  5077.8  526.39  5141.4  527.85  5224.3   531.3  5254.5  531.49
  5296.9  533.36  5325.2  532.75  5353.5  535.72  5367.7  534.13  5384.6  536.95
  5410.1  539.66  5452.5  535.69  5472.9  539.73  5480.8  540.84  5494.9   540.2
#Mann= 9 ,-1 , 0
  4284.1     .07       0    4502     .05       0    4918     .07       0
  4983.7     .05       0  4987.8     .07       0  5077.8    .035       0
  5224.3    .063       0  5384.6    .035       0  5472.9     .07       0
Bank Sta=4983.7,4987.8
XS Rating Curve= 0 ,0
Exp/Cntr=0.3,0.1

Type RM Length L Ch R = 1 ,15858   ,289,289,289
BEGIN DESCRIPTION:
A19032
END DESCRIPTION:
XS GIS Cut Line= 3
      2312159.34     13767597.28       2311295.9     13767697.13
      2310790.81     13767973.17
#Sta/Elev= 30
  4369.1  539.25  4479.2  536.28  4506.5  535.63  4563.3  535.14  4615.1   531.9
  4635.2  531.96  4824.7  524.65  4876.8  523.56  4927.1  524.53  4975.4   522.6
  4975.7   522.1  4979.5   522.6  5007.7  524.62  5148.6  525.27    5209  527.16
  5266.5   527.1    5369  529.77  5391.7  529.88  5429.7   531.9  5495.1  532.46
  5501.4  533.75  5537.3  535.39  5559.8  536.14  5598.5  535.78  5620.4  533.68
  5658.3  535.51  5685.8  540.77  5739.9  537.29  5767.4  539.25  5813.9  539.23
#Mann= 8 ,-1 , 0
  4369.1     .07       0  4479.2    .035       0  4506.5     .07       0
  4975.4     .05       0  4979.5     .07       0    5369    .035       0
  5537.3    .094       0  5559.8    .035       0
Bank Sta=4975.4,4979.5
XS Rating Curve= 0 ,0
Exp/Cntr=0.3,0.1

Type RM Length L Ch R = 1 ,15569   ,219,219,219
BEGIN DESCRIPTION:
A19031
END DESCRIPTION:
XS GIS Cut Line= 4
      2312176.95     13767556.17      2311671.81     13767421.08
      2311454.49     13767421.08      2310673.29     13767609.03
#Sta/Elev= 30
  4371.5  540.17    4440  538.84  4487.4   537.5  4512.4  537.77  4547.3  536.63
  4552.4  537.12  4626.9  534.63  4735.8  531.43  4782.4  528.83  4862.5  527.92
  4981.2  524.51  4991.2  523.91  5001.2  522.31    5009  519.82  5009.3  519.32
  5013.1  519.32  5013.4  519.82  5021.2  520.83  5051.2  522.76    5214  525.62
  5265.5  525.92  5452.4  530.43  5543.2  533.64  5620.5     535  5635.7  535.92
  5657.9  536.17  5728.3  538.04    5746  539.47  5871.9  540.57  5915.2  540.28
#Mann= 7 ,-1 , 0
  4371.5     .07       0    4440    .035       0  4626.9     .07       0
    5009     .05       0  5013.4     .07       0  5620.5    .035       0
  5657.9    .094       0
Bank Sta=5009,5013.4
XS Rating Curve= 0 ,0
Exp/Cntr=0.3,0.1

Type RM Length L Ch R = 1 ,15350   ,536,536,536
BEGIN DESCRIPTION:
GERONIMO TRIBUTARY 2 28.0
END DESCRIPTION:
XS GIS Cut Line= 3
       2312147.6     13767468.08      2311554.34      13767215.5
      2310774.98       13767175.
#Sta/Elev= 30
  4415.9  539.78  4564.8  537.89  4793.8   530.4  4817.4   530.8  4853.5  533.01
  4922.8  533.57  4970.1  532.66  4975.5  530.64  4993.7  528.61  4999.2  525.92
  5016.5  523.28  5022.8   521.4  5028.2  523.88  5038.2  520.79  5044.2  519.99
  5044.5  519.49  5048.6  519.99  5051.9  529.39  5057.6  530.15  5165.9  532.43
  5220.2  528.04  5240.3  525.95  5250.3  523.32  5260.3  523.24  5480.6  528.58
  5530.7  530.45  5548.9  532.35  5560.7  534.67  5620.8  539.35  5841.1     552
#Mann= 3 ,-1 , 0
  4415.9    .035       0  5044.2    .035       0  5048.6    .035       0
Bank Sta=5044.2,5048.6
XS Rating Curve= 0 ,0
Exp/Cntr=0.3,0.1

Type RM Length L Ch R = 1 ,14814   ,290,290,290
BEGIN DESCRIPTION:
GERONIMO TRIBUTARY 2 27.0
END DESCRIPTION:
XS GIS Cut Line= 3
      2312588.05     13766980.56        2311384.     13766892.45
      2310555.86     13767009.92
#Sta/Elev= 30
  3963.4  544.68  4015.5  543.21  4066.7  540.45  4104.9  540.21  4116.9   539.4
  4319.3  536.93    4516  534.15  4808.7  524.98  4939.1  523.59  4979.2  521.93
    4997  519.33  4997.3  518.83  5001.5  519.33  5049.3  520.02  5089.5  522.74
  5172.7  526.01  5224.8  529.16  5270.7  532.95  5295.8  534.04  5321.2  536.33
  5432.5  537.51  5452.5  538.73  5508.6  538.23  5513.7   540.6  5579.6  541.64
  5584.6  543.88  5650.5  545.65  5655.6  546.83  5664.6   547.2  6007.1  558.08
#Mann= 6 ,-1 , 0
  3963.4    .094       0  4015.5    .063       0  4319.3    .035       0
    4997    .035       0  5001.5    .035       0  5432.5    .063       0
Bank Sta=4997,5001.5
XS Rating Curve= 0 ,0
Exp/Cntr=0.3,0.1

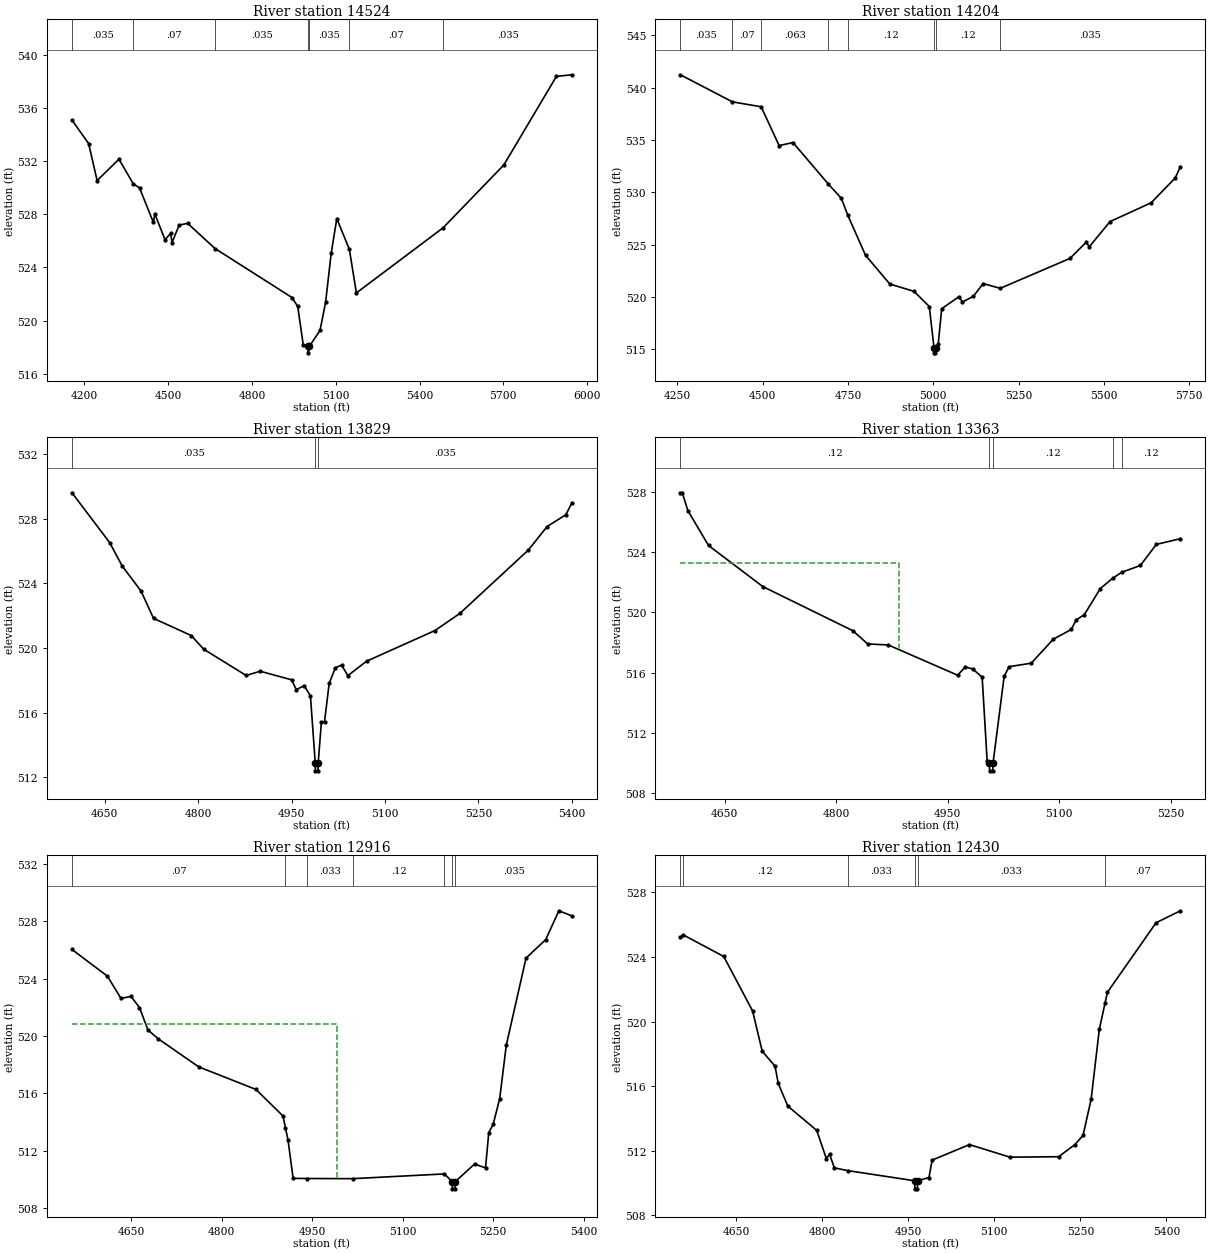
Type RM Length L Ch R = 1 ,14524   ,320,320,320
BEGIN DESCRIPTION:
GERONIMO TRIBUTARY 2 26.0
END DESCRIPTION:
XS GIS Cut Line= 3
      2312323.79     13766757.37      2311636.57     13766645.76
      2310544.07     13766587.03
#Sta/Elev= 30
  4155.5  535.12  4215.1  533.35  4245.5  530.56  4323.8  532.17  4374.8  530.32
  4397.4     530    4447   527.4  4452.1  528.04  4488.6   526.1  4508.6  526.57
  4513.7  525.88  4539.3   527.2  4569.6  527.33  4667.7  525.43  4943.4  521.73
  4963.8  521.06  4983.5  518.17  5001.2  518.06  5001.5  517.56  5005.9  518.06
  5043.6  519.25  5063.6  521.37  5083.6  525.07  5103.7  527.69  5148.8  525.36
  5173.8  522.08  5484.6     527  5701.9  531.74  5890.1  538.42  5945.8  538.54
#Mann= 7 ,-1 , 0
  4155.5    .035       0  4374.8     .07       0  4667.7    .035       0
  5001.2    .035       0  5005.9    .035       0  5148.8     .07       0
  5484.6    .035       0
Bank Sta=5001.2,5005.9
XS Rating Curve= 0 ,0
Exp/Cntr=0.3,0.1

Type RM Length L Ch R = 1 ,14204   ,375,375,375
BEGIN DESCRIPTION:
GERONIMO TRIBUTARY 2 25.0
END DESCRIPTION:
XS GIS Cut Line= 3
      2312200.43     13766199.37      2311360.51     13766340.34
      2310749.78     13766275.74
#Sta/Elev= 30
  4258.6  541.23  4411.1  538.64  4495.3  538.17    4548  534.46  4588.6  534.75
  4691.8   530.8  4730.5  529.41  4749.4  527.79  4801.3  523.97  4872.5  521.22
  4943.5  520.52  4988.2  519.07    5002  515.14  5002.3  514.64  5006.3  514.64
  5006.7  515.14  5014.5  515.52  5024.6  518.86  5075.3  520.01  5085.4   519.5
  5117.2  520.04    5146  521.26  5196.3  520.81  5400.6  523.67  5447.6   525.2
  5457.7   524.8    5518  527.19  5638.7  528.99  5709.1  531.36  5724.4  532.45
#Mann= 8 ,-1 , 0
  4258.6    .035       0  4411.1     .07       0  4495.3    .063       0
  4691.8    .035       0  4749.4     .12       0    5002     .05       0
  5006.7     .12       0  5196.3    .035       0
Bank Sta=5002,5006.7
XS Rating Curve= 0 ,0
Exp/Cntr=0.3,0.1

Type RM Length L Ch R = 1 ,13829   ,466,466,466
BEGIN DESCRIPTION:
GERONIMO TRIBUTARY 2 24.0
END DESCRIPTION:
XS GIS Cut Line= 3
      2311675.03       13766075.        2311275.       13766025.
      2310875.05       13766025.
#Sta/Elev= 30
  4597.2   529.6  4657.7  526.52  4677.9  525.07  4708.1  523.52  4728.2  521.83
  4788.7  520.77  4808.9  519.92  4876.9   518.3  4899.6  518.56    4950  518.03
  4957.5  517.42  4970.1  517.67  4980.2  517.04  4987.9   512.9  4988.2   512.4
  4992.3   512.4  4992.7   512.9  4997.8  515.43  5002.8  515.43  5010.3  517.81
  5020.3  518.78  5030.3  518.94  5040.3  518.29  5070.3  519.18  5180.3  521.08
  5220.3  522.14  5330.3  526.06  5360.3  527.51  5390.3  528.24  5400.3  528.98
#Mann= 3 ,-1 , 0
  4597.2    .035       0  4987.9    .035       0  4992.7    .035       0
Bank Sta=4987.9,4992.7
XS Rating Curve= 0 ,0
Exp/Cntr=0.3,0.1

Type RM Length L Ch R = 1 ,13363   ,447,447,447
BEGIN DESCRIPTION:
GERONIMO TRIBUTARY 2 23.0
END DESCRIPTION:
XS GIS Cut Line= 3
      2311574.99       13765575.        2311175.       13765625.
      2310924.96     13765725.02
#Sta/Elev= 30
  4590.7  527.95  4593.2  527.95  4600.8  526.76  4628.5  524.45  4701.5  521.72
  4822.5  518.79  4842.6  517.91  4870.3  517.84  4963.6  515.83  4973.6  516.38
  4983.7  516.25  4996.5   515.7  5003.2  510.13  5006.2  509.98  5006.5  509.48
  5010.7  509.48  5011.1  509.98  5026.1  515.77  5032.8   516.4  5062.5  516.63
  5092.1  518.22  5116.3  518.87    5123  519.51  5133.8  519.85  5155.4  521.59
    5172  522.27  5184.2  522.67  5209.2  523.12  5230.7  524.52  5263.1   524.9
#Mann= 5 ,-1 , 0
  4590.7     .12       0  5006.2     .05       0  5011.1     .12       0
    5172    .035       0  5184.2     .12       0
#XS Ineff= 2 , 0
       0  4884.4  523.28               0
Permanent Ineff=
       F       F
Bank Sta=5006.2,5011.1
XS Rating Curve= 0 ,0
Exp/Cntr=0.3,0.1

Type RM Length L Ch R = 1 ,12916   ,486,486,486
BEGIN DESCRIPTION:
GERONIMO TRIBUTARY 2 22.0
END DESCRIPTION:
XS GIS Cut Line= 3
      2311425.02     13765124.99        2311025.       13765325.
      2310675.02     13765474.99
#Sta/Elev= 30
  4552.4  526.03  4611.1  524.17  4633.5  522.62  4650.2  522.76  4664.2  521.98
  4678.2  520.42    4695  519.81  4762.1  517.85  4857.1  516.27  4901.8  514.42
  4905.9   513.6  4910.2  512.73  4918.6  510.07  4942.4  510.06  5017.1  510.05
  5169.1  510.38  5182.1  509.84  5182.5  509.34  5186.7  509.34  5187.1  509.84
    5219  511.07  5237.2   510.8  5242.6  513.26  5249.9  513.84  5260.7  515.63
  5271.6  519.36  5304.3  525.43  5336.9  526.72  5358.7  528.73  5380.4  528.37
#Mann= 7 ,-1 , 0
  4552.4     .07       0  4905.9     .12       0  4942.4    .033       0
  5017.1     .12       0  5169.1    .035       0  5182.1    .033       0
  5187.1    .035       0
#XS Ineff= 2 , 0
       0  4991.2  520.81               0
Permanent Ineff=
       F       F
Bank Sta=5182.1,5187.1
XS Rating Curve= 0 ,0
Exp/Cntr=0.3,0.1

Type RM Length L Ch R = 1 ,12430   ,508,508,508
BEGIN DESCRIPTION:
GERONIMO TRIBUTARY 2 21.0
END DESCRIPTION:
XS GIS Cut Line= 3
        2311325.       13764775.        2310925.       13764975.
      2310624.99     13765275.01
#Sta/Elev= 30
  4552.8  525.22  4557.6  525.37  4628.3  524.03  4678.6  520.66  4695.4  518.16
  4717.7  517.24  4723.3  516.17  4740.1  514.76  4790.4  513.26  4807.2  511.51
  4812.7  511.79  4821.1  510.94  4844.2  510.77  4961.1  510.14  4961.5  509.64
  4965.8  509.64  4966.2  510.14    4986  510.34  4991.6  511.42  5056.6  512.38
  5127.3   511.6  5212.1  511.63  5240.4  512.38  5254.6  512.95  5268.7  515.19
  5282.9  519.51  5292.9  521.14    5297  521.81  5381.9  526.12  5424.3  526.86
#Mann= 6 ,-1 , 0
  4552.8    .035       0  4557.6     .12       0  4844.2    .033       0
  4961.1    .033       0  4966.2    .033       0  5292.9     .07       0
Bank Sta=4961.1,4966.2
XS Rating Curve= 0 ,0
Exp/Cntr=0.3,0.1

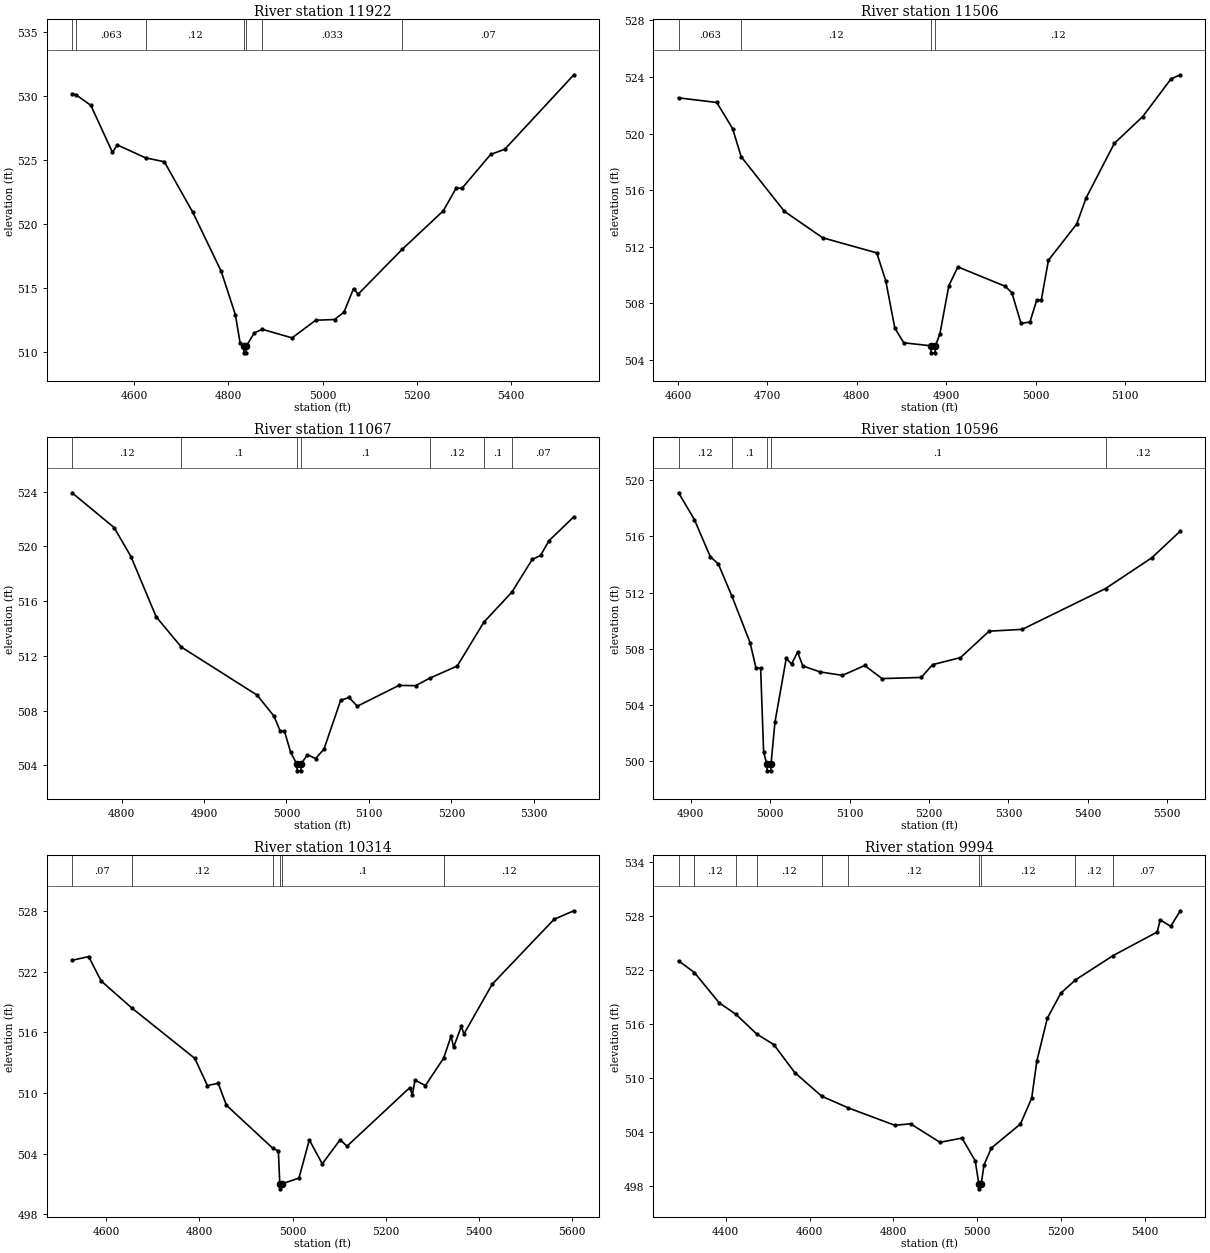
Type RM Length L Ch R = 1 ,11922   ,416,416,416
BEGIN DESCRIPTION:
GERONIMO TRIBUTARY 2 20.0
END DESCRIPTION:
XS GIS Cut Line= 3
      2311430.53      13764667.6      2310809.67     13764706.12
      2310368.95     13764737.76
#Sta/Elev= 30
  4468.8   530.2  4476.9  530.12  4508.5  529.29  4554.5   525.6  4564.5  526.19
  4624.5  525.18  4664.4  524.87  4724.8  520.91  4784.9   516.3    4815   512.9
    4825   510.7  4832.8  510.41  4833.2  509.91  4837.5  509.91  4837.9  510.41
  4855.1  511.48  4872.3  511.75  4935.2  511.08  4985.3  512.46  5025.4  512.52
  5045.4   513.1  5065.5  514.93  5075.5  514.51  5168.9  518.02  5255.9  521.03
  5282.9  522.79    5296  522.81  5356.2  525.44  5386.3  525.85  5532.7  531.68
#Mann= 7 ,-1 , 0
  4468.8    .035       0  4476.9    .063       0  4624.5     .12       0
  4832.8    .033       0  4837.9     .12       0  4872.3    .033       0
  5168.9     .07       0
Bank Sta=4832.8,4837.9
XS Rating Curve= 0 ,0
Exp/Cntr=0.3,0.1

Type RM Length L Ch R = 1 ,11506   ,439,439,439
BEGIN DESCRIPTION:
GERONIMO TRIBUTARY 2 19.0
END DESCRIPTION:
XS GIS Cut Line= 3
        2311225.       13764375.        2310825.       13764325.
      2310675.02     13764275.01
#Sta/Elev= 30
  4600.7  522.53  4643.5   522.2  4661.2  520.35  4670.7  518.37  4719.1   514.5
  4761.9  512.63  4822.4  511.56  4832.5  509.57  4842.6  506.24  4852.6   505.2
  4882.8  504.99  4883.2  504.49  4887.6  504.49    4888  504.99    4893  505.83
    4903  509.24  4913.1  510.57    4966   509.2  4973.6  508.73  4983.7  506.57
  4993.7  506.67  5001.3  508.22  5006.4  508.22  5014.4  511.04    5046   513.6
  5056.5  515.44  5088.1  519.31  5119.8   521.2  5151.4  523.86  5161.9  524.16
#Mann= 4 ,-1 , 0
  4600.7    .063       0  4670.7     .12       0  4882.8     .05       0
    4888     .12       0
Bank Sta=4882.8,4888
XS Rating Curve= 0 ,0
Exp/Cntr=0.3,0.1

Type RM Length L Ch R = 1 ,11067   ,471,471,471
BEGIN DESCRIPTION:
GERONIMO TRIBUTARY 2 18.0
END DESCRIPTION:
XS GIS Cut Line= 3
      2311275.04     13764024.99        2311025.       13764075.
      2310675.05     13764124.99
#Sta/Elev= 30
    4740  523.91    4791  521.37  4811.4  519.25    4842  514.85  4872.5  512.64
  4964.4  509.13  4984.8   507.6  4992.4  506.51  4997.5  506.51  5005.1  504.95
  5012.5   504.1    5013   503.6  5017.4   503.6  5017.8   504.1  5025.3  504.77
  5035.4   504.5  5045.5  505.19  5065.7  508.75  5075.8  508.96  5085.9  508.32
  5136.4  509.84  5156.6  509.82  5173.5  510.36  5207.1  511.26  5239.4  514.46
  5273.4  516.66    5298  519.04  5308.1  519.33  5318.2   520.4  5348.5  522.16
#Mann= 7 ,-1 , 0
    4740     .12       0  4872.5      .1       0  5012.5     .05       0
  5017.8      .1       0  5173.5     .12       0  5239.4      .1       0
  5273.4     .07       0
Bank Sta=5012.5,5017.8
XS Rating Curve= 0 ,0
Exp/Cntr=0.3,0.1

Type RM Length L Ch R = 1 ,10596   ,282,282,282
BEGIN DESCRIPTION:
GERONIMO TRIBUTARY 2 17.0
END DESCRIPTION:
XS GIS Cut Line= 3
      2311224.97       13763625.        2311125.       13763625.
      2310724.98     13763975.01
#Sta/Elev= 30
  4884.8   519.1  4904.8  517.19  4924.8  514.55  4934.8  514.05  4952.1  511.73
  4974.8  508.45  4982.3  506.64  4988.1  506.64  4991.9  500.65  4995.9  499.83
  4996.3  499.33  5000.8  499.33  5001.2  499.83  5006.1  502.77  5020.4  507.34
    5027  506.92  5034.6  507.77  5041.2  506.79  5063.1  506.36  5091.1  506.12
  5119.1  506.82  5140.9  505.89  5190.3  505.97  5204.5  506.88  5239.6  507.38
  5275.7  509.26  5317.4  509.39  5422.2  512.29  5480.7  514.49  5516.3  516.38
#Mann= 5 ,-1 , 0
  4884.8     .12       0  4952.1      .1       0  4995.9     .05       0
  5001.2      .1       0  5422.2     .12       0
Bank Sta=4995.9,5001.2
XS Rating Curve= 0 ,0
Exp/Cntr=0.3,0.1

Type RM Length L Ch R = 1 ,10314   ,320,320,320
BEGIN DESCRIPTION:
A19030
END DESCRIPTION:
XS GIS Cut Line= 3
       2311389.9      13763327.2      2310961.11      13763415.3
       2310391.4     13763708.97
#Sta/Elev= 30
  4526.1  523.15  4561.7  523.52  4588.5  521.11  4654.4  518.43  4789.9  513.43
    4817  510.74  4840.3  510.96  4857.8  508.79  4957.9  504.51  4969.6  504.26
  4972.6     501    4973   500.5  4977.9     501  5013.9  501.57  5036.1  505.35
  5063.9  502.98  5102.6  505.38    5117  504.72    5252  510.53  5257.7  509.82
  5263.3  511.27  5285.7  510.74  5324.9  513.46  5340.8  515.62  5346.4  514.55
  5362.9  516.61  5368.5  515.85  5429.4  520.79  5562.4  527.22  5604.8  528.06
#Mann= 6 ,-1 , 0
  4526.1     .07       0  4654.4     .12       0  4957.9      .1       0
  4972.6     .05       0  4977.9      .1       0  5324.9     .12       0
Bank Sta=4972.6,4977.9
XS Rating Curve= 0 ,0
Exp/Cntr=0.3,0.1

Type RM Length L Ch R = 1 ,9994    ,452,452,452
BEGIN DESCRIPTION:
A19029
END DESCRIPTION:
XS GIS Cut Line= 3
      2311401.66     13763221.48       2310896.5     13763186.24
       2310239.3     13763397.48
#Sta/Elev= 30
  4287.6  523.05  4325.4  521.75  4384.5  518.38  4424.6   517.1  4474.2  514.91
  4514.8  513.74  4564.9  510.62  4629.5  507.99  4692.9   506.7  4803.5  504.77
  4840.9  504.94  4911.1  502.88  4963.6  503.35  4995.1  500.83    5004  498.21
  5004.4  497.71  5009.3  498.21  5016.1  500.36  5033.5  502.24  5102.9  504.91
  5129.8  507.78  5142.2  511.93  5167.1  516.67  5199.2  519.45  5234.3  520.93
    5324  523.63  5429.1  526.25  5436.3   527.6  5461.2  526.88  5484.3  528.61
#Mann= 10 ,-1 , 0
  4287.6     .07       0  4325.4     .12       0  4424.6     .07       0
  4474.2     .12       0  4629.5      .1       0  4692.9     .12       0
    5004     .05       0  5009.3     .12       0  5234.3     .12       0
    5324     .07       0
Bank Sta=5004,5009.3
XS Rating Curve= 0 ,0
Exp/Cntr=0.3,0.1

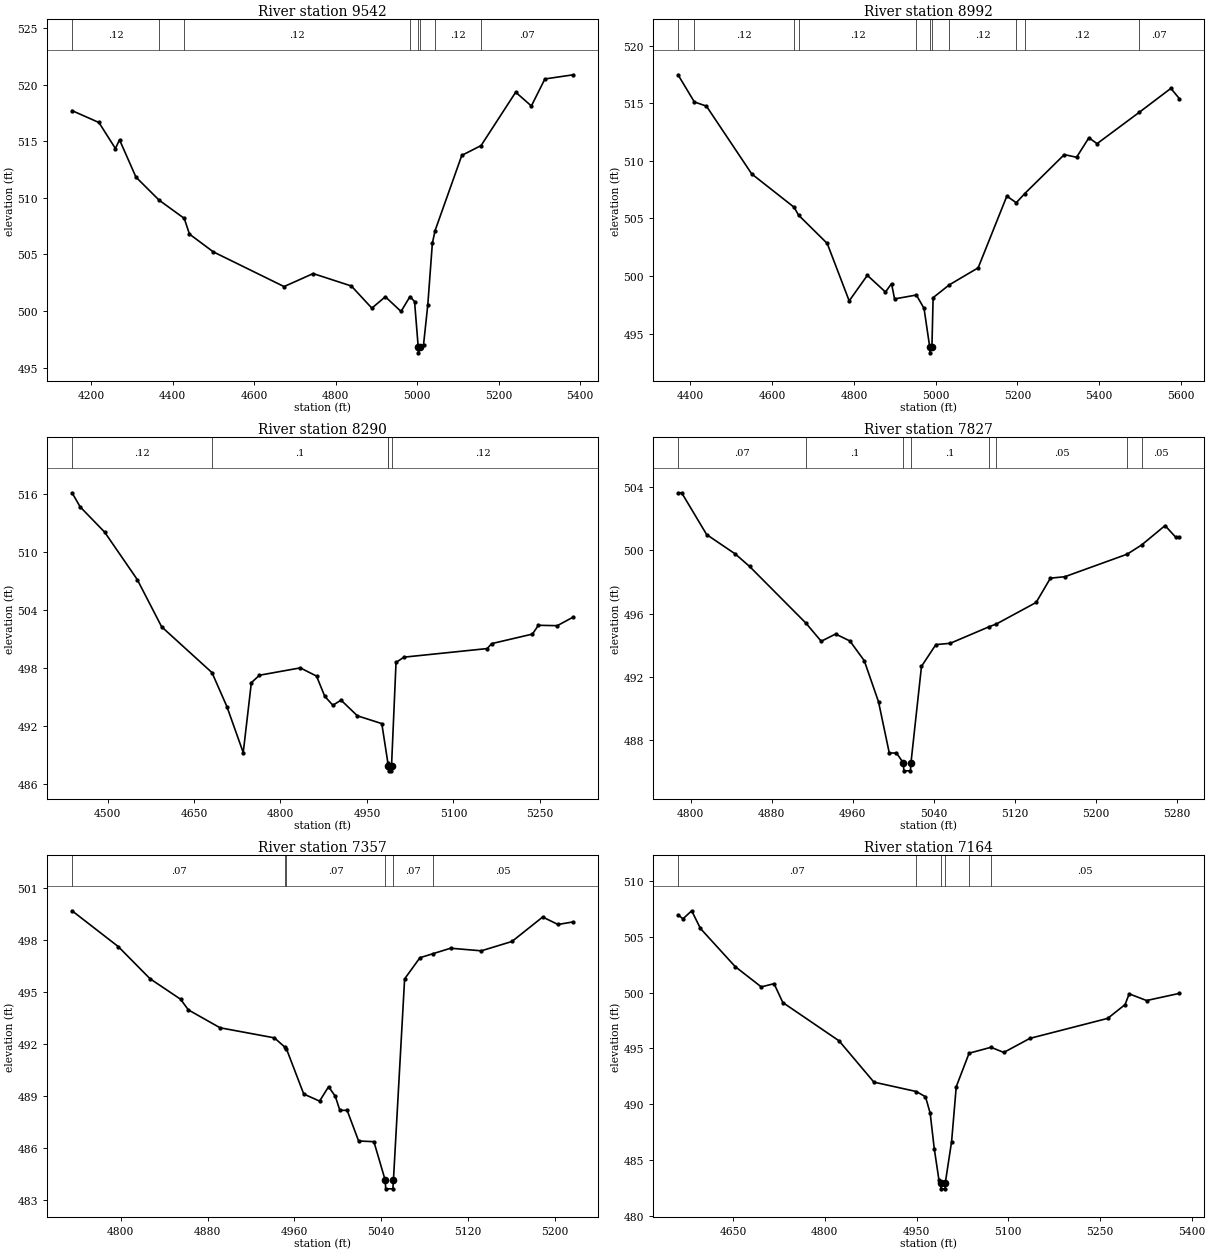
Type RM Length L Ch R = 1 ,9542    ,550,550,550
BEGIN DESCRIPTION:
A19028
END DESCRIPTION:
XS GIS Cut Line= 3
      2311460.34     13763080.51       2310896.5     13762998.28
      2310262.16     13762810.33
#Sta/Elev= 30
  4152.5  517.72  4218.5  516.67    4259  514.37  4269.1  515.14  4309.5  511.84
  4366.4   509.8  4428.1  508.19  4440.9   506.8  4499.5  505.23  4673.3  502.16
  4744.7  503.31  4838.6  502.21  4888.9  500.25    4922  501.26  4960.6  499.96
  4982.6  501.28  4993.8  500.83  5002.8   496.8  5003.2   496.3  5008.2   496.8
  5015.9  497.03  5026.3  500.54  5037.5  505.98  5044.1   507.1  5109.8  513.76
  5157.2  514.63  5242.2  519.35  5280.7  518.13  5313.9  520.52  5383.9  520.89
#Mann= 8 ,-1 , 0
  4152.5     .12       0  4366.4     .07       0  4428.1     .12       0
  4982.6     .07       0  5002.8     .05       0  5008.2     .07       0
  5044.1     .12       0  5157.2     .07       0
Bank Sta=5002.8,5008.2
XS Rating Curve= 0 ,0
Exp/Cntr=0.3,0.1

Type RM Length L Ch R = 1 ,8992    ,702,702,702
BEGIN DESCRIPTION:
A19027
END DESCRIPTION:
XS GIS Cut Line= 3
      2311489.68     13763062.87      2310849.51     13762733.97
       2310344.4     13762692.86
#Sta/Elev= 30
  4369.5  517.47  4409.5  515.11    4439  514.75  4549.9  508.86  4653.5  505.97
  4664.5  505.28  4734.5  502.83  4788.3  497.84  4832.7  500.06  4877.1  498.61
  4891.9  499.34  4899.3  498.01  4952.6  498.35  4971.4  497.19  4985.3  493.83
  4985.7  493.33  4990.7  493.83  4993.6  498.12  5033.1  499.23  5103.8  500.71
    5174  506.94    5197  506.36  5217.9  507.16  5314.5  510.54  5344.6  510.31
  5374.7     512  5394.7  511.49  5497.9  514.21  5575.3  516.29    5596   515.4
#Mann= 11 ,-1 , 0
  4369.5     .07       0  4409.5     .12       0  4653.5     .07       0
  4664.5     .12       0  4952.6      .1       0  4985.3     .05       0
  4990.7      .1       0  5033.1     .12       0    5197     .07       0
  5217.9     .12       0  5497.9     .07       0
Bank Sta=4985.3,4990.7
XS Rating Curve= 0 ,0
Exp/Cntr=0.3,0.1

Type RM Length L Ch R = 1 ,8290    ,463,463,463
BEGIN DESCRIPTION:
GERONIMO TRIBUTARY 2 13.0
END DESCRIPTION:
XS GIS Cut Line= 3
      2311524.99     13762125.01        2311125.       13762525.
        2310825.       13762575.
#Sta/Elev= 30
  4438.4  516.12  4452.5  514.66  4494.9  512.05  4551.5  507.14  4593.9  502.24
  4681.2   497.5  4707.1  493.98  4735.4  489.22  4749.5  496.46  4763.6  497.23
  4834.4  497.99  4862.6  497.14  4876.8  495.05  4890.9  494.12  4905.1  494.65
  4933.4  493.03  4975.8  492.22  4986.5   488.1  4987.2  487.83  4987.6  487.33
  4992.2  487.33  4992.7  487.83  5000.5  498.55  5014.2   499.1  5158.7  499.99
  5166.3   500.5  5237.2  501.49  5247.4   502.4  5280.3  502.36  5308.2  503.26
#Mann= 5 ,-1 , 0
  4438.4     .12       0  4681.2      .1       0  4986.5     .12       0
  4987.2     .05       0  4992.7     .12       0
Bank Sta=4987.2,4992.7
XS Rating Curve= 0 ,0
Exp/Cntr=0.3,0.1

Type RM Length L Ch R = 1 ,7827    ,470,470,470
BEGIN DESCRIPTION:
GERONIMO TRIBUTARY 2 12.0
END DESCRIPTION:
XS GIS Cut Line= 3
      2311125.01     13762024.99        2310975.       13762175.
        2310775.       13762375.
#Sta/Elev= 30
  4787.4  503.65    4791  503.65  4815.7     501    4844  499.77  4858.1  498.98
  4913.7  495.39  4928.8  494.24    4943   494.7  4957.1  494.26  4971.3  493.01
  4985.4   490.4    4996  487.16  5003.1  487.16  5009.9  486.53  5010.4  486.03
  5016.9  486.03  5017.4  486.53  5027.8  492.65    5042  494.03  5056.1  494.11
  5094.9  495.17  5101.6  495.33    5141   496.7  5155.1  498.24  5169.3  498.33
  5230.9  499.76  5245.1  500.34  5268.3  501.57  5278.9  500.83  5282.4  500.83
#Mann= 8 ,-1 , 0
  4787.4     .07       0  4913.7      .1       0  5009.9     .05       0
  5017.4      .1       0  5094.9     .12       0  5101.6     .05       0
  5230.9     .07       0  5245.1     .05       0
Bank Sta=5009.9,5017.4
XS Rating Curve= 0 ,0
Exp/Cntr=0.3,0.1

Type RM Length L Ch R = 1 ,7357    ,193,193,193
BEGIN DESCRIPTION:
GERONIMO TRIBUTARY 2 11.0
END DESCRIPTION:
XS GIS Cut Line= 3
      2310875.02     13761724.98        2310675.       13761875.
      2310524.97     13762025.03
#Sta/Elev= 30
    4755  499.67  4797.7   497.6  4826.9  495.75    4855  494.57  4862.3  493.95
  4891.5  492.92  4941.5  492.34  4951.5  491.79  4952.7   491.7  4968.6   489.1
  4983.2  488.69  4991.5  489.52  4997.7  488.97  5001.9  488.16  5008.6  488.16
  5019.2  486.39  5033.3  486.35  5043.7  484.13  5044.2  483.63  5050.8  483.63
  5051.3  484.13  5061.6  495.74  5075.7  496.96  5087.5  497.19    5104  497.51
  5132.3  497.36  5160.6   497.9  5188.9  499.31    5203  498.88  5217.2  499.03
#Mann= 6 ,-1 , 0
    4755     .07       0  4951.5     .05       0  4952.7     .07       0
  5043.7     .05       0  5051.3     .07       0  5087.5     .05       0
Bank Sta=5043.7,5051.3
XS Rating Curve= 0 ,0
Exp/Cntr=0.3,0.1

Type RM Length L Ch R = 1 ,7164    ,268,268,268
BEGIN DESCRIPTION:
A19026
END DESCRIPTION:
XS GIS Cut Line= 2
      2310908.25     13761426.51       2310291.5      13761966.9
#Sta/Elev= 30
  4559.8  506.97  4567.9  506.61  4582.2  507.33  4596.4  505.75  4653.3  502.33
    4696  500.51  4716.9   500.8  4731.2  499.11  4823.2  495.68  4880.2  491.98
  4949.4  491.14  4964.6  490.67  4972.2  489.21  4978.9  486.03  4986.5  483.25
  4989.3  482.92  4989.8  482.42  4996.4  482.42  4996.9  482.92  5007.3  486.66
  5014.9  491.57  5035.9  494.57  5071.7   495.1  5092.7  494.64  5135.4   495.9
  5262.6  497.69  5291.1  498.93  5297.7  499.89  5326.2  499.29  5379.8  499.93
#Mann= 6 ,-1 , 0
  4559.8     .07       0  4949.4     .05       0  4989.3     .05       0
  4996.9     .05       0  5035.9     .07       0  5071.7     .05       0
Bank Sta=4989.3,4996.9
XS Rating Curve= 0 ,0
Exp/Cntr=0.3,0.1

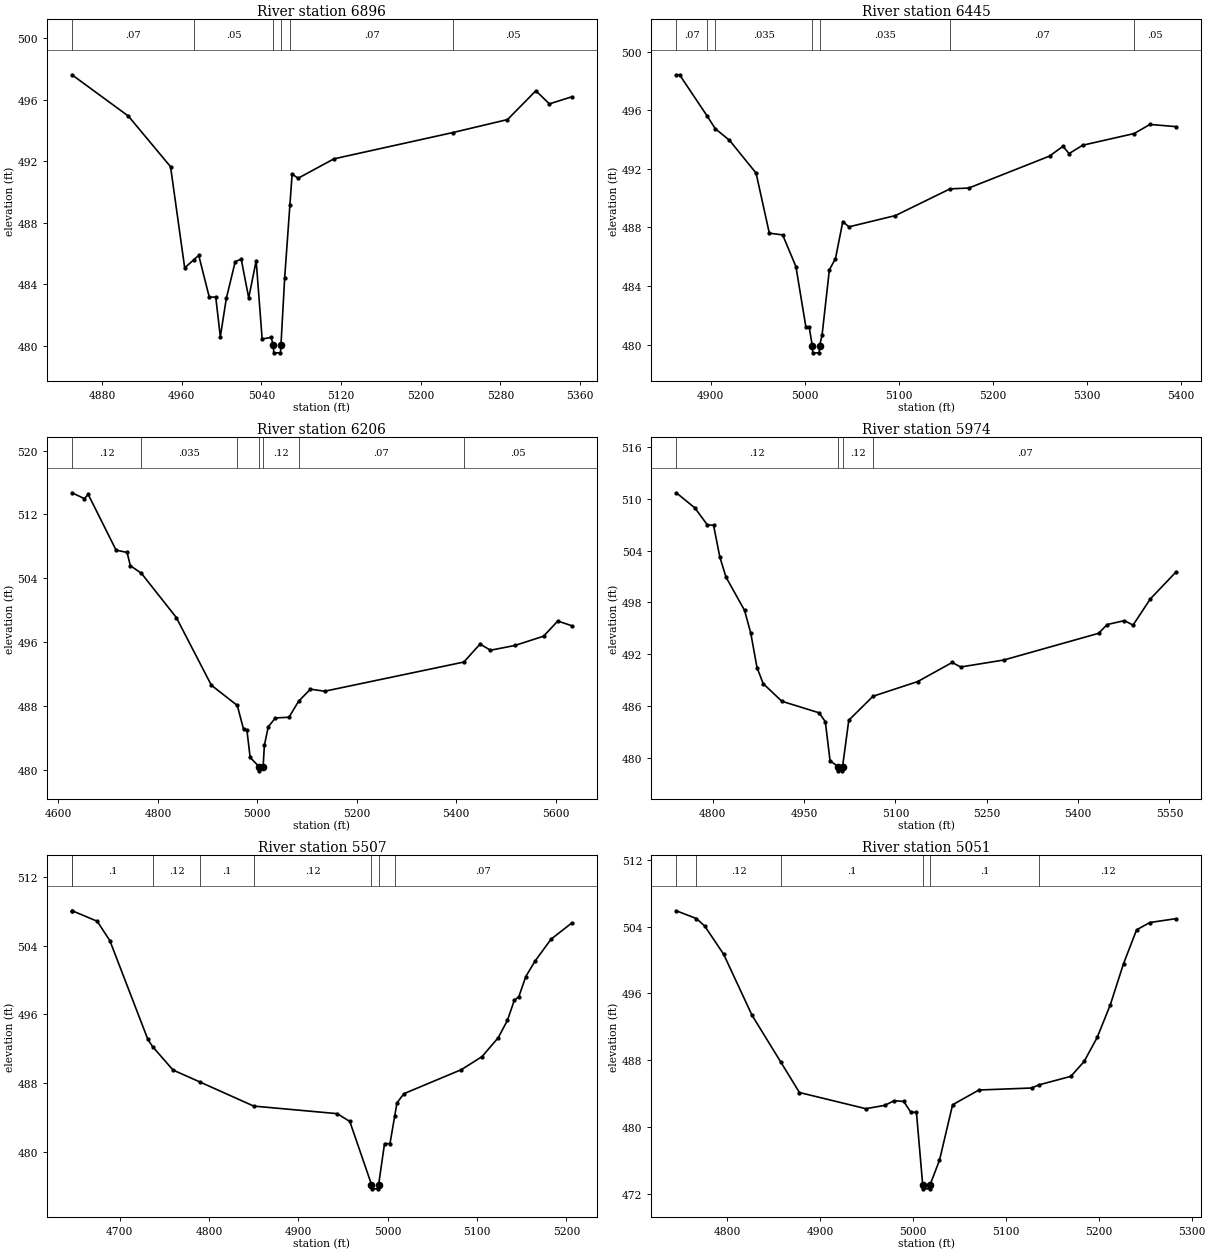
Type RM Length L Ch R = 1 ,6896    ,451,451,451
BEGIN DESCRIPTION:
GERONIMO TRIBUTARY 2 10.0
END DESCRIPTION:
XS GIS Cut Line= 3
      2310675.02     13761374.98        2310575.       13761475.
        2310275.       13761675.
#Sta/Elev= 30
  4849.7  497.62  4906.3  494.94  4948.7  491.65  4962.9  485.08  4971.8  485.59
    4977  485.89  4987.6  483.18  4994.1  483.18  4998.7   480.6  5004.7  483.09
  5013.7  485.49  5019.7  485.64  5027.2  483.13  5034.7  485.54  5040.7  480.46
  5049.7  480.56  5051.9  480.06  5052.4  479.56  5059.1  479.56  5059.6  480.06
  5063.3  484.41  5068.6  489.19  5070.8  491.17  5076.8   490.9  5112.8  492.16
  5232.4  493.87  5287.1  494.71  5315.6  496.58  5329.2  495.73  5351.7  496.19
#Mann= 6 ,-1 , 0
  4849.7     .07       0  4971.8     .05       0  5051.9     .05       0
  5059.6     .05       0  5068.6     .07       0  5232.4     .05       0
Bank Sta=5051.9,5059.6
XS Rating Curve= 0 ,0
Exp/Cntr=0.3,0.1

Type RM Length L Ch R = 1 ,6445    ,239,239,239
BEGIN DESCRIPTION:
GERONIMO TRIBUTARY 2 9.0
END DESCRIPTION:
XS GIS Cut Line= 3
      2310475.01     13761024.99        2310375.       13761125.
      2310125.03     13761424.96
#Sta/Elev= 30
  4863.4  498.42  4866.9  498.42  4896.3   495.6  4904.9  494.74    4920  493.95
  4948.3  491.71  4962.4  487.61  4976.6  487.49  4990.7  485.33  5001.3  481.21
  5004.8  481.21  5008.1  479.94  5008.6  479.44  5015.4  479.44  5015.9  479.94
  5018.5  480.63  5026.3  485.11  5032.8  485.87  5040.6   488.4  5047.1  488.04
  5096.6  488.81  5154.6  490.63  5174.7  490.69  5260.6  492.87  5274.9  493.54
  5281.4  493.04  5295.8  493.61  5350.7  494.41  5367.4  495.03  5395.3  494.88
#Mann= 7 ,-1 , 0
  4863.4     .07       0  4896.3     .12       0  4904.9    .035       0
  5008.1    .035       0  5015.9    .035       0  5154.6     .07       0
  5350.7     .05       0
Bank Sta=5008.1,5015.9
XS Rating Curve= 0 ,0
Exp/Cntr=0.3,0.1

Type RM Length L Ch R = 1 ,6206    ,232,232,232
BEGIN DESCRIPTION:
A19025
END DESCRIPTION:
XS GIS Cut Line= 2
      2310444.21     13760668.85      2309804.04      13761444.1
#Sta/Elev= 30
  4627.2  514.72  4652.1  513.99  4659.9  514.51  4715.9  507.53  4738.1  507.24
  4744.6  505.58  4766.8  504.63  4837.1  499.08  4907.5   490.6  4959.7  488.06
  4972.4  485.05  4979.1  484.97  4985.6  481.54  5003.9  480.36  5004.4  479.86
  5011.7  480.36  5014.2  483.05  5022.1   485.4  5036.4  486.49  5063.7  486.58
  5082.9  488.57  5106.8   490.1  5135.4  489.84  5415.5   493.5  5448.1  495.76
  5468.9  494.98  5518.4  495.58  5575.8  496.74  5604.4  498.64  5632.6  498.05
#Mann= 7 ,-1 , 0
  4627.2     .12       0  4766.8    .035       0  4959.7     .12       0
  5003.9     .05       0  5011.7     .12       0  5082.9     .07       0
  5415.5     .05       0
Bank Sta=5003.9,5011.7
XS Rating Curve= 0 ,0
Exp/Cntr=0.3,0.1

Type RM Length L Ch R = 1 ,5974    ,467,467,467
BEGIN DESCRIPTION:
GERONIMO TRIBUTARY 2 8.0
END DESCRIPTION:
XS GIS Cut Line= 3
      2310074.99     13760575.03        2310025.       13760825.
        2309625.       13761225.
#Sta/Elev= 30
  4740.3  510.69  4770.9  508.93  4791.3  506.97  4801.5  506.93  4811.7  503.27
  4821.8  500.94  4852.4  497.06  4862.6  494.42  4872.8  490.45    4883  488.58
  4913.6  486.54  4974.8   485.2    4985  484.17  4992.7  479.67  5005.4  478.98
  5005.9  478.48  5012.8  478.48  5013.3  478.98  5023.5  484.34  5063.3  487.12
  5136.6  488.82  5193.2  491.03  5207.3  490.51  5278.1  491.32  5433.6  494.41
  5447.8  495.43    5476  495.88  5490.2  495.36  5518.5  498.39  5560.9  501.53
#Mann= 4 ,-1 , 0
  4740.3     .12       0  5005.4     .05       0  5013.3     .12       0
  5063.3     .07       0
Bank Sta=5005.4,5013.3
XS Rating Curve= 0 ,0
Exp/Cntr=0.3,0.1

Type RM Length L Ch R = 1 ,5507    ,456,456,456
BEGIN DESCRIPTION:
GERONIMO TRIBUTARY 2 7.0
END DESCRIPTION:
XS GIS Cut Line= 3
      2309875.01     13760374.99        2309625.       13760625.
      2309425.02       13760675.
#Sta/Elev= 30
  4646.4  508.06  4646.7  508.06  4674.7  506.84  4688.8  504.59  4731.3  493.11
  4736.6  492.26  4759.5  489.53  4790.2  488.11  4849.9  485.33  4943.4  484.45
  4957.5  483.54  4981.8   476.2  4982.3   475.7  4989.3   475.7  4989.8   476.2
  4996.4  480.96  5002.5  480.96  5007.8  484.17  5010.3  485.69    5018  486.77
  5082.4  489.57  5105.6  491.09  5123.7  493.29    5134   495.3  5141.7  497.64
  5146.8  498.07  5154.6  500.41  5164.9   502.2  5182.9  504.76  5206.1  506.64
#Mann= 8 ,-1 , 0
  4646.4     .12       0  4646.7      .1       0  4736.6     .12       0
  4790.2      .1       0  4849.9     .12       0  4981.8     .05       0
  4989.8     .12       0  5007.8     .07       0
Bank Sta=4981.8,4989.8
XS Rating Curve= 0 ,0
Exp/Cntr=0.3,0.1

Type RM Length L Ch R = 1 ,5051    ,493,493,493
BEGIN DESCRIPTION:
GERONIMO TRIBUTARY 2 6.0
END DESCRIPTION:
XS GIS Cut Line= 3
      2309724.96     13760175.01        2309475.       13760225.
      2309274.97     13760425.03
#Sta/Elev= 30
  4745.5   505.9  4767.1  504.97  4776.1  504.07  4796.4   500.7    4827  493.37
    4858  487.75    4878  484.11  4949.4  482.17  4969.8  482.57    4980  483.13
  4990.2  483.04  4997.9  481.74  5003.9  481.74  5010.6  473.06  5011.1  472.56
  5018.1  472.56  5018.6  473.06  5028.7  475.99  5042.8  482.64  5071.1  484.41
  5127.7  484.65  5136.2  485.04  5170.1  486.05  5184.3  487.83  5198.4  490.72
  5212.5  494.63  5226.7  499.56  5240.8  503.62    5255  504.49  5283.3  504.96
#Mann= 6 ,-1 , 0
  4745.5      .1       0  4767.1     .12       0    4858      .1       0
  5010.6     .05       0  5018.6      .1       0  5136.2     .12       0
Bank Sta=5010.6,5018.6
XS Rating Curve= 0 ,0
Exp/Cntr=0.3,0.1