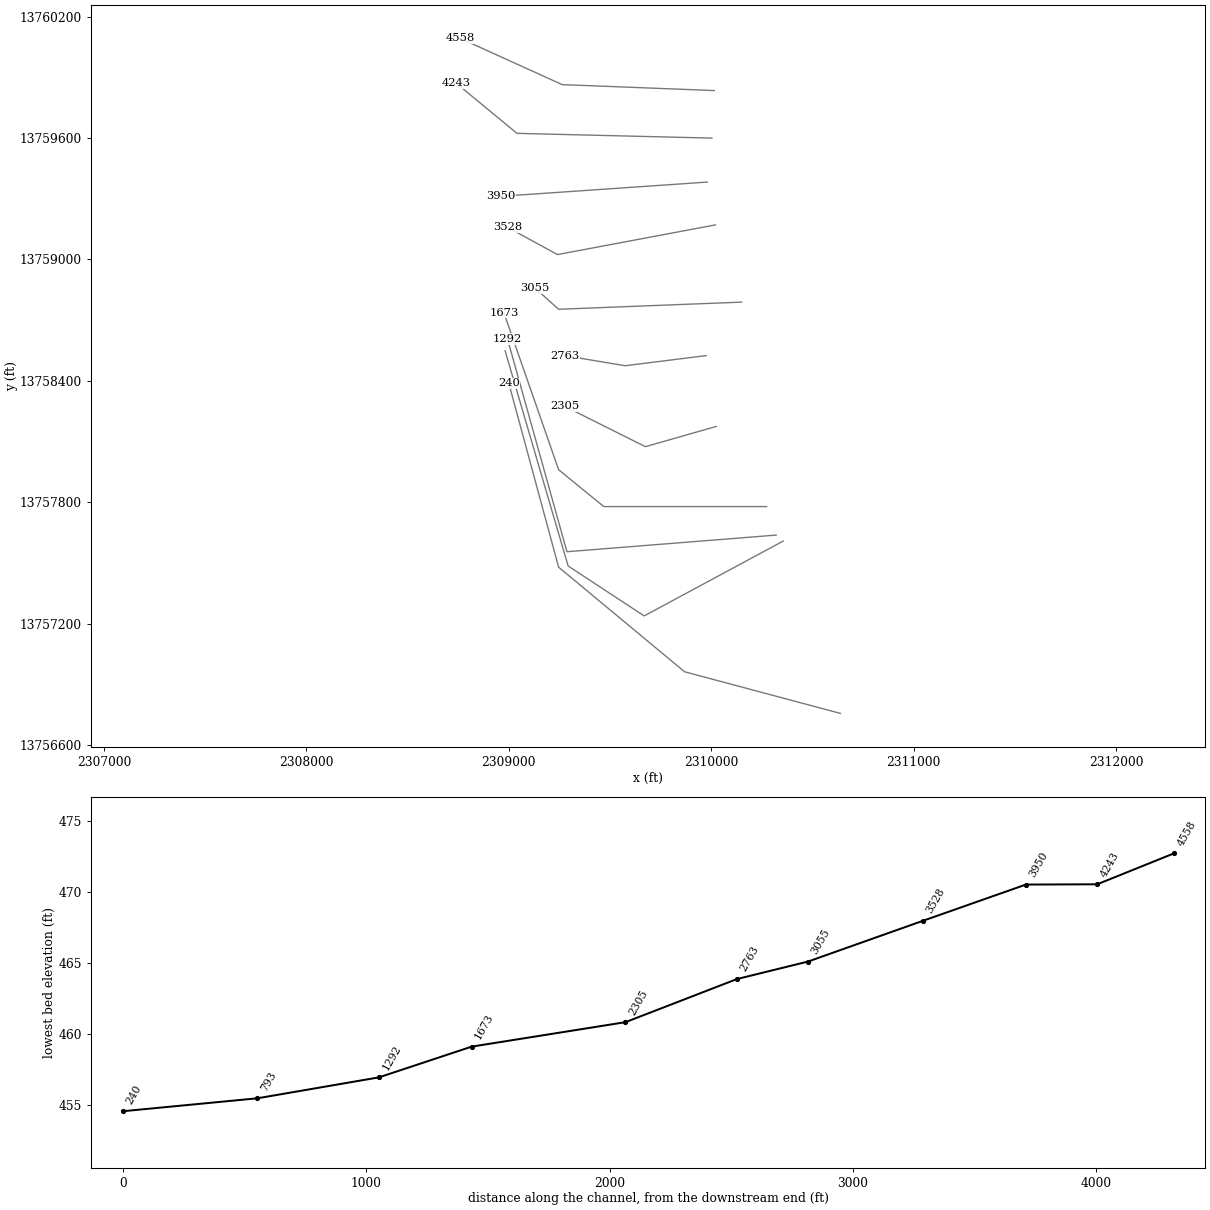
HEC-RAS study GERONIMO TRIBUTARY 2.prj: GERONIMO TRIBUTARY 2 Base Level Engineering

--- GERONIMO TRIBUTARY 2.g01 (geometry) --- (continued)

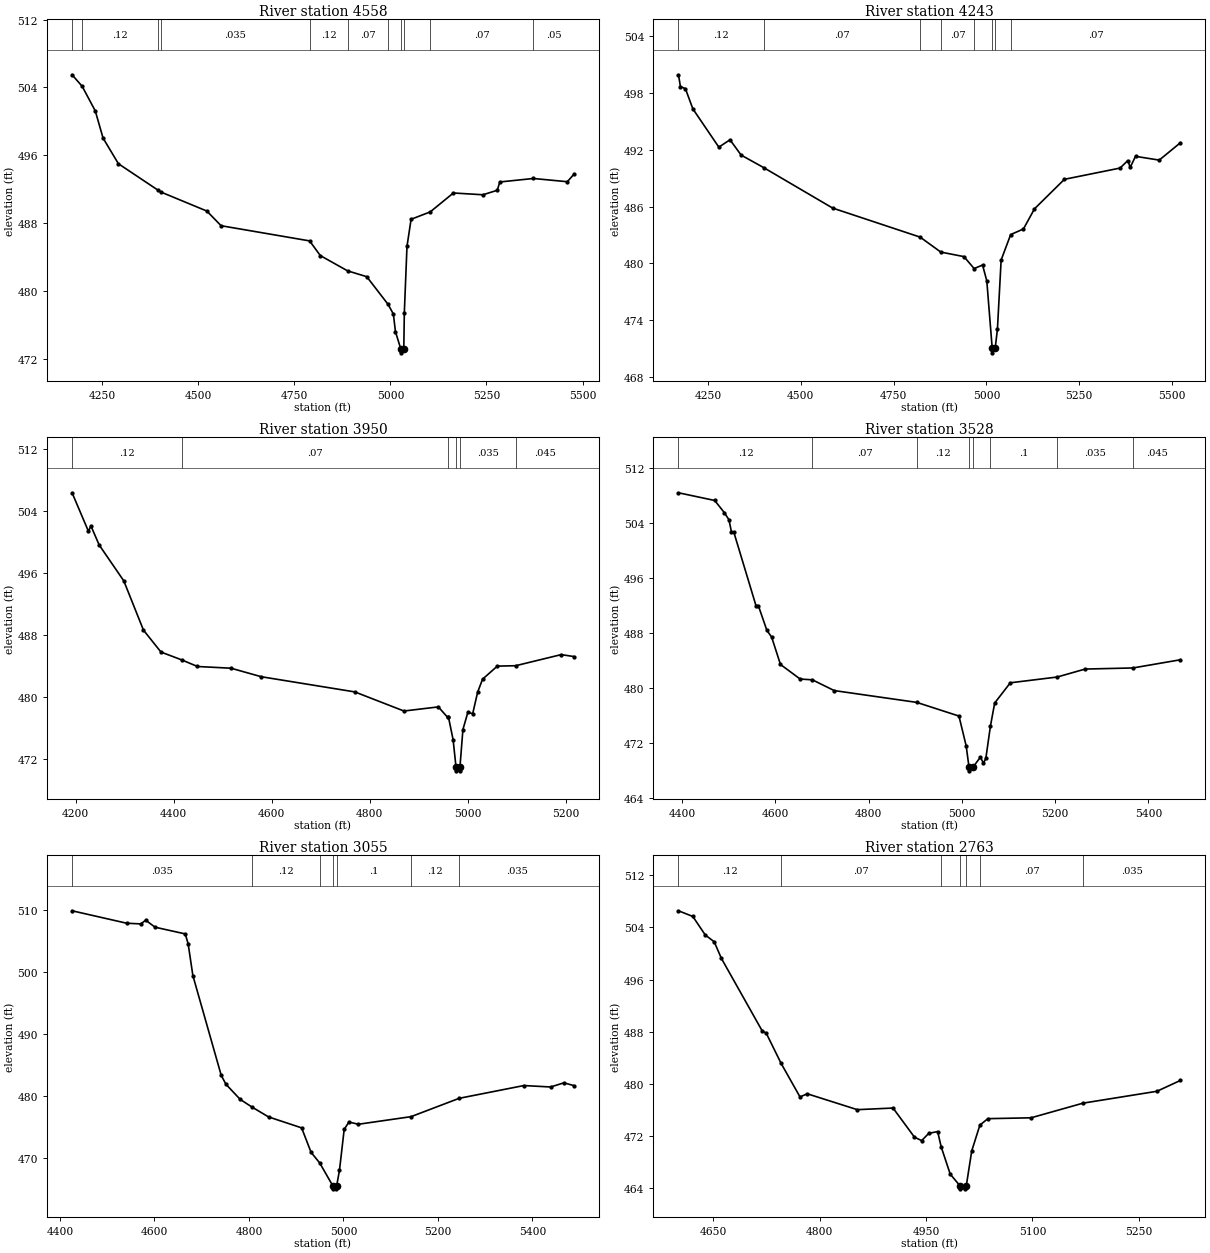
Type RM Length L Ch R = 1 ,4558    ,315,315,315
BEGIN DESCRIPTION:
A19024
END DESCRIPTION:
XS GIS Cut Line= 3
      2310015.49     13759834.78      2309263.65     13759864.15
       2308759.3     13760092.86
#Sta/Elev= 30
  4171.4   505.5  4197.7  504.14  4231.9  501.23    4252  498.04    4292  495.01
  4395.5  491.88  4402.2  491.68  4522.2  489.43  4559.3   487.7  4789.7  485.91
  4817.5  484.18  4888.4  482.38  4938.4  481.69    4994  478.42  5007.7  477.28
  5013.1   475.2  5026.7  473.21  5027.2  472.71  5034.8  473.21  5036.2  477.44
  5043.1  485.26  5053.8  488.46  5103.6  489.33  5163.9  491.56  5240.8  491.35
  5278.1  491.88  5284.7  492.86    5372  493.27  5460.4  492.89  5477.6  493.77
#Mann= 11 ,-1 , 0
  4171.4     .07       0  4197.7     .12       0  4395.5     .07       0
  4402.2    .035       0  4789.7     .12       0  4888.4     .07       0
    4994    .035       0  5026.7    .035       0  5034.8    .035       0
  5103.6     .07       0    5372     .05       0
Bank Sta=5026.7,5034.8
XS Rating Curve= 0 ,0
Exp/Cntr=0.3,0.1

Type RM Length L Ch R = 1 ,4243    ,293,293,293
BEGIN DESCRIPTION:
A19023
END DESCRIPTION:
XS GIS Cut Line= 3
      2310003.71     13759599.84      2309040.45     13759623.33
       2308740.9     13759870.02
#Sta/Elev= 30
  4170.7  499.93  4175.9  498.69  4189.4  498.46  4209.4  496.33  4279.4  492.28
  4309.5  493.06  4339.5  491.44  4400.1  490.12    4586  485.84  4821.6  482.77
  4877.2  481.19  4939.6  480.71  4966.9  479.45  4989.7  479.82  5001.1  478.14
  5015.6  471.04  5016.1  470.54  5023.7  471.04  5029.7  473.02  5039.7  480.35
  5065.4  483.04  5099.7  483.63  5129.5  485.76  5210.1  488.88    5360  490.07
  5380.8  490.86  5387.4  490.15  5401.6  491.31  5465.5  490.91  5522.3  492.74
#Mann= 8 ,-1 , 0
  4170.7     .12       0  4400.1     .07       0  4821.6    .035       0
  4877.2     .07       0  4966.9    .035       0  5015.6    .035       0
  5023.7    .035       0  5065.4     .07       0
Bank Sta=5015.6,5023.7
XS Rating Curve= 0 ,0
Exp/Cntr=0.3,0.1

Type RM Length L Ch R = 1 ,3950    ,422,422,422
BEGIN DESCRIPTION:
A19022
END DESCRIPTION:
XS GIS Cut Line= 2
      2309980.21     13759382.52      2308959.14      13759312.1
#Sta/Elev= 30
  4192.8  506.31  4226.2  501.35  4231.2  502.05  4248.1  499.59  4298.3  494.97
  4338.4  488.63  4374.1  485.81  4416.4   484.8  4448.6  483.95  4516.9  483.73
  4578.9  482.63  4769.4  480.68  4869.6  478.22  4939.8  478.75  4958.5  477.42
  4960.5  477.42  4969.9  474.53  4975.8  471.02  4976.3  470.52  4983.4  470.52
  4983.9  471.02  4989.9  475.83  4999.9  478.03  5009.9  477.89    5020  480.66
    5030  482.32  5060.1     484  5097.4  484.05  5190.4  485.48  5216.3  485.23
#Mann= 6 ,-1 , 0
  4192.8     .12       0  4416.4     .07       0  4958.5    .035       0
  4975.8    .035       0  4983.9    .035       0  5097.4    .045       0
Bank Sta=4975.8,4983.9
XS Rating Curve= 0 ,0
Exp/Cntr=0.3,0.1

Type RM Length L Ch R = 1 ,3528    ,473,473,473
BEGIN DESCRIPTION:
A19021
END DESCRIPTION:
XS GIS Cut Line= 3
      2310021.38     13759171.08      2309240.15     13759024.23
      2308993.43     13759159.34
#Sta/Elev= 30
  4392.4  508.44  4470.1  507.32  4490.5  505.57  4500.6  504.52  4506.1  502.73
  4511.2  502.68  4558.6  492.02  4563.7  492.01    4582  488.42  4592.2  487.44
  4611.1  483.46  4653.3  481.34  4679.6  481.22  4726.3  479.66  4903.4  477.94
  4993.9  475.95  5009.4   471.6  5015.5  468.48    5016  467.98  5023.6  468.48
  5039.9  469.97  5046.4  469.09  5051.5  469.78  5061.4   474.5  5070.5  477.85
    5104  480.79  5204.5  481.63  5264.5  482.79    5367  482.95  5468.6  484.14
#Mann= 8 ,-1 , 0
  4392.4     .12       0  4679.6     .07       0  4903.4     .12       0
  5015.5     .05       0  5023.6     .12       0  5061.4      .1       0
  5204.5    .035       0    5367    .045       0
Bank Sta=5015.5,5023.6
XS Rating Curve= 0 ,0
Exp/Cntr=0.3,0.1

Type RM Length L Ch R = 1 ,3055    ,292,292,292
BEGIN DESCRIPTION:
A19020
END DESCRIPTION:
XS GIS Cut Line= 3
      2310150.55     13758789.29      2309246.03     13758754.04
      2309129.26     13758859.13
#Sta/Elev= 30
  4425.6   509.8  4541.2   507.8  4571.3  507.69  4581.3  508.29  4601.3  507.16
  4665.2  506.08  4671.3  504.49  4681.3  499.39  4741.4  483.33  4751.4  481.91
  4781.4  479.49  4806.5  478.25  4841.5  476.67  4911.5  474.91  4931.5  470.98
  4949.8  469.27  4977.4  465.61  4977.9  465.11  4985.2  465.11  4985.7  465.61
  4991.6  468.07  5001.6  474.66  5011.6  475.85  5031.6  475.49  5143.1  476.71
  5245.1  479.66  5381.9  481.71  5438.7  481.48  5466.7  482.15  5487.9   481.7
#Mann= 7 ,-1 , 0
  4425.6    .035       0  4806.5     .12       0  4949.8      .1       0
  4977.4     .05       0  4985.7      .1       0  5143.1     .12       0
  5245.1    .035       0
Bank Sta=4977.4,4985.7
XS Rating Curve= 0 ,0
Exp/Cntr=0.3,0.1

Type RM Length L Ch R = 1 ,2763    ,458,458,458
BEGIN DESCRIPTION:
GERONIMO TRIBUTARY 2 3.0
END DESCRIPTION:
XS GIS Cut Line= 3
      2309975.02       13758525.        2309575.       13758475.
      2309274.97     13758525.01
#Sta/Elev= 30
  4601.2  506.55  4621.4  505.68    4639  502.83  4651.6  501.79  4661.7  499.24
  4719.6  488.04  4724.7  487.81  4745.9  483.12  4772.5  477.98  4782.6  478.47
  4853.2  476.03  4903.6  476.28  4933.8  471.81  4943.9  471.28  4953.9  472.39
  4966.5  472.67  4971.4  470.34  4984.2  466.14  4997.7  464.38  4998.2  463.88
  5005.5  463.88    5006  464.38  5006.9  464.38  5014.5  469.69    5026  473.66
  5037.3  474.65  5098.1  474.78  5171.4  477.03  5275.5  478.85  5308.5  480.51
#Mann= 7 ,-1 , 0
  4601.2     .12       0  4745.9     .07       0  4971.4     .12       0
  4997.7     .05       0    5006     .12       0    5026     .07       0
  5171.4    .035       0
Bank Sta=4997.7,5006
XS Rating Curve= 0 ,0
Exp/Cntr=0.3,0.1

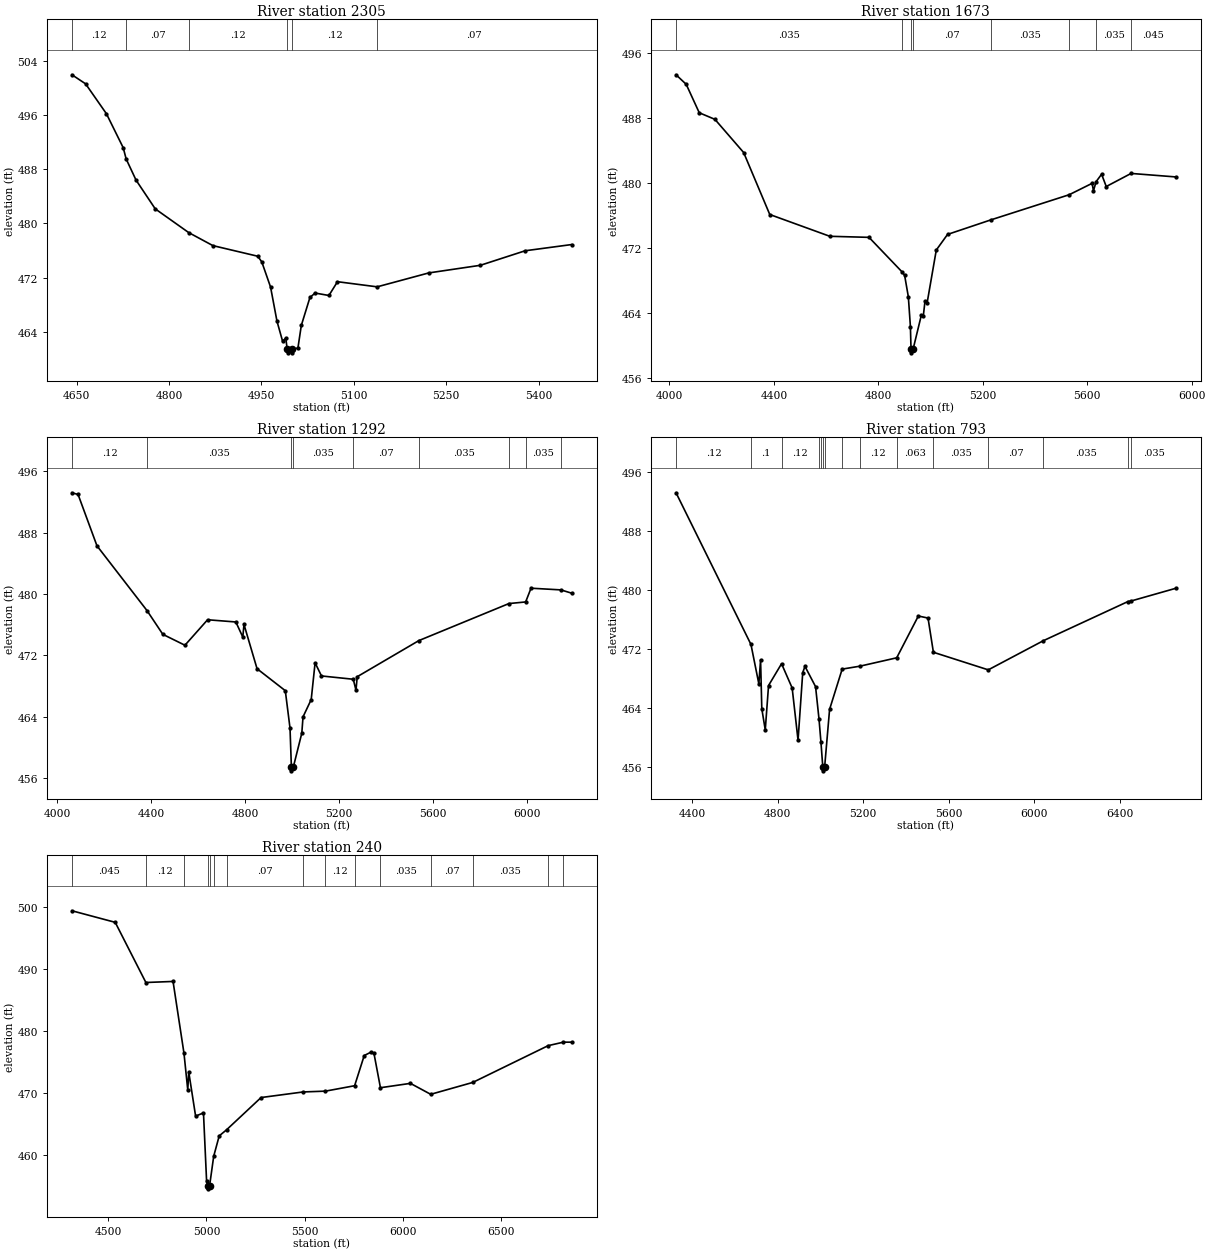
Type RM Length L Ch R = 1 ,2305    ,632,632,632
BEGIN DESCRIPTION:
GERONIMO TRIBUTARY 2 2.0
END DESCRIPTION:
XS GIS Cut Line= 3
      2310024.96     13758174.99        2309675.       13758075.
      2309274.98     13758275.01
#Sta/Elev= 30
  4642.4  502.01  4664.5  500.67  4698.3  496.25  4725.6  491.21  4730.4  489.54
  4746.4  486.42  4777.6  482.16  4831.9  478.65  4871.2  476.72    4944  475.15
  4950.5  474.32  4964.8  470.58  4975.2  465.53  4984.3  462.57  4989.5  463.04
  4991.8  461.35  4992.3  460.85  4999.7  460.85  5000.2  461.35  5009.2  461.57
  5014.7  464.91  5028.7  469.05  5037.1   469.7  5059.5  469.34  5073.4  471.38
  5137.8  470.62  5221.6  472.68  5305.4  473.81  5378.1  475.96  5453.6  476.88
#Mann= 6 ,-1 , 0
  4642.4     .12       0  4730.4     .07       0  4831.9     .12       0
  4991.8     .05       0  5000.2     .12       0  5137.8     .07       0
Bank Sta=4991.8,5000.2
XS Rating Curve= 0 ,0
Exp/Cntr=0.3,0.1

Type RM Length L Ch R = 1 ,1673    ,381,381,381
BEGIN DESCRIPTION:
A19019
END DESCRIPTION:
XS GIS Cut Line= 4
      2310273.86     13757779.03      2309469.22     13757779.03
      2309246.03     13757961.11      2308975.85      13758736.4
#Sta/Elev= 30
  4025.5  493.32  4064.4  492.15  4114.4  488.65  4174.4  487.84  4284.4  483.76
  4384.4  476.14  4614.4  473.46  4764.4  473.33  4890.2  469.11  4900.8  468.67
  4915.1  466.02    4923  462.36  4925.3  459.63  4925.8  459.13  4933.7  459.63
  4964.7  463.74  4972.6  463.72    4979  465.51  4986.9  465.25  5022.1  471.77
  5065.2  473.69  5230.3  475.47    5531  478.57  5618.7  479.97    5624  479.06
  5634.2  480.18  5655.1  481.09    5673  479.58  5768.1  481.19  5939.2  480.76
#Mann= 8 ,-1 , 0
  4025.5    .035       0  4890.2     .07       0  4925.3     .05       0
  4933.7     .07       0  5230.3    .035       0    5531     .07       0
  5634.2    .035       0  5768.1    .045       0
Bank Sta=4925.3,4933.7
XS Rating Curve= 0 ,0
Exp/Cntr=0.3,0.1

Type RM Length L Ch R = 1 ,1292    ,499,499,499
BEGIN DESCRIPTION:
A19018
END DESCRIPTION:
XS GIS Cut Line= 3
      2310320.87     13757638.07      2309287.14     13757555.84
      2308993.47     13758607.19
#Sta/Elev= 30
  4062.7  493.19  4088.7  492.97  4169.2  486.28  4382.2  477.85  4449.8  474.75
  4543.9  473.33  4640.4  476.65  4760.8  476.36  4790.4  474.39  4795.4  476.04
  4851.1  470.27  4971.4  467.41  4991.5  462.53  4997.3  457.47  4997.8  456.97
  5005.7  457.47  5041.7  461.88  5046.9     464  5081.8  466.26  5098.3  471.04
  5125.5  469.33  5260.9   468.9  5272.5  467.47  5277.7  469.23  5540.6  473.94
  5923.9  478.76  5995.2  478.97    6018  480.76  6145.3  480.54  6191.3  480.11
#Mann= 9 ,-1 , 0
  4062.7     .12       0  4382.2    .035       0  4997.3    .035       0
  5005.7    .035       0  5260.9     .07       0  5540.6    .035       0
  5923.9     .07       0  5995.2    .035       0  6145.3    .045       0
Bank Sta=4997.3,5005.7
XS Rating Curve= 0 ,0
Exp/Cntr=0.3,0.1

Type RM Length L Ch R = 1 ,793     ,553,553,553
BEGIN DESCRIPTION:
A19017
END DESCRIPTION:
XS GIS Cut Line= 4
      2310356.11     13757608.69      2309668.92     13757238.66
      2309293.01     13757485.35       2308981.7     13758548.51
#Sta/Elev= 30
  4324.7  493.14  4675.2  472.61  4712.1  467.27  4720.2  470.53  4725.9  463.91
  4742.1  461.04  4757.5  467.05  4818.3     470  4867.9  466.72  4895.5  459.64
  4917.4   468.8  4927.9  469.64  4977.4   466.9  4993.6   462.5  5002.7  459.35
  5011.3     456  5011.8   455.5  5019.8     456  5043.1  463.83  5101.9  469.27
  5185.3  469.67    5357   470.8  5458.3  476.46  5503.6  476.18  5528.7  471.55
  5785.4  469.17  6042.7  473.11  6438.4  478.41  6454.6   478.5  6662.6  480.21
#Mann= 15 ,-1 , 0
  4324.7     .12       0  4675.2      .1       0  4818.3     .12       0
  4993.6      .1       0  5002.7     .12       0  5011.3     .05       0
  5019.8     .12       0  5101.9     .07       0  5185.3     .12       0
    5357    .063       0  5528.7    .035       0  5785.4     .07       0
  6042.7    .035       0  6438.4     .07       0  6454.6    .035       0
Bank Sta=5011.3,5019.8
XS Rating Curve= 0 ,0
Exp/Cntr=0.3,0.1

Type RM Length L Ch R = 1 ,240     ,0,0,0
BEGIN DESCRIPTION:
A19016
END DESCRIPTION:
XS GIS Cut Line= 4
      2310638.02     13756757.04      2309868.62     13756962.61
      2309246.03     13757479.48      2308999.68     13758388.62
#Sta/Elev= 30
  4314.2  499.33  4534.7  497.47    4691  487.79  4829.5  487.96  4885.2  476.41
  4904.5  470.52  4909.6  473.37  4944.5  466.29  4984.6  466.81  5000.5  455.84
  5005.8  455.09  5006.3  454.59  5015.8  455.09  5036.8  459.84  5064.8  463.11
    5102  464.08  5278.2  469.28  5493.1  470.18  5606.3  470.31  5755.1  471.18
  5804.1  476.04  5839.5   476.6  5853.8  476.37  5886.7  470.86  6039.5  471.56
    6143   469.8  6357.3  471.71  6741.7  477.63  6819.6  478.19  6861.7  478.19
#Mann= 15 ,-1 , 0
  4314.2    .045       0    4691     .12       0  4885.2      .1       0
  5005.8     .05       0  5015.8      .1       0  5036.8     .12       0
    5102     .07       0  5493.1    .035       0  5606.3     .12       0
  5755.1    .063       0  5886.7    .035       0    6143     .07       0
  6357.3    .035       0  6741.7     .07       0  6819.6    .035       0
Bank Sta=5005.8,5015.8
XS Rating Curve= 0 ,0
Exp/Cntr=0.3,0.1

Chan Stop Cuts=-1
Use User Specified Reach Order=0
Composite Channel Slope=5