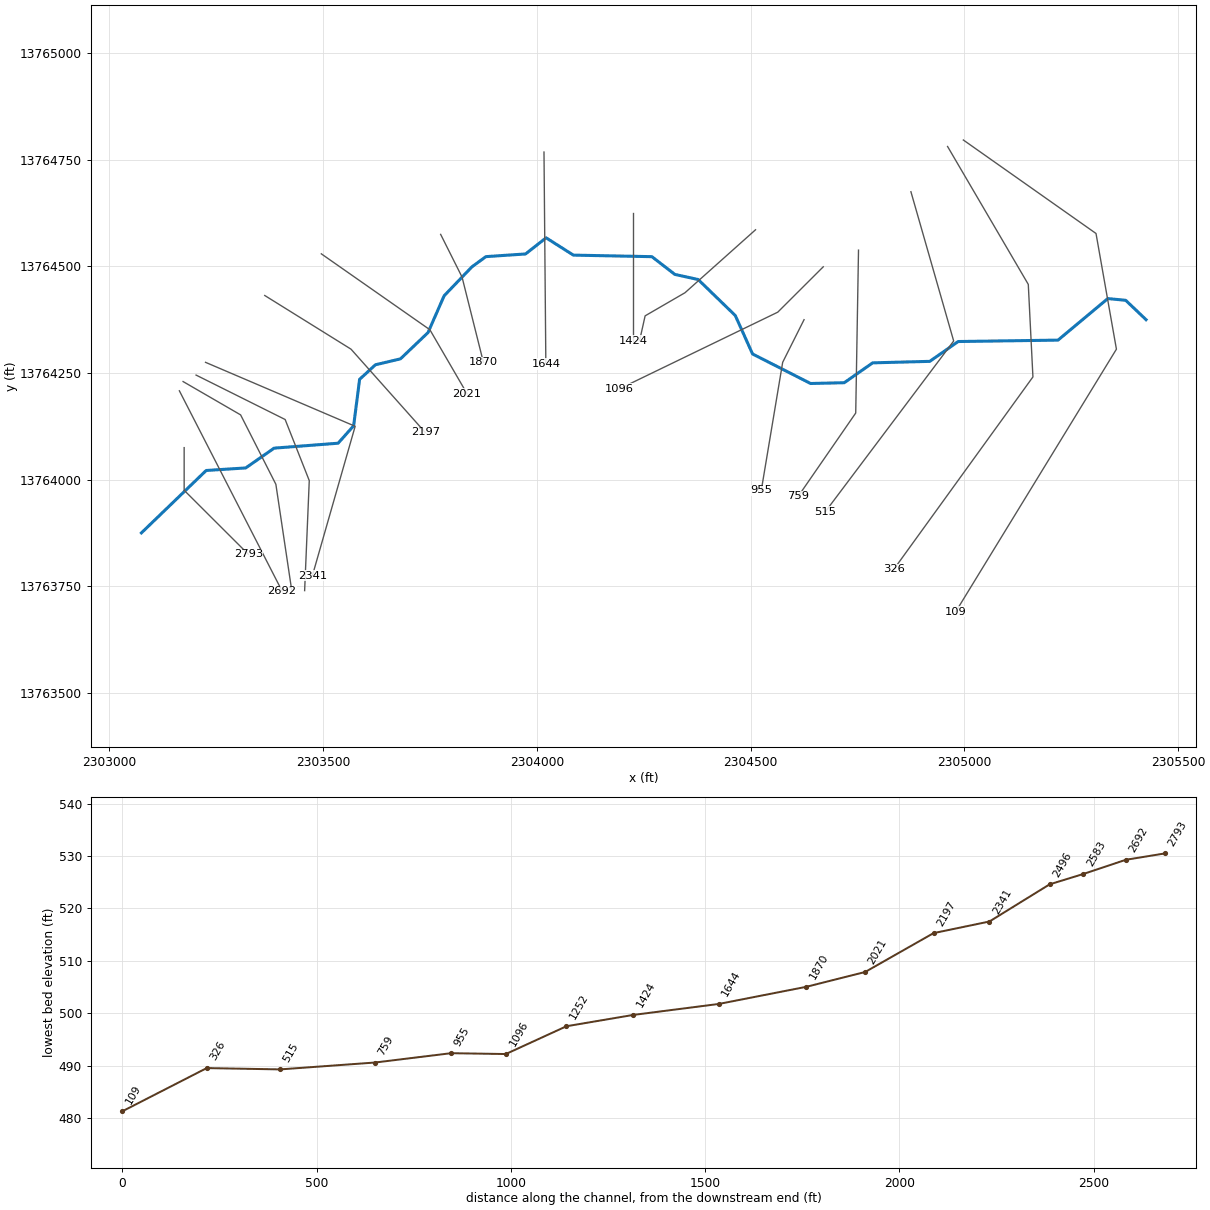
--- GERONIMO TRIBUTARY 4.prj (project) ---

Proj Title=GERONIMO TRIBUTARY 4 Base Level Engineering
Current Plan=p01
Default Exp/Contr=0.3,0.1
English Units
Geom File=g01
Flow File=f01
Plan File=p01
Y Axis Title=Elevation
X Axis Title(PF)=Main Channel Distance
X Axis Title(XS)=Station
BEGIN DESCRIPTION:
GERONIMO TRIBUTARY 4
END DESCRIPTION:
DSS Export Rating Curves= 0
DSS Export Rating Curve Sorted= 0
DSS Export Volume Flow Curves= 0
DXF OffsetX= 0
DXF OffsetY= 0
DXF ScaleX= 1
DXF ScaleY= 10

--- GERONIMO TRIBUTARY 4.p01 (plan) ---

Plan Title=Multiple Run
Short Identifier=Multiple
Geom File=g01
Flow File=f01
Subcritical Flow
K Sum by GR= 0
Std Step Tol= 0.01
Critical Tol= 0.01
Num of Std Step Trials= 20
Max Error Tol= 0.3
Flow Tol Ratio= 0.001
Split Flow NTrial= 30
Split Flow Tol= 0.02
Split Flow Ratio= 0.02
Log Output Level= 0
Friction Slope Method= 1
Unsteady Friction Slope Method= 2
Unsteady Bridges Friction Slope Method= 1
Parabolic Critical Depth
Global Vel Dist=  1 , 1 , 1
Global Log Level= 0
CheckData=True
Encroach Param= -1, 0, 0, 0
BEGIN DESCRIPTION:
Multiple Run
END DESCRIPTION:

--- GERONIMO TRIBUTARY 4.f01 (steady flow) ---

Flow Title=Multiple
Number of Profiles=7
Profile Names=10-year,25-year,50-year,1pct_min,100-year,1pct_plu,500-year
River Rch & RM= GERONIMO TRIBUTA,Reach-1,2793
     442     682     888     559    1115    2224    1742
River Rch & RM= GERONIMO TRIBUTA,Reach-1,2692
     735    1181    1581    1022    2040    4071    3370
Boundary for River Rch & Prof#=GERONIMO TRIBUTA,Reach-1,1
Up Type=0
Dn Type=3
Dn Slope=0.005
Boundary for River Rch & Prof#=GERONIMO TRIBUTA,Reach-1,2
Up Type=0
Dn Type=3
Dn Slope=0.005
Boundary for River Rch & Prof#=GERONIMO TRIBUTA,Reach-1,3
Up Type=0
Dn Type=3
Dn Slope=0.005
Boundary for River Rch & Prof#=GERONIMO TRIBUTA,Reach-1,4
Up Type=0
Dn Type=3
Dn Slope=0.005
Boundary for River Rch & Prof#=GERONIMO TRIBUTA,Reach-1,5
Up Type=0
Dn Type=3
Dn Slope=0.005
Boundary for River Rch & Prof#=GERONIMO TRIBUTA,Reach-1,6
Up Type=0
Dn Type=3
Dn Slope=0.005
Boundary for River Rch & Prof#=GERONIMO TRIBUTA,Reach-1,7
Up Type=0
Dn Type=3
Dn Slope=0.005

--- GERONIMO TRIBUTARY 4.g01 (geometry) ---

Geom Title=Existing Conditions
Program Version=4.10

River Reach=GERONIMO TRIBUTA,Reach-1
Reach XY= 30
        2303075.       13763875.      2303226.49     13764021.39
      2303319.02     13764027.36      2303385.51     13764073.77
      2303535.17     13764085.33      2303571.49     13764126.25
      2303585.39      13764235.1      2303622.43     13764269.26
      2303681.04     13764283.16      2303745.42     13764344.77
      2303783.15     13764431.07      2303848.07     13764498.85
      2303880.88     13764522.86       2303973.5     13764529.09
       2304021.7     13764566.92      2304085.44     13764526.38
      2304269.07     13764522.76      2304322.83     13764481.14
      2304377.31     13764469.18      2304464.22     13764384.68
      2304504.53     13764294.62      2304640.27     13764225.37
      2304719.02     13764227.17      2304785.51     13764273.77
      2304919.06     13764277.27       2304985.5     13764323.78
      2305219.14     13764327.07      2305335.55      13764424.5
      2305377.35     13764420.43        2305425.       13764375.

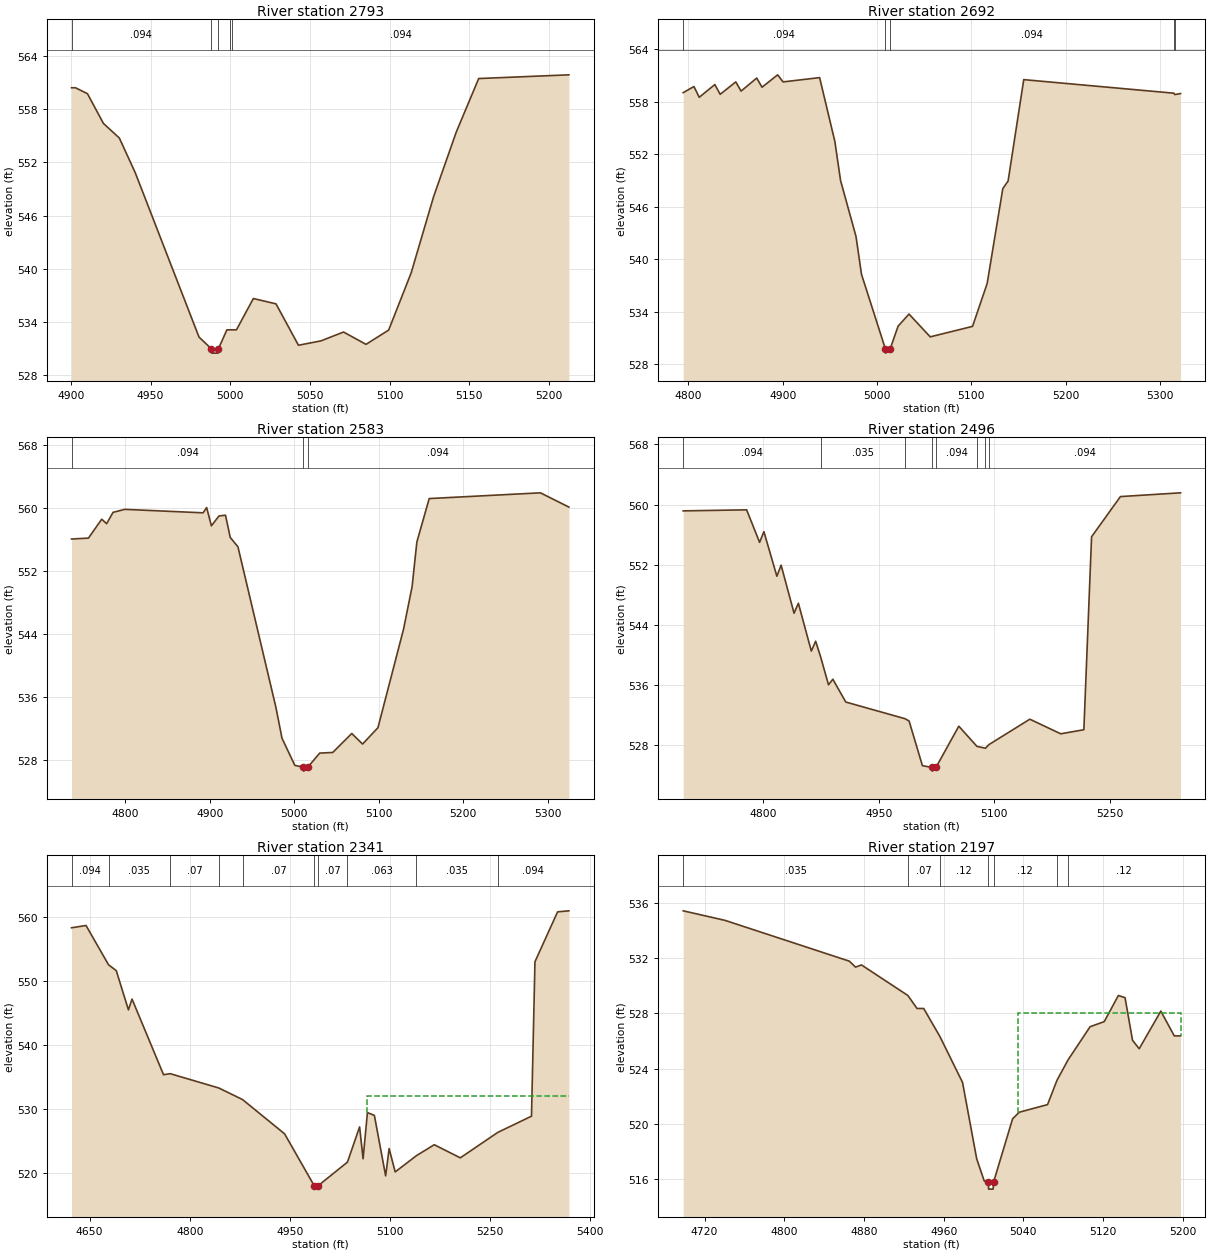
Type RM Length L Ch R = 1 ,2793    ,101,101,101
BEGIN DESCRIPTION:
GERONIMO TRIBUTARY 4 6.0
END DESCRIPTION:
XS GIS Cut Line= 3
        2303175.     13764074.97        2303175.       13763975.
        2303325.       13763825.
#Sta/Elev= 28
  4900.4  560.43  4902.9  560.43  4910.4  559.76  4920.4  556.41  4930.4  554.76
  4940.4  550.84  4980.4   532.3  4988.1  530.99  4988.4  530.49  4992.3  530.49
  4992.6  530.99  4997.9  533.12  4999.8  533.12  5000.4  533.12  5001.4  533.12
  5003.9  533.12  5014.5  536.65  5028.7  536.05  5042.8  531.38  5056.9  531.87
  5071.1  532.87  5085.2  531.48  5099.4  533.09  5113.5  539.53  5127.6  548.14
  5141.8  555.42  5155.9  561.47  5212.5  561.89
#Mann= 5 ,-1 , 0
  4900.4    .094       0  4988.1     .05       0  4992.6    .094       0
  4999.8     .07       0  5001.4    .094       0
Bank Sta=4988.1,4992.6
XS Rating Curve= 0 ,0
Exp/Cntr=0.3,0.1

Type RM Length L Ch R = 1 ,2692    ,109,109,109
BEGIN DESCRIPTION:
A19043
END DESCRIPTION:
XS GIS Cut Line= 2
      2303163.83     13764208.23      2303404.06      13763738.6
#Sta/Elev= 30
  4794.4  559.06  4805.8  559.76  4811.4  558.53    4828  559.99  4833.6  558.87
  4850.2  560.29  4855.8  559.24  4872.4  560.73    4878  559.68  4894.6   561.1
  4900.3  560.29  4939.1  560.78  4955.3  553.46  4961.3  549.02  4977.7  542.61
  4983.5  538.29  5008.8  529.77  5009.2  529.27    5014  529.77  5022.3  532.35
  5033.9  533.74  5056.4  531.13  5101.3  532.33  5116.8  537.24  5133.4  548.09
    5139  548.95  5155.6  560.55  5314.8     559  5315.8  558.84  5321.9  558.96
#Mann= 5 ,-1 , 0
  4794.4    .094       0  5008.8     .05       0    5014    .094       0
  5314.8     .07       0  5315.8    .094       0
Bank Sta=5008.8,5014
XS Rating Curve= 0 ,0
Exp/Cntr=0.3,0.1

Type RM Length L Ch R = 1 ,2583    ,87,87,87
BEGIN DESCRIPTION:
A19042
END DESCRIPTION:
XS GIS Cut Line= 4
       2303172.5     13764229.91      2303307.07     13764151.78
      2303389.54     13763989.02      2303426.43     13763741.62
#Sta/Elev= 30
  4736.6  556.05  4756.6  556.17  4772.3  558.57  4778.1     558  4785.7  559.44
  4799.6  559.82  4892.2  559.38  4896.4  560.05    4902  557.73    4911  558.98
  4918.7  559.08  4924.3  556.25  4933.4  555.07  4978.3  534.68  4985.5  530.75
  5000.7   527.3  5010.8  527.07  5011.2  526.57    5016  527.07  5030.1  528.86
  5045.5  528.94    5068  531.35  5080.8  530.01    5099  532.09  5129.3  544.62
  5139.4  550.02    5145  555.67  5159.6  561.19  5291.1  561.92  5324.8  560.11
#Mann= 3 ,-1 , 0
  4736.6    .094       0  5010.8     .05       0    5016    .094       0
Bank Sta=5010.8,5016
XS Rating Curve= 0 ,0
Exp/Cntr=0.3,0.1

Type RM Length L Ch R = 1 ,2496    ,155,155,155
BEGIN DESCRIPTION:
A19041
END DESCRIPTION:
XS GIS Cut Line= 4
      2303202.91     13764245.09      2303411.24     13764140.93
      2303467.66      13763997.7      2303456.82     13763739.69
#Sta/Elev= 30
  4696.4  559.17  4778.7  559.31  4795.5  554.99  4801.1  556.41  4817.9  550.49
  4823.4  551.96  4840.2  545.57  4845.8   546.9  4862.6  540.54  4868.2  541.85
  4874.5  539.83  4884.9  536.06  4890.5   536.8  4907.3  533.77  4984.3  531.55
  4989.4  531.25  5006.7  525.31  5019.1  525.09  5019.5  524.59  5024.3  525.09
  5053.9  530.56  5077.4  527.88  5088.5  527.63  5092.9  528.11    5146  531.49
  5186.1  529.55  5216.1  530.09  5226.1  555.73  5263.5  561.07  5341.5  561.57
#Mann= 8 ,-1 , 0
  4696.4    .094       0  4874.5    .035       0  4984.3    .094       0
  5019.1     .05       0  5024.3    .094       0  5077.4    .063       0
  5088.5    .035       0  5092.9    .094       0
Bank Sta=5019.1,5024.3
XS Rating Curve= 0 ,0
Exp/Cntr=0.3,0.1

Type RM Length L Ch R = 1 ,2341    ,144,144,144
BEGIN DESCRIPTION:
GERONIMO TRIBUTARY 4 5.0
END DESCRIPTION:
XS GIS Cut Line= 3
      2303225.04     13764274.98        2303575.       13764125.
      2303474.99     13763774.95
#Sta/Elev= 30
    4623  558.35  4644.7  558.71  4678.4  552.57    4690  551.65  4708.2  545.52
  4713.6  547.21  4760.8  535.38  4770.6  535.55  4843.5  533.31  4879.1   531.5
  4942.1  526.14  4986.6     518    4987   517.5  4991.9     518  5036.2  521.72
  5054.4  527.23  5059.6  522.24  5066.1  529.46  5076.5  529.03  5093.4  519.57
  5098.6  523.84  5107.7  520.19  5139.5  522.73  5166.2  524.44  5205.2  522.39
  5261.4  526.37  5311.8   528.9    5317  553.04  5350.9  560.84  5367.8     561
#Mann= 10 ,-1 , 0
    4623    .094       0  4678.4    .035       0  4770.6     .07       0
  4843.5    .035       0  4879.1     .07       0  4986.6     .05       0
  4991.9     .07       0  5036.2    .063       0  5139.5    .035       0
  5261.4    .094       0
#XS Ineff= 2 , 0
       0                    5066       0     532
Permanent Ineff=
       F       F
Bank Sta=4986.6,4991.9
XS Rating Curve= 0 ,0
Exp/Cntr=0.3,0.1

Type RM Length L Ch R = 1 ,2197    ,176,176,176
BEGIN DESCRIPTION:
A19040
END DESCRIPTION:
XS GIS Cut Line= 3
       2303363.5     13764431.73      2303565.32     13764305.86
      2303738.95     13764110.53
#Sta/Elev= 30
  4698.5   535.4  4740.5  534.71  4865.3  531.76  4871.5  531.33  4877.4  531.49
    4924  529.28  4933.2  528.34  4939.9  528.34  4956.2  526.31  4978.9  522.99
  4993.1  517.47  5000.7  515.86  5004.7  515.78  5005.1  515.28  5009.6  515.28
    5010  515.78  5029.1  520.36  5035.8  520.84  5064.2  521.39  5073.7  523.15
  5084.6   524.6  5106.9  527.02  5121.1  527.39  5135.3  529.28    5142  529.12
  5149.5  526.04  5156.2  525.43  5177.9  528.15  5191.4  526.36  5197.7  526.36
#Mann= 7 ,-1 , 0
  4698.5    .035       0    4924     .07       0  4956.2     .12       0
  5004.7     .05       0    5010     .12       0  5073.7     .07       0
  5084.6     .12       0
#XS Ineff= 2 , 0
       0                    5035       0     528
Permanent Ineff=
       F       F
Bank Sta=5004.7,5010
XS Rating Curve= 0 ,0
Exp/Cntr=0.3,0.1

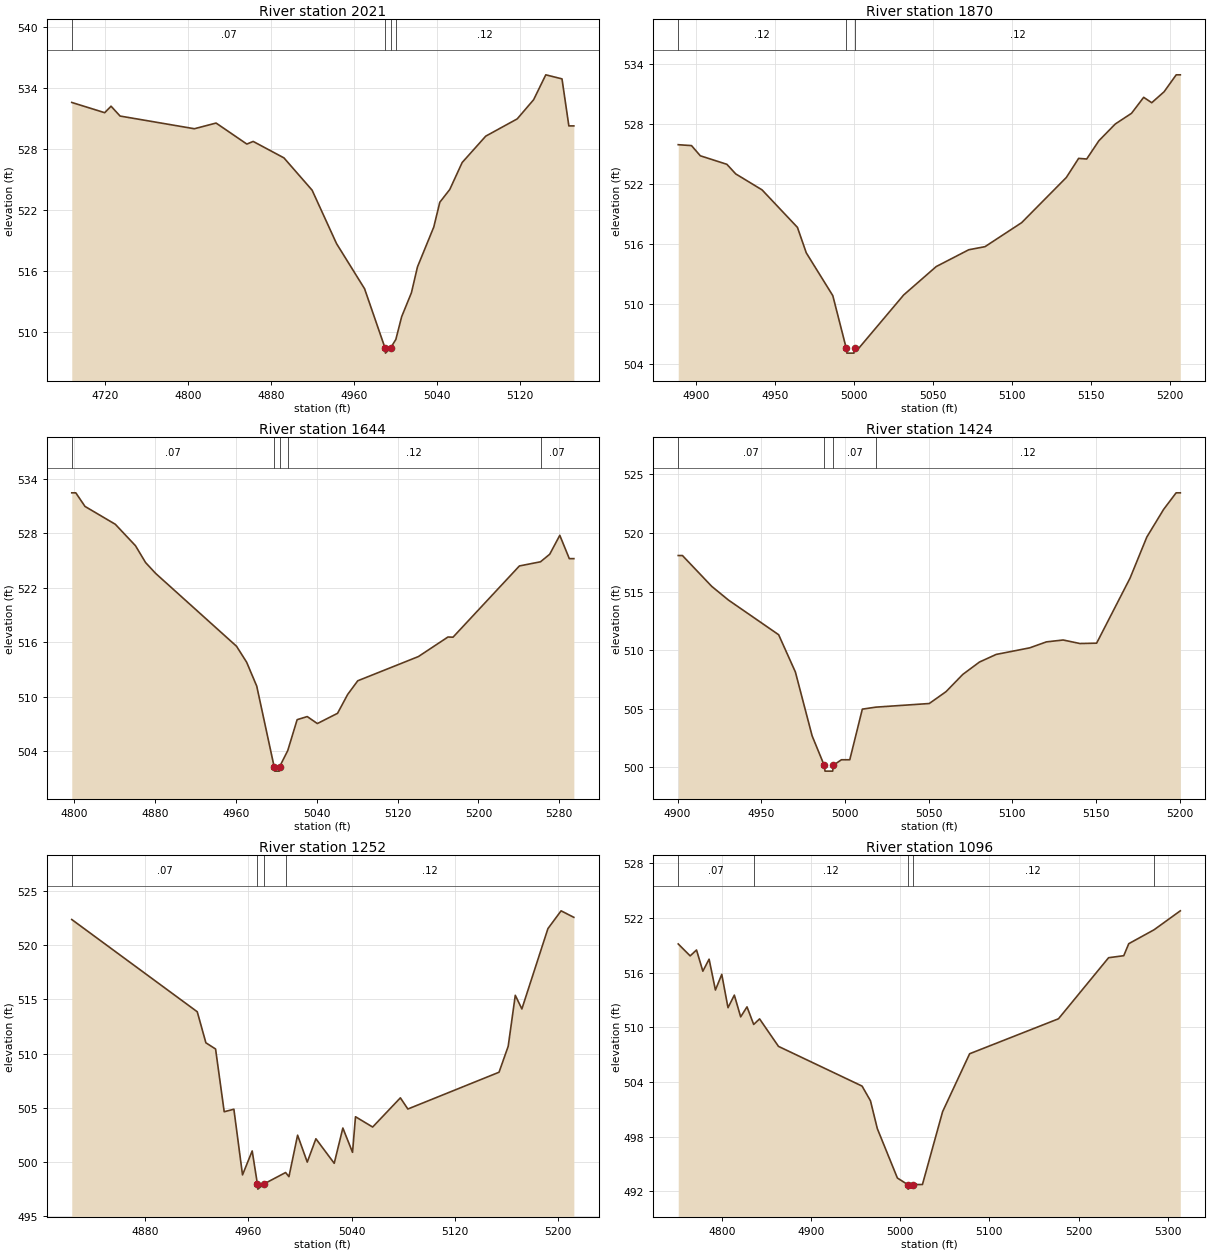
Type RM Length L Ch R = 1 ,2021    ,151,151,151
BEGIN DESCRIPTION:
A19039
END DESCRIPTION:
XS GIS Cut Line= 3
      2303495.85      13764529.4      2303749.78     13764351.43
       2303836.6     13764201.67
#Sta/Elev= 30
  4688.3  532.56    4720  531.55  4726.1  532.19  4734.8  531.22  4806.3  529.97
  4827.2  530.53  4856.8  528.46  4862.9  528.72  4892.5   527.1  4919.6  523.92
  4943.1  518.66  4970.1  514.21  4989.8  508.37  4990.2  507.87  4995.1  508.37
  5000.2  509.22  5005.8  511.46  5015.2  513.82    5021  516.36  5036.7  520.29
  5042.5  522.73  5052.1  523.99    5064  526.64  5086.7  529.24    5117  530.94
  5132.8  532.83  5144.5  535.28  5160.1  534.88  5166.7  530.25  5171.5  530.25
#Mann= 4 ,-1 , 0
  4688.3     .07       0  4989.8     .05       0  4995.1     .07       0
  5000.2     .12       0
Bank Sta=4989.8,4995.1
XS Rating Curve= 0 ,0
Exp/Cntr=0.3,0.1

Type RM Length L Ch R = 1 ,1870    ,226,226,226
BEGIN DESCRIPTION:
GERONIMO TRIBUTARY 4 4.0
END DESCRIPTION:
XS GIS Cut Line= 3
      2303774.99     13764575.02        2303825.       13764475.
        2303875.     13764274.99
#Sta/Elev= 30
  4888.7   525.9  4897.1  525.81  4902.7  524.79  4919.5  523.94  4925.1  522.98
  4941.8  521.38  4964.2  517.63  4969.8  515.08  4986.6   510.8  4995.1  505.55
  4995.5  505.05    5000  505.05  5000.4  505.55  5003.1  505.55  5031.5  510.87
  5052.1  513.71  5072.7  515.39    5083   515.7  5106.2   518.1  5134.5  522.62
  5142.3  524.53  5147.4  524.47  5155.1  526.29  5165.5  527.97  5175.8  529.04
  5183.5  530.64  5188.6   530.1  5196.4  531.19  5204.1  532.89  5206.7  532.89
#Mann= 3 ,-1 , 0
  4888.7     .12       0  4995.1     .05       0  5000.4     .12       0
Bank Sta=4995.1,5000.4
XS Rating Curve= 0 ,0
Exp/Cntr=0.3,0.1

Type RM Length L Ch R = 1 ,1644    ,220,220,220
BEGIN DESCRIPTION:
A19038
END DESCRIPTION:
XS GIS Cut Line= 2
      2304016.71     13764768.07      2304021.05     13764271.09
#Sta/Elev= 30
  4797.5  532.48  4801.5  532.48  4810.6  530.98  4840.6  529.01  4860.6  526.64
  4870.6  524.78  4880.6  523.58  4960.6  515.55  4970.6  513.79  4980.6  511.15
  4997.8  502.27  4998.3  501.77  5002.9  501.77  5003.3  502.27  5011.3  504.04
  5020.6  507.45  5030.6  507.79  5040.6  507.02  5060.6  508.15  5070.6  510.23
  5080.6  511.74  5140.6  514.41  5169.9  516.57  5174.9  516.55  5240.6  524.41
  5261.5  524.87  5270.6   525.7  5280.6  527.79    5290  525.22  5294.5  525.22
#Mann= 5 ,-1 , 0
  4797.5     .07       0  4997.8     .05       0  5003.3     .07       0
  5011.3     .12       0  5261.5     .07       0
Bank Sta=4997.8,5003.3
XS Rating Curve= 0 ,0
Exp/Cntr=0.3,0.1

Type RM Length L Ch R = 1 ,1424    ,172,172,172
BEGIN DESCRIPTION:
GERONIMO TRIBUTARY 4 3.0
END DESCRIPTION:
XS GIS Cut Line= 3
        2304225.       13764625.        2304225.       13764525.
        2304225.       13764325.
#Sta/Elev= 30
  4900.4  518.08  4902.9  518.08  4920.4  515.45  4930.4  514.28  4960.4  511.32
  4970.4  508.14  4980.4  502.69  4987.6  500.18  4988.1  499.68  4992.7  499.68
  4993.1  500.18  4997.9  500.65  5002.9  500.65  5010.4  504.97  5018.5  505.14
  5050.4  505.45  5060.4  506.46  5070.4  507.93  5080.4  508.99  5090.4  509.64
  5110.4   510.2  5120.4  510.71  5130.4  510.87  5140.4  510.57  5150.4   510.6
  5170.4  516.16  5180.4  519.66  5190.4  522.01  5197.9  523.43  5200.4  523.43
#Mann= 4 ,-1 , 0
  4900.4     .07       0  4987.6     .05       0  4993.1     .07       0
  5018.5     .12       0
Bank Sta=4987.6,4993.1
XS Rating Curve= 0 ,0
Exp/Cntr=0.3,0.1

Type RM Length L Ch R = 1 ,1252    ,156,156,156
BEGIN DESCRIPTION:
A19037
END DESCRIPTION:
XS GIS Cut Line= 4
       2304511.5      13764585.8      2304346.57     13764438.23
      2304253.26     13764383.98      2304240.23     13764325.36
#Sta/Elev= 30
    4823  522.36  4920.3  513.86    4927     511  4934.5  510.43  4941.2  504.65
  4948.7  504.88  4955.4  498.83  4962.9  501.04  4966.9  498.02  4967.3  497.52
  4972.4  498.02  4988.8  499.05  4991.4  498.67  4998.1  502.49  5005.6  500.01
  5012.3  502.16  5026.5   499.9  5033.2  503.15  5040.7  500.91    5043  504.19
  5056.3  503.24  5077.8  505.93  5083.6   504.9  5154.3  508.29  5161.4  510.68
  5166.9  515.38    5172  514.12  5192.2  521.52  5202.4  523.16  5212.3  522.56
#Mann= 4 ,-1 , 0
    4823     .07       0  4966.9     .05       0  4972.4     .07       0
  4988.8     .12       0
Bank Sta=4966.9,4972.4
XS Rating Curve= 0 ,0
Exp/Cntr=0.3,0.1

Type RM Length L Ch R = 1 ,1096    ,141,141,141
BEGIN DESCRIPTION:
A19036
END DESCRIPTION:
XS GIS Cut Line= 3
      2304669.95     13764499.02      2304563.59     13764392.66
       2304192.5     13764212.55
#Sta/Elev= 30
  4751.1  519.15  4764.5  517.84  4771.6  518.49  4778.7  516.16  4785.7  517.48
  4792.8  514.09  4799.9  515.81  4806.9  512.15    4814  513.53  4821.1  511.14
  4828.2  512.24  4835.7  510.31  4842.3  510.92  4863.5   507.9  4957.2  503.54
  4966.6  501.93  4974.3  498.87  4996.8  493.44  5008.4  492.72  5008.8  492.22
  5013.9  492.72  5024.9  492.73  5047.5  500.73  5077.8  507.09  5177.4  510.93
  5233.6  517.64  5250.6  517.86  5256.2  519.18  5284.6  520.71    5314  522.79
#Mann= 5 ,-1 , 0
  4751.1     .07       0  4835.7     .12       0  5008.4     .05       0
  5013.9     .12       0  5284.6     .07       0
Bank Sta=5008.4,5013.9
XS Rating Curve= 0 ,0
Exp/Cntr=0.3,0.1

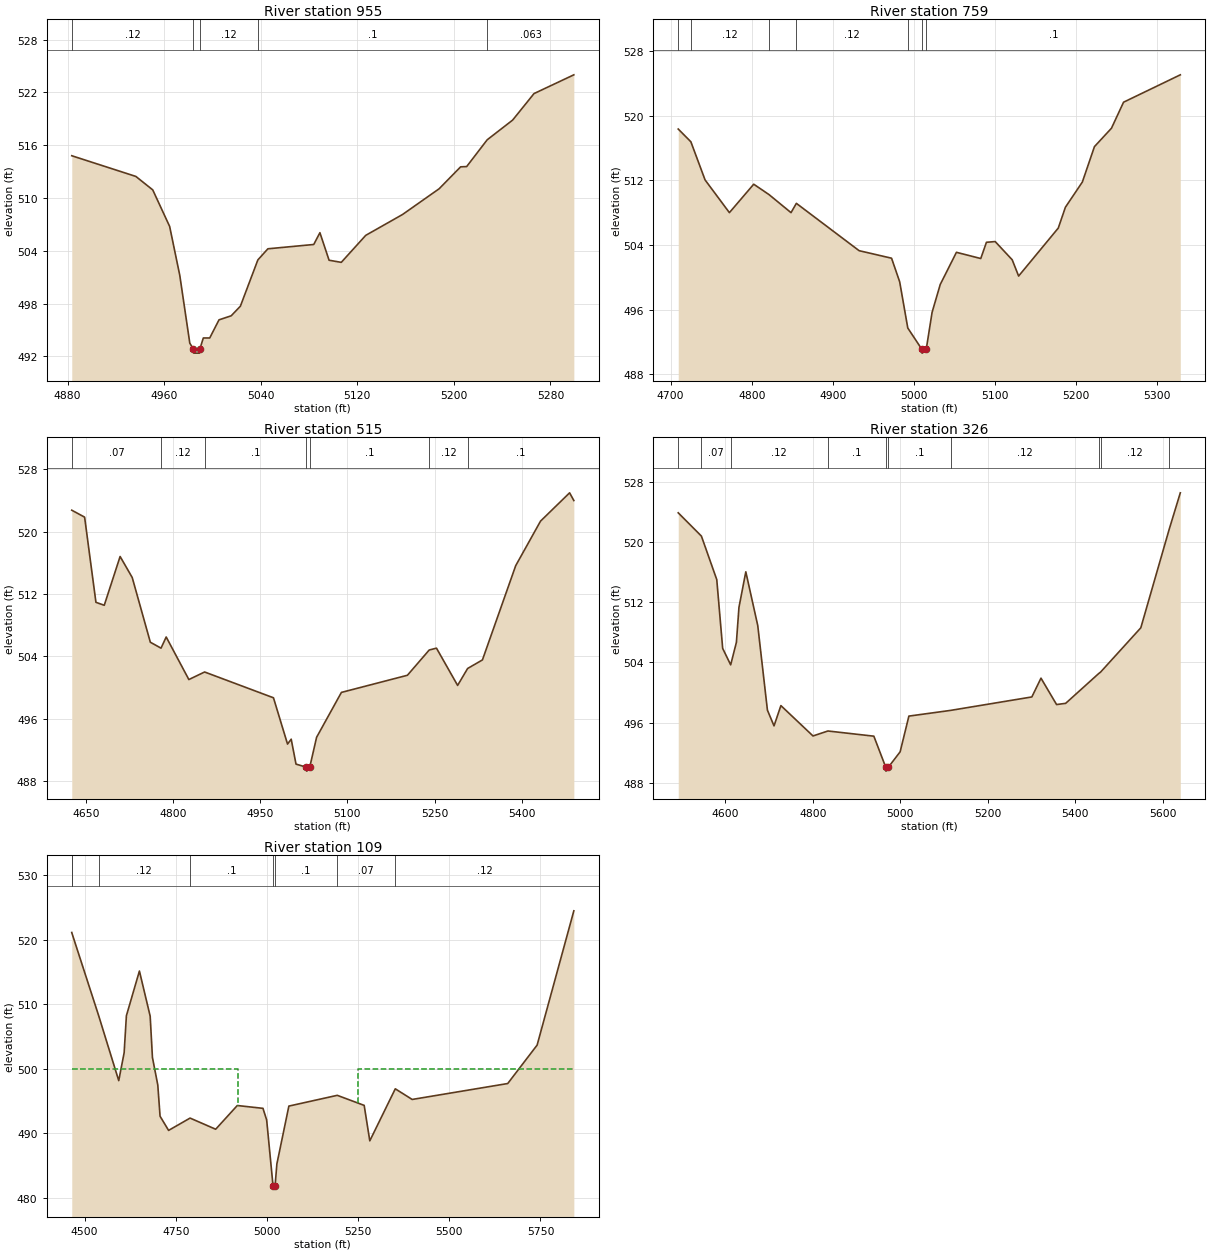
Type RM Length L Ch R = 1 ,955     ,196,196,196
BEGIN DESCRIPTION:
GERONIMO TRIBUTARY 4 2.0
END DESCRIPTION:
XS GIS Cut Line= 3
      2304625.01     13764375.01        2304575.       13764275.
      2304524.99     13763974.95
#Sta/Elev= 30
  4883.4   514.8  4936.5  512.45  4950.5  510.92  4964.5  506.77  4972.9  501.21
  4981.2  493.51    4984  492.88  4984.5  492.38  4989.2  492.38  4989.6  492.88
  4992.4   494.1  4997.7   494.1  5005.4  496.16  5015.5  496.62  5023.1  497.71
  5037.6  502.97  5045.9  504.23  5083.9  504.72    5089  506.06  5096.6  502.93
  5106.7  502.69    5127  505.76  5157.4  508.12  5187.8  511.05  5205.6  513.54
  5210.6  513.57  5227.6  516.61  5248.7  518.85  5266.4  521.86  5299.4  523.99
#Mann= 5 ,-1 , 0
  4883.4     .12       0    4984     .05       0  4989.6     .12       0
  5037.6      .1       0  5227.6    .063       0
Bank Sta=4984,4989.6
XS Rating Curve= 0 ,0
Exp/Cntr=0.3,0.1

Type RM Length L Ch R = 1 ,759     ,244,244,244
BEGIN DESCRIPTION:
A19035
END DESCRIPTION:
XS GIS Cut Line= 3
      2304752.39     13764538.08      2304745.88     13764156.12
      2304611.32     13763960.79
#Sta/Elev= 30
  4709.4  518.34    4725  516.76  4742.5  512.04  4772.5  507.99  4802.5  511.51
  4821.3  510.23  4848.5  507.99  4855.1  509.14  4932.5  503.28  4972.5  502.35
  4982.5  499.43  4992.5  493.71  5009.7   491.1  5010.2   490.6  5015.3   491.1
  5022.5  495.66  5032.5  499.09  5052.5  503.08  5082.5  502.31  5089.5  504.32
  5100.3  504.41  5121.3  502.15  5129.2  500.14  5178.1  506.08  5186.9  508.66
  5207.8  511.78  5222.7  516.16  5243.7  518.44  5258.6  521.66  5328.6  525.05
#Mann= 7 ,-1 , 0
  4709.4     .07       0    4725     .12       0  4821.3      .1       0
  4855.1     .12       0  4992.5      .1       0  5009.7     .05       0
  5015.3      .1       0
Bank Sta=5009.7,5015.3
XS Rating Curve= 0 ,0
Exp/Cntr=0.3,0.1

Type RM Length L Ch R = 1 ,515     ,189,189,189
BEGIN DESCRIPTION:
GERONIMO TRIBUTARY 4 1.0
END DESCRIPTION:
XS GIS Cut Line= 3
        2304875.     13764675.01        2304975.       13764325.
      2304675.01     13763925.01
#Sta/Elev= 30
  4625.7  522.77  4647.8  521.88  4667.3  510.95  4681.6  510.57  4708.9  516.83
  4729.7  514.14  4760.9  505.83  4779.3  505.07  4788.2   506.5  4827.2  501.04
  4854.3  502.01  4972.8   498.7    4997  492.76  5003.3  493.39  5011.6  490.19
  5029.6  489.79  5030.1  489.29  5035.2  489.79    5047  493.63  5089.7  499.39
  5203.3  501.59  5240.8  504.83  5253.3  505.07  5289.7  500.29  5306.9  502.46
  5332.4  503.56  5389.7  515.66  5432.4  521.37  5482.4     525  5489.7  524.01
#Mann= 7 ,-1 , 0
  4625.7     .07       0  4779.3     .12       0  4854.3      .1       0
  5029.6     .05       0  5035.2      .1       0  5240.8     .12       0
  5306.9      .1       0
Bank Sta=5029.6,5035.2
XS Rating Curve= 0 ,0
Exp/Cntr=0.3,0.1

Type RM Length L Ch R = 1 ,326     ,217,217,217
BEGIN DESCRIPTION:
A19034
END DESCRIPTION:
XS GIS Cut Line= 4
      2304960.74     13764781.08      2305149.52     13764457.77
      2305160.37     13764240.75      2304835.09     13763789.69
#Sta/Elev= 30
  4492.4  523.91  4545.4  520.81  4580.5  515.02    4594  505.87  4612.3  503.68
  4625.4  506.69  4631.2  511.32  4646.9  516.06  4674.2  508.91  4696.3  497.65
  4711.4  495.56  4727.1  498.26  4800.5  494.22  4834.6  494.88  4939.6  494.19
  4966.9  490.04  4967.3  489.54  4972.5  490.04  4999.7  492.11  5019.7  496.86
  5114.9  497.62  5300.8  499.41  5321.7  501.91  5357.3   498.4  5378.1  498.56
  5453.2   502.5    5458  502.72  5549.9  508.61  5614.9  521.74  5640.2  526.57
#Mann= 10 ,-1 , 0
  4492.4     .12       0  4545.4     .07       0  4612.3     .12       0
  4834.6      .1       0  4966.9     .05       0  4972.5      .1       0
  5114.9     .12       0  5453.2      .1       0    5458     .12       0
  5614.9      .1       0
Bank Sta=4966.9,4972.5
XS Rating Curve= 0 ,0
Exp/Cntr=0.3,0.1

Type RM Length L Ch R = 1 ,109     ,0,0,0
BEGIN DESCRIPTION:
A19033
END DESCRIPTION:
XS GIS Cut Line= 4
      2304997.58     13764796.33      2305307.94     13764577.12
      2305355.69     13764305.86      2304979.83     13763690.23
#Sta/Elev= 30
  4464.9  521.12  4465.8  520.94  4538.2   508.3  4593.7  498.14  4608.5  502.46
  4614.7  508.21  4650.4  515.14  4679.9  508.14  4686.1  501.74  4700.8  497.45
    4707  492.62  4730.4  490.42  4789.3  492.33  4859.5   490.6  4918.8  494.28
  4989.2  493.84  4999.3  492.04  5016.8  481.81  5017.3  481.31  5022.4  481.81
  5027.3  485.21  5060.2  494.19  5192.9  495.86  5266.7   494.3  5282.1   488.8
    5352  496.87  5398.3  495.22  5660.3  497.69  5740.9  503.65  5841.6  524.48
#Mann= 8 ,-1 , 0
  4464.9     .12       0  4465.8     .07       0  4538.2     .12       0
  4789.3      .1       0  5016.8     .05       0  5022.4      .1       0
  5192.9     .07       0    5352     .12       0
#XS Ineff= 2 , 0
       0    4920     500    5250       0     500
Permanent Ineff=
       F       F
Bank Sta=5016.8,5022.4
XS Rating Curve= 0 ,0
Exp/Cntr=0.3,0.1

Chan Stop Cuts=-1
Use User Specified Reach Order=0
Composite Channel Slope=5