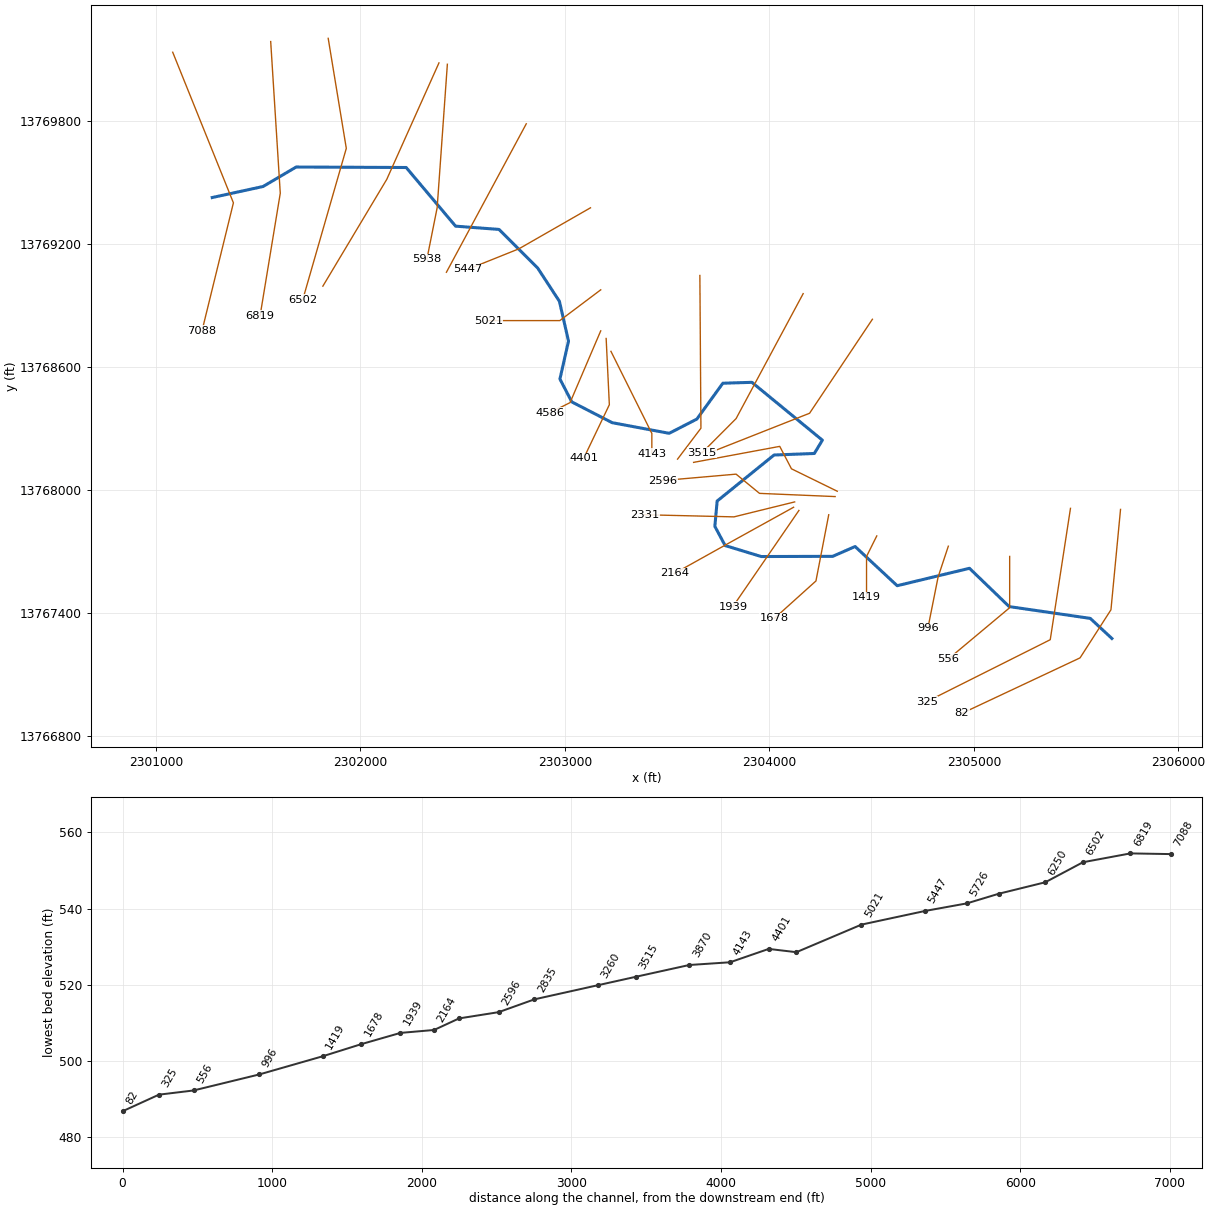
--- GERONIMO TRIBUTARY 5.prj (project) ---

Proj Title=GERONIMO TRIBUTARY 5 Base Level Engineering
Current Plan=p01
Default Exp/Contr=0.3,0.1
English Units
Geom File=g01
Flow File=f01
Plan File=p01
Y Axis Title=Elevation
X Axis Title(PF)=Main Channel Distance
X Axis Title(XS)=Station
BEGIN DESCRIPTION:
GERONIMO TRIBUTARY 5
END DESCRIPTION:
DSS Export Rating Curves= 0
DSS Export Rating Curve Sorted= 0
DSS Export Volume Flow Curves= 0
DXF OffsetX= 0
DXF OffsetY= 0
DXF ScaleX= 1
DXF ScaleY= 10

--- GERONIMO TRIBUTARY 5.p01 (plan) ---

Plan Title=Multiple Run
Short Identifier=Multiple
Geom File=g01
Flow File=f01
Subcritical Flow
K Sum by GR= 0
Std Step Tol= 0.01
Critical Tol= 0.01
Num of Std Step Trials= 20
Max Error Tol= 0.3
Flow Tol Ratio= 0.001
Split Flow NTrial= 30
Split Flow Tol= 0.02
Split Flow Ratio= 0.02
Log Output Level= 0
Friction Slope Method= 1
Unsteady Friction Slope Method= 2
Unsteady Bridges Friction Slope Method= 1
Parabolic Critical Depth
Global Vel Dist=  1 , 1 , 1
Global Log Level= 0
CheckData=True
Encroach Param= -1, 0, 0, 0
BEGIN DESCRIPTION:
Multiple Run
END DESCRIPTION:

--- GERONIMO TRIBUTARY 5.f01 (steady flow) ---

Flow Title=Multiple
Number of Profiles=7
Profile Names=10-year,25-year,50-year,1pct_min,100-year,1pct_plu,500-year
River Rch & RM= GERONIMO TRIBUTA,Reach-1,7088
     545     864    1148     738    1472    2936    2398
River Rch & RM= GERONIMO TRIBUTA,Reach-1,6502
     799    1306    1767    1158    2310    4608    3909
Boundary for River Rch & Prof#=GERONIMO TRIBUTA,Reach-1,1
Up Type=0
Dn Type=3
Dn Slope=0.005
Boundary for River Rch & Prof#=GERONIMO TRIBUTA,Reach-1,2
Up Type=0
Dn Type=3
Dn Slope=0.005
Boundary for River Rch & Prof#=GERONIMO TRIBUTA,Reach-1,3
Up Type=0
Dn Type=3
Dn Slope=0.005
Boundary for River Rch & Prof#=GERONIMO TRIBUTA,Reach-1,4
Up Type=0
Dn Type=3
Dn Slope=0.005
Boundary for River Rch & Prof#=GERONIMO TRIBUTA,Reach-1,5
Up Type=0
Dn Type=3
Dn Slope=0.005
Boundary for River Rch & Prof#=GERONIMO TRIBUTA,Reach-1,6
Up Type=0
Dn Type=3
Dn Slope=0.005
Boundary for River Rch & Prof#=GERONIMO TRIBUTA,Reach-1,7
Up Type=0
Dn Type=3
Dn Slope=0.005

--- GERONIMO TRIBUTARY 5.g01 (geometry) ---

Geom Title=Existing Conditions
Program Version=4.10

River Reach=GERONIMO TRIBUTA,Reach-1
Reach XY= 30
        2301275.       13769425.      2301523.44     13769478.76
       2301685.5      13769573.8      2302223.54     13769571.46
      2302465.18     13769285.47      2302677.45     13769269.54
      2302866.84     13769081.05      2302972.93     13768919.14
      2303017.44       13768725.      2302975.48      13768540.2
      2303033.46      13768428.5      2303230.93     13768327.25
      2303509.73     13768275.37      2303645.13     13768344.77
       2303772.3     13768519.65      2303914.56     13768523.97
        2304259.     13768241.94      2304219.56     13768177.07
      2304022.55     13768169.54      2303744.35     13767945.04
      2303733.21     13767821.73      2303783.29     13767728.16
      2303959.82     13767674.57      2304309.79     13767675.54
      2304418.97     13767723.38       2304624.9     13767532.32
      2304978.42     13767617.21      2305172.57     13767430.52
      2305569.16     13767372.98        2305675.       13767275.

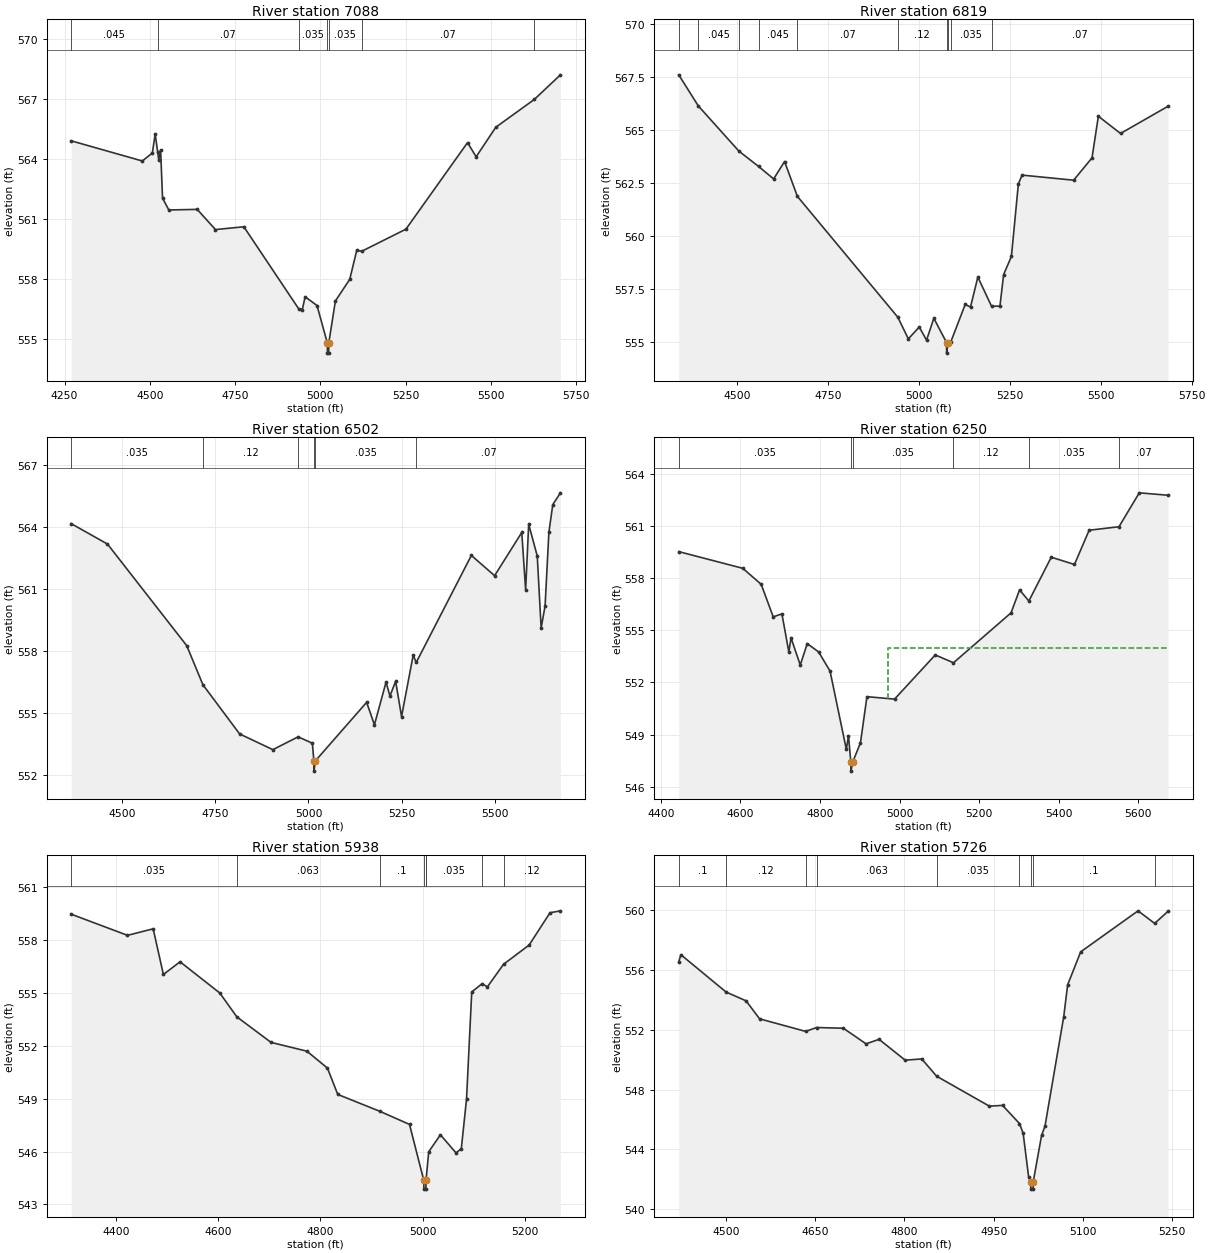
Type RM Length L Ch R = 1 ,7088    ,269,269,269
BEGIN DESCRIPTION:
GERONIMO TRIBUTARY 5 13.0
END DESCRIPTION:
XS GIS Cut Line= 3
      2301081.79     13770133.54      2301378.65      13769399.2
        2301225.     13768775.01
#Sta/Elev= 30
  4269.2  564.93  4477.9  563.92  4507.4  564.32  4515.7  565.27    4523  564.37
  4526.2  563.97  4531.6  564.46  4537.3  562.06  4555.7  561.47  4638.9   561.5
  4692.5  560.49  4775.7  560.63    4936  556.54  4947.2  556.49  4955.4  557.13
  4990.3  556.69  5020.6  554.81  5020.9  554.31  5024.5  554.31  5024.7  554.81
  5044.2  556.92  5086.2     558  5106.8  559.45    5122  559.41    5251  560.51
  5431.7  564.84  5456.9  564.13  5514.7  565.61  5627.6     567  5704.1  568.23
#Mann= 7 ,-1 , 0
  4269.2    .045       0    4523     .07       0    4936    .035       0
  5020.6    .035       0  5024.7    .035       0    5122     .07       0
  5627.6    .035       0
Bank Sta=5020.6,5024.7
XS Rating Curve= 0 ,0
Exp/Cntr=0.3,0.1

Type RM Length L Ch R = 1 ,6819    ,317,317,317
BEGIN DESCRIPTION:
A19059
END DESCRIPTION:
XS GIS Cut Line= 3
      2301560.94     13770185.65      2301607.81     13769446.08
      2301509.09     13768848.54
#Sta/Elev= 30
  4338.3  567.59    4392  566.13  4503.8     564  4557.9  563.28  4599.5  562.69
  4629.5  563.51  4664.8  561.87  4941.3  556.18  4970.2  555.16  5000.3  555.72
  5020.3   555.1  5040.4  556.13  5075.3  554.99  5075.6  554.49  5079.5  554.99
  5087.3  555.03  5126.7  556.78  5141.3  556.66  5161.5  558.07  5199.1   556.7
  5222.3   556.7  5232.5  558.19  5253.9  559.04    5273  562.45  5283.2  562.87
  5425.1  562.63  5475.7  563.68  5493.2  565.64  5554.2  564.83    5685  566.11
#Mann= 10 ,-1 , 0
  4338.3     .12       0    4392    .045       0  4503.8    .035       0
  4557.9    .045       0  4664.8     .07       0  4941.3     .12       0
  5075.3     .05       0  5079.5     .12       0  5087.3    .035       0
  5199.1     .07       0
Bank Sta=5075.3,5079.5
XS Rating Curve= 0 ,0
Exp/Cntr=0.3,0.1

Type RM Length L Ch R = 1 ,6502    ,252,252,252
BEGIN DESCRIPTION:
A19058
END DESCRIPTION:
XS GIS Cut Line= 3
      2301842.19     13770201.29      2301930.73     13769664.83
      2301717.19     13768925.26
#Sta/Elev= 30
  4362.8  564.15  4460.4  563.16  4673.2  558.24  4716.6  556.35  4815.1  553.97
  4904.3  553.21  4972.2  553.83  5010.4  553.52  5014.4  552.67  5014.6  552.17
  5018.6  552.67  5156.1   555.5    5177  554.41  5208.2  556.48  5218.6   555.8
  5233.9  556.52  5249.8  554.81    5281  557.78  5289.2  557.43  5437.2  562.61
  5499.6  561.63  5572.5  563.72  5582.9  560.94  5591.1  564.12  5614.1  562.58
  5624.5   559.1  5635.1  560.16  5645.3  563.73  5655.8  565.07  5676.3  565.64
#Mann= 6 ,-1 , 0
  4362.8    .035       0  4716.6     .12       0  4972.2    .035       0
  5014.4    .035       0  5018.6    .035       0  5289.2     .07       0
Bank Sta=5014.4,5018.6
XS Rating Curve= 0 ,0
Exp/Cntr=0.3,0.1

Type RM Length L Ch R = 1 ,6250    ,312,312,312
BEGIN DESCRIPTION:
A19057
END DESCRIPTION:
XS GIS Cut Line= 3
      2302383.86     13770081.51      2302128.65     13769513.79
      2301816.17     13768992.99
#Sta/Elev= 30
    4445  559.52  4605.9  558.56  4652.2  557.64  4682.4  555.77  4704.3  555.94
  4721.7  553.75  4727.2  554.56  4750.4     553    4768  554.23  4796.7  553.75
  4825.3  552.65  4866.2  548.15  4871.6  548.93  4877.6   547.4  4877.9   546.9
  4881.8   547.4  4901.7  548.52    4918  551.18  4987.4  551.04  5089.7  553.58
  5135.5  553.13  5280.2     556  5301.6  557.32    5325  556.68  5381.3   559.2
  5439.6  558.78  5476.5  560.75  5551.5  560.95  5602.5   562.9  5674.8  562.76
#Mann= 6 ,-1 , 0
    4445    .035       0  4877.6    .035       0  4881.8    .035       0
  5135.5     .12       0    5325    .035       0  5551.5     .07       0
#XS Ineff= 2 , 0
       0                    4970       0     554
Permanent Ineff=
       F       F
Bank Sta=4877.6,4881.8
XS Rating Curve= 0 ,0
Exp/Cntr=0.3,0.1

Type RM Length L Ch R = 1 ,5938    ,212,212,212
BEGIN DESCRIPTION:
GERONIMO TRIBUTARY 5 12.0
END DESCRIPTION:
XS GIS Cut Line= 3
        2302425.     13770074.95        2302375.       13769375.
        2302325.     13769124.98
#Sta/Elev= 30
  4312.6  559.46  4422.8  558.26    4473  558.63    4493  556.04  4525.6  556.76
  4603.3  554.99  4636.5  553.64  4703.5  552.19  4773.7  551.69  4813.8  550.73
  4833.9  549.24  4916.4  548.28  4974.2  547.54  5002.1  544.37  5002.4  543.87
  5006.2  543.87  5006.5  544.37  5006.6   544.4  5011.8  545.99  5034.7  546.95
  5065.3  545.92  5075.5  546.17  5085.7  548.97  5095.9  555.05  5116.2  555.52
  5126.5  555.34  5158.1  556.62  5208.1  557.71  5248.9  559.54  5269.3  559.65
#Mann= 8 ,-1 , 0
  4312.6    .035       0  4636.5    .063       0  4916.4      .1       0
  5002.1     .05       0  5006.5      .1       0  5006.6    .035       0
  5116.2      .1       0  5158.1     .12       0
Bank Sta=5002.1,5006.5
XS Rating Curve= 0 ,0
Exp/Cntr=0.3,0.1

Type RM Length L Ch R = 1 ,5726    ,279,279,279
BEGIN DESCRIPTION:
A19056
END DESCRIPTION:
XS GIS Cut Line= 2
      2302810.92     13769784.59      2302420.31     13769060.65
#Sta/Elev= 30
  4420.6  556.53  4424.2     557  4500.1  554.51  4533.8  553.92  4556.5  552.72
    4634  551.88  4652.4  552.14  4697.4  552.09  4735.5  551.05  4757.4  551.35
  4801.2  549.96  4829.2  550.04  4854.1  548.89  4942.8  546.89    4965  546.94
  4993.4  545.73  4999.6  545.08  5008.8  542.17  5012.2  541.85  5012.5  541.35
  5016.3  541.35  5016.6  541.85  5030.6  544.94  5036.3  545.55  5067.8  552.85
  5074.4  554.99  5096.3  557.19  5192.8  559.93  5220.7  559.09  5243.2   559.9
#Mann= 9 ,-1 , 0
  4420.6      .1       0  4500.1     .12       0    4634    .035       0
  4652.4    .063       0  4854.1    .035       0  4993.4      .1       0
  5012.2     .05       0  5016.6      .1       0  5220.7     .12       0
Bank Sta=5012.2,5016.6
XS Rating Curve= 0 ,0
Exp/Cntr=0.3,0.1

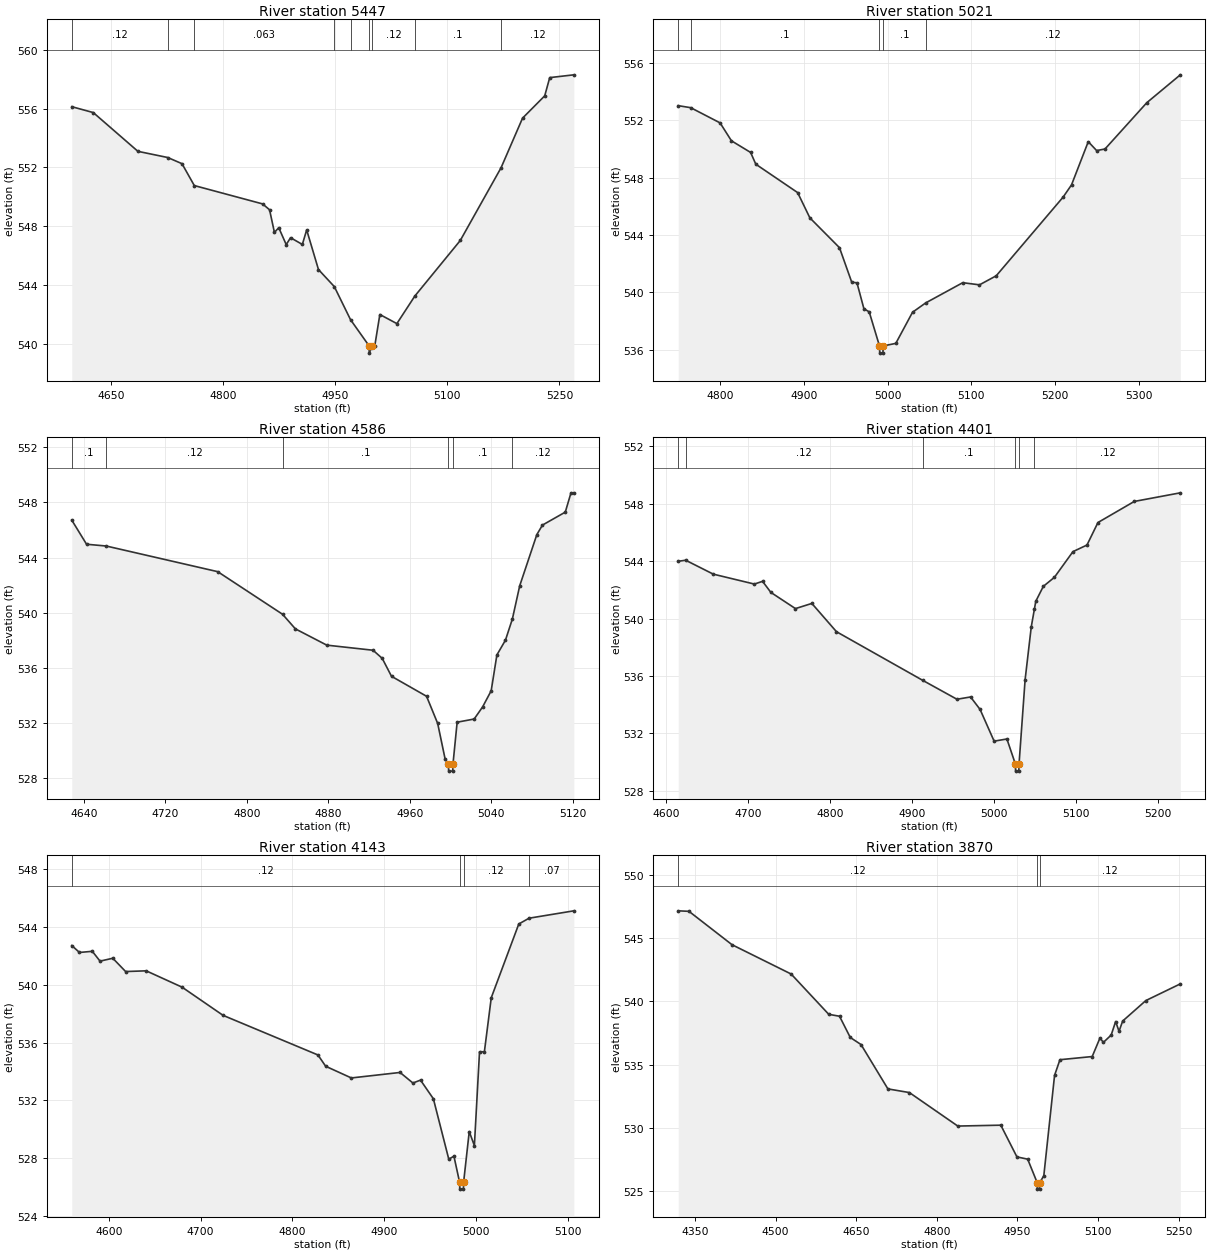
Type RM Length L Ch R = 1 ,5447    ,426,426,426
BEGIN DESCRIPTION:
GERONIMO TRIBUTARY 5 11.0
END DESCRIPTION:
XS GIS Cut Line= 3
      2303125.02     13769375.01        2302775.       13769175.
      2302524.99       13769075.
#Sta/Elev= 30
  4596.9  556.14  4625.7  555.74  4685.5   553.1  4725.4  552.68  4744.5  552.26
    4761  550.77  4852.5  549.52  4861.8  549.12  4868.3  547.58  4874.1   547.9
  4884.1  546.75  4889.9  547.22  4905.7  546.76  4911.5  547.75  4927.3  545.05
  4948.5  543.89  4970.2  541.64    4995  539.86  4995.3  539.36  4999.4  539.86
  5002.7  539.86  5009.5  541.99  5032.3  541.37  5056.4  543.25  5117.2  547.03
  5171.8  551.98  5200.6  555.36  5230.3  556.88    5237  558.12  5269.3  558.31
#Mann= 9 ,-1 , 0
  4596.9     .12       0  4725.4    .035       0    4761    .063       0
  4948.5    .035       0  4970.2     .12       0    4995     .05       0
  4999.4     .12       0  5056.4      .1       0  5171.8     .12       0
Bank Sta=4995,4999.4
XS Rating Curve= 0 ,0
Exp/Cntr=0.3,0.1

Type RM Length L Ch R = 1 ,5021    ,435,435,435
BEGIN DESCRIPTION:
GERONIMO TRIBUTARY 5 10.0
END DESCRIPTION:
XS GIS Cut Line= 3
      2303175.03     13768975.02        2302975.       13768825.
      2302625.03       13768825.
#Sta/Elev= 30
  4749.7  553.01  4764.6  552.87  4799.7  551.81  4813.3  550.56  4836.2  549.75
  4842.4  548.93  4892.4  546.95    4907  545.19  4942.4  543.11    4957  540.71
  4963.3  540.66  4971.6  538.85  4977.9  538.64  4990.2  536.26  4990.5  535.76
  4994.3  535.76  4994.6  536.26  5009.7  536.44  5029.7  538.61  5045.4  539.26
  5089.7  540.67  5109.7  540.52  5129.7  541.15  5209.7  546.64  5219.7  547.49
  5239.7   550.5  5249.7  549.88  5259.7  549.99  5309.7  553.22  5349.7  555.16
#Mann= 5 ,-1 , 0
  4749.7     .12       0  4764.6      .1       0  4990.2     .05       0
  4994.6      .1       0  5045.4     .12       0
Bank Sta=4990.2,4994.6
XS Rating Curve= 0 ,0
Exp/Cntr=0.3,0.1

Type RM Length L Ch R = 1 ,4586    ,185,185,185
BEGIN DESCRIPTION:
GERONIMO TRIBUTARY 5 9.0
END DESCRIPTION:
XS GIS Cut Line= 3
        2303175.       13768775.        2303025.       13768425.
      2302924.99     13768374.99
#Sta/Elev= 30
  4628.3  546.72  4642.8  544.97  4662.2  544.84  4771.5  542.98  4835.1  539.89
  4847.7  538.83  4878.5  537.65  4923.9  537.28  4932.9  536.69    4942  535.39
  4976.4  533.94  4987.3  531.97  4994.6  529.39  4997.8  529.01  4998.1  528.51
    5002  528.51  5002.3  529.01  5006.4  532.06  5023.1  532.29  5031.4  533.17
  5039.8  534.34  5045.4  536.94  5053.8  538.01  5060.6  539.55  5067.8  541.96
  5084.6  545.67  5090.1  546.36  5112.5   547.3  5118.1   548.7  5120.9   548.7
#Mann= 6 ,-1 , 0
  4628.3      .1       0  4662.2     .12       0  4835.1      .1       0
  4997.8     .05       0  5002.3      .1       0  5060.6     .12       0
Bank Sta=4997.8,5002.3
XS Rating Curve= 0 ,0
Exp/Cntr=0.3,0.1

Type RM Length L Ch R = 1 ,4401    ,258,258,258
BEGIN DESCRIPTION:
A19055
END DESCRIPTION:
XS GIS Cut Line= 3
      2303201.56     13768737.72      2303217.19     13768414.83
       2303092.2     13768154.44
#Sta/Elev= 30
  4614.7     544  4623.8  544.07  4657.5   543.1  4707.5  542.41  4717.5   542.6
  4727.6  541.83  4757.6   540.7  4777.6  541.06  4807.6  539.09  4912.7   535.7
  4954.5  534.38  4971.1  534.54  4982.7  533.67  4999.8  531.46  5015.4  531.61
  5025.7  529.87    5026  529.37  5029.9  529.37  5030.2  529.87  5037.6  535.75
  5045.1  539.43    5049  540.69  5050.6  541.21  5059.8  542.25  5073.3  542.88
  5095.9  544.67    5113  545.13  5126.4   546.7  5170.7  548.17  5226.8  548.77
#Mann= 6 ,-1 , 0
  4614.7      .1       0  4623.8     .12       0  4912.7      .1       0
  5025.7     .05       0  5030.2      .1       0    5049     .12       0
Bank Sta=5025.7,5030.2
XS Rating Curve= 0 ,0
Exp/Cntr=0.3,0.1

Type RM Length L Ch R = 1 ,4143    ,273,273,273
BEGIN DESCRIPTION:
GERONIMO TRIBUTARY 5 8.0
END DESCRIPTION:
XS GIS Cut Line= 3
        2303225.     13768675.01        2303425.       13768275.
        2303425.     13768175.02
#Sta/Elev= 30
  4559.7  542.71  4568.1  542.23  4582.1  542.31  4590.5  541.63  4604.4  541.83
  4618.4  540.91  4640.8  540.96  4679.9  539.83  4724.6  537.88    4828  535.14
  4836.4  534.36  4864.4  533.55  4917.5  533.93  4931.5   533.2  4939.8   533.4
  4953.8  532.11  4970.6  527.93  4976.2  528.14  4982.3  526.36  4982.6  525.86
  4986.5  525.86  4986.8  526.36  4992.9  529.84  4998.5  528.87  5004.1  535.36
  5009.4  535.36  5016.9   539.1  5046.9   544.2  5058.1   544.6  5106.9  545.11
#Mann= 4 ,-1 , 0
  4559.7     .12       0  4982.3     .05       0  4986.8     .12       0
  5058.1     .07       0
Bank Sta=4982.3,4986.8
XS Rating Curve= 0 ,0
Exp/Cntr=0.3,0.1

Type RM Length L Ch R = 1 ,3870    ,355,355,355
BEGIN DESCRIPTION:
A19054
END DESCRIPTION:
XS GIS Cut Line= 3
       2303659.9       13769045.       2303665.1     13768300.25
       2303550.8     13768149.57
#Sta/Elev= 30
    4319  547.16    4339  547.12    4419  544.48    4529  542.16    4599  538.97
    4619  538.82    4639  537.14    4659  536.58    4709  533.07    4749  532.78
    4839  530.13    4919   530.2    4949  527.69    4969  527.51  4986.8  525.64
  4987.1  525.14    4991  525.14  4991.3  525.64    4999   526.2    5019  534.14
    5029  535.38    5089  535.63  5103.5   537.1  5109.8  536.75  5124.3  537.33
  5132.6   538.4  5138.9  537.63  5145.7  538.44  5188.8  540.06  5252.9  541.38
#Mann= 3 ,-1 , 0
    4319     .12       0  4986.8     .05       0  4991.3     .12       0
Bank Sta=4986.8,4991.3
XS Rating Curve= 0 ,0
Exp/Cntr=0.3,0.1

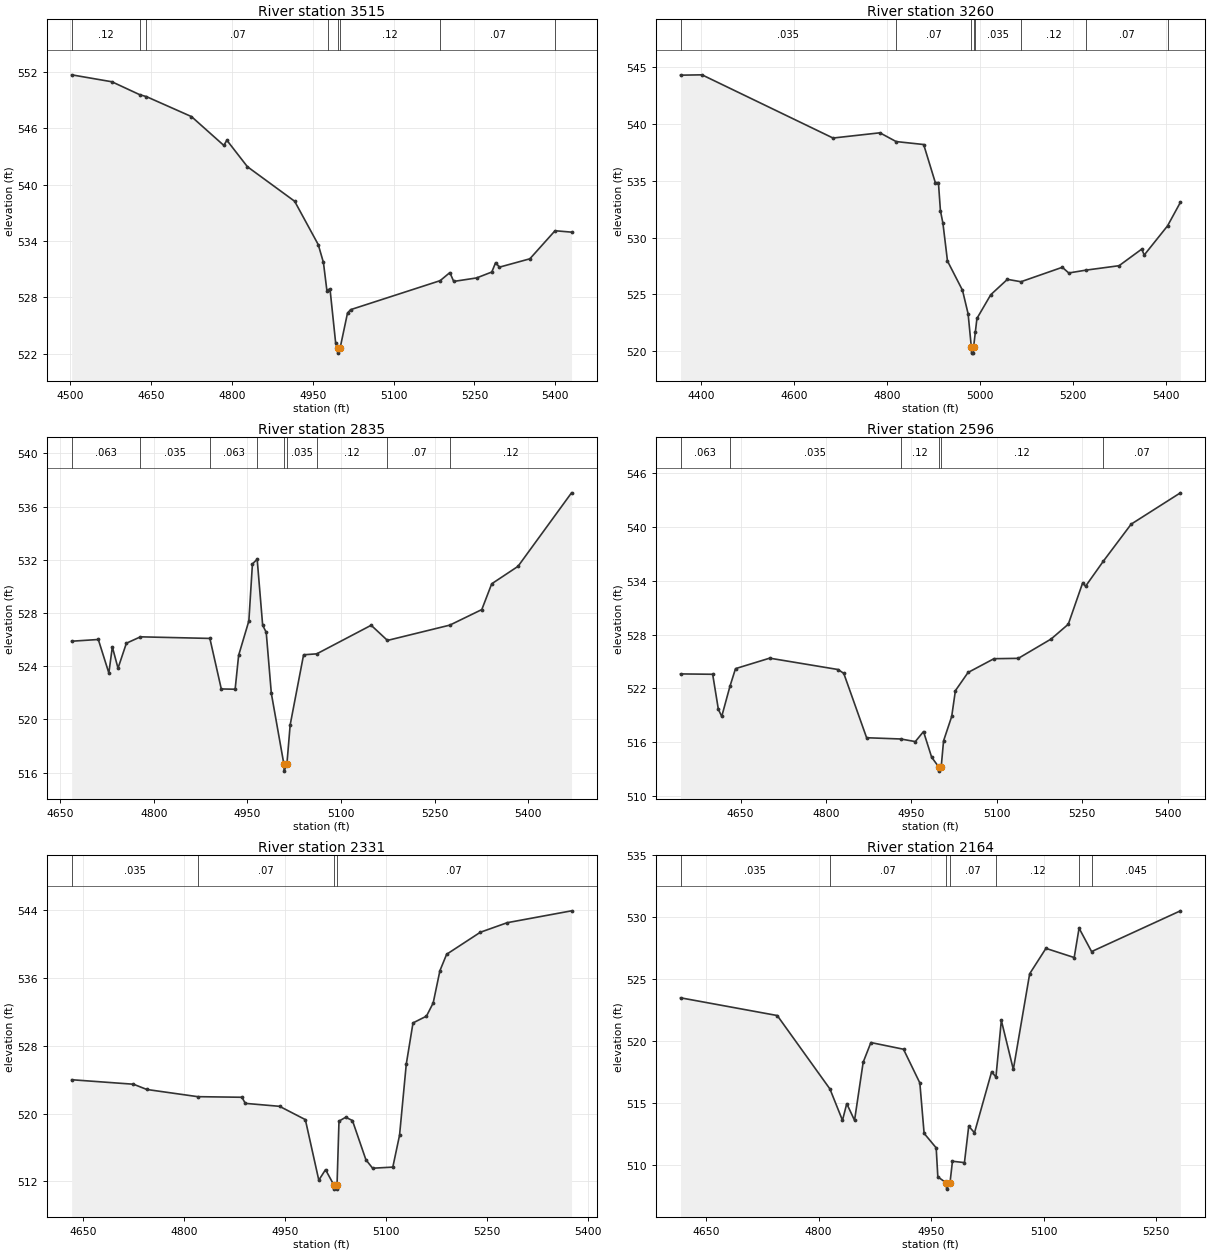
Type RM Length L Ch R = 1 ,3515    ,255,255,255
BEGIN DESCRIPTION:
A19053
END DESCRIPTION:
XS GIS Cut Line= 3
      2304165.09     13768956.47      2303836.98     13768347.12
      2303670.29     13768180.43
#Sta/Elev= 30
  4502.5  551.71  4577.2  550.97    4629  549.59  4641.2  549.39  4724.9  547.26
  4784.9  544.19  4790.6  544.74  4828.7  541.92  4916.4  538.24  4960.2  533.62
  4969.8  531.72  4976.4  528.65  4979.2  528.75  4982.1  528.85  4992.5  523.14
    4996  522.56  4996.3  522.06  5000.6  522.56  5014.5  526.33  5020.2  526.69
  5186.4  529.78  5204.5  530.64  5211.6   529.7    5254  530.07  5282.3   530.7
  5289.4   531.7  5296.5  531.22    5353  532.11  5399.7   535.1  5430.3  534.95
#Mann= 8 ,-1 , 0
  4502.5     .12       0    4629      .1       0  4641.2     .07       0
  4979.2     .12       0    4996     .05       0  5000.6     .12       0
  5186.4     .07       0  5399.7     .12       0
Bank Sta=4996,5000.6
XS Rating Curve= 0 ,0
Exp/Cntr=0.3,0.1

Type RM Length L Ch R = 1 ,3260    ,425,425,425
BEGIN DESCRIPTION:
A19052
END DESCRIPTION:
XS GIS Cut Line= 3
      2304503.64     13768831.48      2304196.35     13768373.16
      2303708.39     13768181.09
#Sta/Elev= 30
  4355.9  544.28  4402.1  544.31  4684.2  538.75  4785.1  539.21    4820  538.44
  4879.3  538.18  4904.4  534.83  4911.1  534.83  4915.4  532.36  4920.8  531.25
  4930.6  527.93  4962.9  525.36    4975  523.29    4982  520.33  4982.4  519.83
  4986.4  519.83  4986.7  520.33  4990.7  521.73    4994  522.88  5023.8  524.97
  5059.6  526.32  5088.8  526.11  5177.8  527.38  5191.7  526.88  5228.7  527.13
    5300  527.52  5348.8  528.98  5354.2  528.46  5404.3  531.02  5432.1   533.1
#Mann= 8 ,-1 , 0
  4355.9    .035       0    4820     .07       0    4982    .035       0
  4986.7     .07       0  4990.7    .035       0  5088.8     .12       0
  5228.7     .07       0  5404.3     .12       0
Bank Sta=4982,4986.7
XS Rating Curve= 0 ,0
Exp/Cntr=0.3,0.1

Type RM Length L Ch R = 1 ,2835    ,239,239,239
BEGIN DESCRIPTION:
A19051
END DESCRIPTION:
XS GIS Cut Line= 4
      2304331.76     13767992.96      2304107.81     13768102.33
      2304050.52      13768211.7      2303629.28      13768133.7
#Sta/Elev= 30
  4668.2  525.88  4710.9  526.01  4727.8  523.49  4733.4  525.45  4742.5  523.85
  4755.9  525.73  4778.5  526.21  4889.7  526.09    4908  522.29  4930.2  522.27
  4935.8  524.82  4952.2  527.41  4957.9  531.69  4965.5  532.05  4974.3  527.08
    4980  526.55  4988.2  521.96  5008.4  516.61  5008.7  516.11  5013.1  516.61
  5018.4  519.59  5039.9  524.86    5061  524.93  5148.2  527.08  5174.3  525.94
  5274.2  527.09  5325.5  528.26  5341.4   530.2  5383.5  531.51  5469.3  537.04
#Mann= 9 ,-1 , 0
  4668.2    .063       0  4778.5    .035       0  4889.7    .063       0
  4965.5    .035       0  5008.4    .035       0  5013.1    .035       0
    5061     .12       0  5174.3     .07       0  5274.2     .12       0
Bank Sta=5008.4,5013.1
XS Rating Curve= 0 ,0
Exp/Cntr=0.3,0.1

Type RM Length L Ch R = 1 ,2596    ,265,265,265
BEGIN DESCRIPTION:
A19050
END DESCRIPTION:
XS GIS Cut Line= 4
      2304321.39     13767966.91      2303951.56     13767982.54
      2303836.98     13768076.29      2303478.84     13768045.14
#Sta/Elev= 30
  4544.6   523.6    4601  523.56    4611  519.64  4616.9  518.85  4631.3  522.21
  4641.1  524.19  4701.1  525.36  4821.2  524.09  4831.2  523.66  4871.3  516.47
  4931.4  516.33  4956.8  516.04  4971.2  517.16  4985.5  514.29  4997.6  513.24
  4997.9  512.74  5002.3  513.24  5006.4  516.12  5020.7  518.85  5027.2  521.73
  5049.4  523.76  5094.9   525.3  5137.7  525.34  5195.3   527.5  5225.4  529.15
  5250.7  533.78  5255.7  533.39  5286.8  536.18  5335.8  540.33  5422.3  543.83
#Mann= 6 ,-1 , 0
  4544.6    .063       0  4631.3    .035       0  4931.4     .12       0
  4997.6     .05       0  5002.3     .12       0  5286.8     .07       0
Bank Sta=4997.6,5002.3
XS Rating Curve= 0 ,0
Exp/Cntr=0.3,0.1

Type RM Length L Ch R = 1 ,2331    ,167,167,167
BEGIN DESCRIPTION:
A19049
END DESCRIPTION:
XS GIS Cut Line= 3
      2304123.45     13767940.87      2303826.56     13767867.95
       2303389.5     13767878.36
#Sta/Elev= 30
  4633.2  524.01  4725.1  523.48  4744.9  522.86  4820.6  522.01  4886.2  521.94
  4891.3  521.22  4942.2  520.87  4980.5   519.3  5000.5  512.15  5010.5  513.39
  5022.8  511.59  5023.1  511.09  5027.2  511.09  5027.6  511.59  5030.5  519.12
  5040.5  519.58  5050.5  519.19  5070.5  514.56  5080.5  513.56  5110.5  513.69
  5120.5  517.45  5130.5  525.85  5140.5  530.72  5160.5  531.52  5170.5  533.08
  5180.5  536.89  5190.5  538.83  5240.6  541.43  5280.6  542.56  5376.1  543.96
#Mann= 4 ,-1 , 0
  4633.2    .035       0  4820.6     .07       0  5022.8     .05       0
  5027.6     .07       0
Bank Sta=5022.8,5027.6
XS Rating Curve= 0 ,0
Exp/Cntr=0.3,0.1

Type RM Length L Ch R = 1 ,2164    ,225,225,225
BEGIN DESCRIPTION:
A19048
END DESCRIPTION:
XS GIS Cut Line= 3
      2304118.27     13767914.85      2303816.15     13767748.16
      2303534.89     13767591.91
#Sta/Elev= 30
  4615.8  523.49  4744.8  522.06  4815.1  516.13  4831.8   513.6  4837.5  514.95
  4847.9   513.6  4859.4  518.29  4869.7  519.88  4913.2  519.34    4935  516.62
  4940.7  512.55  4956.8  511.38    4959  509.04  4970.3  508.55  4970.7  508.05
  4975.2  508.55  4978.5   510.3  4994.5  510.19  5000.2  513.13  5007.9   512.6
  5030.8  517.53  5036.5  517.09  5043.7  521.67  5059.7  517.71  5081.5  525.43
  5103.2  527.48  5140.9  526.74  5147.4  529.11  5164.1  527.22  5282.6  530.51
#Mann= 7 ,-1 , 0
  4615.8    .035       0  4815.1     .07       0  4970.3     .05       0
  4975.2     .07       0  5036.5     .12       0  5147.4     .07       0
  5164.1    .045       0
Bank Sta=4970.3,4975.2
XS Rating Curve= 0 ,0
Exp/Cntr=0.3,0.1

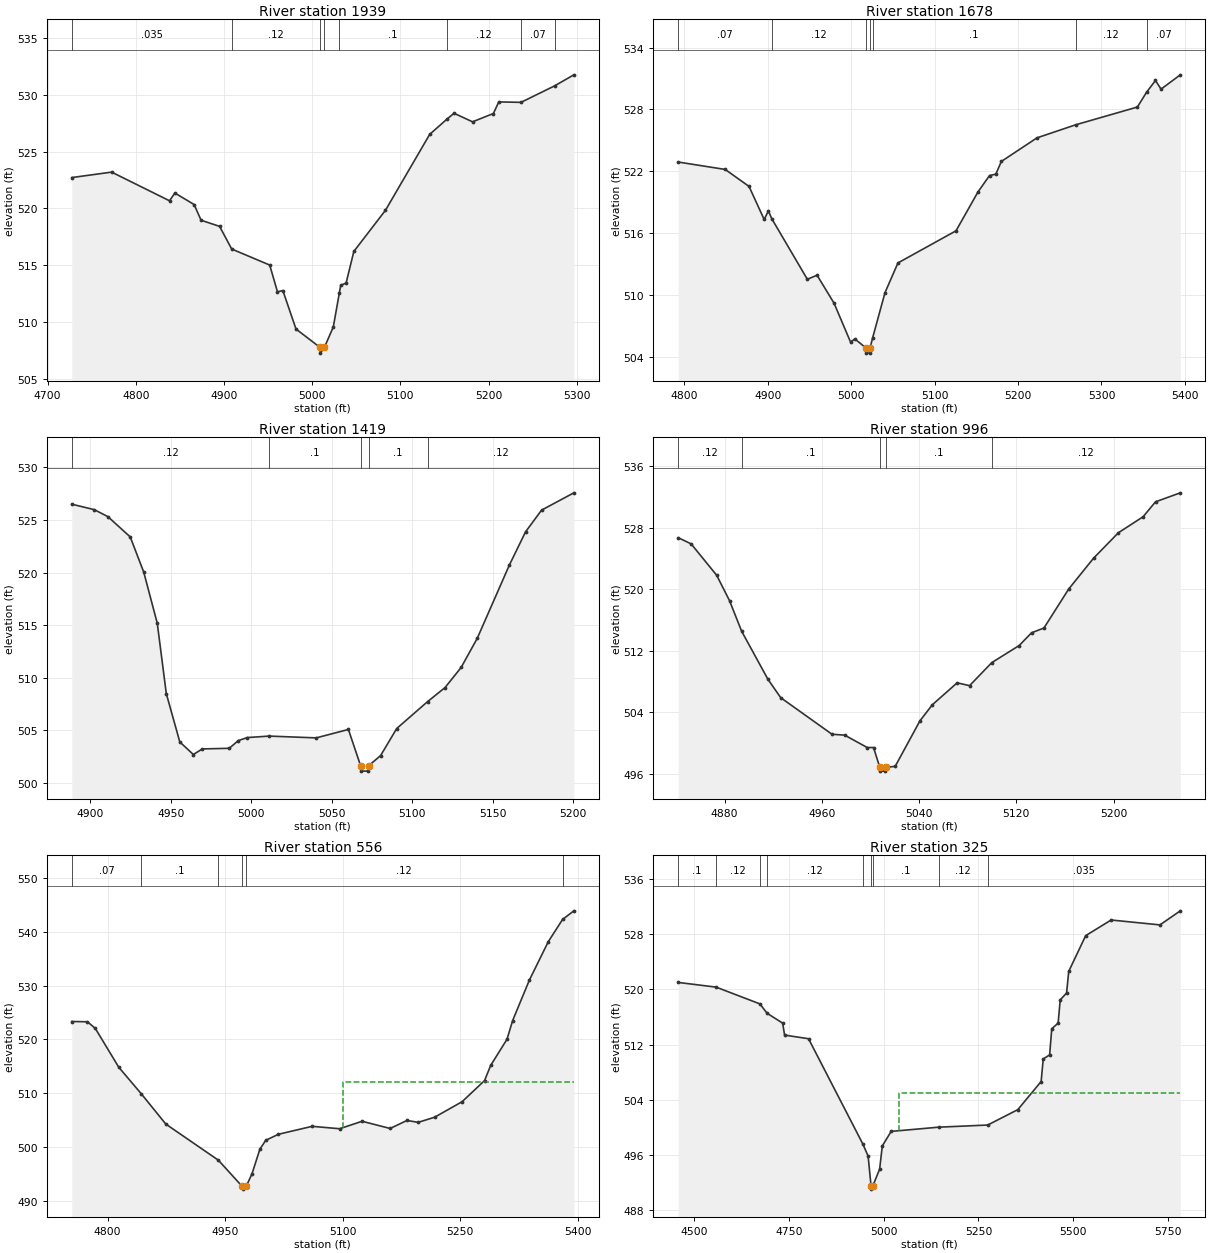
Type RM Length L Ch R = 1 ,1939    ,261,261,261
BEGIN DESCRIPTION:
A19047
END DESCRIPTION:
XS GIS Cut Line= 2
      2304144.27      13767899.2      2303821.36     13767430.46
#Sta/Elev= 30
  4727.4  522.71  4772.6  523.19  4838.2  520.67  4844.3  521.35  4866.1  520.34
    4874  518.96    4895  518.42  4908.7  516.43  4951.8  515.02  4960.6  512.67
  4966.7  512.78  4981.6   509.4  5008.9  507.78  5009.2  507.28  5013.8  507.78
  5023.9  509.58  5030.7  512.54  5032.3  513.24  5038.4  513.44  5047.2  516.22
    5083  519.83  5133.2  526.51  5152.8  527.85  5160.8  528.36  5181.8  527.61
  5205.4  528.34  5211.5  529.36  5236.7  529.32  5274.8  530.77  5296.6  531.74
#Mann= 8 ,-1 , 0
  4727.4    .035       0  4908.7     .12       0  5008.9     .05       0
  5013.8     .12       0  5030.7      .1       0  5152.8     .12       0
  5236.7     .07       0  5274.8    .045       0
Bank Sta=5008.9,5013.8
XS Rating Curve= 0 ,0
Exp/Cntr=0.3,0.1

Type RM Length L Ch R = 1 ,1678    ,259,259,259
BEGIN DESCRIPTION:
A19046
END DESCRIPTION:
XS GIS Cut Line= 3
      2304290.11     13767878.39       2304227.6     13767555.45
      2304024.45     13767373.13
#Sta/Elev= 30
  4792.6  522.89  4848.9  522.17  4877.5  520.52  4895.6  517.31  4900.7  518.14
  4904.7  517.39  4947.4   511.5    4959   511.9  4979.4  509.18  4999.2   505.4
  5004.3  505.71  5017.7  504.83    5018  504.33  5022.2  504.33  5022.6  504.83
  5025.7  505.83  5040.5  510.21    5056  513.09  5125.6  516.21  5151.9  519.98
  5165.8  521.58  5173.3  521.71    5180  522.95  5222.7  525.24  5269.2  526.51
    5343  528.23    5354  529.66  5364.7  530.81  5371.4  529.97  5394.5  531.36
#Mann= 7 ,-1 , 0
  4792.6     .07       0  4904.7     .12       0  5017.7     .05       0
  5022.6     .12       0  5025.7      .1       0  5269.2     .12       0
    5354     .07       0
Bank Sta=5017.7,5022.6
XS Rating Curve= 0 ,0
Exp/Cntr=0.3,0.1

Type RM Length L Ch R = 1 ,1419    ,423,423,423
BEGIN DESCRIPTION:
GERONIMO TRIBUTARY 5 3.0
END DESCRIPTION:
XS GIS Cut Line= 3
      2304525.01     13767775.01        2304475.       13767675.
        2304475.     13767475.02
#Sta/Elev= 30
  4888.5   526.5  4902.5  525.98  4910.9  525.32  4924.8  523.39  4933.2  520.04
  4941.6  515.18  4947.2   508.5  4955.6   503.9    4964  502.71  4969.6  503.24
  4986.3   503.3  4991.9  504.03  4997.5  504.32  5011.1  504.46  5040.3  504.29
  5060.3  505.09  5067.9  501.63  5068.2  501.13  5072.4  501.13  5072.8  501.63
  5080.3  502.61  5090.3  505.18  5109.5  507.74  5120.3  509.07  5130.3  510.98
  5140.3  513.75  5160.3  520.73  5170.3  523.87  5180.3  525.94  5200.3  527.58
#Mann= 5 ,-1 , 0
  4888.5     .12       0  5011.1      .1       0  5067.9     .05       0
  5072.8      .1       0  5109.5     .12       0
Bank Sta=5067.9,5072.8
XS Rating Curve= 0 ,0
Exp/Cntr=0.3,0.1

Type RM Length L Ch R = 1 ,996     ,440,440,440
BEGIN DESCRIPTION:
GERONIMO TRIBUTARY 5 2.0
END DESCRIPTION:
XS GIS Cut Line= 3
        2304875.     13767725.01        2304825.       13767575.
        2304775.     13767324.98
#Sta/Elev= 30
  4841.8  526.73  4852.4  525.93  4873.4  521.85    4884  518.54    4894  514.55
  4915.6  508.31  4926.1  505.92  4968.3  501.16  4978.8  501.04  4997.3  499.43
  5002.5  499.43  5007.6  496.86    5008  496.36  5012.2  496.36  5012.6  496.86
  5020.3  496.98  5040.7  502.91  5050.9     505  5071.3  507.85  5081.5  507.48
  5099.8  510.48  5122.3   512.7  5132.5  514.36  5142.7  514.98  5163.1  520.06
  5183.5  524.06  5203.9  527.37  5224.3  529.46  5234.5   531.4  5254.9  532.57
#Mann= 5 ,-1 , 0
  4841.8     .12       0    4894      .1       0  5007.6     .05       0
  5012.6      .1       0  5099.8     .12       0
Bank Sta=5007.6,5012.6
XS Rating Curve= 0 ,0
Exp/Cntr=0.3,0.1

Type RM Length L Ch R = 1 ,556     ,231,231,231
BEGIN DESCRIPTION:
GERONIMO TRIBUTARY 5 1.0
END DESCRIPTION:
XS GIS Cut Line= 3
        2305175.     13767675.04        2305175.       13767425.
      2304874.96     13767174.97
#Sta/Elev= 30
  4754.3  523.34  4774.3  523.29  4784.3  522.06  4814.3  514.82  4842.9   509.9
  4874.3  504.25  4941.4  497.52  4971.8  492.64  4972.2  492.14  4976.8  492.64
  4984.3  495.01  4994.3  499.57  5001.8  501.23    5018  502.35    5061  503.83
  5096.1  503.38  5124.7  504.77  5160.5  503.43    5182  504.92  5196.3  504.57
  5217.2  505.52  5252.3  508.41    5281  512.35  5288.8  515.17  5309.6  520.03
  5316.8  523.51  5338.2  531.06  5362.3   538.2  5380.5  542.33  5394.9  543.94
#Mann= 6 ,-1 , 0
  4754.3     .07       0  4842.9      .1       0  4941.4     .12       0
  4971.8     .05       0  4976.8     .12       0  5380.5    .035       0
#XS Ineff= 2 , 0
       0                    5100       0     512
Permanent Ineff=
       F       F
Bank Sta=4971.8,4976.8
XS Rating Curve= 0 ,0
Exp/Cntr=0.3,0.1

Type RM Length L Ch R = 1 ,325     ,243,243,243
BEGIN DESCRIPTION:
A19045
END DESCRIPTION:
XS GIS Cut Line= 3
      2305472.39     13767909.58      2305373.44       13767269.
      2304769.68     13766967.12
#Sta/Elev= 30
  4458.8     521  4558.6  520.32    4674  517.89    4693  516.53    4734   515.1
  4739.1  513.37  4802.2  512.84  4945.5  497.56  4959.2  495.83  4966.9  491.54
  4967.2  491.04  4971.9  491.54  4989.6  493.94  4996.6   497.3    5020  499.41
  5145.3  500.02  5274.4  500.33  5353.7  502.56  5415.2  506.64  5420.8  509.91
  5437.6   510.5  5443.2  514.28    5460  515.11  5465.5  518.47  5482.3  519.47
  5487.9   522.6  5532.6  527.78  5599.7  530.05  5728.3  529.34    5782  531.38
#Mann= 9 ,-1 , 0
  4458.8      .1       0  4558.6     .12       0    4674      .1       0
    4693     .12       0  4945.5      .1       0  4966.9     .05       0
  4971.9      .1       0  5145.3     .12       0  5274.4    .035       0
#XS Ineff= 2 , 0
       0                    5040       0     505
Permanent Ineff=
       F       F
Bank Sta=4966.9,4971.9
XS Rating Curve= 0 ,0
Exp/Cntr=0.3,0.1

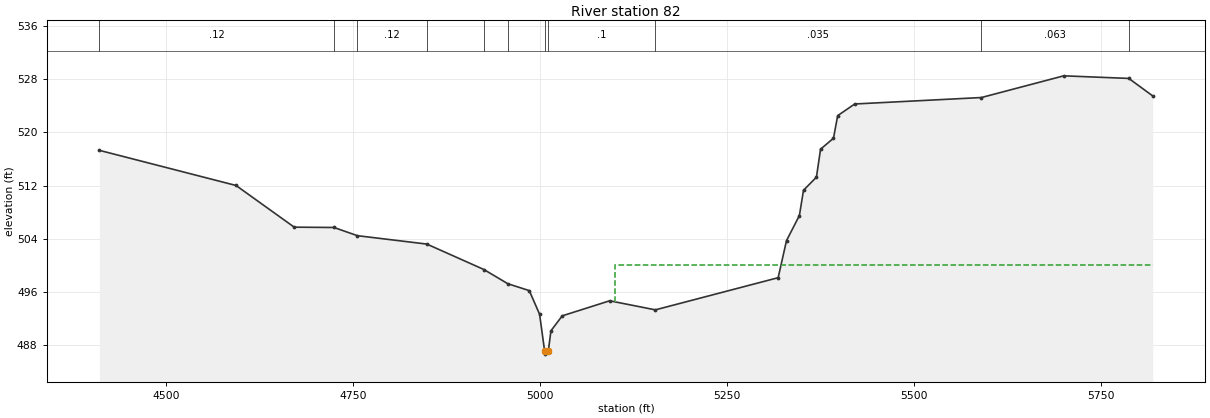
Type RM Length L Ch R = 1 ,82      ,0,0,0
BEGIN DESCRIPTION:
A19044
END DESCRIPTION:
XS GIS Cut Line= 4
      2305717.18     13767904.38      2305670.31     13767414.83
      2305519.27     13767180.45      2304941.54     13766909.81
#Sta/Elev= 30
  4410.9  517.29  4593.7  512.01  4671.5  505.75  4724.7   505.7    4756  504.47
  4848.8  503.21  4925.1  499.39  4957.2  497.25  4985.8  496.22  4999.6  492.67
  5006.3  487.18  5006.7  486.68  5011.3  487.18  5014.8  490.19  5029.9  492.43
  5093.3  494.69  5154.4  493.33  5318.6  498.16  5329.8  503.74    5347  507.49
  5352.5  511.29  5369.8  513.26  5375.3  517.46  5392.6  519.11  5398.2   522.5
    5421  524.25  5590.4  525.22  5700.5  528.48  5787.5  528.09  5819.5  525.46
#Mann= 11 ,-1 , 0
  4410.9     .12       0  4724.7      .1       0    4756     .12       0
  4848.8      .1       0  4925.1     .12       0  4957.2      .1       0
  5006.3     .05       0  5011.3      .1       0  5154.4    .035       0
  5590.4    .063       0  5787.5    .035       0
#XS Ineff= 2 , 0
       0                    5100       0     500
Permanent Ineff=
       F       F
Bank Sta=5006.3,5011.3
XS Rating Curve= 0 ,0
Exp/Cntr=0.3,0.1

Chan Stop Cuts=-1
Use User Specified Reach Order=0
Composite Channel Slope=5