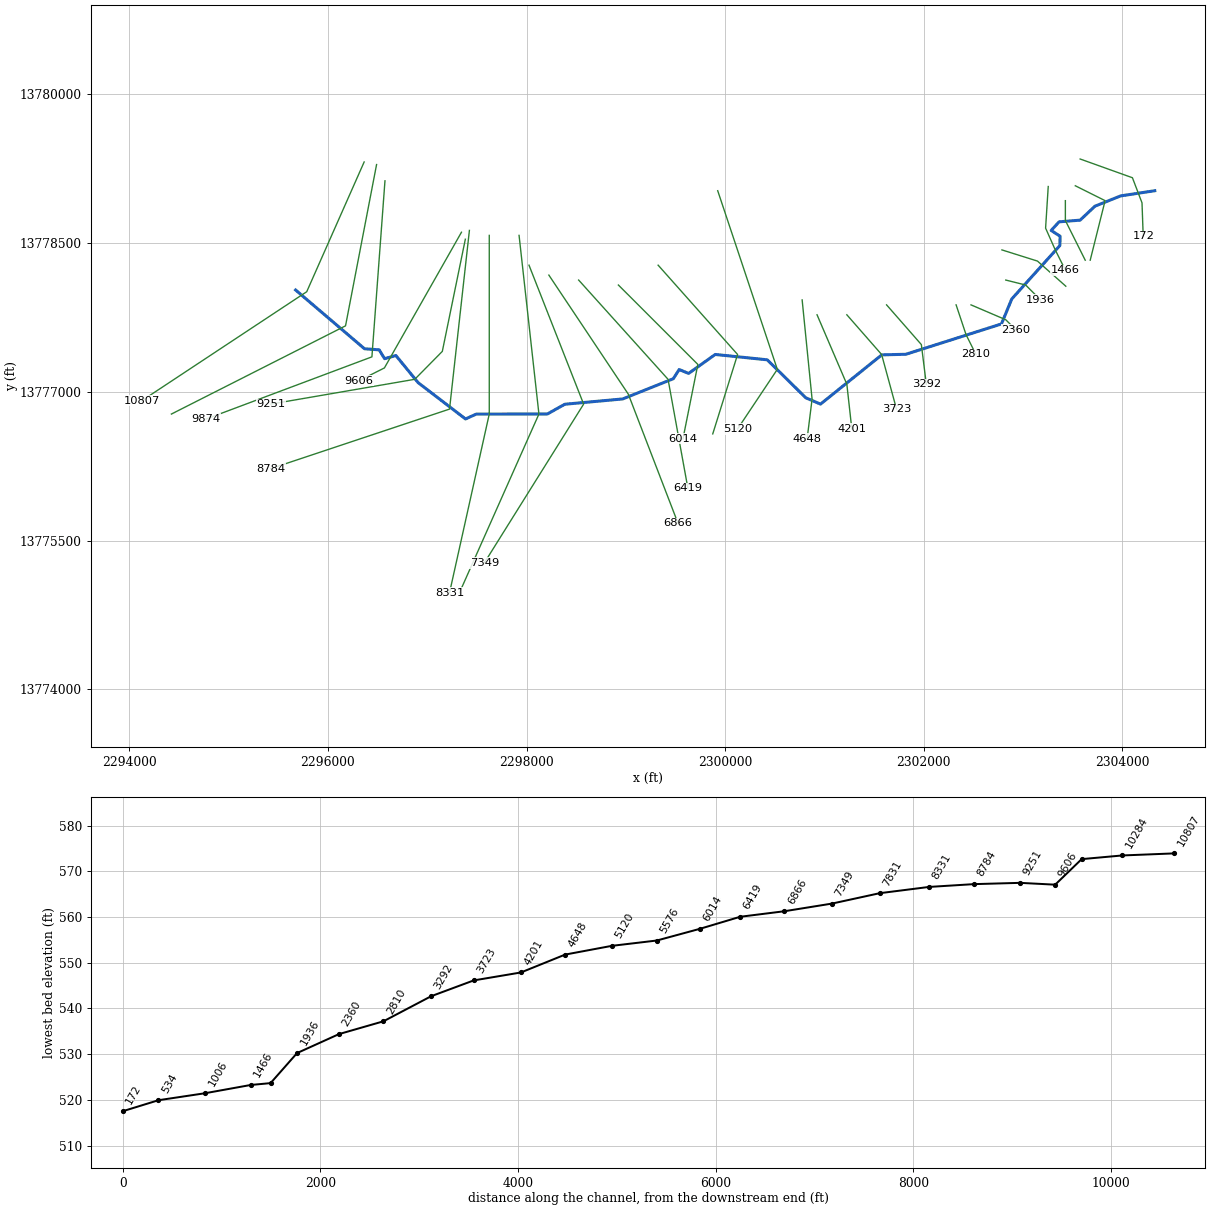
--- GERONIMO TRIBUTARY 6.prj (project) ---

Proj Title=GERONIMO TRIBUTARY 6 Base Level Engineering
Current Plan=p01
Default Exp/Contr=0.3,0.1
English Units
Geom File=g01
Flow File=f01
Plan File=p01
Y Axis Title=Elevation
X Axis Title(PF)=Main Channel Distance
X Axis Title(XS)=Station
BEGIN DESCRIPTION:
GERONIMO TRIBUTARY 6
END DESCRIPTION:
DSS Export Rating Curves= 0
DSS Export Rating Curve Sorted= 0
DSS Export Volume Flow Curves= 0
DXF OffsetX= 0
DXF OffsetY= 0
DXF ScaleX= 1
DXF ScaleY= 10

--- GERONIMO TRIBUTARY 6.p01 (plan) ---

Plan Title=Multiple Run
Short Identifier=Multiple
Geom File=g01
Flow File=f01
Subcritical Flow
K Sum by GR= 0
Std Step Tol= 0.01
Critical Tol= 0.01
Num of Std Step Trials= 20
Max Error Tol= 0.3
Flow Tol Ratio= 0.001
Split Flow NTrial= 30
Split Flow Tol= 0.02
Split Flow Ratio= 0.02
Log Output Level= 0
Friction Slope Method= 1
Unsteady Friction Slope Method= 2
Unsteady Bridges Friction Slope Method= 1
Parabolic Critical Depth
Global Vel Dist=  1 , 1 , 1
Global Log Level= 0
CheckData=True
Encroach Param= -1, 0, 0, 0
BEGIN DESCRIPTION:
Multiple Run
END DESCRIPTION:

--- GERONIMO TRIBUTARY 6.f01 (steady flow) ---

Flow Title=Multiple
Number of Profiles=7
Profile Names=10-year,25-year,50-year,1pct_min,100-year,1pct_plu,500-year
River Rch & RM= GERONIMO TRIBUTA,Reach-1,10807
     573     908    1203     771    1538    3068    2491
River Rch & RM= GERONIMO TRIBUTA,Reach-1,7831
     778    1251    1675    1083    2161    4312    3568
River Rch & RM= GERONIMO TRIBUTA,Reach-1,6866
    1029    1684    2282    1493    2979    5944    5035
River Rch & RM= GERONIMO TRIBUTA,Reach-1,1466
    1665    2776    3808    2517    5022   10020    8666
Boundary for River Rch & Prof#=GERONIMO TRIBUTA,Reach-1,1
Up Type=0
Dn Type=3
Dn Slope=0.005
Boundary for River Rch & Prof#=GERONIMO TRIBUTA,Reach-1,2
Up Type=0
Dn Type=3
Dn Slope=0.005
Boundary for River Rch & Prof#=GERONIMO TRIBUTA,Reach-1,3
Up Type=0
Dn Type=3
Dn Slope=0.005
Boundary for River Rch & Prof#=GERONIMO TRIBUTA,Reach-1,4
Up Type=0
Dn Type=3
Dn Slope=0.005
Boundary for River Rch & Prof#=GERONIMO TRIBUTA,Reach-1,5
Up Type=0
Dn Type=3
Dn Slope=0.005
Boundary for River Rch & Prof#=GERONIMO TRIBUTA,Reach-1,6
Up Type=0
Dn Type=3
Dn Slope=0.005
Boundary for River Rch & Prof#=GERONIMO TRIBUTA,Reach-1,7
Up Type=0
Dn Type=3
Dn Slope=0.005

--- GERONIMO TRIBUTARY 6.g01 (geometry) ---

Geom Title=Existing Conditions
Program Version=4.10

River Reach=GERONIMO TRIBUTA,Reach-1
Reach XY= 30
        2295675.       13778025.      2296368.81     13777432.82
      2296516.69     13777421.87      2296571.36     13777332.76
       2296684.7      13777364.8      2296908.33     13777091.65
      2297385.62      13776725.6      2297495.03     13776774.91
      2298209.79     13776775.51       2298385.5      13776873.8
      2298969.06     13776927.26      2299477.53     13777130.77
      2299537.04     13777223.76       2299631.7     13777184.17
      2299899.88     13777375.29      2300423.53     13777321.46
      2300811.79     13776938.62      2300959.66     13776874.95
      2301576.55     13777371.25      2301819.07     13777377.24
      2302781.46     13777682.74      2302885.52     13777934.79
      2303369.63     13778472.63      2303371.98     13778566.66
      2303282.01     13778624.81      2303361.62     13778711.63
      2303573.54     13778728.54       2303722.7     13778869.17
      2303980.94     13778972.74        2304325.       13779025.

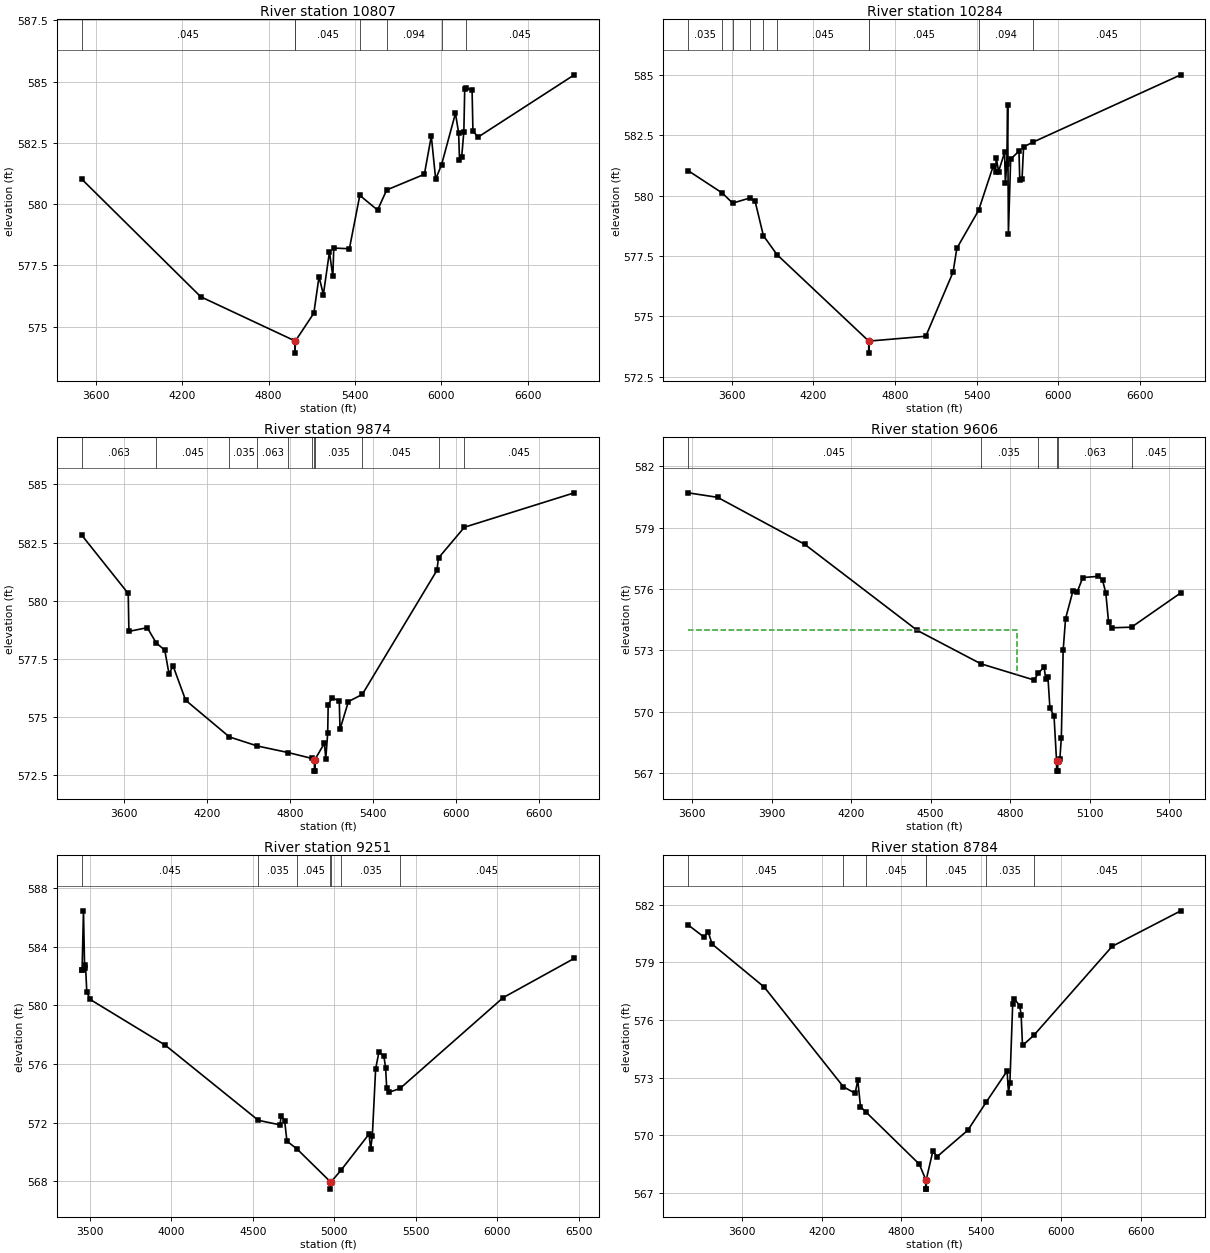
Type RM Length L Ch R = 1 ,10807   ,523,523,523
BEGIN DESCRIPTION:
GERONIMO TRIBUTARY 6 23.0
END DESCRIPTION:
XS GIS Cut Line= 3
      2296365.47     13779314.82      2295787.36     13778007.55
        2294127.     13776909.32
#Sta/Elev= 30
  3502.1  581.03  4329.5  576.22  4982.9  574.42  4983.1  573.92  4986.9  574.42
  5114.2  575.55  5150.4  577.04  5180.5  576.31  5222.6  578.05  5246.1  577.05
  5252.7  578.21    5361  578.18  5433.3  580.36  5556.6  579.76    5620  580.58
  5881.5  581.22  5929.7  582.78  5959.8  581.02  6000.7  581.61  6097.3  583.71
  6119.3  582.91  6125.3  581.82  6140.4  581.92  6155.5  582.96  6161.5  584.69
  6173.2  584.74  6212.6  584.66  6218.6  582.98  6254.7  582.74  6922.2  585.28
#Mann= 7 ,-1 , 0
  3502.1    .045       0  4982.9    .045       0  4986.9    .045       0
  5433.3    .035       0    5620    .094       0  6000.7    .035       0
  6173.2    .045       0
Bank Sta=4982.9,4986.9
XS Rating Curve= 0 ,0
Exp/Cntr=0.3,0.1

Type RM Length L Ch R = 1 ,10284   ,410,410,410
BEGIN DESCRIPTION:
GERONIMO TRIBUTARY 6 22.0
END DESCRIPTION:
XS GIS Cut Line= 3
      2296490.48     13779288.79      2296177.98      13777663.8
        2294425.       13776775.
#Sta/Elev= 30
  3278.4  581.04  3529.7  580.11  3606.5  579.69  3731.3   579.9  3771.1  579.77
  3832.1  578.34  3932.9  577.55    4606  573.97  4606.2  573.47    4610  573.97
  5025.3  574.17  5225.7  576.83  5253.6  577.82  5413.2  579.39  5520.8  581.23
  5537.5  580.96  5543.1  581.57  5559.8     581  5604.3  581.79  5609.9  580.53
  5620.4  581.31  5626.6  583.75  5632.2  578.42  5648.8  581.51    5710  581.85
  5715.6  580.63  5732.3  580.68  5743.8  582.02  5809.8  582.21  6898.6  585.01
#Mann= 10 ,-1 , 0
  3278.4    .035       0  3529.7    .045       0  3606.5    .035       0
  3731.3    .063       0  3832.1    .035       0  3932.9    .045       0
    4606    .045       0    4610    .045       0  5413.2    .094       0
  5809.8    .045       0
Bank Sta=4606,4610
XS Rating Curve= 0 ,0
Exp/Cntr=0.3,0.1

Type RM Length L Ch R = 1 ,9874    ,268,268,268
BEGIN DESCRIPTION:
GERONIMO TRIBUTARY 6 21.0
END DESCRIPTION:
XS GIS Cut Line= 3
        2296575.     13779124.99      2296443.61      13777351.3
      2294775.03     13776725.01
#Sta/Elev= 30
  3295.4  582.83  3632.6  580.31  3637.6  578.68  3770.4  578.84  3834.2  578.19
    3897  577.87  3927.1  576.86  3957.2  577.19  4047.4  575.72    4364  574.14
  4566.5  573.75  4787.2  573.47  4957.5  573.22  4977.9  573.17  4978.2  572.67
  4981.8  572.67    4982  573.17  5050.2  573.87  5060.2  573.21    5074   574.3
  5077.7  575.53    5108  575.83  5157.8  575.67  5163.1  574.47  5223.6  575.66
    5324  575.97  5862.9   581.3  5874.9  581.84    6062  583.16  6856.2  584.64
#Mann= 11 ,-1 , 0
  3295.4    .063       0  3834.2    .045       0    4364    .035       0
  4566.5    .063       0  4787.2    .045       0  4957.5    .035       0
  4977.9    .035       0    4982    .035       0    5324    .045       0
  5874.9     .07       0    6062    .045       0
Bank Sta=4977.9,4982
XS Rating Curve= 0 ,0
Exp/Cntr=0.3,0.1

Type RM Length L Ch R = 1 ,9606    ,355,355,355
BEGIN DESCRIPTION:
GERONIMO TRIBUTARY 6 20.5
END DESCRIPTION:
XS GIS Cut Line= 3
      2297345.12     13778606.82      2296569.26     13777239.53
      2296311.83     13777109.71
#Sta/Elev= 30
    3584  580.71  3695.5  580.49  4024.3  578.19  4449.8  573.97  4689.1  572.34
  4891.1  571.54  4905.9  571.87  4928.6  572.18  4934.4  571.58  4942.8  571.69
  4950.3  570.17  4965.8  569.79  4975.4  567.58  4975.7  567.08  4979.6  567.08
  4979.9  567.58  4987.8  567.66  4993.5  568.72  5000.3  572.99  5009.4  574.55
  5036.8  575.88  5052.7  575.83  5074.3  576.56  5133.4  576.62  5149.3  576.42
  5161.3  575.81  5171.9  574.36  5183.3   574.1  5258.4  574.13  5444.4  575.81
#Mann= 6 ,-1 , 0
    3584    .045       0  4689.1    .035       0  4905.9    .063       0
  4975.4     .05       0  4979.9    .063       0  5258.4    .045       0
#XS Ineff= 2 , 0
       0    4825     574               0
Permanent Ineff=
       F       F
Bank Sta=4975.4,4979.9
XS Rating Curve= 0 ,0
Exp/Cntr=0.3,0.1

Type RM Length L Ch R = 1 ,9251    ,467,467,467
BEGIN DESCRIPTION:
GERONIMO TRIBUTARY 6 20.0
END DESCRIPTION:
XS GIS Cut Line= 4
      2297384.18     13778536.53      2297152.35     13777406.36
        2296875.       13777125.      2295424.98       13776875.
#Sta/Elev= 30
  3450.9  582.43  3454.2  582.43  3462.7  586.45  3469.7  582.54  3474.9  582.76
  3483.1  580.92  3503.5  580.41  3962.9   577.3  4534.4  572.17  4667.3  571.86
  4674.4  572.48  4695.6  572.15  4709.7  570.75  4771.1  570.22  4976.2  567.98
  4976.5  567.48  4980.8  567.98  5041.2  568.77  5212.8  571.23  5222.9  570.22
  5233.1  571.09  5253.4  575.68  5273.7  576.83  5304.1  576.53  5314.3  575.77
  5321.4  574.34  5334.6  574.08  5402.7  574.34  6034.7  580.53  6471.1  583.21
#Mann= 7 ,-1 , 0
  3450.9    .045       0  4534.4    .035       0  4771.1    .045       0
  4976.2    .045       0  4980.8    .045       0  5041.2    .035       0
  5402.7    .045       0
Bank Sta=4976.2,4980.8
XS Rating Curve= 0 ,0
Exp/Cntr=0.3,0.1

Type RM Length L Ch R = 1 ,8784    ,453,453,453
BEGIN DESCRIPTION:
GERONIMO TRIBUTARY 6 19.0
END DESCRIPTION:
XS GIS Cut Line= 3
        2297425.     13778624.97        2297225.       13776825.
      2295425.01       13776225.
#Sta/Elev= 30
  3193.5  580.96  3314.2  580.32  3344.4  580.61  3374.6  579.96    3767  577.72
  4362.7  572.53  4451.2  572.19  4471.3  572.88  4491.4  571.49  4531.7  571.22
  4934.1   568.5  4982.1   567.7  4982.4   567.2  4986.4   567.2  4986.7   567.7
  5036.2  569.18  5067.8  568.89  5299.7  570.27  5437.6  571.73  5594.8  573.35
  5605.4  572.22  5615.9  572.74    5637  576.86  5647.5  577.12  5689.7  576.75
  5700.3  576.29  5710.8  574.68    5795   575.2  6385.4  579.84  6901.9  581.69
#Mann= 7 ,-1 , 0
  3193.5    .045       0  4362.7    .035       0  4531.7    .045       0
  4982.1    .045       0  4986.7    .045       0  5437.6    .035       0
    5795    .045       0
Bank Sta=4982.1,4986.7
XS Rating Curve= 0 ,0
Exp/Cntr=0.3,0.1

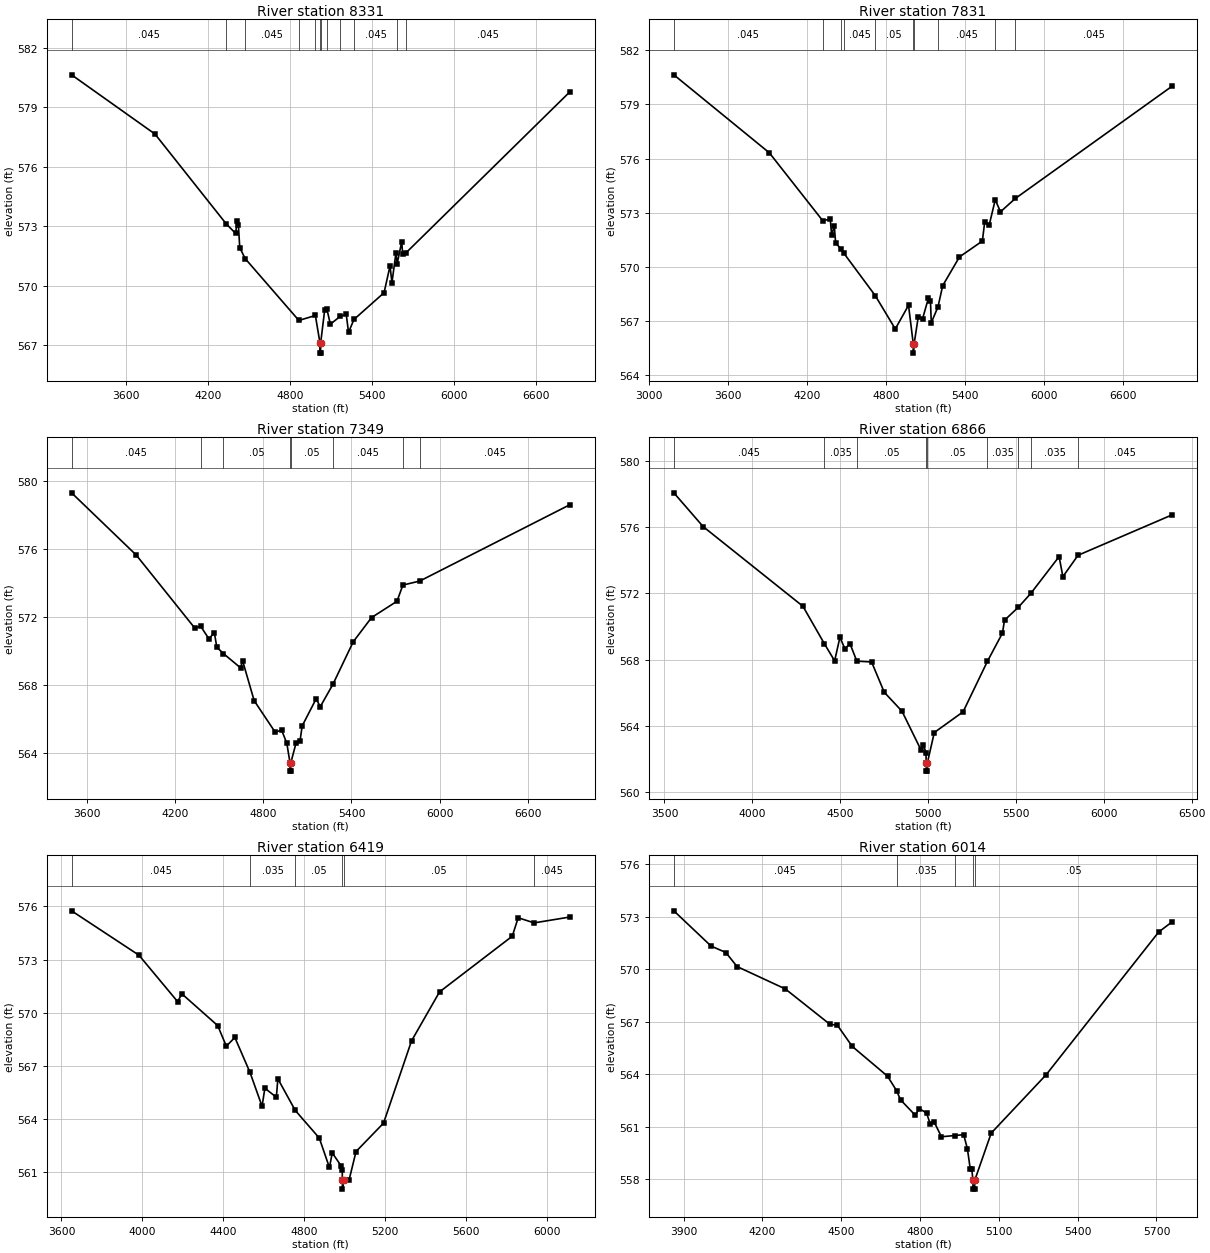
Type RM Length L Ch R = 1 ,8331    ,500,500,500
BEGIN DESCRIPTION:
GERONIMO TRIBUTARY 6 18.0
END DESCRIPTION:
XS GIS Cut Line= 3
        2297625.     13778575.01        2297625.       13776775.
      2297225.01     13774975.02
#Sta/Elev= 30
    3200  580.64    3810  577.65  4329.3  573.13    4400  572.63    4410  573.26
    4420  573.05    4430  571.91  4469.8  571.36  4862.3  568.24    4983  568.49
  5016.9  567.09  5017.2  566.59  5021.2  566.59  5021.5  567.09  5051.2  568.78
  5067.6  568.81  5092.2  568.05  5163.7  568.44  5208.7  568.55  5225.4  567.64
  5265.2  568.29  5485.3  569.64  5528.9  570.99  5542.9  570.15  5572.4  571.66
  5581.2  571.11  5614.7  572.22  5621.1  571.58  5643.7  571.64  6843.9  579.78
#Mann= 12 ,-1 , 0
    3200    .045       0  4329.3    .035       0  4469.8    .045       0
  4862.3     .05       0    4983     .07       0  5016.9     .05       0
  5021.5     .07       0  5067.6     .05       0  5163.7    .035       0
  5265.2    .045       0  5581.2    .035       0  5643.7    .045       0
Bank Sta=5016.9,5021.5
XS Rating Curve= 0 ,0
Exp/Cntr=0.3,0.1

Type RM Length L Ch R = 1 ,7831    ,482,482,482
BEGIN DESCRIPTION:
GERONIMO TRIBUTARY 6 17.0
END DESCRIPTION:
XS GIS Cut Line= 3
        2297925.     13778575.02        2298125.       13776775.
      2297324.99     13774974.97
#Sta/Elev= 30
  3188.8  580.64  3913.3  576.32  4318.3  572.56  4376.1  572.64  4386.1  571.74
  4406.3  572.28  4416.3  571.34    4454  571.01  4477.5  570.77  4716.8  568.41
  4869.1  566.56  4969.7  567.87  5005.8  565.72  5006.3  565.22  5011.8  565.72
  5043.7  567.24  5076.5  567.13  5120.3  568.26    5136  568.13  5142.2  566.91
  5193.2  567.78    5229  568.96  5356.2  570.55    5530  571.43  5547.1  572.46
  5581.9  572.32  5627.8  573.72  5667.4  573.05  5780.3  573.79  6969.7  580.01
#Mann= 10 ,-1 , 0
  3188.8    .045       0  4318.3    .035       0    4454     .05       0
  4477.5    .045       0  4716.8     .05       0  5005.8     .05       0
  5011.8     .05       0  5193.2    .045       0  5627.8    .035       0
  5780.3    .045       0
Bank Sta=5005.8,5011.8
XS Rating Curve= 0 ,0
Exp/Cntr=0.3,0.1

Type RM Length L Ch R = 1 ,7349    ,483,483,483
BEGIN DESCRIPTION:
GERONIMO TRIBUTARY 6 16.0
END DESCRIPTION:
XS GIS Cut Line= 3
      2298025.01     13778274.97        2298575.       13776875.
      2297575.01     13775275.02
#Sta/Elev= 30
  3495.4   579.3  3935.9  575.64  4334.1  571.35  4374.1  571.46  4430.1  570.72
    4467  571.09  4483.8  570.23  4528.4  569.86    4645  569.02  4659.4  569.43
    4738  567.09  4881.6  565.23  4924.3  565.37  4960.2  564.59  4981.6  563.45
  4982.1  562.95  4987.2  562.95  4987.7  563.45  5022.5  564.58  5049.6   564.7
    5065  565.61  5159.3  567.19  5188.2  566.74  5273.9  568.05  5412.3  570.55
  5536.7  571.97    5710  572.93  5750.1  573.88  5865.7  574.12  6886.3   578.6
#Mann= 8 ,-1 , 0
  3495.4    .045       0  4374.1    .035       0  4528.4     .05       0
  4981.6     .05       0  4987.7     .05       0  5273.9    .045       0
  5750.1    .035       0  5865.7    .045       0
Bank Sta=4981.6,4987.7
XS Rating Curve= 0 ,0
Exp/Cntr=0.3,0.1

Type RM Length L Ch R = 1 ,6866    ,447,447,447
BEGIN DESCRIPTION:
GERONIMO TRIBUTARY 6 15.0
END DESCRIPTION:
XS GIS Cut Line= 3
        2298225.       13778175.        2299025.       13776975.
      2299525.02     13775674.96
#Sta/Elev= 30
  3553.6  578.07  3720.4  576.03  4288.2  571.22  4409.6  568.97  4468.5  567.93
  4498.6  569.35  4527.1  568.65  4555.6  568.97  4594.8  567.91  4678.8  567.86
  4750.9  566.03  4851.6  564.89  4959.8  562.55  4973.3  562.85  4988.3  562.39
  4989.4  561.77  4989.9  561.27  4995.8  561.27  4996.3  561.77  5035.5   563.6
  5199.4  564.85  5337.9   567.9  5423.3   569.6  5435.1  570.38  5514.6  571.17
  5585.6  572.01  5745.8  574.22  5767.2  573.01  5853.5   574.3  6388.7  576.74
#Mann= 9 ,-1 , 0
  3553.6    .045       0  4409.6    .035       0  4594.8     .05       0
  4989.4     .05       0  4996.3     .05       0  5337.9    .035       0
  5514.6     .05       0  5585.6    .035       0  5853.5    .045       0
Bank Sta=4989.4,4996.3
XS Rating Curve= 0 ,0
Exp/Cntr=0.3,0.1

Type RM Length L Ch R = 1 ,6419    ,405,405,405
BEGIN DESCRIPTION:
GERONIMO TRIBUTARY 6 14.0
END DESCRIPTION:
XS GIS Cut Line= 3
      2298524.99     13778125.01        2299425.       13777125.
        2299625.     13776025.01
#Sta/Elev= 30
  3649.9  575.75  3982.9  573.25  4174.2  570.63  4195.2  571.07  4372.3  569.28
  4414.9  568.12  4457.1  568.61    4532  566.64  4591.7  564.73  4605.5  565.75
  4662.3  565.24  4669.8  566.28  4755.6   564.5  4874.6  562.94  4924.6  561.28
  4938.8   562.1  4981.5  561.39  4988.2  561.16  4988.5  560.56    4989  560.06
  4995.4  560.56    5022  560.58  5056.3  562.18  5192.2  563.78  5330.7  568.42
  5469.2  571.18  5828.7  574.32  5857.9  575.36  5936.8  575.07  6113.3   575.4
#Mann= 6 ,-1 , 0
  3649.9    .045       0    4532    .035       0  4755.6     .05       0
  4988.5     .05       0  4995.4     .05       0  5936.8    .045       0
Bank Sta=4988.5,4995.4
XS Rating Curve= 0 ,0
Exp/Cntr=0.3,0.1

Type RM Length L Ch R = 1 ,6014    ,438,438,438
BEGIN DESCRIPTION:
GERONIMO TRIBUTARY 6 13.0
END DESCRIPTION:
XS GIS Cut Line= 3
      2298924.98     13778075.02        2299725.       13777275.
      2299574.99     13776524.95
#Sta/Elev= 30
  3863.2  573.33  4004.7  571.32  4061.2  570.95  4103.6  570.15  4287.5  568.87
  4457.2  566.85  4485.5   566.8  4542.1  565.59  4676.4  563.89  4710.6  563.07
  4725.9  562.54  4782.5  561.65  4796.6  562.04  4824.9  561.79    4839  561.16
  4853.2   561.3  4881.5  560.43  4932.5   560.5  4966.3  560.55  4980.5  559.74
  4991.1  558.61  4997.1  558.61  5001.3  557.94  5001.8  557.44  5007.8  557.44
  5008.3  557.94  5071.1  560.64  5280.1  563.97  5708.5  572.12  5759.5   572.7
#Mann= 5 ,-1 , 0
  3863.2    .045       0  4710.6    .035       0  4932.5     .05       0
  5001.3     .05       0  5008.3     .05       0
Bank Sta=5001.3,5008.3
XS Rating Curve= 0 ,0
Exp/Cntr=0.3,0.1

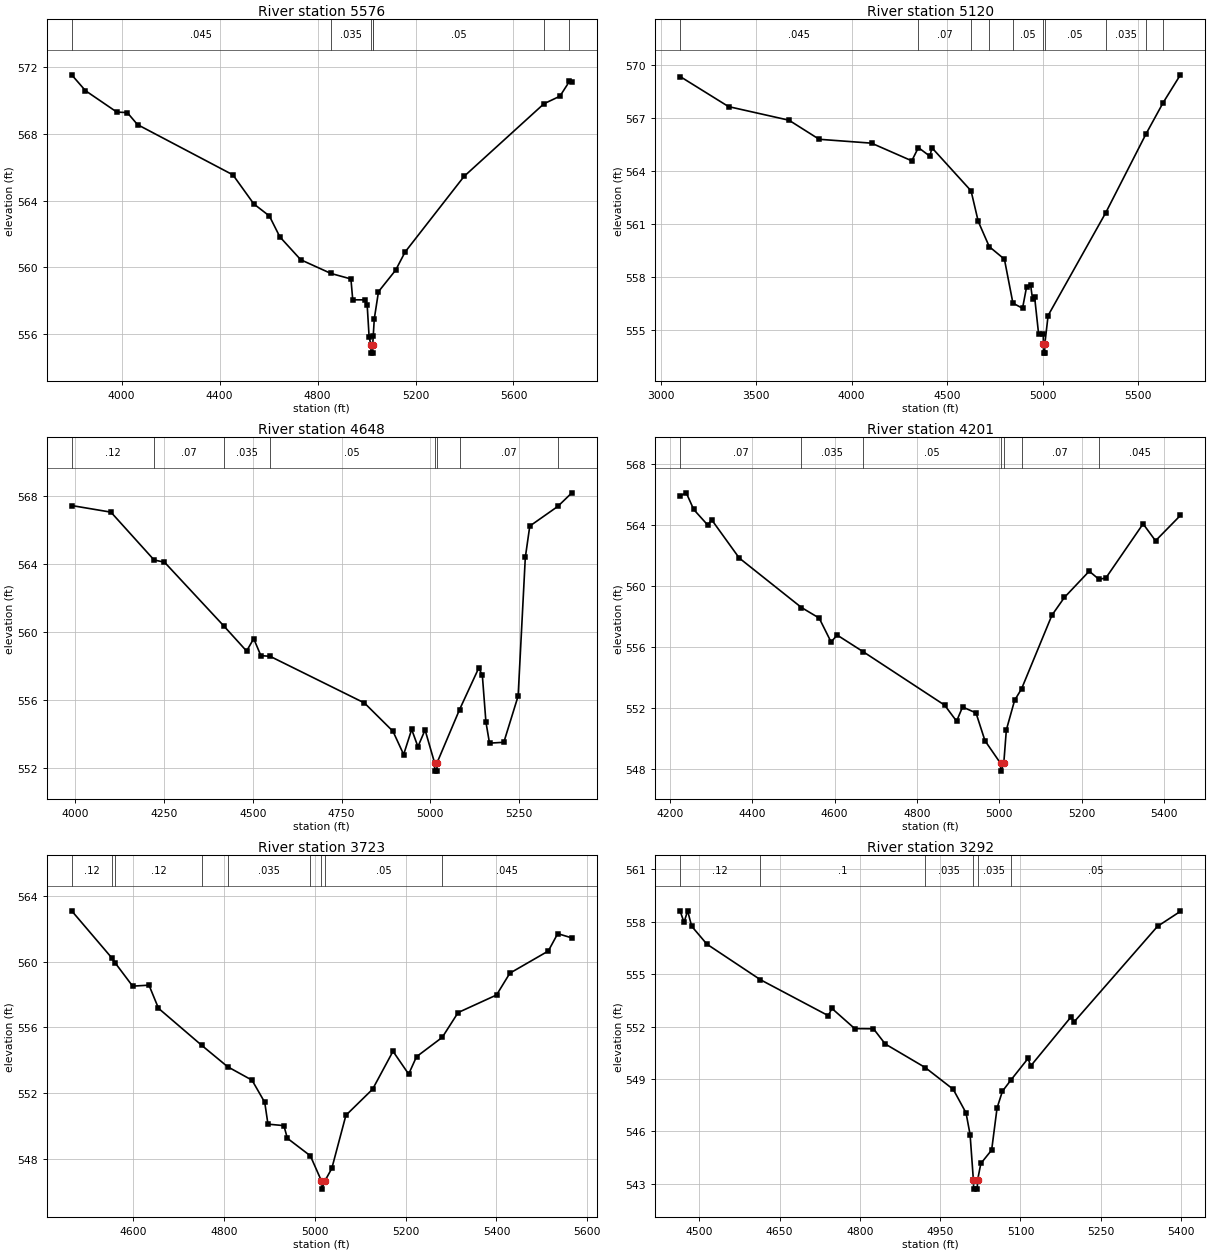
Type RM Length L Ch R = 1 ,5576    ,456,456,456
BEGIN DESCRIPTION:
GERONIMO TRIBUTARY 6 12.0
END DESCRIPTION:
XS GIS Cut Line= 3
      2299325.02     13778274.97        2300125.       13777375.
      2299874.99     13776574.98
#Sta/Elev= 30
    3796  571.53  3852.4  570.58  3980.4   569.3    4023  569.27  4064.8  568.55
  4454.5  565.54  4539.8   563.8  4603.3  563.08    4646  561.83  4731.3  560.46
  4854.6  559.64  4936.2  559.31  4943.7  558.06    4993  558.06  5002.7  557.73
  5010.6  555.82  5018.1  555.37  5018.6  554.87  5024.7  554.87  5025.2  555.37
  5027.3  555.88  5031.6  556.92  5048.8  558.55    5119  559.84  5157.3  560.92
  5398.2  565.45  5724.5   569.8  5789.6  570.25  5828.6  571.14  5838.3  571.08
#Mann= 7 ,-1 , 0
    3796    .045       0  4854.6    .035       0  5018.1    .035       0
  5025.2    .035       0  5027.3     .05       0  5724.5    .035       0
  5828.6     .05       0
Bank Sta=5018.1,5025.2
XS Rating Curve= 0 ,0
Exp/Cntr=0.3,0.1

Type RM Length L Ch R = 1 ,5120    ,472,472,472
BEGIN DESCRIPTION:
GERONIMO TRIBUTARY 6 11.0
END DESCRIPTION:
XS GIS Cut Line= 3
        2299925.       13779025.        2300525.       13777225.
      2300124.99     13776624.98
#Sta/Elev= 30
  3102.7  569.36  3355.7  567.66  3671.9  566.89    3830  565.81  4104.1  565.59
  4314.9  564.59  4349.4  565.34  4409.8  564.85  4420.3  565.33  4625.2  562.89
  4662.8  561.16  4720.5  559.73  4799.8  559.02  4844.4  556.53  4894.7  556.24
  4915.7  557.44  4936.8  557.57  4947.4  556.74  4957.9  556.88    4979  554.77
  5003.1  554.76    5004   554.2  5004.5   553.7  5010.7   553.7  5011.2   554.2
  5028.6  555.83  5330.3  561.65  5540.5   566.1  5631.2  567.89  5721.2  569.46
#Mann= 10 ,-1 , 0
  3102.7    .045       0  4349.4     .07       0  4625.2    .045       0
  4720.5    .035       0  4844.4     .05       0    5004     .05       0
  5011.2     .05       0  5330.3    .035       0  5540.5     .05       0
  5631.2    .035       0
Bank Sta=5004,5011.2
XS Rating Curve= 0 ,0
Exp/Cntr=0.3,0.1

Type RM Length L Ch R = 1 ,4648    ,447,447,447
BEGIN DESCRIPTION:
GERONIMO TRIBUTARY 6 10.0
END DESCRIPTION:
XS GIS Cut Line= 3
        2300775.     13777924.96        2300875.       13776925.
        2300825.     13776524.97
#Sta/Elev= 30
  3990.2  567.45  4100.7  567.06  4222.2  564.24  4251.5  564.11  4419.4  560.33
  4482.6  558.87  4502.7   559.6  4522.8   558.6  4548.8  558.56  4814.3  555.81
  4894.7  554.14  4924.8  552.77  4947.4  554.25    4965  553.23  4985.1  554.22
  5011.7  552.29  5012.2  551.79  5018.5  551.79    5019  552.29  5082.2  555.42
  5136.2  557.87  5146.3  557.45  5156.4  554.69  5166.5  553.44  5206.8  553.49
  5247.1  556.22  5267.3  564.39  5279.9  566.24  5358.8   567.4  5398.3   568.2
#Mann= 8 ,-1 , 0
  3990.2     .12       0  4222.2     .07       0  4419.4    .035       0
  4548.8     .05       0  5011.7     .05       0    5019     .05       0
  5082.2     .07       0  5358.8    .045       0
Bank Sta=5011.7,5019
XS Rating Curve= 0 ,0
Exp/Cntr=0.3,0.1

Type RM Length L Ch R = 1 ,4201    ,478,478,478
BEGIN DESCRIPTION:
GERONIMO TRIBUTARY 6 9.0
END DESCRIPTION:
XS GIS Cut Line= 3
      2300924.98     13777775.04        2301225.       13777075.
        2301275.     13776624.99
#Sta/Elev= 30
  4225.4   565.9    4240   566.1  4258.1  565.01  4292.5  563.98  4301.6  564.34
  4368.7  561.83  4519.8  558.59  4562.7   557.9  4591.7  556.33  4606.2  556.79
    4670  555.69  4867.3   552.2  4896.4  551.15  4910.9  552.08  4943.5  551.69
  4965.3  549.87  5003.4  548.38  5003.9  547.88  5010.9  548.38  5017.2  550.58
  5037.3  552.52    5054  553.26  5127.9  558.09  5158.1  559.25  5218.4  560.97
  5241.9  560.44  5258.7  560.52  5349.2  564.07  5379.4  562.96  5439.8  564.62
#Mann= 7 ,-1 , 0
  4225.4     .07       0  4519.8    .035       0    4670     .05       0
  5003.4     .05       0  5010.9     .05       0    5054     .07       0
  5241.9    .045       0
Bank Sta=5003.4,5010.9
XS Rating Curve= 0 ,0
Exp/Cntr=0.3,0.1

Type RM Length L Ch R = 1 ,3723    ,431,431,431
BEGIN DESCRIPTION:
GERONIMO TRIBUTARY 6 8.0
END DESCRIPTION:
XS GIS Cut Line= 3
      2301225.02     13777774.97        2301575.       13777375.
      2301725.01     13776824.96
#Sta/Elev= 30
  4464.4   563.1  4552.8  560.23  4560.9   559.9  4598.7  558.51  4634.7  558.57
  4655.6  557.16  4750.5  554.91  4807.8   553.6  4861.6  552.78  4889.6  551.43
  4896.7   550.1  4931.8  550.01  4939.4  549.24  4990.1  548.17  5014.5  546.64
    5015  546.14  5022.1  546.64  5037.3   547.4  5068.4  550.64  5127.2  552.23
  5172.1  554.54  5206.6  553.15  5223.9  554.21  5280.6  555.39  5315.5   556.9
  5400.1  557.97  5429.5   559.3  5514.1  560.65  5534.9  561.71    5566  561.45
#Mann= 9 ,-1 , 0
  4464.4     .12       0  4552.8     .07       0  4560.9     .12       0
  4750.5      .1       0  4807.8    .035       0  4990.1     .05       0
  5014.5     .05       0  5022.1     .05       0  5280.6    .045       0
Bank Sta=5014.5,5022.1
XS Rating Curve= 0 ,0
Exp/Cntr=0.3,0.1

Type RM Length L Ch R = 1 ,3292    ,482,482,482
BEGIN DESCRIPTION:
GERONIMO TRIBUTARY 6 7.0
END DESCRIPTION:
XS GIS Cut Line= 3
      2301625.01     13777874.99        2301975.       13777475.
        2302025.     13777075.01
#Sta/Elev= 30
  4464.2   558.6  4471.3  557.97    4478  558.63  4485.5  557.75    4514  556.72
  4614.1  554.68  4740.9  552.62  4747.5  553.04  4790.2  551.88  4825.3  551.87
  4847.2     551  4921.9  549.65  4974.3   548.4  4998.2  547.05  5005.8  545.81
    5012  543.18  5012.5  542.68  5019.2  542.68  5019.7  543.18  5025.9  544.15
  5046.1  544.92  5056.2  547.33  5066.2  548.29  5082.8  548.96  5114.1  550.17
  5119.1  549.74  5194.7  552.56  5199.8  552.25    5356  557.74  5398.8   558.6
#Mann= 6 ,-1 , 0
  4464.2     .12       0  4614.1      .1       0  4921.9    .035       0
    5012    .035       0  5019.7    .035       0  5082.8     .05       0
Bank Sta=5012,5019.7
XS Rating Curve= 0 ,0
Exp/Cntr=0.3,0.1

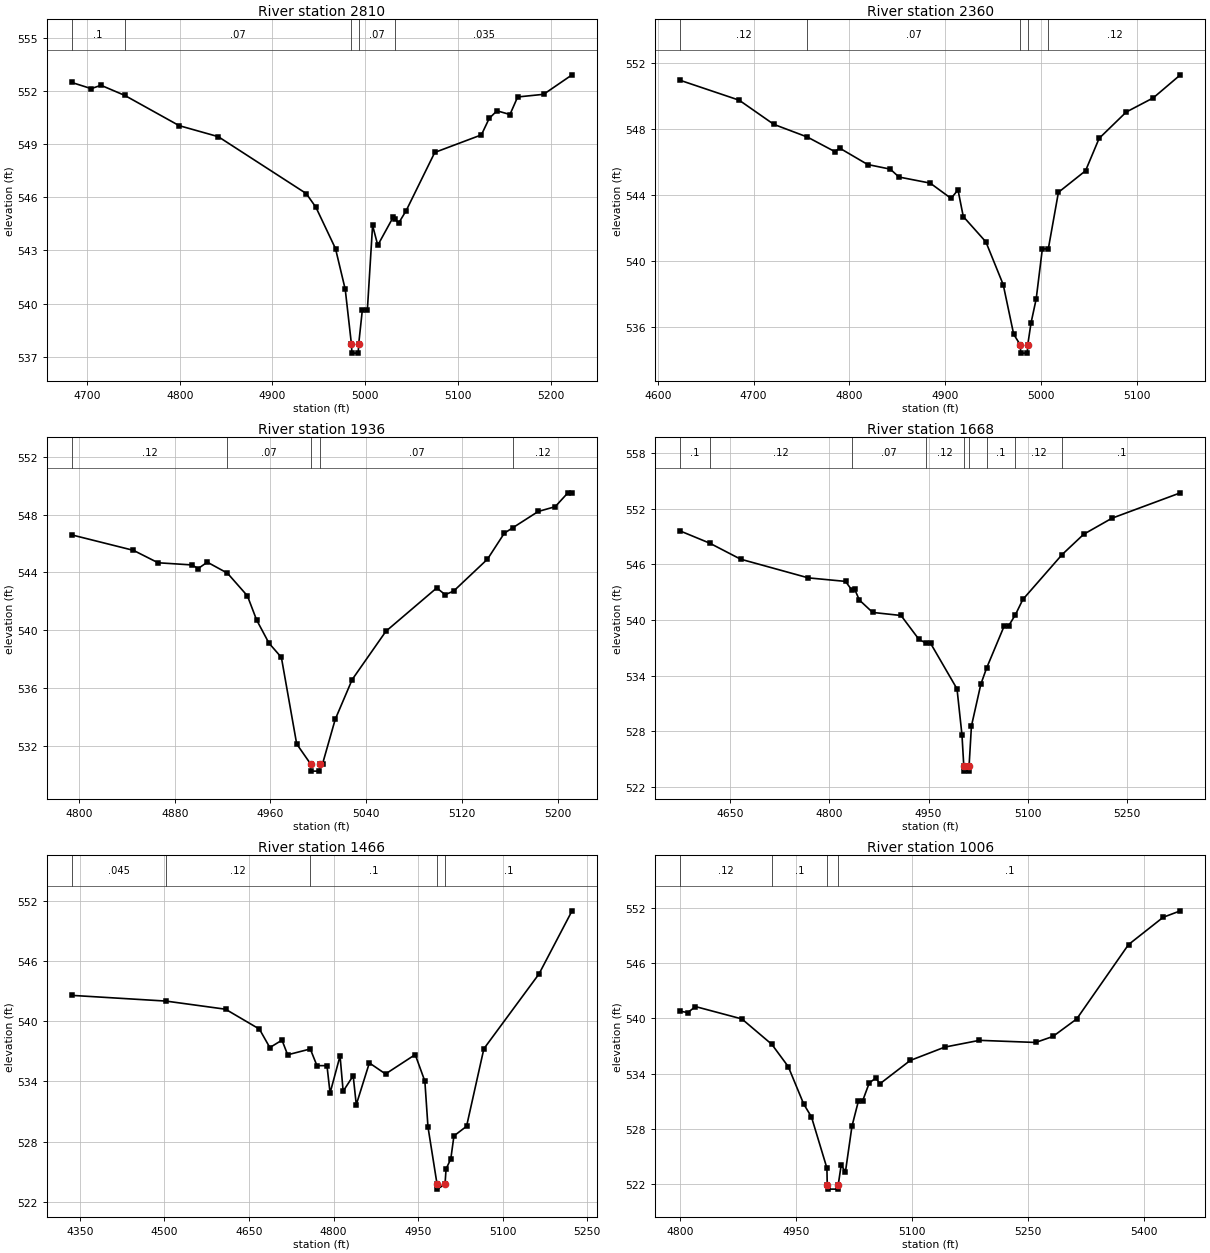
Type RM Length L Ch R = 1 ,2810    ,450,450,450
BEGIN DESCRIPTION:
GERONIMO TRIBUTARY 6 6.0
END DESCRIPTION:
XS GIS Cut Line= 3
        2302325.       13777875.        2302425.       13777575.
      2302524.98     13777375.03
#Sta/Elev= 30
  4683.4  552.48  4704.5  552.13    4715  552.32  4740.6  551.75  4799.4  550.04
  4841.5  549.42  4936.4  546.21  4946.9  545.43    4968   543.1  4978.5   540.8
  4985.2   537.7  4985.7   537.2  4992.5   537.2    4993   537.7    4997  539.66
  5002.4  539.66    5008  544.41  5013.6  543.29  5030.4  544.89  5032.4  544.76
    5036  544.53  5044.3  545.25  5075.1  548.53  5125.4  549.52  5133.8  550.45
  5142.2  550.88  5156.2  550.67  5164.5  551.66  5192.5  551.81  5223.2  552.91
#Mann= 5 ,-1 , 0
  4683.4      .1       0  4740.6     .07       0  4985.2     .05       0
    4993     .07       0  5032.4    .035       0
Bank Sta=4985.2,4993
XS Rating Curve= 0 ,0
Exp/Cntr=0.3,0.1

Type RM Length L Ch R = 1 ,2360    ,424,424,424
BEGIN DESCRIPTION:
GERONIMO TRIBUTARY 6 5.0
END DESCRIPTION:
XS GIS Cut Line= 3
      2302474.99     13777875.01        2302825.       13777725.
      2302924.98     13777625.02
#Sta/Elev= 30
  4623.3  550.98    4685  549.77  4721.2   548.3  4756.2  547.53  4784.7  546.65
  4790.1  546.85  4819.1  545.86  4842.7  545.58  4851.8   545.1  4884.4  544.73
  4906.2   543.8  4913.4  544.32  4918.9   542.7  4942.5  541.16  4960.6  538.56
  4971.5  535.55  4978.4   534.9  4978.9   534.4  4985.7   534.4  4986.2   534.9
  4989.6  536.23    4995  537.69  5001.4  540.72  5007.7  540.75  5018.2  544.17
  5046.5  545.48  5060.7  547.45    5089  549.05  5117.2  549.91  5145.5  551.31
#Mann= 5 ,-1 , 0
  4623.3     .12       0  4756.2     .07       0  4978.4     .05       0
  4986.2     .07       0  5007.7     .12       0
Bank Sta=4978.4,4986.2
XS Rating Curve= 0 ,0
Exp/Cntr=0.3,0.1

Type RM Length L Ch R = 1 ,1936    ,268,268,268
BEGIN DESCRIPTION:
GERONIMO TRIBUTARY 6 4.0
END DESCRIPTION:
XS GIS Cut Line= 3
      2302824.98     13778125.01        2303025.       13778075.
      2303174.99     13777925.01
#Sta/Elev= 30
  4793.8   546.6  4845.4  545.53    4866  544.67  4894.3  544.52  4899.5  544.27
  4907.2  544.71    4924  543.95  4940.7  542.38  4948.4  540.71  4958.7  539.11
  4969.1  538.12  4981.9  532.13  4993.5  530.75    4994  530.25  5000.9  530.25
  5001.4  530.75  5003.5  530.75  5014.1  533.83  5028.3  536.59  5056.5  539.93
    5099  542.93    5106  542.46  5113.1  542.71  5141.4  544.92  5155.5  546.72
  5162.5  547.09  5183.8  548.22    5198  548.55  5208.6  549.51  5212.1  549.51
#Mann= 5 ,-1 , 0
  4793.8     .12       0    4924     .07       0  4993.5     .05       0
  5001.4     .07       0  5162.5     .12       0
Bank Sta=4993.5,5001.4
XS Rating Curve= 0 ,0
Exp/Cntr=0.3,0.1

Type RM Length L Ch R = 1 ,1668    ,202,202,202
BEGIN DESCRIPTION:
A19061
END DESCRIPTION:
XS GIS Cut Line= 3
      2302786.47     13778428.66      2303144.02     13778316.17
      2303429.28     13778063.06
#Sta/Elev= 30
  4574.3  549.61  4619.1  548.29  4665.8  546.56  4768.2  544.54  4824.4  544.16
  4834.2   543.2  4838.2  543.32  4845.3  542.15  4865.4  540.81  4908.3  540.48
  4935.4   537.9  4946.6  537.48  4953.1  537.46  4992.9  532.56  5000.4  527.59
  5003.2  524.18  5003.7  523.68  5010.6  523.68  5011.1  524.18  5014.7  528.54
  5028.9  533.06  5037.6   534.8    5064  539.31  5070.8  539.35  5081.1  540.55
  5092.4  542.21  5151.8  547.06  5184.4  549.25  5227.1  550.98  5330.5  553.72
#Mann= 9 ,-1 , 0
  4574.3      .1       0  4619.1     .12       0  4834.2     .07       0
  4946.6     .12       0  5003.2     .05       0  5011.1     .12       0
  5037.6      .1       0  5081.1     .12       0  5151.8      .1       0
Bank Sta=5003.2,5011.1
XS Rating Curve= 0 ,0
Exp/Cntr=0.3,0.1

Type RM Length L Ch R = 1 ,1466    ,460,460,460
BEGIN DESCRIPTION:
GERONIMO TRIBUTARY 6 3.0
END DESCRIPTION:
XS GIS Cut Line= 4
      2303252.49     13779067.44      2303225.87     13778648.04
        2303325.       13778425.      2303424.99     13778225.03
#Sta/Elev= 30
  4335.4  542.57  4502.8     542  4608.4  541.19  4668.5  539.21    4687  537.37
  4708.6  538.11  4718.6  536.65  4758.8  537.23  4770.6  535.57  4788.4  535.57
  4793.9  532.84  4811.6  536.54  4817.1  533.02  4834.9  534.56  4840.4  531.68
  4863.6  535.84  4892.3  534.74    4945  536.67  4962.1  534.02  4967.6  529.48
  4983.7  523.77  4984.2  523.27  4997.9  523.77  4999.7  525.28  5008.1  526.27
  5013.7  528.57  5036.1  529.53  5066.8  537.25  5164.6   544.7  5223.3  550.99
#Mann= 5 ,-1 , 0
  4335.4    .045       0  4502.8     .12       0  4758.8      .1       0
  4983.7     .05       0  4997.9      .1       0
Bank Sta=4983.7,4997.9
XS Rating Curve= 0 ,0
Exp/Cntr=0.3,0.1

Type RM Length L Ch R = 1 ,1006    ,472,472,472
BEGIN DESCRIPTION:
GERONIMO TRIBUTARY 6 2.0
END DESCRIPTION:
XS GIS Cut Line= 3
        2303425.     13778925.01        2303425.       13778725.
      2303624.99     13778325.02
#Sta/Elev= 30
  4800.4  540.76  4810.4  540.61  4820.4  541.26  4880.4  539.92  4919.1  537.17
  4940.4  534.75  4960.4  530.69  4970.4   529.3  4990.4  523.75  4990.8  521.97
  4991.3  521.47  5004.6  521.47  5005.1  521.97  5008.8  524.05  5014.4  523.37
  5022.8  528.29  5031.2  531.04  5036.7  531.06  5045.1  532.97  5053.5  533.51
  5059.1   532.9  5098.2  535.42    5143  536.87  5187.7   537.6  5260.4  537.37
  5282.7  538.02  5313.5  539.92  5380.5  547.98  5425.3  550.94  5447.6  551.64
#Mann= 4 ,-1 , 0
  4800.4     .12       0  4919.1      .1       0  4990.8     .05       0
  5005.1      .1       0
Bank Sta=4990.8,5005.1
XS Rating Curve= 0 ,0
Exp/Cntr=0.3,0.1

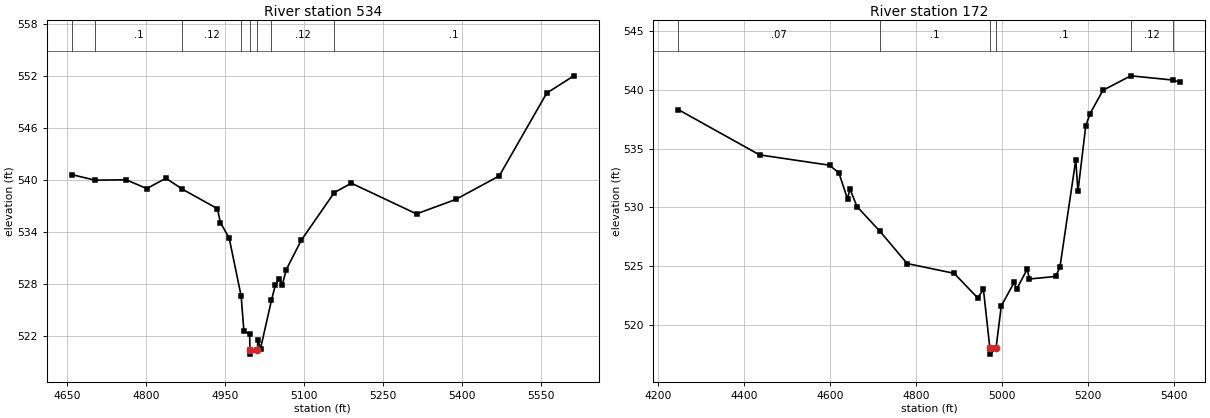
Type RM Length L Ch R = 1 ,534     ,362,362,362
BEGIN DESCRIPTION:
GERONIMO TRIBUTARY 6 1.0
END DESCRIPTION:
XS GIS Cut Line= 3
      2303525.04     13779074.98        2303825.       13778925.
      2303675.01     13778325.03
#Sta/Elev= 30
  4659.2  540.64  4703.2     540  4762.6  540.04  4801.7  539.03    4838  540.22
  4869.3  538.96  4935.9  536.71  4941.5  535.11  4958.2  533.33    4981  526.62
  4986.2  522.58  4997.1  522.26  4997.7  520.44  4998.2  519.94    5012  520.44
  5012.6  521.61  5017.8  520.58  5038.6  526.16  5046.1  527.94  5053.8  528.66
    5059   527.9  5066.7  529.69  5095.1  533.06  5157.9  538.57  5190.4  539.65
  5314.1  536.11  5388.8  537.78  5471.3  540.49  5561.5  550.04    5613  552.03
#Mann= 8 ,-1 , 0
  4659.2    .045       0  4703.2      .1       0  4869.3     .12       0
    4981      .1       0  4997.7     .05       0    5012      .1       0
  5038.6     .12       0  5157.9      .1       0
Bank Sta=4997.7,5012
XS Rating Curve= 0 ,0
Exp/Cntr=0.3,0.1

Type RM Length L Ch R = 1 ,172     ,0,0,0
BEGIN DESCRIPTION:
A19060
END DESCRIPTION:
XS GIS Cut Line= 4
      2303573.84     13779344.62      2304100.14     13779155.79
      2304196.56      13778902.7      2304208.61      13778565.2
#Sta/Elev= 30
    4247  538.32  4436.2  534.47  4598.8  533.59  4620.7  532.94  4640.8  530.71
  4646.1  531.59  4662.6  530.08  4716.2  527.97  4779.4  525.23  4888.6   524.4
  4943.5  522.31  4956.8  523.03  4971.8  518.03  4972.3  517.53  4986.1  518.03
  4998.3  521.62  5028.4  523.64  5033.8  523.04  5058.5  524.74  5063.9  523.92
  5124.7  524.13  5134.7  524.92  5171.6  534.05  5176.6  531.36  5194.8  536.94
  5204.8  537.98  5234.8  539.96  5299.4  541.19  5397.8  540.83  5414.7  540.63
#Mann= 6 ,-1 , 0
    4247     .07       0  4716.2      .1       0  4971.8     .05       0
  4986.1      .1       0  5299.4     .12       0  5397.8     .07       0
Bank Sta=4971.8,4986.1
XS Rating Curve= 0 ,0
Exp/Cntr=0.3,0.1

Chan Stop Cuts=-1
Use User Specified Reach Order=0
Composite Channel Slope=5