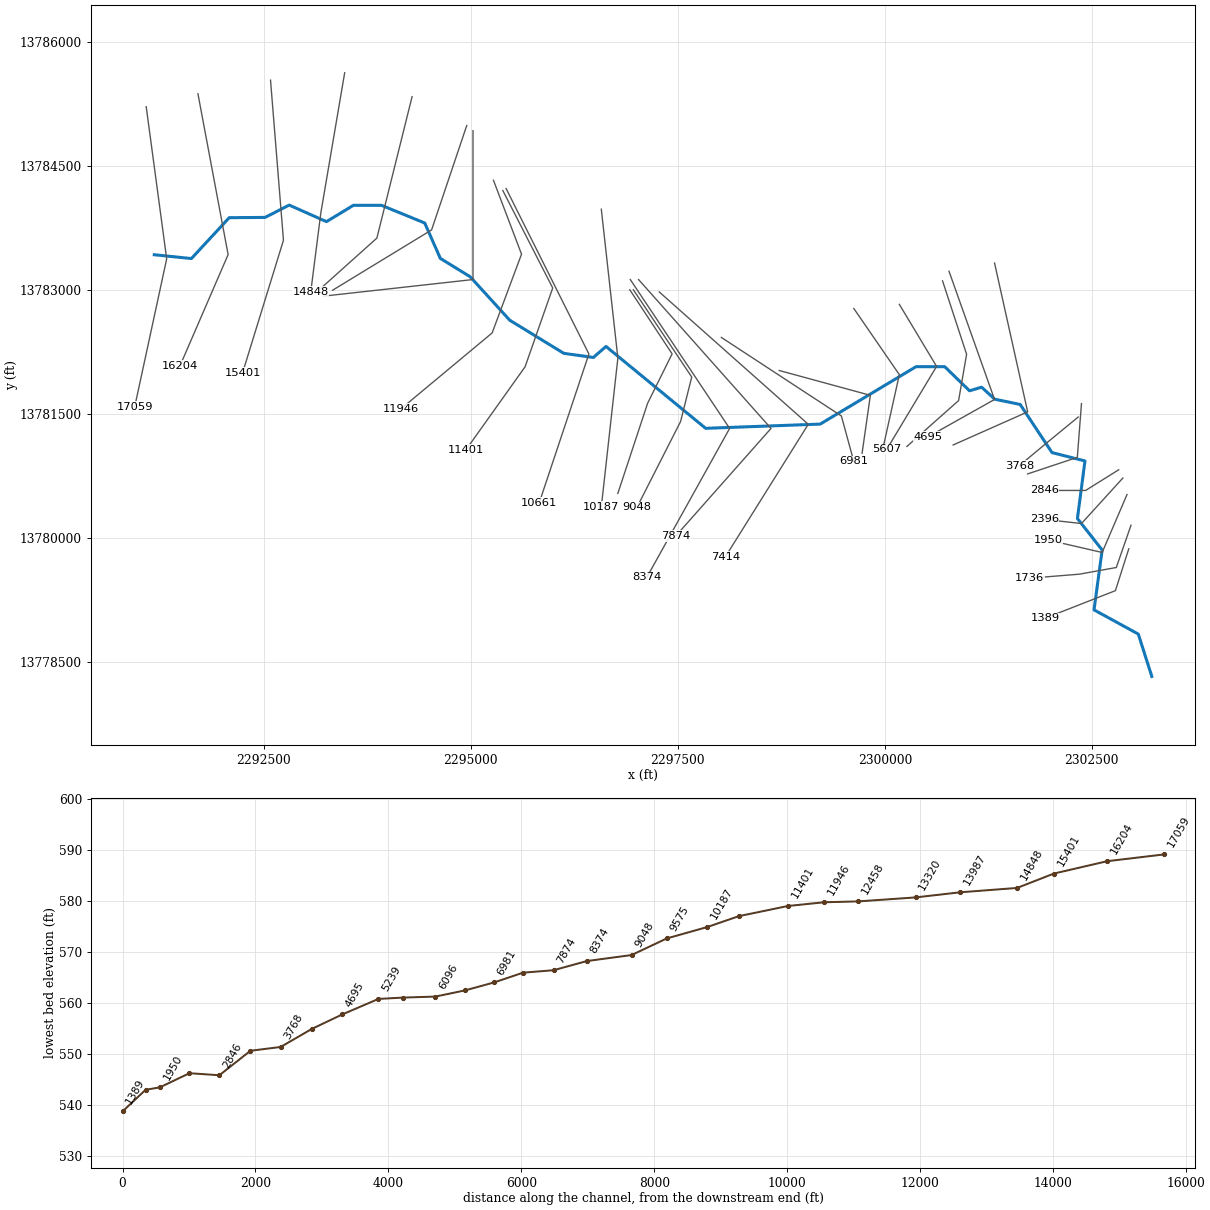
--- GERONIMO TRIBUTARY 7.prj (project) ---

Proj Title=GERONIMO TRIBUTARY 7 Base Level Engineering
Current Plan=p01
Default Exp/Contr=0.3,0.1
English Units
Geom File=g01
Flow File=f01
Plan File=p01
Y Axis Title=Elevation
X Axis Title(PF)=Main Channel Distance
X Axis Title(XS)=Station
BEGIN DESCRIPTION:
GERONIMO TRIBUTARY 7
END DESCRIPTION:
DSS Export Rating Curves= 0
DSS Export Rating Curve Sorted= 0
DSS Export Volume Flow Curves= 0
DXF OffsetX= 0
DXF OffsetY= 0
DXF ScaleX= 1
DXF ScaleY= 10

--- GERONIMO TRIBUTARY 7.p01 (plan) ---

Plan Title=Multiple Run
Short Identifier=Multiple
Geom File=g01
Flow File=f01
Subcritical Flow
K Sum by GR= 0
Std Step Tol= 0.01
Critical Tol= 0.01
Num of Std Step Trials= 20
Max Error Tol= 0.3
Flow Tol Ratio= 0.001
Split Flow NTrial= 30
Split Flow Tol= 0.02
Split Flow Ratio= 0.02
Log Output Level= 0
Friction Slope Method= 1
Unsteady Friction Slope Method= 2
Unsteady Bridges Friction Slope Method= 1
Parabolic Critical Depth
Global Vel Dist=  1 , 1 , 1
Global Log Level= 0
CheckData=True
Encroach Param= -1, 0, 0, 0
BEGIN DESCRIPTION:
Multiple Run
END DESCRIPTION:

--- GERONIMO TRIBUTARY 7.f01 (steady flow) ---

Flow Title=Multiple
Number of Profiles=7
Profile Names=10-year,25-year,50-year,1pct_min,100-year,1pct_plu,500-year
River Rch & RM= GERONIMO TRIBUTA,Reach-1,17059
     481     745     972     614    1224    2443    1924
River Rch & RM= GERONIMO TRIBUTA,Reach-1,14848
     693    1100    1459     934    1864    3720    3019
River Rch & RM= GERONIMO TRIBUTA,Reach-1,9575
    1011    1645    2219    1445    2883    5752    4824
Boundary for River Rch & Prof#=GERONIMO TRIBUTA,Reach-1,1
Up Type=0
Dn Type=3
Dn Slope=0.005
Boundary for River Rch & Prof#=GERONIMO TRIBUTA,Reach-1,2
Up Type=0
Dn Type=3
Dn Slope=0.005
Boundary for River Rch & Prof#=GERONIMO TRIBUTA,Reach-1,3
Up Type=0
Dn Type=3
Dn Slope=0.005
Boundary for River Rch & Prof#=GERONIMO TRIBUTA,Reach-1,4
Up Type=0
Dn Type=3
Dn Slope=0.005
Boundary for River Rch & Prof#=GERONIMO TRIBUTA,Reach-1,5
Up Type=0
Dn Type=3
Dn Slope=0.005
Boundary for River Rch & Prof#=GERONIMO TRIBUTA,Reach-1,6
Up Type=0
Dn Type=3
Dn Slope=0.005
Boundary for River Rch & Prof#=GERONIMO TRIBUTA,Reach-1,7
Up Type=0
Dn Type=3
Dn Slope=0.005

--- GERONIMO TRIBUTARY 7.g01 (geometry) ---

Geom Title=Existing Conditions
Program Version=4.10

River Reach=GERONIMO TRIBUTA,Reach-1
Reach XY= 30
        2291175.       13783425.      2291623.45     13783378.75
      2292080.67     13783873.02       2292514.5      13783876.2
      2292804.82      13784025.3      2293254.97     13783825.04
      2293580.93     13784022.76      2293919.06     13784022.74
      2294441.79     13783808.56      2294630.59     13783380.61
      2294991.67     13783158.35      2295468.94     13782633.14
      2296121.68     13782233.04      2296478.41     13782182.77
      2296631.67     13782316.04      2297835.43     13781326.05
      2299219.06     13781377.27      2300376.47     13782071.45
      2300723.45     13782071.25      2301022.45     13781779.99
      2301168.96     13781823.38      2301326.47     13781678.54
      2301634.81     13781614.49      2302018.79      13781032.8
      2302417.31     13780931.48      2302326.04     13780235.44
      2302625.04     13779855.02      2302526.62     13779131.03
      2303061.53     13778838.57        2303225.       13778325.

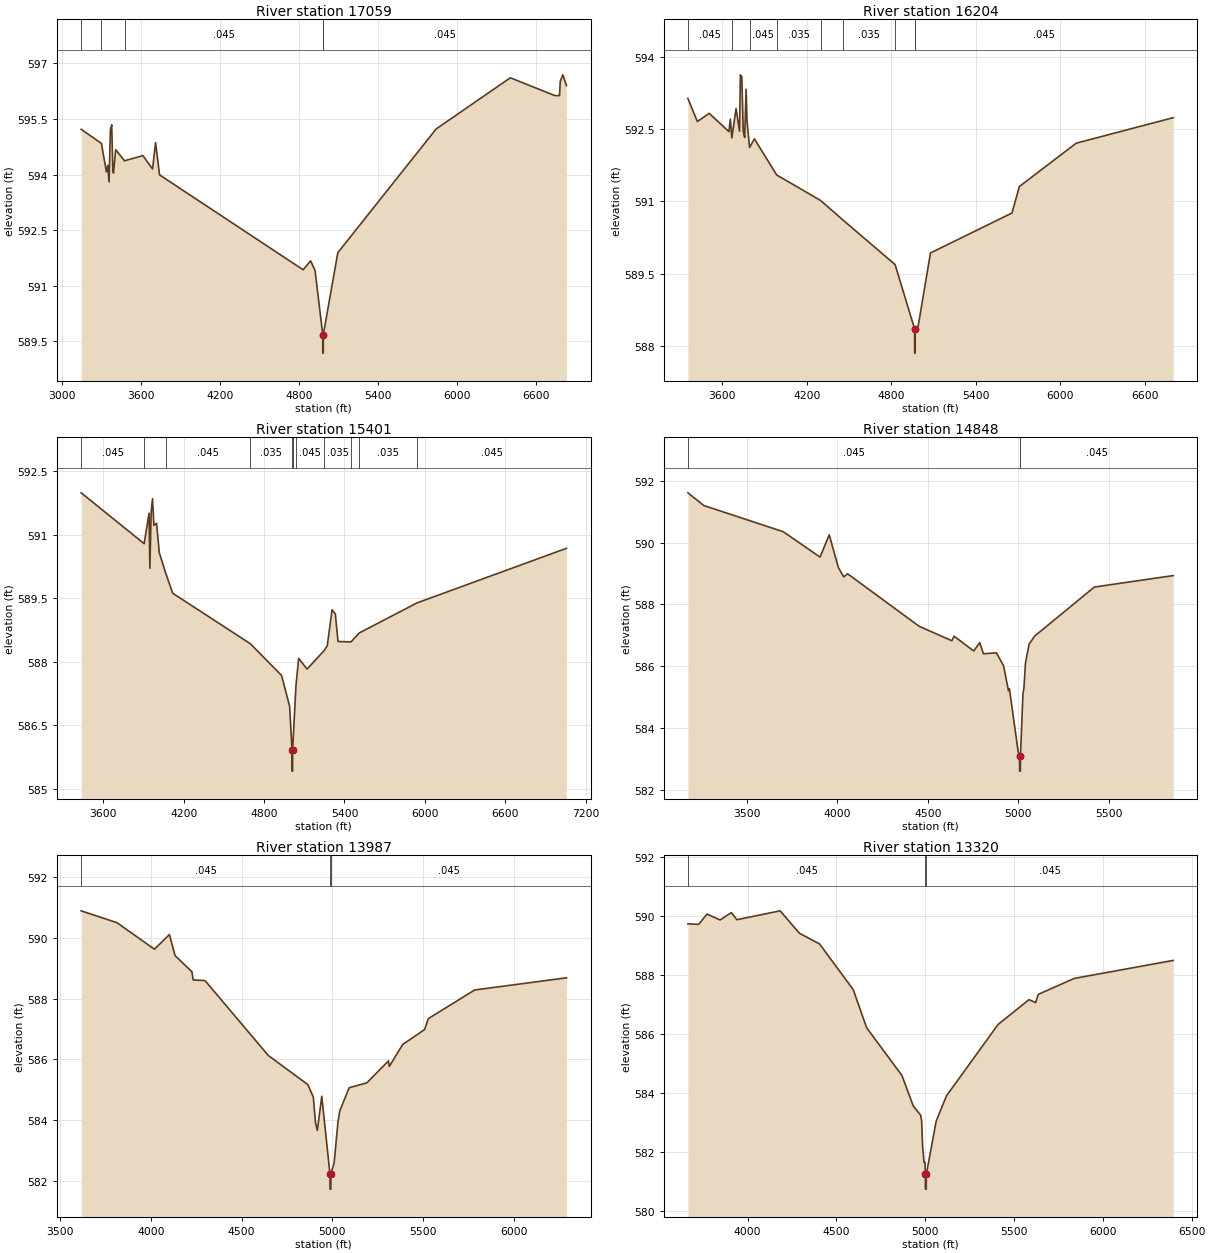
Type RM Length L Ch R = 1 ,17059   ,855,855,855
BEGIN DESCRIPTION:
GERONIMO TRIBUTARY 7 21.0
END DESCRIPTION:
XS GIS Cut Line= 3
      2291077.52     13785214.83        2291325.       13783375.
      2290939.03     13781588.21
#Sta/Elev= 30
  3143.2  595.22    3297  594.84  3334.7  594.07  3344.8  594.25  3354.9   593.8
    3365  595.21  3375.1  595.34  3383.5   594.1  3388.5  594.04  3405.4  594.67
  3472.2  594.37    3612  594.51  3684.9  594.15  3708.1  594.86  3738.3  593.99
  4828.1  591.43  4885.3  591.67  4918.9  591.41  4977.3  589.68  4977.6  589.18
  4981.3  589.18  4981.6  589.68  5091.7  591.89  5838.5  595.23  6401.5  596.61
  6738.8  596.13  6775.1  596.13  6780.3  596.51  6800.2  596.69  6827.6   596.4
#Mann= 5 ,-1 , 0
  3143.2    .045       0    3297    .035       0  3472.2    .045       0
  4977.3    .045       0  4981.6    .045       0
Bank Sta=4977.3,4981.6
XS Rating Curve= 0 ,0
Exp/Cntr=0.3,0.1

Type RM Length L Ch R = 1 ,16204   ,803,803,803
BEGIN DESCRIPTION:
A19072
END DESCRIPTION:
XS GIS Cut Line= 3
      2291702.52     13785371.06       2292067.1     13783426.64
      2291485.51     13782081.17
#Sta/Elev= 30
  3356.5  593.14  3423.7  592.66  3507.9  592.83  3647.5  592.45  3657.7  592.71
  3668.2  592.32  3698.4  592.93  3723.2  592.46  3728.9  593.63  3739.1  593.59
  3749.3  592.46  3759.5  592.33  3769.6  593.33  3775.8  592.68  3794.3  592.12
  3828.4   592.3  3986.9  591.55  4298.5  591.02  4458.9  590.61  4826.9  589.69
  4965.7  588.35    4966  587.85  4969.8  587.85  4970.1  588.35  4990.6  588.41
  5078.1  589.93  5656.6  590.76    5709  591.31  6112.2  592.21  6800.6  592.74
#Mann= 9 ,-1 , 0
  3356.5    .045       0  3668.2    .035       0  3794.3    .045       0
  3986.9    .035       0  4298.5    .045       0  4458.9    .035       0
  4826.9    .045       0  4965.7    .045       0  4970.1    .045       0
Bank Sta=4965.7,4970.1
XS Rating Curve= 0 ,0
Exp/Cntr=0.3,0.1

Type RM Length L Ch R = 1 ,15401   ,553,553,553
BEGIN DESCRIPTION:
A19071
END DESCRIPTION:
XS GIS Cut Line= 3
      2292579.26     13785536.02      2292735.51     13783600.25
       2292240.7     13781994.31
#Sta/Elev= 30
  3434.4  591.99  3904.4  590.79  3941.4  591.51  3947.1  590.21  3957.1  591.55
  3967.1  591.85  3977.2  591.22  3997.2  591.27  4017.3  590.58  4065.9  590.09
  4117.6  589.62  4696.1  588.43  4930.2  587.68  4990.5  586.95  5008.3  585.92
  5008.6  585.42  5012.5  585.42  5012.8  585.92  5037.6  587.43  5057.6  588.08
  5120.9  587.83  5246.6  588.26  5271.4  588.38  5307.3  589.23  5331.6  589.13
  5351.6  588.48  5448.5  588.47  5509.3  588.68  5940.2  589.39  7056.9  590.68
#Mann= 11 ,-1 , 0
  3434.4    .045       0  3904.4    .035       0  4065.9    .045       0
  4696.1    .035       0  5008.3    .035       0  5012.8    .035       0
  5037.6    .045       0  5246.6    .035       0  5448.5    .045       0
  5509.3    .035       0  5940.2    .045       0
Bank Sta=5008.3,5012.8
XS Rating Curve= 0 ,0
Exp/Cntr=0.3,0.1

Type RM Length L Ch R = 1 ,14848   ,861,861,861
BEGIN DESCRIPTION:
GERONIMO TRIBUTARY 7 20.0
END DESCRIPTION:
XS GIS Cut Line= 3
      2293474.99     13785624.96       2293186.9     13783930.11
      2293065.37     13782975.27
#Sta/Elev= 30
  3174.4  591.61  3262.2   591.2  3701.8  590.35  3904.7  589.53  3955.4  590.25
  4006.1  589.19  4035.5  588.89  4056.8  588.99  4452.3  587.29  4633.1  586.82
  4645.2  586.97  4753.7  586.49  4787.2  586.76  4807.5   586.4  4879.3  586.43
  4918.9  586.01  4946.1   585.2  4951.2  585.27  4999.5  583.23  5007.1   583.1
  5007.5   582.6  5011.7   582.6  5012.1   583.1    5026  585.11  5031.1  585.27
  5039.8   586.1    5060  586.71  5090.2  586.97  5420.6  588.56  5856.1  588.93
#Mann= 3 ,-1 , 0
  3174.4    .045       0  5007.1    .045       0  5012.1    .045       0
Bank Sta=5007.1,5012.1
XS Rating Curve= 0 ,0
Exp/Cntr=0.3,0.1

Type RM Length L Ch R = 1 ,13987   ,667,667,667
BEGIN DESCRIPTION:
A19073
END DESCRIPTION:
XS GIS Cut Line= 3
      2294289.32     13785336.33      2293863.98     13783626.29
      2293187.64     13783019.32
#Sta/Elev= 30
  3617.4  590.88  3814.6  590.49  4020.6  589.62  4103.1   590.1    4134  589.41
  4226.7  588.88    4234  588.61  4298.9  588.59  4647.2  586.13  4865.6  585.17
  4895.1  584.76  4906.9  583.92  4917.2  583.67  4941.6  584.79  4986.7  582.24
  4987.1  581.74  4991.4  581.74  4991.8  582.24  5009.9  582.61  5030.5  583.94
  5040.8  584.31  5092.3  585.07  5189.6  585.23  5308.4  585.95  5313.5  585.77
  5386.9  586.49  5507.3  586.98  5528.2  587.34  5783.1  588.28  6288.3  588.68
#Mann= 3 ,-1 , 0
  3617.4    .045       0  4986.7    .045       0  4991.8    .045       0
Bank Sta=4986.7,4991.8
XS Rating Curve= 0 ,0
Exp/Cntr=0.3,0.1

Type RM Length L Ch R = 1 ,13320   ,862,862,862
BEGIN DESCRIPTION:
GERONIMO TRIBUTARY 7 19.0
END DESCRIPTION:
XS GIS Cut Line= 3
      2294949.37     13784987.18        2294525.       13783725.
      2293329.72     13782996.11
#Sta/Elev= 30
  3664.4  589.73  3724.9  589.71  3772.2  590.06  3845.7  589.86  3908.8  590.11
  3940.3  589.87  4183.7  590.17  4292.2  589.41  4405.2  589.05  4595.1   587.5
  4670.4  586.21  4869.4  584.59  4932.7  583.56  4974.9  583.24  4980.3  583.05
  4985.5  582.21  4993.4  581.65  4998.9  581.65  5001.1  581.24  5001.5  580.74
    5006  580.74  5006.4  581.24  5061.8  583.04  5119.9   583.9  5410.4  586.32
  5584.7  587.16  5621.4  587.06  5636.9  587.34  5839.3  587.88    6396  588.49
#Mann= 3 ,-1 , 0
  3664.4    .045       0  5001.1    .045       0  5006.4    .045       0
Bank Sta=5001.1,5006.4
XS Rating Curve= 0 ,0
Exp/Cntr=0.3,0.1

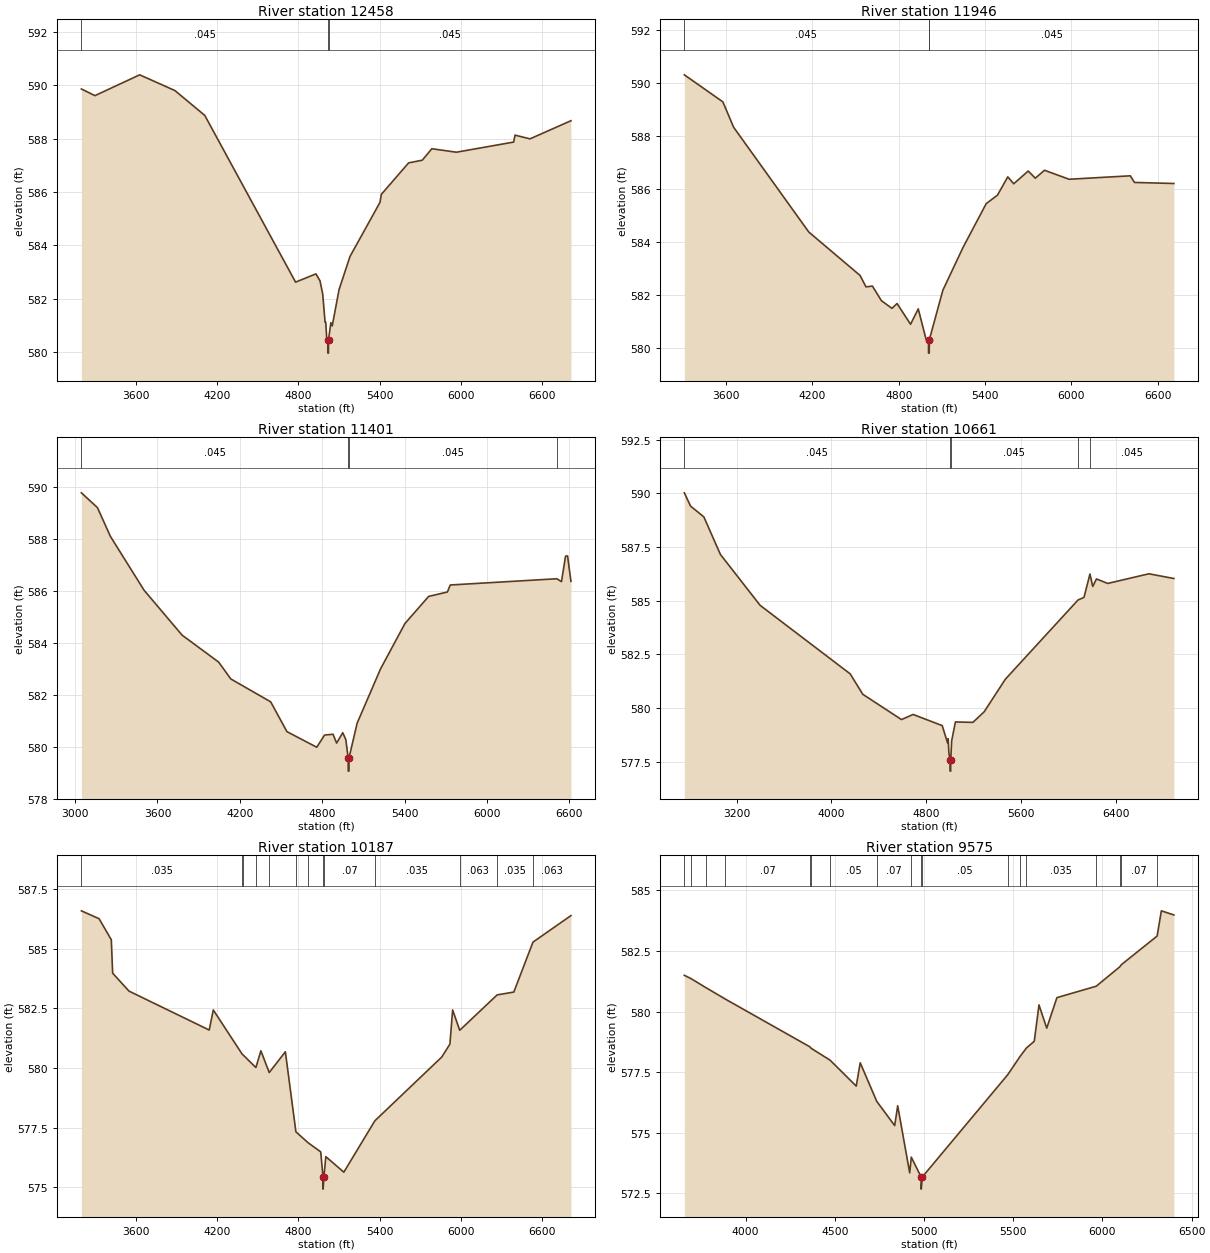
Type RM Length L Ch R = 1 ,12458   ,512,512,512
BEGIN DESCRIPTION:
GERONIMO TRIBUTARY 7 18.0
END DESCRIPTION:
XS GIS Cut Line= 3
        2295025.     13784925.02        2295025.       13783125.
        2293225.       13782925.
#Sta/Elev= 30
  3200.3  589.86  3300.3  589.61  3630.3  590.39  3890.3   589.8  4110.3  588.87
  4780.3  582.62  4930.3  582.93  4960.3  582.67  4980.3  582.18  4997.8  581.12
  5002.8  581.12  5010.4  580.47  5017.7  580.46  5018.2  579.96  5022.7  579.96
  5023.1  580.46  5040.6   581.1  5050.6  580.98  5100.9  582.34  5181.4  583.58
  5402.8  585.61  5412.8  585.91  5614.1  587.09  5714.7  587.19  5785.1  587.62
  5966.2  587.49  6388.8  587.87  6398.9  588.13  6509.5  587.99  6811.4  588.67
#Mann= 3 ,-1 , 0
  3200.3    .045       0  5017.7    .045       0  5023.1    .045       0
Bank Sta=5017.7,5023.1
XS Rating Curve= 0 ,0
Exp/Cntr=0.3,0.1

Type RM Length L Ch R = 1 ,11946   ,545,545,545
BEGIN DESCRIPTION:
A19070
END DESCRIPTION:
XS GIS Cut Line= 4
      2295272.25     13784325.26       2295611.3     13783431.89
      2295256.12     13782479.34      2294159.14      13781565.2
#Sta/Elev= 30
  3311.2  590.29  3578.9  589.27  3653.8  588.31  4175.5  584.36  4531.8  582.72
  4572.9  582.29  4617.5  582.32  4679.7  581.77    4753  581.48  4788.7  581.66
  4882.4  580.88  4935.8  581.46  4990.3  580.31  5007.2  580.29  5007.6  579.79
  5012.2  579.79  5012.6  580.29  5106.6  582.16  5247.1  583.78  5407.9  585.43
    5486  585.75  5557.6  586.44  5599.2  586.18  5699.5  586.66  5748.9  586.39
  5812.7  586.69  5983.2  586.35  6408.9  586.48  6437.5  586.23  6711.3  586.19
#Mann= 3 ,-1 , 0
  3311.2    .045       0  5007.2    .045       0  5012.6    .045       0
Bank Sta=5007.2,5012.6
XS Rating Curve= 0 ,0
Exp/Cntr=0.3,0.1

Type RM Length L Ch R = 1 ,11401   ,740,740,740
BEGIN DESCRIPTION:
A19069
END DESCRIPTION:
XS GIS Cut Line= 4
      2295385.27     13784201.47      2295988.01     13783022.89
      2295654.35     13782070.34       2294939.3     13781064.96
#Sta/Elev= 30
  3045.9  589.78    3163  589.21  3257.5   588.1  3502.4  586.03  3779.3   584.3
  4045.9  583.26  4134.7  582.61  4424.9  581.73  4543.7  580.58  4760.8  579.98
  4817.6  580.45  4879.6  580.48  4905.3  580.14  4950.2  580.54  4972.7  580.27
  4989.8  579.56  4990.3  579.06  4994.9  579.06  4995.3  579.56  5055.1  580.91
  5225.7     583  5403.8  584.75    5576  585.79  5712.5  585.96  5733.4  586.23
  6509.4  586.47  6543.8  586.36  6573.3  587.34  6588.1  587.35  6612.7  586.37
#Mann= 4 ,-1 , 0
  3045.9    .045       0  4989.8    .045       0  4995.3    .045       0
  6509.4    .035       0
Bank Sta=4989.8,4995.3
XS Rating Curve= 0 ,0
Exp/Cntr=0.3,0.1

Type RM Length L Ch R = 1 ,10661   ,474,474,474
BEGIN DESCRIPTION:
GERONIMO TRIBUTARY 7 17.0
END DESCRIPTION:
XS GIS Cut Line= 3
      2295425.01     13784224.99        2296425.       13782225.
      2295825.01     13780425.02
#Sta/Elev= 30
  2759.2  590.02  2812.3   589.4  2924.1   588.9  3063.9  587.15  3399.3  584.78
  4159.5  581.59  4265.7  580.64  4592.8  579.46  4690.6   579.7  4936.6  579.18
  4981.3  578.38  4986.9  578.57  4992.5  577.94    5003  577.56  5003.5  577.06
  5008.1  577.06  5008.5  577.56  5016.3  578.47    5048  579.35  5195.5  579.33
  5290.4  579.82  5469.6  581.34  6083.4  585.03  6133.7  585.15  6183.9  586.24
  6207.5  585.66  6239.1  586.01    6334   585.8  6681.8  586.25  6892.6  586.03
#Mann= 5 ,-1 , 0
  2759.2    .045       0    5003    .045       0  5008.5    .045       0
  6083.4    .035       0  6183.9    .045       0
Bank Sta=5003,5008.5
XS Rating Curve= 0 ,0
Exp/Cntr=0.3,0.1

Type RM Length L Ch R = 1 ,10187   ,612,612,612
BEGIN DESCRIPTION:
GERONIMO TRIBUTARY 7 16.0
END DESCRIPTION:
XS GIS Cut Line= 3
      2296575.01     13783974.95        2296775.       13782175.
        2296575.     13780375.01
#Sta/Elev= 30
    3194  586.58  3324.8  586.25  3415.3  585.37  3425.4  583.97  3546.1  583.22
  4139.7  581.59  4169.9  582.43  4383.7  580.58  4386.3  580.57    4485  580.02
  4522.1  580.72  4583.7  579.81  4703.2  580.68  4781.1  577.33  4871.8  576.87
  4964.8  576.49  4981.8  575.43  4982.3  574.93  4988.1  575.43  5002.5  576.29
  5135.8  575.64  5365.3  577.79  5860.3  580.46  5920.6     581  5940.8  582.43
  5993.2  581.58    6270  583.06  6393.5  583.18  6535.2  585.27  6816.1  586.38
#Mann= 13 ,-1 , 0
    3194    .035       0  4383.7     .05       0  4386.3     .07       0
    4485     .05       0  4583.7     .07       0  4781.1     .05       0
  4871.8     .07       0  4981.8     .05       0  4988.1     .07       0
  5365.3    .035       0  5993.2    .063       0    6270    .035       0
  6535.2    .063       0
Bank Sta=4981.8,4988.1
XS Rating Curve= 0 ,0
Exp/Cntr=0.3,0.1

Type RM Length L Ch R = 1 ,9575    ,527,527,527
BEGIN DESCRIPTION:
A19068
END DESCRIPTION:
XS GIS Cut Line= 4
      2296919.01     13783001.39      2297430.28     13782226.41
       2297134.3     13781629.05      2296774.31     13780538.33
#Sta/Elev= 30
  3656.7   581.5  3692.9  581.37  3775.6     581  3886.3  580.52  4360.4  578.55
  4367.3  578.49  4473.5     578  4620.2  576.93  4642.5  577.89  4735.2   576.3
  4835.7   575.3  4852.5  576.12  4919.8  573.35  4928.7     574  4983.8  573.18
  4984.3  572.68  4990.3  573.18  5469.2   577.4    5539  578.16  5573.8   578.5
  5617.9  578.78  5644.4  580.28  5687.8  579.32  5744.9  580.58  5965.2  581.05
  6097.2  581.85  6106.2  581.94  6306.5  583.12  6330.2  584.16  6400.4  583.99
#Mann= 18 ,-1 , 0
  3656.7     .05       0  3692.9     .07       0  3775.6     .05       0
  3886.3     .07       0  4360.4     .05       0  4367.3     .07       0
  4473.5     .05       0  4735.2     .07       0  4928.7     .05       0
  4983.8     .05       0  4990.3     .05       0  5469.2     .07       0
    5539     .05       0  5573.8    .035       0  5965.2     .05       0
  6097.2    .035       0  6106.2     .07       0  6306.5     .15       0
Bank Sta=4983.8,4990.3
XS Rating Curve= 0 ,0
Exp/Cntr=0.3,0.1

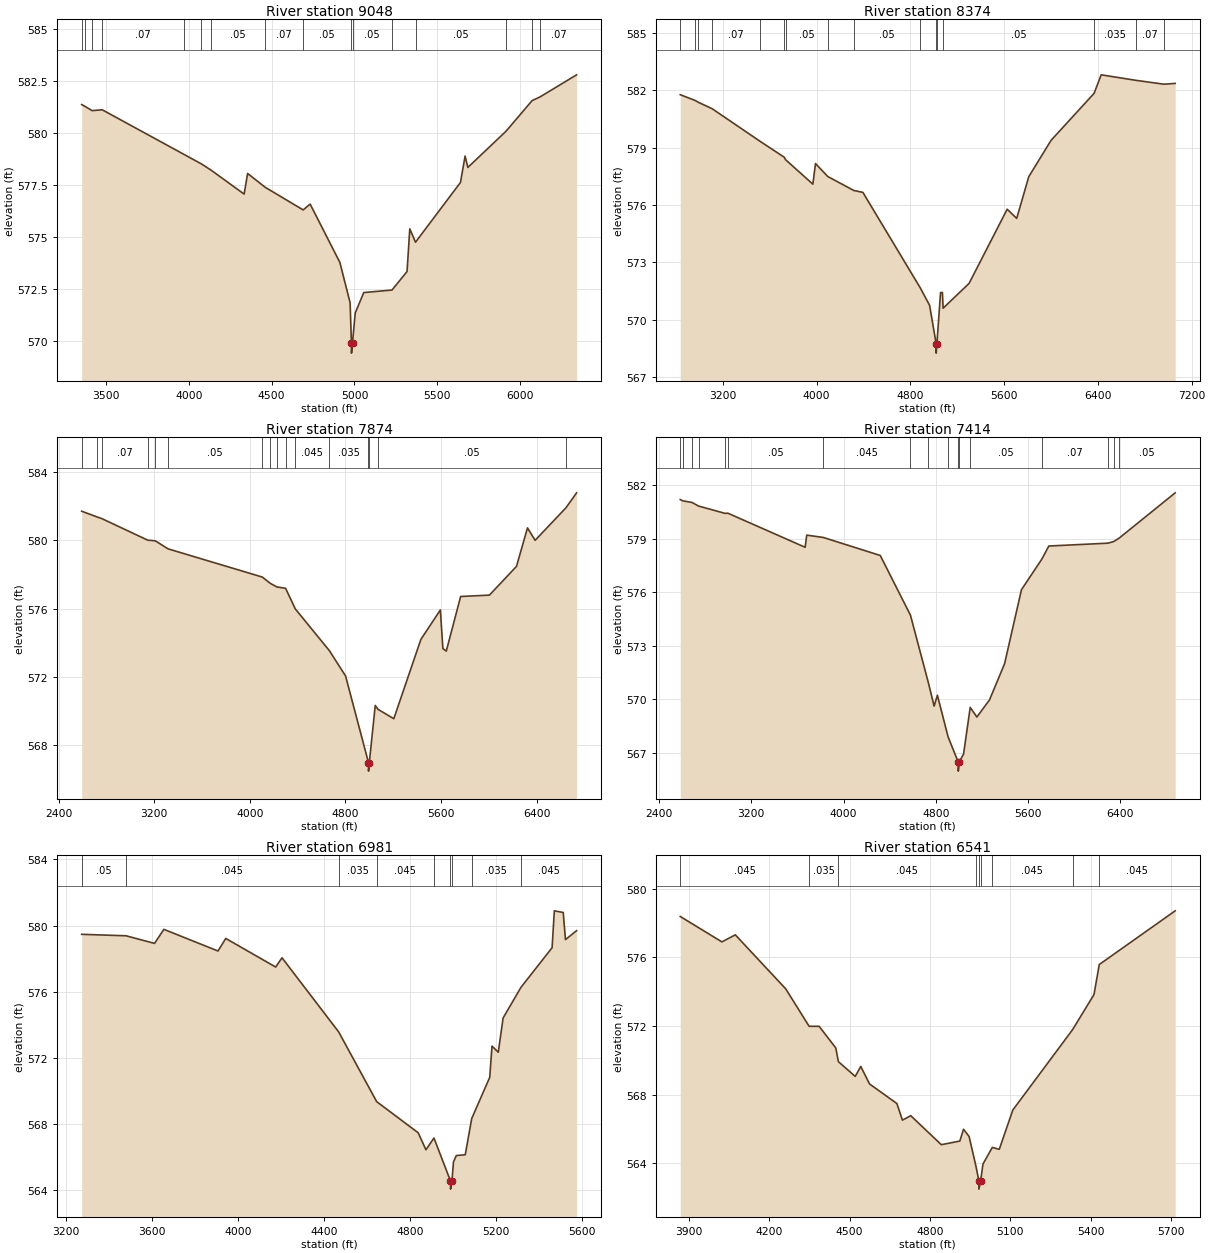
Type RM Length L Ch R = 1 ,9048    ,674,674,674
BEGIN DESCRIPTION:
A19067
END DESCRIPTION:
XS GIS Cut Line= 4
       2296962.1     13783001.33      2297667.08     13781946.56
      2297532.54      13781408.4      2297005.21      13780369.9
#Sta/Elev= 30
  3353.1  581.37  3372.1  581.29  3416.3  581.08  3477.4  581.12  3972.6  578.97
    4076  578.52  4136.5  578.21    4334  577.07  4355.1  578.06  4460.8   577.4
  4690.4  576.31  4732.5  576.59    4912  573.79  4973.8  571.85  4981.7  569.93
  4982.2  569.43  4988.3  569.93  5004.8  571.36  5056.3  572.34  5226.6  572.46
  5317.6  573.35  5334.2   575.4  5368.7  574.76  5640.1  577.63  5668.1   578.9
  5684.7  578.35  5915.1  580.09  6072.5  581.56    6123  581.75  6341.2   582.8
#Mann= 16 ,-1 , 0
  3353.1     .05       0  3372.1     .07       0  3416.3     .05       0
  3477.4     .07       0  3972.6     .05       0    4076     .07       0
  4136.5     .05       0  4460.8     .07       0  4690.4     .05       0
  4981.7     .05       0  4988.3     .05       0  5226.6    .035       0
  5368.7     .05       0  5915.1     .07       0  6072.5    .035       0
    6123     .07       0
Bank Sta=4981.7,4988.3
XS Rating Curve= 0 ,0
Exp/Cntr=0.3,0.1

Type RM Length L Ch R = 1 ,8374    ,500,500,500
BEGIN DESCRIPTION:
GERONIMO TRIBUTARY 7 15.0
END DESCRIPTION:
XS GIS Cut Line= 3
      2296925.02     13783124.97        2298125.       13781325.
      2297125.01     13779525.02
#Sta/Elev= 30
  2836.7  581.77  2963.1  581.47  2991.9  581.37  3107.9  581.04  3520.4  579.32
  3723.6   578.5  3735.1  578.37  3967.9  577.09  3990.4  578.17  4095.1  577.49
  4316.8  576.76  4394.6  576.66  4885.6  571.65  4963.9  570.75  5019.5  568.75
    5020  568.25  5026.3  568.75  5057.2  571.42  5073.2  571.42    5079   570.6
  5300.9   571.9  5625.7  575.78    5707   575.3  5809.9  577.48  5999.8  579.38
    6367  581.84  6427.7  582.81  6726.3  582.52    6962  582.32  7059.1  582.36
#Mann= 16 ,-1 , 0
  2836.7     .05       0  2963.1     .07       0  2991.9     .05       0
  3107.9     .07       0  3520.4     .05       0  3723.6     .07       0
  3735.1     .05       0  4095.1     .07       0  4316.8     .05       0
  4885.6    .035       0  5019.5    .035       0  5026.3    .035       0
    5079     .05       0    6367    .035       0  6726.3     .07       0
    6962    .035       0
Bank Sta=5019.5,5026.3
XS Rating Curve= 0 ,0
Exp/Cntr=0.3,0.1

Type RM Length L Ch R = 1 ,7874    ,460,460,460
BEGIN DESCRIPTION:
GERONIMO TRIBUTARY 7 14.0
END DESCRIPTION:
XS GIS Cut Line= 3
      2297025.02     13783124.98        2298625.       13781325.
      2297475.03     13780025.03
#Sta/Elev= 30
  2591.7  581.72  2718.2  581.39  2759.5  581.29  3144.5  580.02  3208.5  579.98
  3314.6  579.51  4104.7  577.85  4171.1  577.48  4227.1  577.27  4299.4  577.19
  4380.4  575.98  4665.6  573.53  4801.4  572.04  4993.2  566.95  4993.7  566.45
  5000.1  566.95  5049.8  570.31  5072.9  570.08  5205.3  569.53    5432  574.19
  5595.1  575.92    5616  573.65  5644.5   573.5  5764.9  576.71  6005.8  576.79
  6232.5  578.48  6324.5  580.74  6388.5  580.01  6646.4  581.92  6735.6   582.8
#Mann= 16 ,-1 , 0
  2591.7     .07       0  2718.2     .05       0  2759.5     .07       0
  3144.5     .05       0  3208.5     .07       0  3314.6     .05       0
  4104.7     .07       0  4171.1     .05       0  4227.1     .07       0
  4299.4     .05       0  4380.4    .045       0  4665.6    .035       0
  4993.2    .035       0  5000.1    .035       0  5072.9     .05       0
  6646.4    .035       0
Bank Sta=4993.2,5000.1
XS Rating Curve= 0 ,0
Exp/Cntr=0.3,0.1

Type RM Length L Ch R = 1 ,7414    ,433,433,433
BEGIN DESCRIPTION:
GERONIMO TRIBUTARY 7 13.0
END DESCRIPTION:
XS GIS Cut Line= 3
        2297275.       13782975.        2299075.       13781375.
        2298075.     13779775.01
#Sta/Elev= 30
  2583.3  581.18  2606.5  581.11    2685  581.02  2741.9  580.82  2971.8  580.41
  2996.1  580.42    3667  578.51  3680.8  579.19  3824.5  579.06  4318.9  578.05
  4580.7  574.71  4736.9  570.91  4786.3  569.61  4814.8  570.22  4907.6  567.89
  4995.8  566.47  4996.3  565.97  5002.8  566.47  5041.7  566.92  5099.6  569.54
  5157.3     569    5267  569.96  5397.9  571.99  5544.1  576.13  5721.4  577.85
  5781.7  578.58    6295  578.74  6344.6  578.83  6393.4  579.03  6878.4  581.56
#Mann= 17 ,-1 , 0
  2583.3     .07       0  2606.5     .05       0    2685     .07       0
  2741.9     .05       0  2971.8     .07       0  2996.1     .05       0
  3824.5    .045       0  4580.7    .035       0  4736.9    .045       0
  4907.6    .035       0  4995.8    .035       0  5002.8    .035       0
  5099.6     .05       0  5721.4     .07       0    6295     .05       0
  6344.6     .07       0  6393.4     .05       0
Bank Sta=4995.8,5002.8
XS Rating Curve= 0 ,0
Exp/Cntr=0.3,0.1

Type RM Length L Ch R = 1 ,6981    ,440,440,440
BEGIN DESCRIPTION:
GERONIMO TRIBUTARY 7 12.0
END DESCRIPTION:
XS GIS Cut Line= 3
      2298024.96     13782425.03        2299475.       13781475.
      2299624.99     13780925.03
#Sta/Elev= 30
  3271.9  579.47  3478.6  579.38  3611.1  578.92  3654.5  579.77  3906.5  578.46
  3942.7  579.22  4174.9  577.49  4204.4  578.05    4468  573.57  4645.1  569.35
  4838.1  567.47  4874.3  566.44  4911.7  567.15  4988.4  564.56  4988.9  564.06
  4995.5  564.56  5002.5  565.71  5015.8  566.09  5057.3  566.14  5087.4  568.33
  5171.3  570.82  5181.7  572.71    5211  572.34  5233.5  574.41    5317  576.27
  5461.5  578.66  5471.9  580.89  5513.3  580.79  5523.7  579.15  5575.5  579.69
#Mann= 9 ,-1 , 0
  3271.9     .05       0  3478.6    .045       0    4468    .035       0
  4645.1    .045       0  4911.7     .07       0  4988.4     .05       0
  4995.5     .07       0  5087.4    .035       0    5317    .045       0
Bank Sta=4988.4,4995.5
XS Rating Curve= 0 ,0
Exp/Cntr=0.3,0.1

Type RM Length L Ch R = 1 ,6541    ,445,445,445
BEGIN DESCRIPTION:
GERONIMO TRIBUTARY 7 11.0
END DESCRIPTION:
XS GIS Cut Line= 3
      2298725.03     13782024.99        2299825.       13781725.
      2299724.99     13781024.95
#Sta/Elev= 30
  3868.3  578.38  4023.7   576.9  4073.8  577.31  4262.1  574.16  4349.3  571.98
  4386.5  571.98  4448.7  570.72  4458.5  569.92  4521.3  569.06    4542  569.64
  4574.8  568.62  4676.8  567.48  4697.5  566.51  4728.6  566.77  4842.6  565.08
  4911.7  565.29  4925.5  565.98  4946.3  565.56  4972.9  563.76  4982.4  562.99
  4982.9  562.49  4989.6  562.99  4998.1  563.95  5032.9  564.92    5059  564.81
  5109.5   567.1  5332.4  571.78  5412.5  573.83  5432.2  575.58  5715.6  578.71
#Mann= 9 ,-1 , 0
  3868.3    .045       0  4349.3    .035       0  4458.5    .045       0
  4972.9     .07       0  4982.4     .05       0  4989.6     .07       0
  5032.9    .045       0  5332.4    .035       0  5432.2    .045       0
Bank Sta=4982.4,4989.6
XS Rating Curve= 0 ,0
Exp/Cntr=0.3,0.1

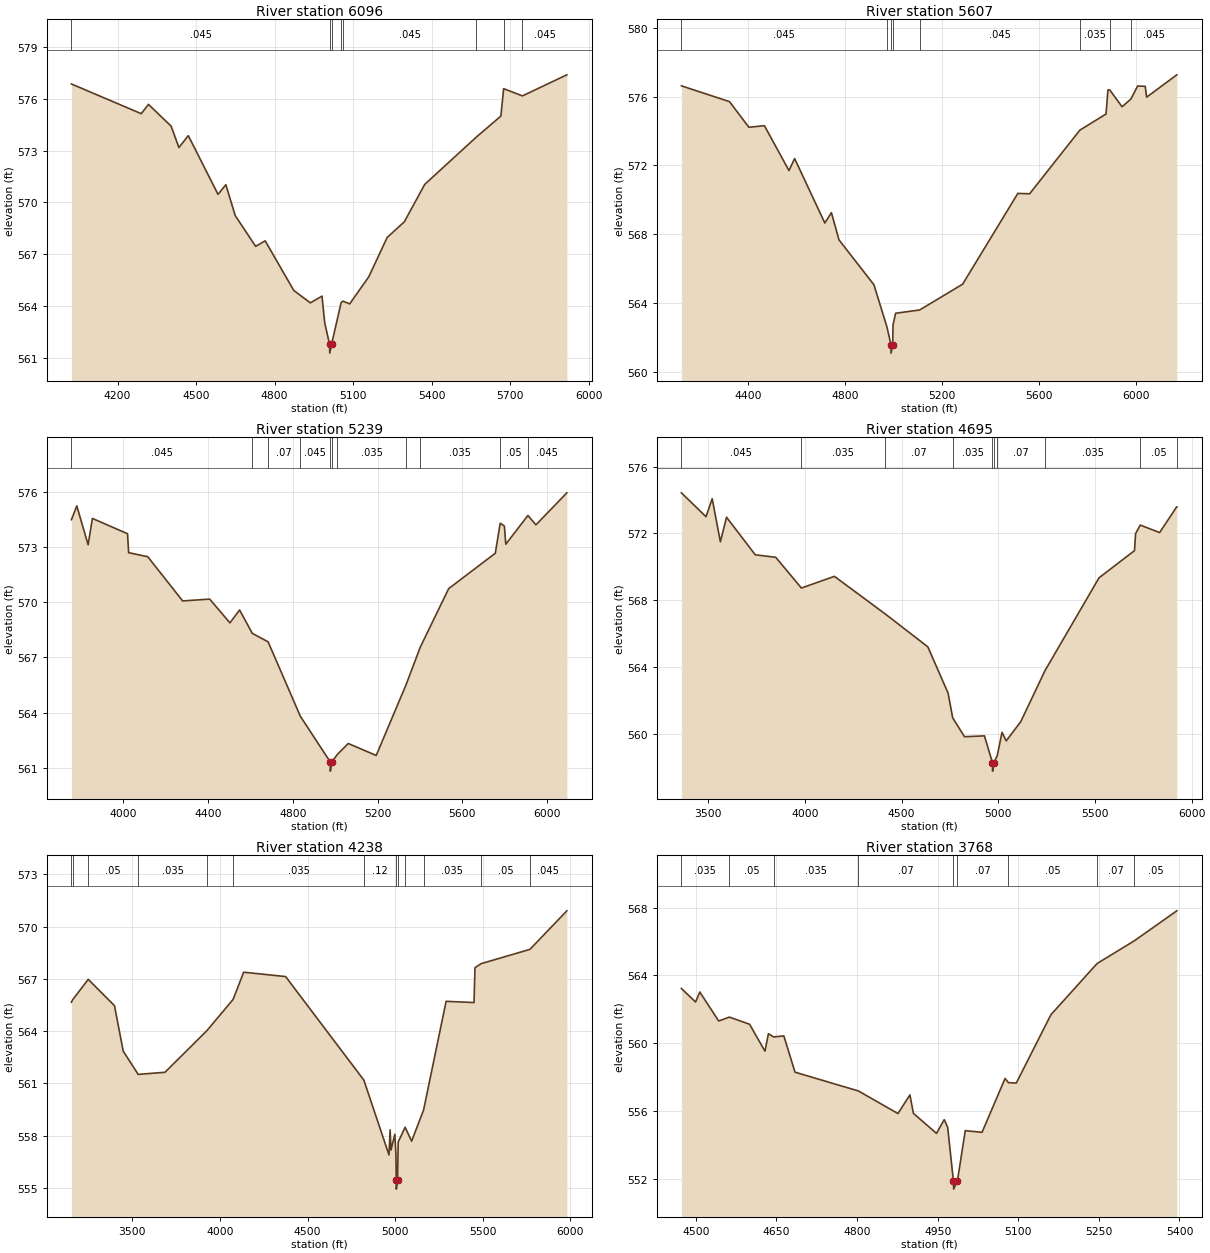
Type RM Length L Ch R = 1 ,6096    ,489,489,489
BEGIN DESCRIPTION:
GERONIMO TRIBUTARY 7 10.0
END DESCRIPTION:
XS GIS Cut Line= 3
      2299625.02     13782774.97        2300175.       13781975.
      2299975.01     13781075.04
#Sta/Elev= 30
  4023.9  576.86  4290.8  575.14  4318.1  575.68  4404.7  574.42  4434.5  573.18
  4470.4  573.87    4584  570.47  4613.8  571.03  4649.7  569.24  4727.7  567.46
  4764.1  567.78  4873.3  564.91  4936.5  564.19  4981.2  564.58  4991.6  563.03
  5010.2  561.78  5010.7  561.28  5017.5  561.78  5054.2   564.2  5060.8  564.29
  5086.9  564.13  5159.9   565.7  5230.3  567.98  5295.6  568.88  5373.7  571.05
  5571.1  573.79  5664.4     575  5675.1  576.59  5746.8  576.17  5916.6  577.39
#Mann= 8 ,-1 , 0
  4023.9    .045       0  5010.2    .045       0  5017.5    .045       0
  5054.2    .035       0  5060.8    .045       0  5571.1    .035       0
  5675.1     .05       0  5746.8    .045       0
Bank Sta=5010.2,5017.5
XS Rating Curve= 0 ,0
Exp/Cntr=0.3,0.1

Type RM Length L Ch R = 1 ,5607    ,368,368,368
BEGIN DESCRIPTION:
GERONIMO TRIBUTARY 7 9.0
END DESCRIPTION:
XS GIS Cut Line= 3
      2300175.02     13782824.96        2300625.       13782075.
        2300025.     13781074.99
#Sta/Elev= 30
  4125.5  576.63  4323.7  575.71  4403.4  574.22  4467.5  574.31  4568.6   571.7
  4591.9   572.4  4716.3  568.65  4743.5  569.25  4774.6  567.67  4918.5  565.06
  4972.1  562.61  4988.6  561.58  4989.1  561.08    4996  561.58  4997.2  562.72
  5007.9   563.4    5107  563.59  5283.9  565.09  5511.3  570.37  5559.9  570.35
  5766.7  574.05  5874.7  574.99  5882.5  576.39  5889.6   576.4  5940.8  575.41
  5976.8  575.86    6005  576.62  6036.1   576.6  6041.9  575.97  6166.3  577.27
#Mann= 8 ,-1 , 0
  4125.5    .045       0  4972.1    .035       0  4988.6    .035       0
    4996    .035       0    5107    .045       0  5766.7    .035       0
  5889.6     .05       0  5976.8    .045       0
Bank Sta=4988.6,4996
XS Rating Curve= 0 ,0
Exp/Cntr=0.3,0.1

Type RM Length L Ch R = 1 ,5239    ,544,544,544
BEGIN DESCRIPTION:
A19066
END DESCRIPTION:
XS GIS Cut Line= 4
      2300696.91     13783109.04      2300987.53     13782221.03
      2300890.66     13781661.34       2300266.4     13781107.04
#Sta/Elev= 30
  3755.8  574.47  3781.1  575.22  3834.5  573.11  3854.7  574.54  4020.4  573.71
  4025.7  572.68    4116  572.46  4280.5  570.06    4408  570.16  4503.5  568.87
  4549.2  569.57    4609   568.3  4683.6  567.84  4835.7   563.8  4976.7  561.32
  4977.2  560.82  4984.1  561.32  5010.7  561.73  5061.6  562.32  5193.6  561.67
  5333.8  565.49  5401.8  567.56  5535.6  570.73  5755.5  572.65  5778.6  574.28
  5798.2  574.13  5804.9  573.14  5909.3   574.7    5947  574.19    6093  575.93
#Mann= 11 ,-1 , 0
  3755.8    .045       0    4609    .035       0  4683.6     .07       0
  4835.7    .045       0  4976.7    .045       0  4984.1    .045       0
  5010.7    .035       0  5333.8     .07       0  5401.8    .035       0
  5778.6     .05       0  5909.3    .045       0
Bank Sta=4976.7,4984.1
XS Rating Curve= 0 ,0
Exp/Cntr=0.3,0.1

Type RM Length L Ch R = 1 ,4695    ,457,457,457
BEGIN DESCRIPTION:
GERONIMO TRIBUTARY 7 8.0
END DESCRIPTION:
XS GIS Cut Line= 3
        2300775.     13783224.99        2301325.       13781675.
      2300524.96     13781224.98
#Sta/Elev= 30
  3360.8  574.43  3488.1     573    3520  574.08  3562.4   571.5  3594.2  572.97
  3742.8  570.72  3848.9  570.57  3981.5  568.73  4152.3  569.43    4415  567.18
  4635.5  565.21  4740.2  562.44    4764  560.96  4825.1  559.83  4928.3  559.88
  4969.9  558.27  4970.4  557.77  4977.4  558.27  4994.6   558.7  5019.2  560.09
  5040.9  559.58  5116.1  560.73  5241.2  563.78  5520.8  569.34  5704.4  570.97
  5710.1  571.99  5734.2   572.5  5834.4  572.05  5922.6  573.59  5923.4  573.59
#Mann= 10 ,-1 , 0
  3360.8    .045       0  3981.5    .035       0    4415     .07       0
    4764    .035       0  4969.9     .05       0  4977.4    .035       0
  4994.6     .07       0  5241.2    .035       0  5734.2     .05       0
  5922.6    .045       0
Bank Sta=4969.9,4977.4
XS Rating Curve= 0 ,0
Exp/Cntr=0.3,0.1

Type RM Length L Ch R = 1 ,4238    ,470,470,470
BEGIN DESCRIPTION:
GERONIMO TRIBUTARY 7 7.0
END DESCRIPTION:
XS GIS Cut Line= 3
        2301325.     13783324.99        2301725.       13781525.
      2300824.98     13781124.99
#Sta/Elev= 30
  3151.8  565.66  3159.6  565.81  3247.7  566.97  3397.6  565.46  3447.6  562.85
  3533.1  561.52  3685.8  561.64  3925.4  564.03    4075  565.82  4135.2  567.38
  4374.7  567.13  4821.6  561.19    4965   556.9  4971.4  558.34  4976.5  557.18
  4998.4  558.09  5004.6  556.91  5006.3  555.44  5006.8  554.94  5013.8  555.44
  5017.6  557.64  5057.1  558.49  5094.2  557.69  5162.6  559.48  5291.2  565.71
  5450.5  565.64    5456  567.64  5490.9  567.87  5769.8  568.69  5980.6   570.9
#Mann= 13 ,-1 , 0
  3151.8     .05       0  3159.6    .045       0  3247.7     .05       0
  3533.1    .035       0  3925.4     .05       0    4075    .035       0
  4821.6     .12       0  5006.3     .05       0  5013.8     .12       0
  5057.1     .07       0  5162.6    .035       0  5490.9     .05       0
  5769.8    .045       0
Bank Sta=5006.3,5013.8
XS Rating Curve= 0 ,0
Exp/Cntr=0.3,0.1

Type RM Length L Ch R = 1 ,3768    ,455,455,455
BEGIN DESCRIPTION:
GERONIMO TRIBUTARY 7 6.0
END DESCRIPTION:
XS GIS Cut Line= 3
      2302335.31     13781462.68        2301925.       13781125.
      2301625.01     13780875.01
#Sta/Elev= 30
  4473.2  563.23  4499.6  562.43  4507.4  563.02  4542.6  561.31  4562.4  561.54
    4600  561.12  4628.7  559.53  4635.1  560.56  4644.7  560.37  4663.8  560.43
  4684.6  558.29  4802.7  557.18  4876.2  555.85  4898.4  556.95  4904.9  555.86
  4947.9  554.68  4962.3  555.49  4968.7  555.03  4979.3  551.89  4979.8  551.39
  4986.9  551.89  5001.4  554.84  5032.6  554.74  5075.5  557.92  5081.8  557.67
  5096.4  557.65  5160.8  561.68  5246.7   564.7  5315.9  566.04  5395.1  567.81
#Mann= 9 ,-1 , 0
  4473.2    .035       0  4562.4     .05       0  4644.7    .035       0
  4802.7     .07       0  4979.3     .05       0  4986.9     .07       0
  5081.8     .05       0  5246.7     .07       0  5315.9     .05       0
Bank Sta=4979.3,4986.9
XS Rating Curve= 0 ,0
Exp/Cntr=0.3,0.1

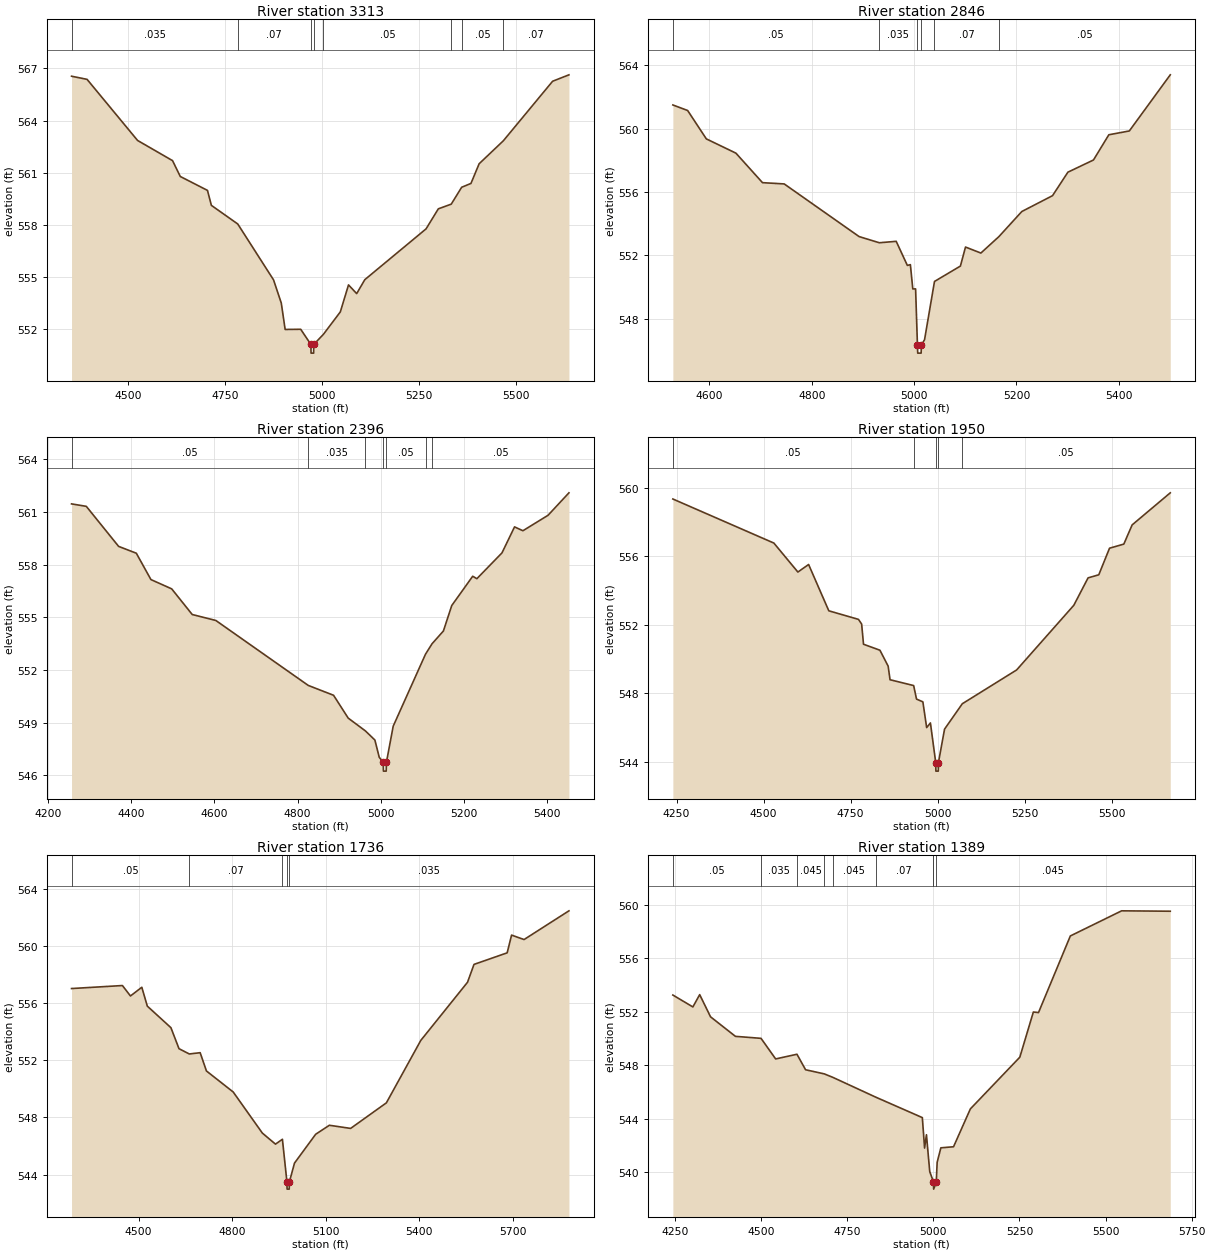
Type RM Length L Ch R = 1 ,3313    ,467,467,467
BEGIN DESCRIPTION:
GERONIMO TRIBUTARY 7 5.0
END DESCRIPTION:
XS GIS Cut Line= 3
        2302375.     13781625.01        2302325.       13780975.
      2301724.99       13780775.
#Sta/Elev= 30
    4353  566.55  4393.1  566.37  4523.5  562.86  4613.8   561.7  4633.8  560.79
    4704  559.99  4714.1  559.13  4782.2  558.06  4874.6  554.85  4894.6  553.52
  4904.6     552  4944.8  552.01    4971  551.14  4971.5  550.64  4978.1  550.64
  4978.6  551.14  5003.4  551.72  5047.1  553.01  5068.2  554.56  5089.3  554.06
  5110.3  554.86  5268.5  557.78  5300.1  558.93  5333.5   559.2  5360.4  560.17
  5384.4  560.39  5405.5  561.52    5468  562.84  5595.2  566.26  5637.4  566.63
#Mann= 8 ,-1 , 0
    4353    .035       0  4782.2     .07       0    4971     .05       0
  4978.6     .07       0  5003.4     .05       0  5333.5     .07       0
  5360.4     .05       0    5468     .07       0
Bank Sta=4971,4978.6
XS Rating Curve= 0 ,0
Exp/Cntr=0.3,0.1

Type RM Length L Ch R = 1 ,2846    ,450,450,450
BEGIN DESCRIPTION:
GERONIMO TRIBUTARY 7 4.0
END DESCRIPTION:
XS GIS Cut Line= 3
      2302824.97     13780824.98        2302425.       13780575.
      2301924.96       13780575.
#Sta/Elev= 30
  4528.8  561.49  4557.7  561.14  4594.2  559.35    4652  558.45  4703.9  556.59
  4746.3  556.51  4892.6  553.19  4932.1   552.8  4965.1  552.89  4986.9  551.37
  4992.8  551.42  4997.5  549.89    5003  549.89  5006.6  546.34  5007.1  545.84
  5013.8  545.84  5014.3  546.34  5020.5  546.69  5039.9  550.36  5090.5  551.33
  5100.5  552.53  5130.5  552.15  5165.8  553.19  5210.5  554.77  5270.5  555.77
  5300.5  557.25  5350.5  558.02  5380.5  559.61  5420.5  559.85  5500.5  563.39
#Mann= 6 ,-1 , 0
  4528.8     .05       0  4932.1    .035       0  5006.6    .035       0
  5014.3    .035       0  5039.9     .07       0  5165.8     .05       0
Bank Sta=5006.6,5014.3
XS Rating Curve= 0 ,0
Exp/Cntr=0.3,0.1

Type RM Length L Ch R = 1 ,2396    ,446,446,446
BEGIN DESCRIPTION:
GERONIMO TRIBUTARY 7 3.0
END DESCRIPTION:
XS GIS Cut Line= 3
        2302875.       13780725.        2302375.       13780175.
      2301924.97       13780225.
#Sta/Elev= 30
  4256.3  561.46  4291.8  561.32  4369.5  559.04  4412.1  558.65  4447.2  557.15
  4497.2  556.62  4546.5  555.16  4603.3  554.82  4825.6  551.12  4886.4  550.56
  4921.6  549.26    4963  548.53  4985.8  548.01  4996.2  547.03  5005.8  546.74
  5006.3  546.24    5013  546.24  5013.5  546.74  5029.8   548.8  5107.5   552.9
  5123.1  553.49  5150.5  554.22  5170.6  555.67    5221  557.34    5231   557.2
  5291.4  558.67  5321.6  560.15  5341.7  559.93  5402.1  560.81  5452.4  562.09
#Mann= 7 ,-1 , 0
  4256.3     .05       0  4825.6    .035       0    4963     .05       0
  5005.8     .05       0  5013.5     .05       0  5107.5     .07       0
  5123.1     .05       0
Bank Sta=5005.8,5013.5
XS Rating Curve= 0 ,0
Exp/Cntr=0.3,0.1

Type RM Length L Ch R = 1 ,1950    ,214,214,214
BEGIN DESCRIPTION:
GERONIMO TRIBUTARY 7 2.0
END DESCRIPTION:
XS GIS Cut Line= 3
      2302925.01     13780525.02        2302625.       13779825.
      2301974.98       13779975.
#Sta/Elev= 30
  4239.5  559.33  4529.6  556.76  4598.6  555.07  4629.4  555.51  4687.4  552.81
  4772.6  552.31  4781.7  552.04  4787.1  550.86  4834.3  550.51  4857.9  549.58
  4863.3  548.79  4931.1  548.45  4939.4  547.66  4957.6   547.5  4968.5     546
  4979.3  546.27  4994.5  543.96    4995  543.46  5001.8  543.46  5002.3  543.96
  5019.9  545.91  5070.9  547.39  5226.9  549.36  5391.1  553.13  5432.1  554.73
  5462.9  554.91  5493.7  556.46  5534.8   556.7  5558.7  557.82  5668.2  559.69
#Mann= 5 ,-1 , 0
  4239.5     .05       0  4931.1     .07       0  4994.5     .05       0
  5002.3     .07       0  5070.9     .05       0
Bank Sta=4994.5,5002.3
XS Rating Curve= 0 ,0
Exp/Cntr=0.3,0.1

Type RM Length L Ch R = 1 ,1736    ,347,347,347
BEGIN DESCRIPTION:
A19065
END DESCRIPTION:
XS GIS Cut Line= 4
      2302973.34      13780154.5      2302795.75     13779643.24
      2302349.07     13779562.51      2301751.67     13779514.07
#Sta/Elev= 30
  4285.3  557.02  4448.4  557.23  4474.2   556.5  4510.6  557.11  4528.2  555.79
  4603.9  554.28  4629.8  552.81  4662.9  552.44  4697.6  552.53  4717.8  551.25
  4803.5  549.78  4897.1   546.9  4939.1  546.13  4961.3  546.47  4975.8  543.48
  4976.3  542.98  4983.1  542.98  4983.6  543.48    5000   544.8  5067.9  546.82
  5111.8  547.45    5180  547.23  5294.6  549.02  5404.9  553.39  5554.7  557.46
  5575.5  558.71  5681.8  559.52  5695.9  560.76    5736  560.45  5879.8  562.46
#Mann= 5 ,-1 , 0
  4285.3     .05       0  4662.9     .07       0  4961.3    .035       0
  4975.8    .035       0  4983.6    .035       0
Bank Sta=4975.8,4983.6
XS Rating Curve= 0 ,0
Exp/Cntr=0.3,0.1

Type RM Length L Ch R = 1 ,1389    ,381,381,381
BEGIN DESCRIPTION:
A19064
END DESCRIPTION:
XS GIS Cut Line= 3
      2302946.43     13779869.26      2302784.98     13779363.39
      2301934.99     13779029.85
#Sta/Elev= 30
  4243.8  553.26  4301.9  552.37  4321.7  553.29  4353.2  551.63  4425.4  550.17
  4499.8  550.02  4542.2  548.48  4604.1  548.83  4629.1  547.67  4683.6  547.36
  4708.4   547.1  4832.9  545.62  4968.1  544.09  4974.6  541.81    4980  542.81
  4989.6  540.05  4998.2  539.44  5000.4  539.24  5000.9  538.74  5008.5  539.24
  5011.1  540.75  5021.9  541.83  5058.7  541.91  5107.5  544.74  5251.1  548.61
  5290.4  551.99  5305.4  551.95  5397.8  557.68  5546.7  559.56  5687.9  559.53
#Mann= 9 ,-1 , 0
  4243.8     .05       0  4499.8    .035       0  4604.1    .045       0
  4683.6     .07       0  4708.4    .045       0  4832.9     .07       0
  4998.2    .045       0  5000.4    .045       0  5008.5    .045       0
Bank Sta=5000.4,5008.5
XS Rating Curve= 0 ,0
Exp/Cntr=0.3,0.1