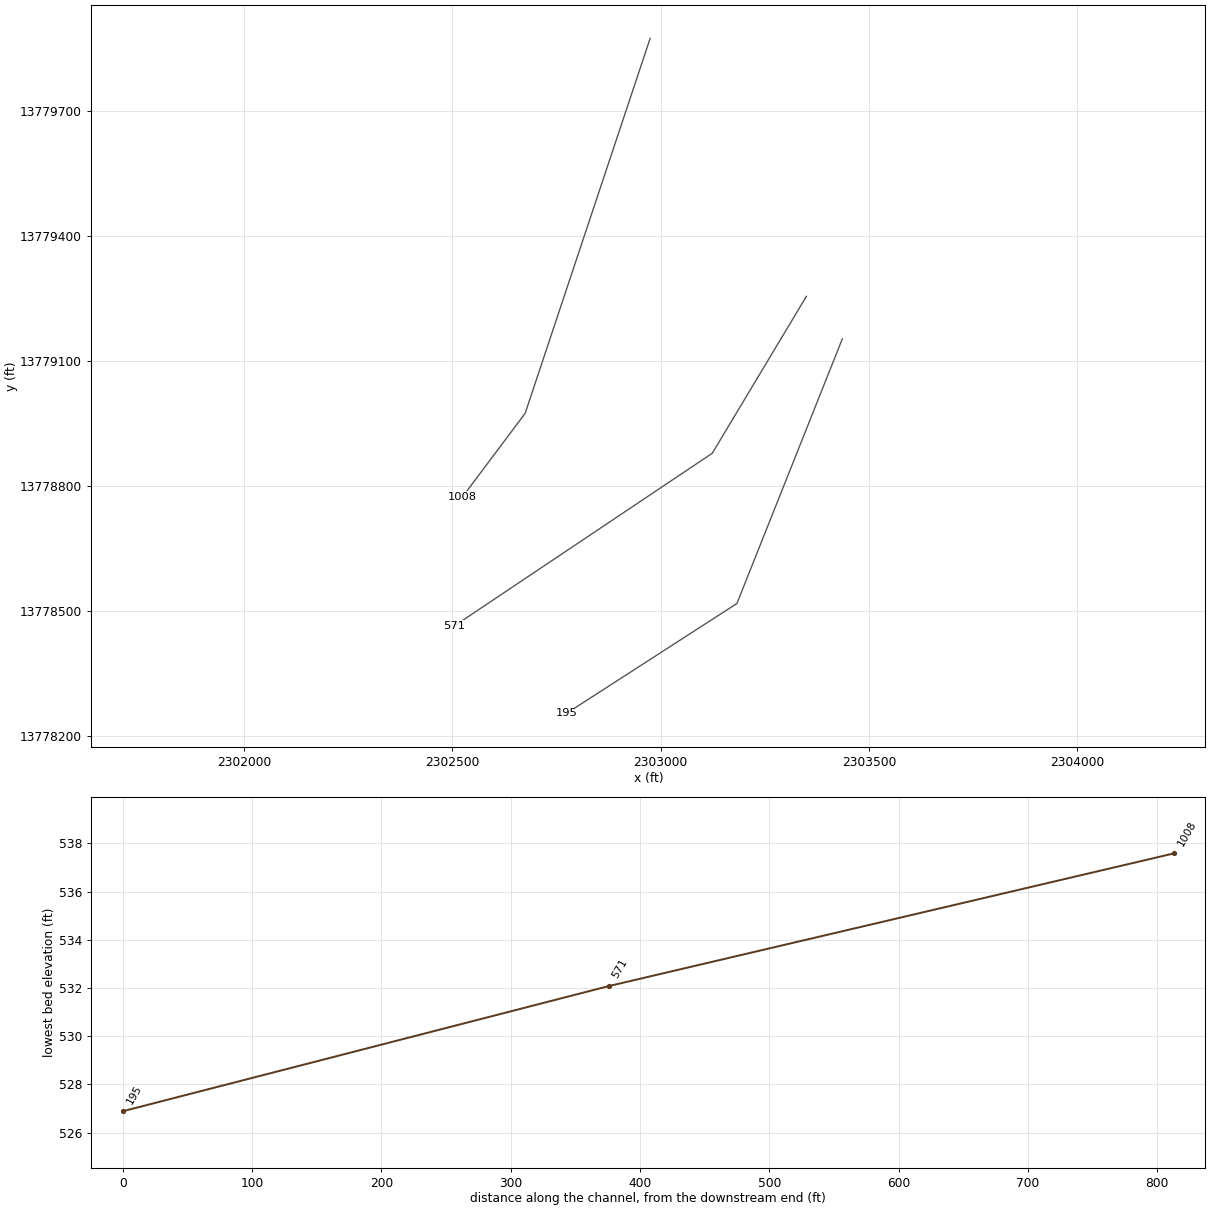
HEC-RAS study GERONIMO TRIBUTARY 7.prj: GERONIMO TRIBUTARY 7 Base Level Engineering

--- GERONIMO TRIBUTARY 7.g01 (geometry) --- (continued)

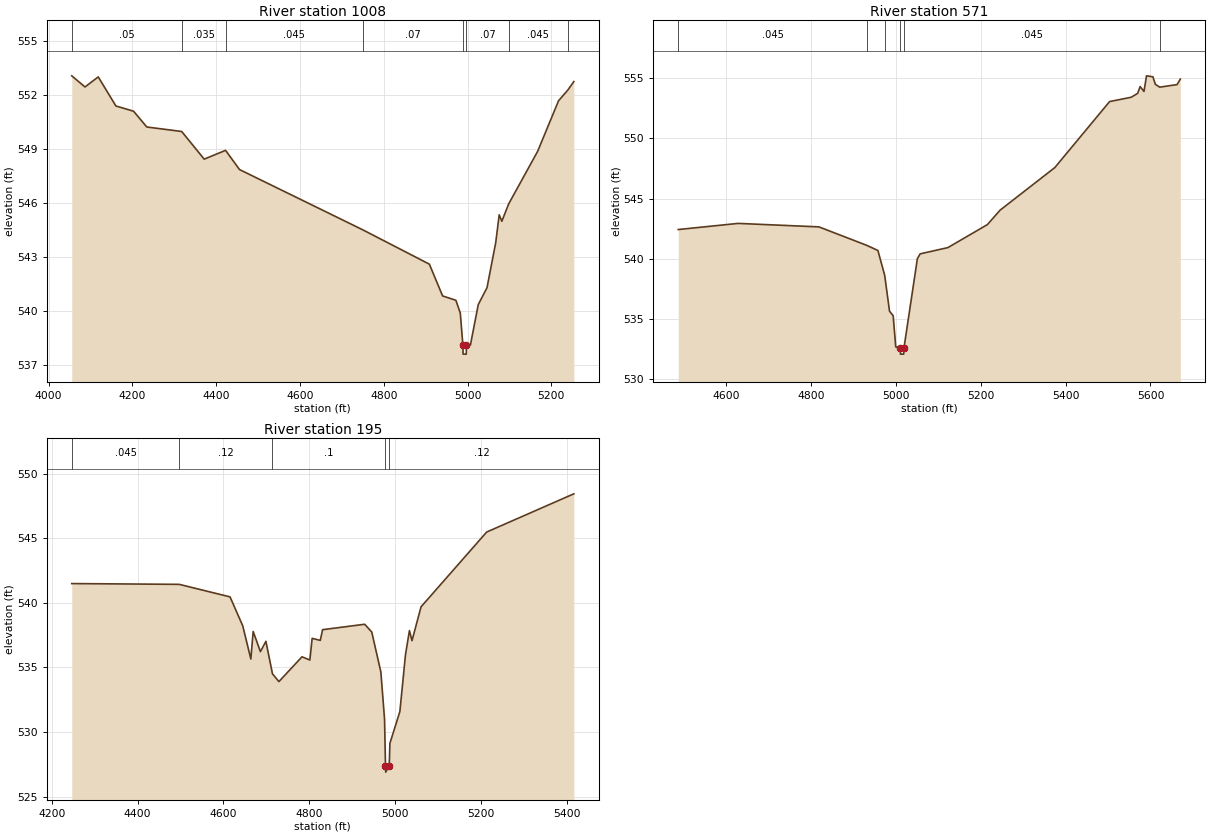
Type RM Length L Ch R = 1 ,1008    ,437,437,437
BEGIN DESCRIPTION:
GERONIMO TRIBUTARY 7 1.0
END DESCRIPTION:
XS GIS Cut Line= 3
      2302974.99     13779874.97        2302675.       13778975.
      2302524.97     13778774.96
#Sta/Elev= 30
  4055.2  553.08  4086.8  552.46  4118.4  553.02  4160.6   551.4  4202.7  551.11
  4234.4  550.23  4317.6  549.98  4371.4  548.44  4422.4  548.93  4455.7  547.86
  4749.4  544.51    4909  542.59  4940.6  540.82  4972.2  540.58  4982.8  539.87
    4989  538.08  4989.5  537.58  4997.1  537.58  4997.6  538.08    5007  538.09
  5025.7  540.34  5046.6  541.28  5067.4  543.79  5075.7  545.34    5082  544.98
  5098.4  545.95  5167.4  548.87  5217.4  551.69  5239.6  552.29  5253.9  552.76
#Mann= 8 ,-1 , 0
  4055.2     .05       0  4317.6    .035       0  4422.4    .045       0
  4749.4     .07       0    4989     .05       0  4997.6     .07       0
  5098.4    .045       0  5239.6    .035       0
Bank Sta=4989,4997.6
XS Rating Curve= 0 ,0
Exp/Cntr=0.3,0.1

Type RM Length L Ch R = 1 ,571     ,376,376,376
BEGIN DESCRIPTION:
A19063
END DESCRIPTION:
XS GIS Cut Line= 3
      2303350.06     13779255.78      2303124.03     13778879.05
      2302505.18     13778464.69
#Sta/Elev= 30
  4486.3  542.43  4627.7  542.94  4818.2  542.65  4931.4  541.11  4957.2  540.69
  4973.2  538.63  4984.6  535.65  4993.2  535.27  4999.3  532.68  5009.9  532.58
  5010.4  532.08  5018.1  532.08  5018.6  532.58  5050.3  540.01  5056.8  540.41
  5122.3  540.93  5215.4  542.84  5245.4  544.04  5374.5  547.58  5503.6  553.06
  5554.6  553.42  5569.7  553.74  5575.7  554.31  5584.7   553.9  5590.7   555.2
  5605.7  555.12  5611.7  554.49  5621.8  554.26  5662.7  554.47  5670.4  554.93
#Mann= 6 ,-1 , 0
  4486.3    .045       0  4931.4     .12       0  4973.2    .045       0
  5009.9    .045       0  5018.6    .045       0  5621.8     .12       0
Bank Sta=5009.9,5018.6
XS Rating Curve= 0 ,0
Exp/Cntr=0.3,0.1

Type RM Length L Ch R = 1 ,195     ,0,0,0
BEGIN DESCRIPTION:
A19062
END DESCRIPTION:
XS GIS Cut Line= 3
      2303436.16     13779153.52      2303183.22     13778518.48
      2302774.22     13778254.78
#Sta/Elev= 30
  4246.7  541.49  4497.2  541.43  4615.6  540.46  4645.2  538.22  4664.1  535.65
  4669.5  537.78  4686.4  536.22  4699.2  537.02  4714.5   534.5  4729.5   533.9
  4783.3  535.82  4801.6  535.57    4807  537.25  4825.9  537.09  4831.3  537.92
  4929.4  538.34  4945.9  537.74  4967.1  534.65  4975.7     531  4977.9  527.39
  4978.4  526.89  4986.6  527.39  4988.2  529.12  5011.4  531.58  5024.5  535.98
  5033.7  537.85  5039.7  537.07  5060.8  539.69  5213.7  545.48  5416.9  548.44
#Mann= 5 ,-1 , 0
  4246.7    .045       0  4497.2     .12       0  4714.5      .1       0
  4977.9     .05       0  4986.6     .12       0
Bank Sta=4977.9,4986.6
XS Rating Curve= 0 ,0
Exp/Cntr=0.3,0.1

Chan Stop Cuts=-1
Use User Specified Reach Order=0
Composite Channel Slope=5