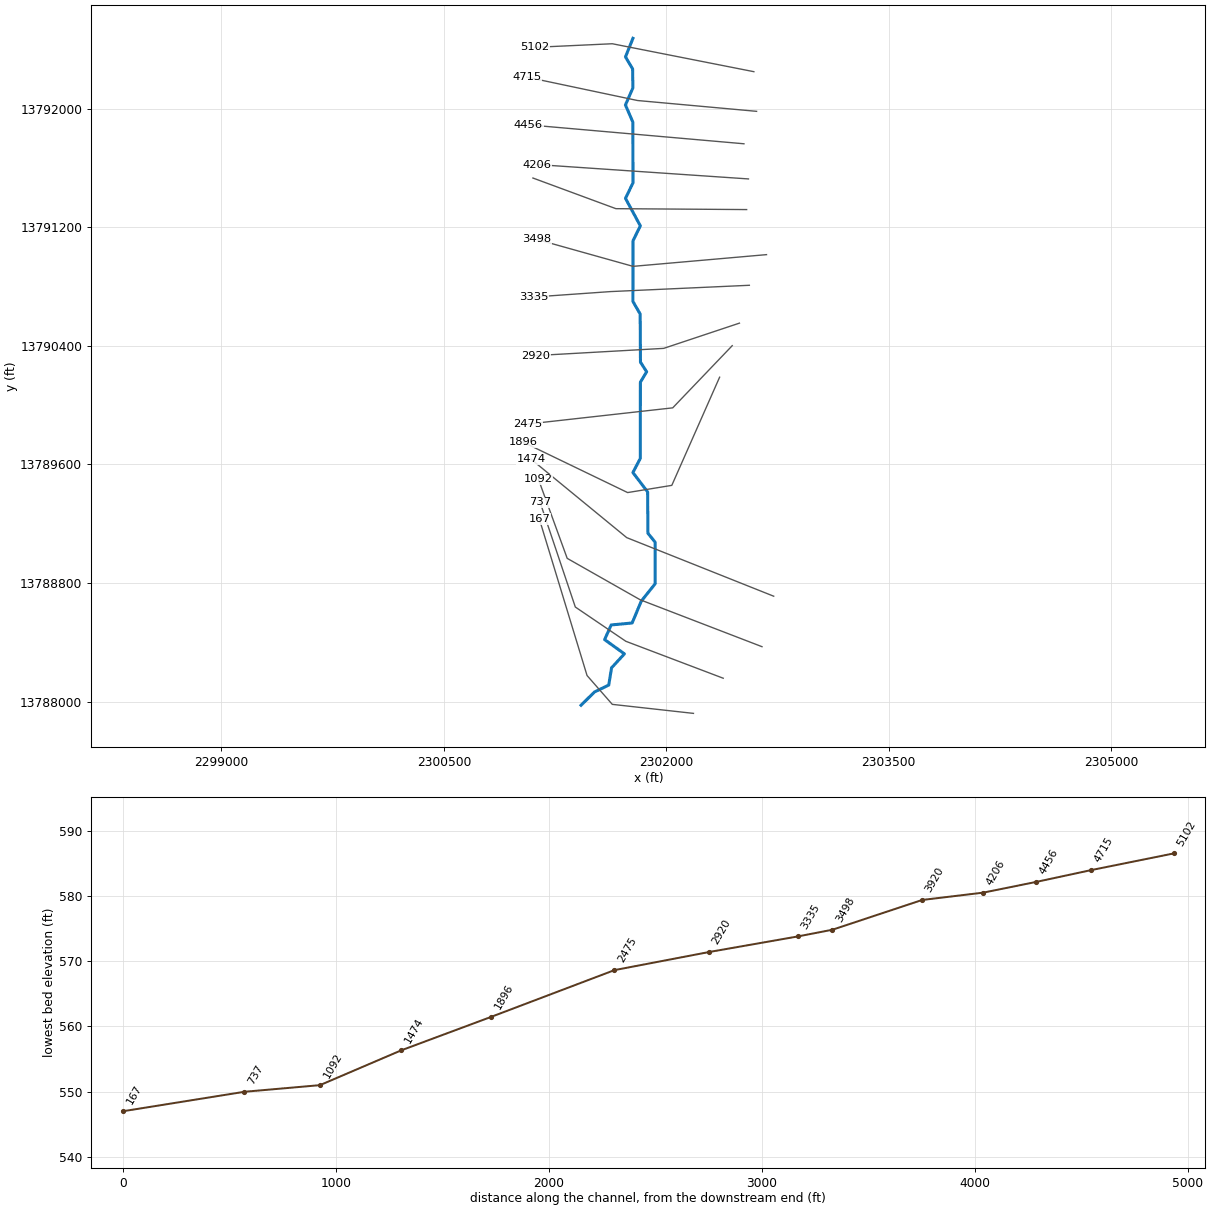
--- GERONIMO TRIBUTARY 9.prj (project) ---

Proj Title=GERONIMO TRIBUTARY 9 Base Level Engineering
Current Plan=p01
Default Exp/Contr=0.3,0.1
English Units
Geom File=g01
Flow File=f01
Plan File=p01
BEGIN DESCRIPTION:
GERONIMO TRIBUTARY 9
END DESCRIPTION:

--- GERONIMO TRIBUTARY 9.p01 (plan) ---

Plan Title=Multiple Run
Short Identifier=Multiple
Geom File=g01
Flow File=f01
Subcritical Flow
K Sum by GR= 0
Std Step Tol= 0.01
Critical Tol= 0.01
Num of Std Step Trials= 20
Max Error Tol= 0.3
Flow Tol Ratio= 0.001
Split Flow NTrial= 30
Split Flow Tol= 0.02
Split Flow Ratio= 0.02
Log Output Level= 0
Friction Slope Method= 1
Unsteady Friction Slope Method= 2
Unsteady Bridges Friction Slope Method= 1
Parabolic Critical Depth
Global Vel Dist=  1 , 1 , 1
Global Log Level= 0
CheckData=True
Encroach Param= -1, 0, 0, 0
BEGIN DESCRIPTION:
Multiple Run
END DESCRIPTION:

--- GERONIMO TRIBUTARY 9.f01 (steady flow) ---

Flow Title=Multiple
Number of Profiles=7
Profile Names=10-year,25-year,50-year,1pct_min,100-year,1pct_plu,500-year
River Rch & RM= GERONIMO TRIBUTA,Reach-1,5102
     253     385     497     312     623    1243     968
River Rch & RM= GERONIMO TRIBUTA,Reach-1,1474
     594     955    1281     832    1660    3312    2761
Boundary for River Rch & Prof#=GERONIMO TRIBUTA,Reach-1,1
Up Type=0
Dn Type=3
Dn Slope=0.005
Boundary for River Rch & Prof#=GERONIMO TRIBUTA,Reach-1,2
Up Type=0
Dn Type=3
Dn Slope=0.005
Boundary for River Rch & Prof#=GERONIMO TRIBUTA,Reach-1,3
Up Type=0
Dn Type=3
Dn Slope=0.005
Boundary for River Rch & Prof#=GERONIMO TRIBUTA,Reach-1,4
Up Type=0
Dn Type=3
Dn Slope=0.005
Boundary for River Rch & Prof#=GERONIMO TRIBUTA,Reach-1,5
Up Type=0
Dn Type=3
Dn Slope=0.005
Boundary for River Rch & Prof#=GERONIMO TRIBUTA,Reach-1,6
Up Type=0
Dn Type=3
Dn Slope=0.005
Boundary for River Rch & Prof#=GERONIMO TRIBUTA,Reach-1,7
Up Type=0
Dn Type=3
Dn Slope=0.005

--- GERONIMO TRIBUTARY 9.g01 (geometry) ---

Geom Title=Existing Conditions

River Reach=GERONIMO TRIBUTA,Reach-1
Reach XY= 30
      2301775.00     13792475.00      2301724.53     13792350.00
      2301772.73     13792269.07      2301774.49     13792140.22
      2301724.18     13792025.00      2301774.48     13791909.78
      2301775.19     13791499.91      2301724.71     13791395.17
      2301824.92     13791209.61      2301775.54     13791109.79
      2301774.80     13790699.92      2301823.78     13790614.50
      2301825.66     13790290.16      2301867.44     13790225.00
      2301825.18     13790155.02      2301824.46     13789640.21
      2301774.61     13789545.13      2301873.94     13789414.56
      2301875.96     13789135.40      2301925.00     13789075.00
      2301925.04     13788794.98      2301830.85     13788677.29
      2301769.58     13788530.18      2301628.31     13788516.88
      2301583.99     13788418.01      2301717.47     13788321.86
      2301630.56     13788227.42      2301611.74     13788111.35
      2301515.31     13788064.28      2301425.00     13787975.00

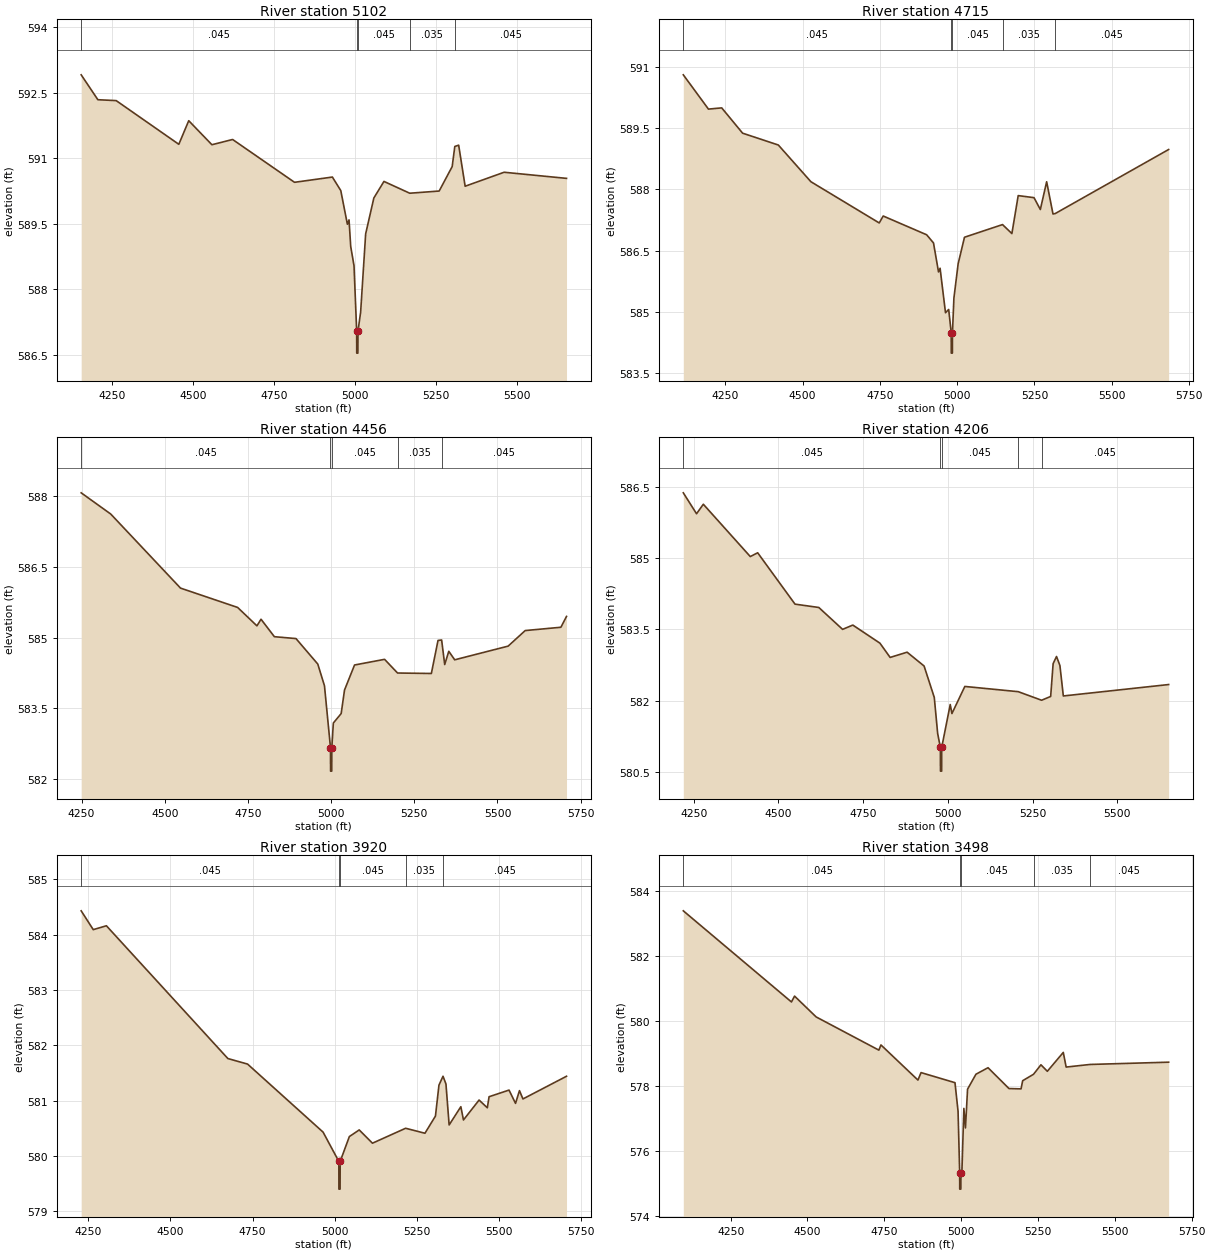
Type RM Length L Ch R = 1,5102,387,387,387
BEGIN DESCRIPTION:
A19087
END DESCRIPTION:
XS GIS Cut Line= 3
      2302590.43     13792250.00      2301635.71     13792438.51
      2301112.73     13792414.19
#Sta/Elev= 30
  4155.8  592.91  4207.3  592.34  4263.7  592.32  4456.9  591.32  4487.5  591.86
  4558.9  591.31  4622.8  591.43  4813.7  590.45  4930.5  590.57  4956.4  590.26
  4976.7  589.49  4981.8  589.59  4987.0  588.98  4997.2  588.54  5005.4  587.04
  5005.6  586.54  5009.1  586.54  5009.4  587.04  5017.6  587.48  5033.1  589.27
  5058.3  590.09  5089.5  590.47  5169.0  590.20  5259.8  590.25  5299.9  590.81
  5308.0  591.27  5319.9  591.30  5339.9  590.36  5460.0  590.68  5652.5  590.54
#Mann=5,-1,0
  4155.8   0.045       0  5005.4   0.045       0  5009.4   0.045       0
  5169.0   0.035       0  5308.0   0.045       0
Bank Sta=5005.4,5009.4
Exp/Cntr=0.3,0.1

Type RM Length L Ch R = 1,4715,259,259,259
BEGIN DESCRIPTION:
A19086
END DESCRIPTION:
XS GIS Cut Line= 3
      2302608.73     13791982.43      2301805.98     13792055.41
      2301059.05     13792213.29
#Sta/Elev= 30
  4114.4  590.81  4195.7  589.97  4238.6  590.00  4306.2  589.38  4421.7  589.09
  4527.1  588.19  4748.0  587.18  4760.8  587.35  4901.4  586.89  4923.5  586.69
  4939.7  585.98  4944.8  586.07  4962.3  584.98  4972.6  585.06  4980.8  584.49
  4981.0  583.99  4984.5  583.99  4984.8  584.49  4989.5  585.34  5003.2  586.18
  5023.7  586.83  5146.7  587.14  5177.0  586.92  5197.4  587.85  5248.5  587.80
  5269.0  587.51  5289.4  588.19  5309.9  587.40  5317.0  587.41  5683.9  588.98
#Mann=5,-1,0
  4114.4   0.045       0  4980.8   0.045       0  4984.8   0.045       0
  5146.7   0.035       0  5317.0   0.045       0
Bank Sta=4980.8,4984.8
Exp/Cntr=0.3,0.1

Type RM Length L Ch R = 1,4456,250,250,250
BEGIN DESCRIPTION:
A19085
END DESCRIPTION:
XS GIS Cut Line= 2
      2302523.52     13791763.52      2301070.22     13791891.21
#Sta/Elev= 30
  4248.7  588.07  4337.6  587.62  4547.3  586.05  4719.0  585.64  4777.0  585.25
  4789.3  585.39  4829.4  585.02  4894.4  584.98  4959.9  584.44  4980.0  583.98
  4998.1  582.67  4998.4  582.17  5001.9  582.17  5002.1  582.67  5006.7  583.19
  5030.2  583.39  5040.3  583.89  5070.4  584.42  5160.7  584.54  5199.7  584.25
  5301.3  584.24  5321.3  584.94  5332.2  584.95  5341.4  584.43  5353.7  584.71
  5371.5  584.53  5532.1  584.82  5583.4  585.15  5690.7  585.22  5707.6  585.45
#Mann=5,-1,0
  4248.7   0.045       0  4998.1   0.045       0  5002.1   0.045       0
  5199.7   0.035       0  5332.2   0.045       0
Bank Sta=4998.1,5002.1
Exp/Cntr=0.3,0.1

Type RM Length L Ch R = 1,4206,286,286,286
BEGIN DESCRIPTION:
A19084
END DESCRIPTION:
XS GIS Cut Line= 2
      2302553.98     13791526.35      2301124.88     13791623.65
#Sta/Elev= 30
  4219.3  586.37  4258.4  585.93  4278.4  586.13  4417.0  585.03  4438.8  585.11
  4549.0  584.03  4619.2  583.96  4689.4  583.50  4719.6  583.59  4799.6  583.21
  4829.7  582.91  4879.8  583.02  4929.9  582.73  4960.0  582.07  4970.0  581.31
  4978.0  581.02  4978.3  580.52  4981.8  580.52  4982.0  581.02  5007.1  581.92
  5012.1  581.73  5050.2  582.30  5207.8  582.19  5276.8  582.01  5303.5  582.09
  5310.8  582.78  5320.8  582.93  5330.8  582.74  5340.9  582.10  5651.7  582.34
#Mann=5,-1,0
  4219.3   0.045       0  4978.0   0.045       0  4982.0   0.045       0
  5207.8   0.035       0  5276.8   0.045       0
Bank Sta=4978,4982
Exp/Cntr=0.3,0.1

Type RM Length L Ch R = 1,3920,422,422,422
BEGIN DESCRIPTION:
A19083
END DESCRIPTION:
XS GIS Cut Line= 3
      2302541.75     13791319.59      2301660.04     13791325.68
      2301100.56     13791532.44
#Sta/Elev= 30
  4228.2  584.43  4265.0  584.09  4305.0  584.16  4675.0  581.76  4735.0  581.66
  4965.0  580.43  5013.0  579.90  5013.2  579.40  5016.7  579.40  5017.0  579.90
  5045.0  580.35  5075.0  580.47  5115.3  580.23  5216.4  580.50  5275.2  580.41
  5307.2  580.72  5317.9  581.28  5330.3  581.44  5339.2  581.30  5348.9  580.56
  5384.6  580.89  5392.5  580.65  5440.1  581.01  5465.2  580.87  5470.5  581.07
  5531.3  581.19  5551.1  580.95  5563.1  581.18  5573.7  581.03  5706.4  581.44
#Mann=5,-1,0
  4228.2   0.045       0  5013.0   0.045       0  5017.0   0.045       0
  5216.4   0.035       0  5330.3   0.045       0
Bank Sta=5013,5017
Exp/Cntr=0.3,0.1

Type RM Length L Ch R = 1,3498,163,163,163
BEGIN DESCRIPTION:
A19082
END DESCRIPTION:
XS GIS Cut Line= 3
      2302675.59     13791015.54      2301775.58     13790936.49
      2301124.95     13791118.91
#Sta/Elev= 30
  4095.9  583.38  4447.8  580.58  4457.9  580.76  4528.2  580.12  4732.3  579.10
  4739.0  579.26  4859.4  578.18  4869.5  578.41  4979.9  578.10  4989.9  577.22
  4995.2  575.33  4995.4  574.83  4998.9  574.83  4999.2  575.33  5002.3  575.33
  5008.8  577.31  5014.0  576.71  5020.8  577.90  5048.1  578.36  5087.4  578.56
  5155.6  577.92  5194.9  577.91  5200.1  578.16  5235.6  578.36  5259.6  578.65
  5280.4  578.45  5332.3  579.03  5341.6  578.58  5419.1  578.66  5675.1  578.73
#Mann=5,-1,0
  4095.9   0.045       0  4995.2   0.045       0  4999.2   0.045       0
  5235.6   0.035       0  5419.1   0.045       0
Bank Sta=4995.2,4999.2
Exp/Cntr=0.3,0.1

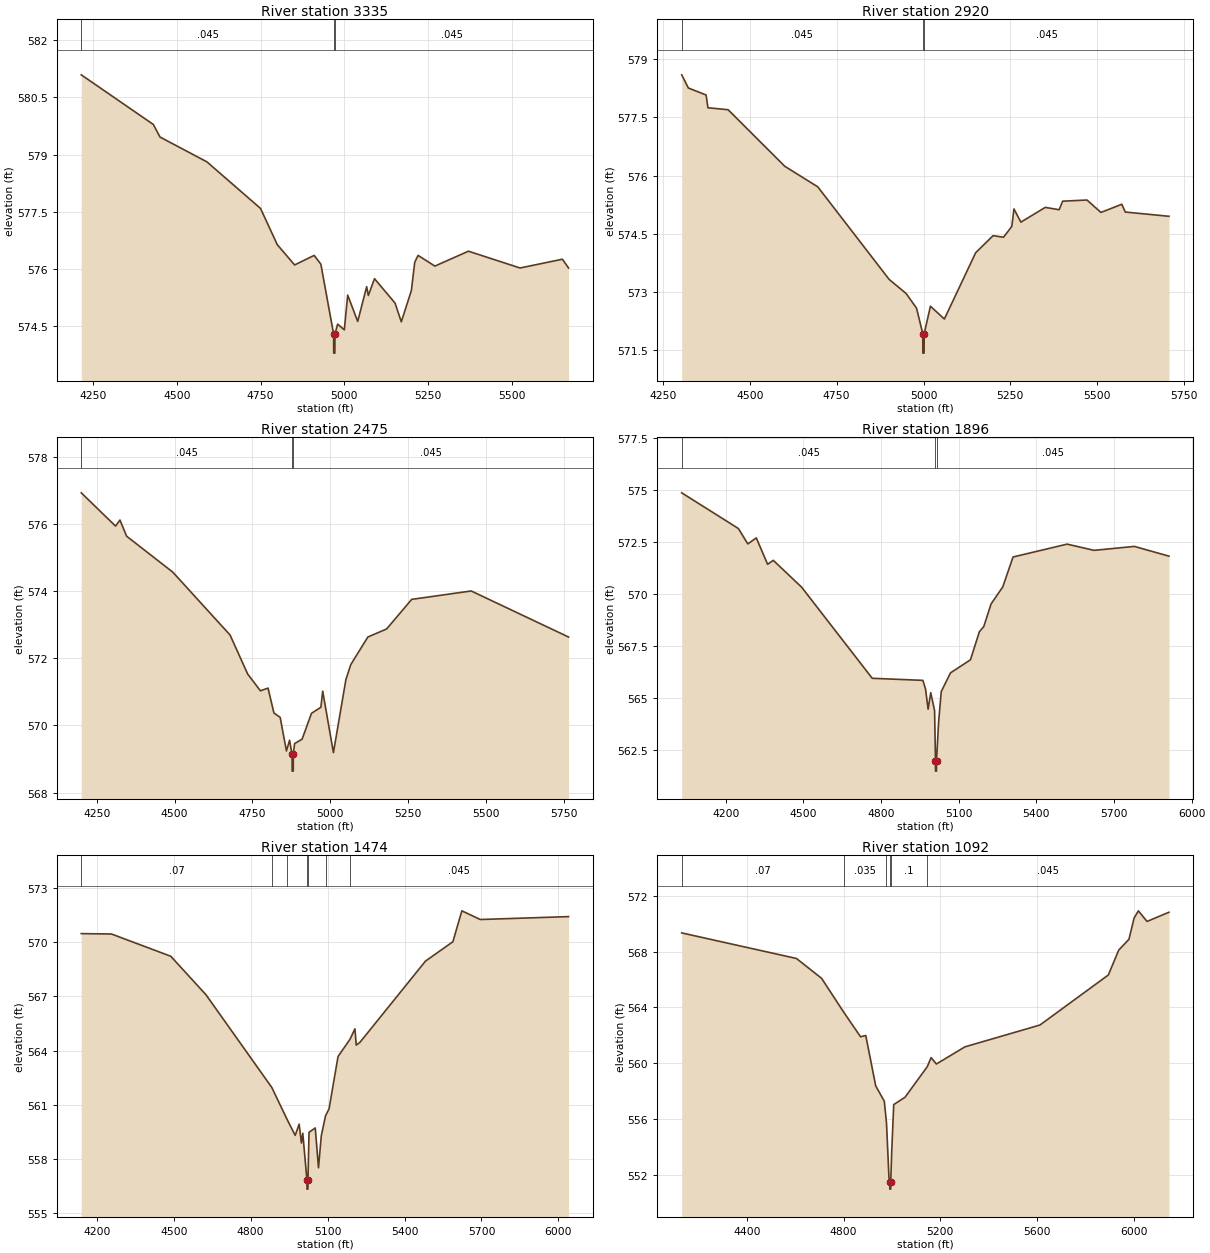
Type RM Length L Ch R = 1,3335,415,415,415
BEGIN DESCRIPTION:
A19081
END DESCRIPTION:
XS GIS Cut Line= 3
      2302559.99     13790808.78      2301623.55     13790766.22
      2301106.65     13790729.73
#Sta/Elev= 30
  4214.1  581.09  4429.3  579.79  4449.3  579.46  4589.5  578.81  4749.6  577.59
  4799.7  576.64  4851.4  576.11  4909.8  576.36  4929.8  576.13  4967.9  574.30
  4968.1  573.80  4971.6  573.80  4971.9  574.30  4979.9  574.56  4999.9  574.41
  5009.9  575.32  5039.9  574.63  5066.6  575.54  5071.6  575.31  5090.0  575.75
  5151.5  575.11  5170.1  574.62  5200.2  575.44  5210.2  576.18  5220.2  576.36
  5270.4  576.08  5370.6  576.47  5524.9  576.03  5651.3  576.26  5669.7  576.03
#Mann=3,-1,0
  4214.1   0.045       0  4967.9   0.045       0  4971.9   0.045       0
Bank Sta=4967.9,4971.9
Exp/Cntr=0.3,0.1

Type RM Length L Ch R = 1,2920,445,445,445
BEGIN DESCRIPTION:
A19080
END DESCRIPTION:
XS GIS Cut Line= 3
      2302493.12     13790553.37      2301982.33     13790383.11
      2301119.42     13790334.49
#Sta/Elev= 30
  4303.9  578.60  4323.0  578.26  4374.1  578.08  4379.4  577.75  4437.4  577.70
  4600.7  576.24  4695.6  575.71  4901.2  573.32  4949.8  572.96  4979.9  572.58
  4997.9  571.92  4998.1  571.42  5001.6  571.42  5001.9  571.92  5019.9  572.63
  5060.0  572.30  5150.1  574.01  5200.2  574.45  5230.3  574.41  5254.2  574.69
  5260.3  575.14  5280.3  574.80  5350.5  575.18  5390.5  575.12  5400.5  575.34
  5470.6  575.37  5510.7  575.05  5570.8  575.26  5580.8  575.06  5706.6  574.95
#Mann=3,-1,0
  4303.9   0.045       0  4997.9   0.045       0  5001.9   0.045       0
Bank Sta=4997.9,5001.9
Exp/Cntr=0.3,0.1

Type RM Length L Ch R = 1,2475,579,579,579
BEGIN DESCRIPTION:
A19079
END DESCRIPTION:
XS GIS Cut Line= 3
      2302444.46     13790401.32      2302043.14     13789981.76
      2301064.14     13789872.30
#Sta/Elev= 30
  4199.9  576.92  4310.0  575.93  4324.2  576.11  4345.6  575.63  4494.0  574.56
  4678.0  572.69  4734.5  571.53  4775.5  571.03  4800.0  571.11  4818.9  570.37
  4839.0  570.24  4859.1  569.24  4869.2  569.56  4877.2  569.14  4877.5  568.64
  4881.0  568.64  4881.2  569.14  4885.3  569.46  4909.4  569.59  4939.6  570.36
  4969.8  570.54  4975.6  571.02  5010.1  569.19  5050.3  571.37  5065.9  571.81
  5120.7  572.63  5181.1  572.87  5261.6  573.75  5452.8  574.00  5765.6  572.63
#Mann=3,-1,0
  4199.9   0.045       0  4877.2   0.045       0  4881.2   0.045       0
Bank Sta=4877.2,4881.2
Exp/Cntr=0.3,0.1

Type RM Length L Ch R = 1,1896,422,422,422
BEGIN DESCRIPTION:
A19078
END DESCRIPTION:
XS GIS Cut Line= 4
      2302359.36     13790188.52      2302037.06     13789458.78
      2301739.09     13789410.14      2301034.37     13789750.35
#Sta/Elev= 30
  4030.2  574.87  4249.3  573.15  4285.5  572.41  4318.3  572.70  4362.0  571.43
  4383.9  571.62  4493.2  570.33  4766.1  565.94  4961.7  565.84  4971.9  565.43
  4982.0  564.45  4992.1  565.25  5007.0  564.38  5010.4  561.97  5010.7  561.47
  5014.2  561.47  5014.4  561.97  5022.5  563.82  5032.7  565.30  5068.4  566.20
  5145.5  566.83  5180.0  568.18  5197.0  568.43  5225.2  569.52  5270.4  570.34
  5310.0  571.78  5519.0  572.40  5623.0  572.10  5778.8  572.29  5912.4  571.82
#Mann=3,-1,0
  4030.2   0.045       0  5010.4   0.045       0  5014.4   0.045       0
Bank Sta=5010.4,5014.4
Exp/Cntr=0.3,0.1

Type RM Length L Ch R = 1,1474,382,382,382
BEGIN DESCRIPTION:
A19077
END DESCRIPTION:
XS GIS Cut Line= 3
      2302724.21     13788710.82      2301733.01     13789106.08
      2301089.19     13789634.50
#Sta/Elev= 30
  4139.6  570.46  4257.2  570.44  4488.5  569.21  4626.0  567.08  4882.4  561.96
  4940.9  560.23  4973.7  559.31  4989.2  559.93  4998.0  558.89  5003.3  559.43
  5019.5  556.84  5019.8  556.34  5023.3  556.34  5023.5  556.84  5027.6  559.48
  5051.9  559.72  5064.6  557.52  5075.4  559.28  5092.0  560.39  5105.8  560.78
  5140.8  563.67  5187.3  564.62  5206.7  565.20  5211.7  564.30  5226.1  564.45
  5481.6  568.94  5588.5  570.01  5623.6  571.72  5695.4  571.24  6039.6  571.40
#Mann=7,-1,0
  4139.6    0.07       0  4882.4   0.035       0  4940.9     0.1       0
  5019.5    0.05       0  5023.5     0.1       0  5092.0    0.12       0
  5187.3   0.045       0
Bank Sta=5019.5,5023.5
Exp/Cntr=0.3,0.1

Type RM Length L Ch R = 1,1092,355,355,355
BEGIN DESCRIPTION:
A19076
END DESCRIPTION:
XS GIS Cut Line= 4
      2302645.22     13788370.25      2301824.23     13788686.49
      2301331.66     13788966.22      2301137.32     13789500.64
#Sta/Elev= 30
  4131.0  569.33  4605.7  567.50  4709.5  566.08  4802.8  563.61  4870.6  561.90
  4892.1  561.99  4933.3  558.38  4968.7  557.29  4975.6  556.11  4977.8  555.73
  4988.0  551.83  4991.3  551.50  4991.6  551.00  4995.1  551.00  4995.3  551.50
  4999.2  553.62  5007.7  557.05  5054.3  557.57  5146.4  559.76  5162.4  560.41
  5184.0  559.95  5302.3  561.18  5612.3  562.74  5895.2  566.32  5938.1  568.10
  5980.3  568.87  6001.6  570.39  6019.3  570.91  6055.2  570.15  6145.9  570.81
#Mann=6,-1,0
  4131.0    0.07       0  4802.8   0.035       0  4975.6     0.1       0
  4991.3    0.05       0  4995.3     0.1       0  5146.4   0.045       0
Bank Sta=4991.3,4995.3
Exp/Cntr=0.3,0.1

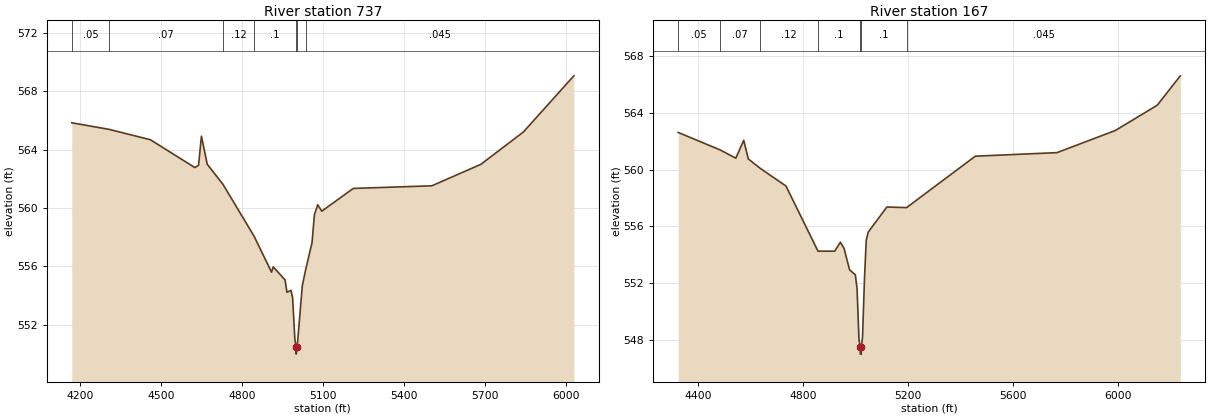
Type RM Length L Ch R = 1,737,570,570,570
BEGIN DESCRIPTION:
A19075
END DESCRIPTION:
XS GIS Cut Line= 4
      2302383.66     13788157.44      2301726.93     13788406.76
      2301386.39     13788637.84      2301149.23     13789343.23
#Sta/Elev= 30
  4169.4  565.84  4307.3  565.39  4460.2  564.68  4625.0  562.77  4638.6  562.93
  4649.3  564.92  4670.7  563.00  4729.1  561.62  4844.0  558.07  4908.8  555.60
  4914.9  555.96  4958.8  555.07  4965.8  554.22  4980.7  554.35  4986.7  553.86
  4995.0  551.02  4999.7  550.48  4999.9  549.98  5003.7  550.48  5022.7  554.68
  5035.5  555.81  5058.6  557.62  5067.5  559.54  5079.6  560.22  5094.6  559.78
  5211.3  561.34  5502.0  561.52  5683.3  562.99  5840.9  565.21  6027.6  569.06
#Mann=7,-1,0
  4169.4    0.05       0  4307.3    0.07       0  4729.1    0.12       0
  4844.0     0.1       0  4999.7    0.05       0  5003.7     0.1       0
  5035.5   0.045       0
Bank Sta=4999.7,5003.7
Exp/Cntr=0.3,0.1

Type RM Length L Ch R = 1,167,0,0,0
BEGIN DESCRIPTION:
A19074
END DESCRIPTION:
XS GIS Cut Line= 4
      2302183.04     13787920.27      2301635.71     13787981.08
      2301465.44     13788175.68      2301143.72     13789231.89
#Sta/Elev= 30
  4324.2  562.61  4484.1  561.38  4543.6  560.80  4573.8  562.06  4591.2  560.75
  4636.9  560.08  4734.8  558.84  4856.9  554.25  4920.3  554.25  4942.1  554.88
  4956.3  554.44  4977.2  552.94  4999.1  552.59  5005.7  551.62  5013.0  548.04
  5017.9  547.50  5018.2  547.00  5021.7  547.00  5021.9  547.50  5026.6  548.20
  5034.2  552.44  5040.8  555.03  5048.4  555.60  5119.3  557.36  5194.5  557.32
  5456.3  560.94  5767.6  561.19  5990.0  562.75  6149.7  564.53  6237.6  566.60
#Mann=7,-1,0
  4324.2    0.05       0  4484.1    0.07       0  4636.9    0.12       0
  4856.9     0.1       0  5017.9    0.05       0  5021.9     0.1       0
  5194.5   0.045       0
Bank Sta=5017.9,5021.9
Exp/Cntr=0.3,0.1

Chan Stop Cuts=-1