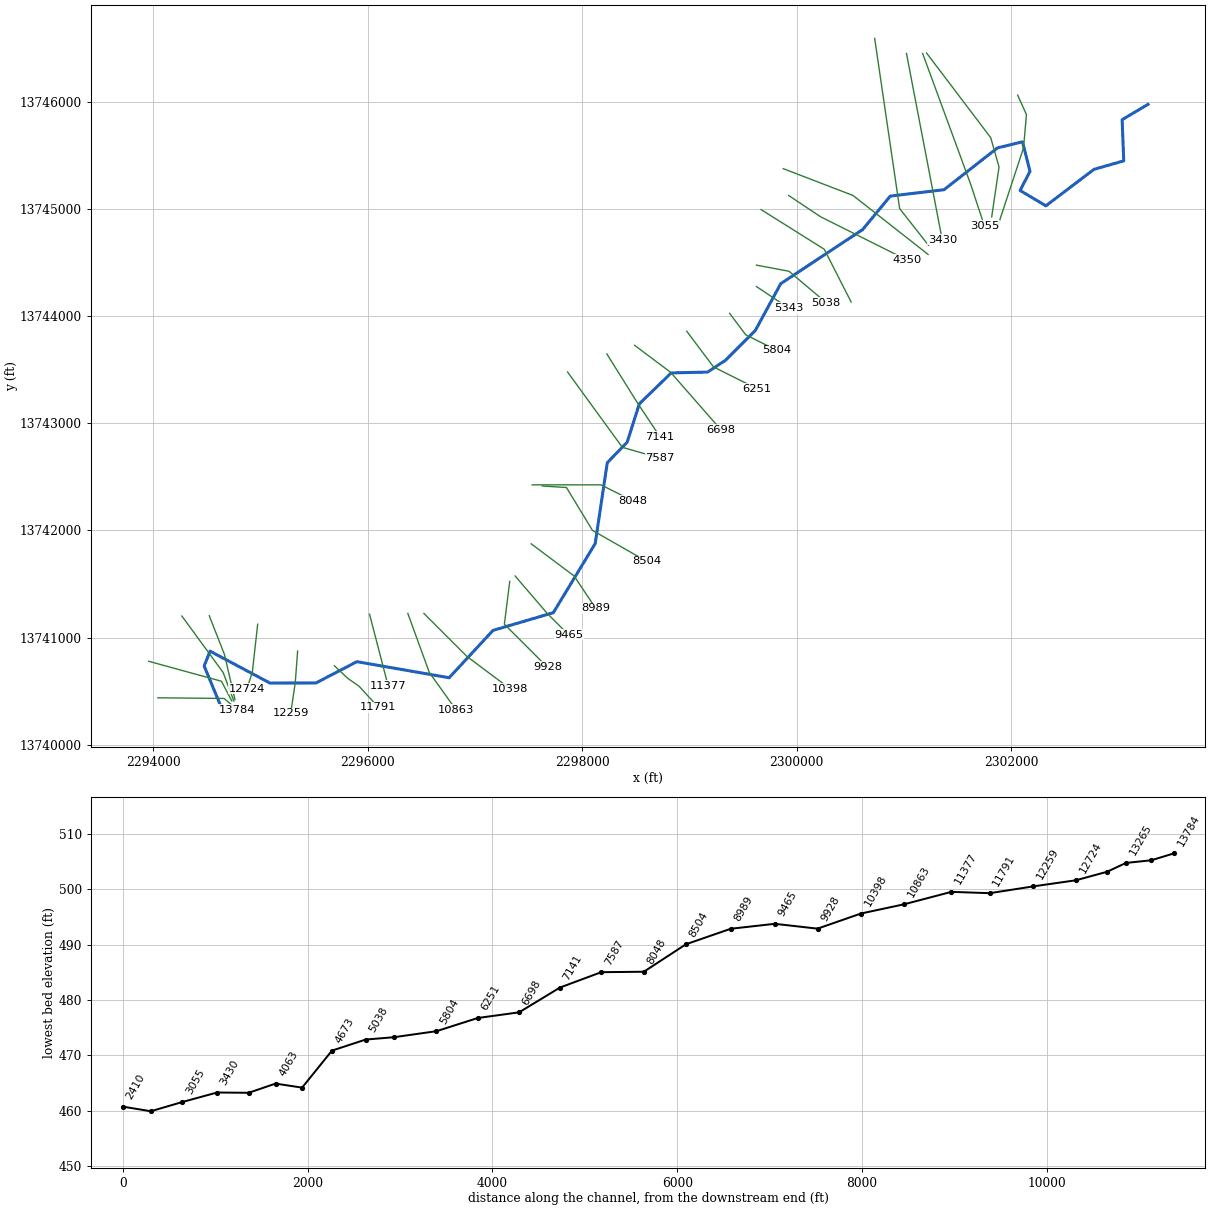
--- GUADALUPE TRIBUTARY 13.prj (project) ---

Proj Title=GUADALUPE TRIBUTARY 13 Base Level Engineering
Current Plan=p01
Default Exp/Contr=0.3,0.1
English Units
Geom File=g01
Flow File=f01
Plan File=p01
BEGIN DESCRIPTION:
GUADALUPE TRIBUTARY 13
END DESCRIPTION:

--- GUADALUPE TRIBUTARY 13.p01 (plan) ---

Plan Title=Multiple Run
Short Identifier=Multiple
Geom File=g01
Flow File=f01
Subcritical Flow
K Sum by GR= 0
Std Step Tol= 0.01
Critical Tol= 0.01
Num of Std Step Trials= 20
Max Error Tol= 0.3
Flow Tol Ratio= 0.001
Split Flow NTrial= 30
Split Flow Tol= 0.02
Split Flow Ratio= 0.02
Log Output Level= 0
Friction Slope Method= 1
Unsteady Friction Slope Method= 2
Unsteady Bridges Friction Slope Method= 1
Parabolic Critical Depth
Global Vel Dist=  1 , 1 , 1
Global Log Level= 0
CheckData=True
Encroach Param= -1, 0, 0, 0
BEGIN DESCRIPTION:
Multiple Run
END DESCRIPTION:

--- GUADALUPE TRIBUTARY 13.f01 (steady flow) ---

Flow Title=Multiple
Number of Profiles=7
Profile Names=10-year,25-year,50-year,1pct_min,100-year,1pct_plu,500-year
River Rch & RM= GUADALUPE TRIBUT,Reach-1,13784
     523     834    1112     718    1432    2858    2355
River Rch & RM= GUADALUPE TRIBUT,Reach-1,11377
     895    1463    1980    1296    2585    5158    4368
River Rch & RM= GUADALUPE TRIBUT,Reach-1,3055
    1037    1709    2326    1530    3052    6089    5209
Boundary for River Rch & Prof#=GUADALUPE TRIBUT,Reach-1,1
Up Type=0
Dn Type=3
Dn Slope=0.005
Boundary for River Rch & Prof#=GUADALUPE TRIBUT,Reach-1,2
Up Type=0
Dn Type=3
Dn Slope=0.005
Boundary for River Rch & Prof#=GUADALUPE TRIBUT,Reach-1,3
Up Type=0
Dn Type=3
Dn Slope=0.005
Boundary for River Rch & Prof#=GUADALUPE TRIBUT,Reach-1,4
Up Type=0
Dn Type=3
Dn Slope=0.005
Boundary for River Rch & Prof#=GUADALUPE TRIBUT,Reach-1,5
Up Type=0
Dn Type=3
Dn Slope=0.005
Boundary for River Rch & Prof#=GUADALUPE TRIBUT,Reach-1,6
Up Type=0
Dn Type=3
Dn Slope=0.005
Boundary for River Rch & Prof#=GUADALUPE TRIBUT,Reach-1,7
Up Type=0
Dn Type=3
Dn Slope=0.005

--- GUADALUPE TRIBUTARY 13.g01 (geometry) ---

Geom Title=Existing Conditions

River Reach=GUADALUPE TRIBUT,Reach-1
Reach XY= 30
      2294625.00     13740375.00      2294476.08     13740735.55
      2294530.84     13740873.50      2295090.27     13740575.37
      2295519.14     13740577.06      2295899.88     13740775.29
      2296759.84     13740625.36      2297168.94     13741066.86
      2297731.52     13741232.68      2298121.45     13741876.47
      2298234.15     13742631.73      2298419.48     13742822.57
      2298533.13     13743181.07      2298830.61     13743469.41
      2299169.14     13743477.05      2299338.21     13743588.63
      2299614.35     13743865.01      2299851.29     13744301.82
      2300615.09     13744806.84      2300872.69     13745119.19
      2301373.53     13745178.55      2301872.71     13745569.16
      2302105.14     13745625.11      2302175.40     13745350.00
      2302082.76     13745171.58      2302323.28     13745028.34
      2302772.70     13745369.17      2303049.03     13745447.65
      2303034.12     13745831.76      2303275.00     13745975.00

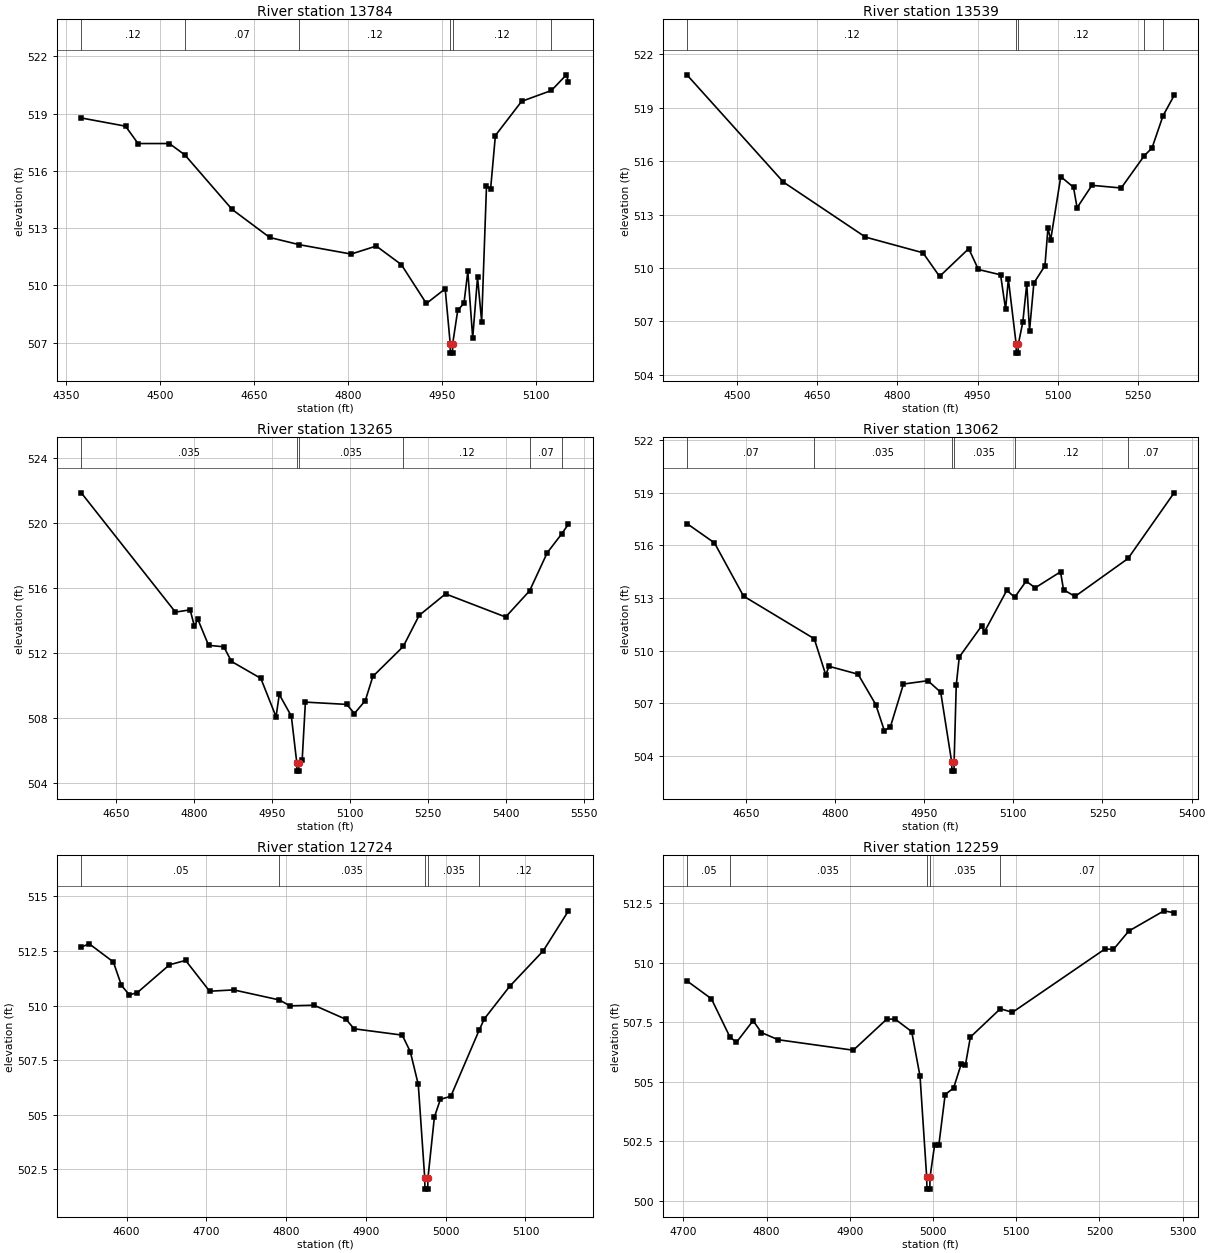
Type RM Length L Ch R = 1,13784,245,245,245
BEGIN DESCRIPTION:
GUADALUPE TRIBUTARY 13 30.0
END DESCRIPTION:
XS GIS Cut Line= 3
      2294044.45     13740438.36      2294662.25     13740432.06
      2294783.99     13740329.05
#Sta/Elev= 30
  4374.7  518.77  4445.3  518.34  4465.3  517.43  4515.3  517.43  4540.1  516.83
  4615.3  513.98  4675.3  512.51  4722.7  512.13  4805.3  511.64  4845.3  512.06
  4885.3  511.09  4925.3  509.05  4955.3  509.82  4963.3  506.95  4963.5  506.45
  4967.0  506.45  4967.3  506.95  4975.3  508.69  4985.3  509.07  4991.4  510.73
  4999.2  507.25  5006.9  510.42  5013.5  508.10  5021.2  515.19  5027.8  515.07
  5035.4  517.85  5077.2  519.64  5124.8  520.21  5148.7  521.03  5152.0  520.65
#Mann=6,-1,0
  4374.7    0.12       0  4540.1    0.07       0  4722.7    0.12       0
  4963.3    0.05       0  4967.3    0.12       0  5124.8    0.07       0
Bank Sta=4963.3,4967.3
Exp/Cntr=0.3,0.1

Type RM Length L Ch R = 1,13539,274,274,274
BEGIN DESCRIPTION:
A19150
END DESCRIPTION:
XS GIS Cut Line= 3
      2293959.44     13740778.75      2294637.04     13740592.80
      2294733.90     13740408.45
#Sta/Elev= 30
  4406.5  520.85  4587.0  514.82  4740.4  511.73  4847.8  510.85  4878.9  509.52
  4933.4  511.08  4951.5  509.91  4993.0  509.61  5002.3  507.67  5007.5  509.37
  5022.1  505.71  5022.3  505.21  5025.8  505.21  5026.1  505.71  5034.5  506.95
  5041.9  509.10  5047.1  506.48  5055.2  509.15  5075.9  510.12  5081.5  512.23
  5086.7  511.59  5105.5  515.13  5129.3  514.53  5136.0  513.38  5163.7  514.64
  5218.5  514.49  5261.3  516.29  5276.1  516.74  5296.7  518.55  5317.4  519.69
#Mann=5,-1,0
  4406.5    0.12       0  5022.1    0.05       0  5026.1    0.12       0
  5261.3    0.07       0  5296.7    0.12       0
Bank Sta=5022.1,5026.1
Exp/Cntr=0.3,0.1

Type RM Length L Ch R = 1,13265,203,203,203
BEGIN DESCRIPTION:
A19149
END DESCRIPTION:
XS GIS Cut Line= 3
      2294268.26     13741201.13      2294652.80     13740674.75
      2294753.08     13740408.38
#Sta/Elev= 30
  4583.0  521.83  4764.0  514.50  4792.2  514.64  4800.6  513.62  4806.8  514.08
  4827.7  512.46  4857.0  512.37  4871.7  511.47  4928.1  510.43  4957.4  508.07
  4963.6  509.44  4986.8  508.11  4997.3  505.23  4997.5  504.73  5001.0  504.73
  5001.3  505.23  5007.6  505.40  5013.8  508.97  5093.3  508.83  5108.0  508.27
  5128.9  509.06  5143.5  510.55  5201.9  512.39  5232.5  514.30  5283.2  515.62
  5398.7  514.20  5444.8  515.81  5478.7  518.15  5506.3  519.30  5519.5  519.91
#Mann=6,-1,0
  4583.0   0.035       0  4997.3   0.035       0  5001.3   0.035       0
  5201.9    0.12       0  5444.8    0.07       0  5506.3    0.12       0
Bank Sta=4997.3,5001.3
Exp/Cntr=0.3,0.1

Type RM Length L Ch R = 1,13062,338,338,338
BEGIN DESCRIPTION:
GUADALUPE TRIBUTARY 13 29.0
END DESCRIPTION:
XS GIS Cut Line= 3
      2294523.58     13741204.24      2294665.41     13740841.79
      2294763.10     13740422.63
#Sta/Elev= 30
  4550.9  517.24  4597.2  516.14  4646.1  513.11  4765.1  510.68  4784.5  508.62
  4789.9  509.11  4838.8  508.66  4868.6  506.93  4883.0  505.45  4893.1  505.65
  4915.2  508.10  4956.3  508.29  4977.9  507.63  4996.4  503.64  4996.7  503.14
  5000.2  503.14  5000.4  503.64  5004.0  508.04  5009.1  509.64  5046.5  511.40
  5051.7  511.09  5089.1  513.44  5102.3  513.04  5121.6  513.96  5136.8  513.58
  5179.4  514.49  5184.5  513.47  5203.8  513.09  5293.0  515.25  5370.5  518.99
#Mann=6,-1,0
  4550.9    0.07       0  4765.1   0.035       0  4996.4   0.035       0
  5000.4   0.035       0  5102.3    0.12       0  5293.0    0.07       0
Bank Sta=4996.4,5000.4
Exp/Cntr=0.3,0.1

Type RM Length L Ch R = 1,12724,465,465,465
BEGIN DESCRIPTION:
GUADALUPE TRIBUTARY 13 28.0
END DESCRIPTION:
XS GIS Cut Line= 3
      2294974.99     13741124.95      2294925.00     13740675.00
      2294875.01     13740525.03
#Sta/Elev= 30
  4543.1  512.68  4553.1  512.83  4583.3  512.00  4593.4  510.93  4603.4  510.49
  4613.5  510.60  4653.7  511.87  4673.9  512.07  4704.0  510.66  4734.2  510.72
  4791.5  510.26  4804.7  509.99  4834.8  510.02  4875.1  509.37  4885.1  508.94
  4945.5  508.65  4955.6  507.89  4965.6  506.39  4973.7  502.10  4973.9  501.60
  4977.4  501.60  4977.7  502.10  4985.8  504.90  4993.3  505.71  5006.4  505.85
  5042.2  508.90  5048.5  509.40  5080.1  510.88  5122.3  512.51  5153.9  514.34
#Mann=5,-1,0
  4543.1    0.05       0  4791.5   0.035       0  4973.7   0.035       0
  4977.7   0.035       0  5042.2    0.12       0
Bank Sta=4973.7,4977.7
Exp/Cntr=0.3,0.1

Type RM Length L Ch R = 1,12259,468,468,468
BEGIN DESCRIPTION:
GUADALUPE TRIBUTARY 13 27.0
END DESCRIPTION:
XS GIS Cut Line= 3
      2295347.31     13740874.31      2295325.00     13740575.00
      2295282.32     13740292.95
#Sta/Elev= 30
  4704.3  509.23  4733.7  508.48  4755.9  506.88  4763.8  506.65  4783.8  507.56
  4793.9  507.06  4813.9  506.76  4904.2  506.32  4944.3  507.62  4954.3  507.63
  4974.4  507.10  4984.4  505.23  4992.4  500.99  4992.7  500.49  4996.2  500.49
  4996.4  500.99  5001.9  502.34  5007.0  502.34  5014.6  504.46  5024.7  504.73
  5033.8  505.73  5038.9  505.69  5044.9  506.87  5080.9  508.06  5095.5  507.91
  5206.7  510.57  5216.8  510.55  5235.2  511.32  5277.5  512.17  5289.7  512.09
#Mann=5,-1,0
  4704.3    0.05       0  4755.9   0.035       0  4992.4   0.035       0
  4996.4   0.035       0  5080.9    0.07       0
Bank Sta=4992.4,4996.4
Exp/Cntr=0.3,0.1

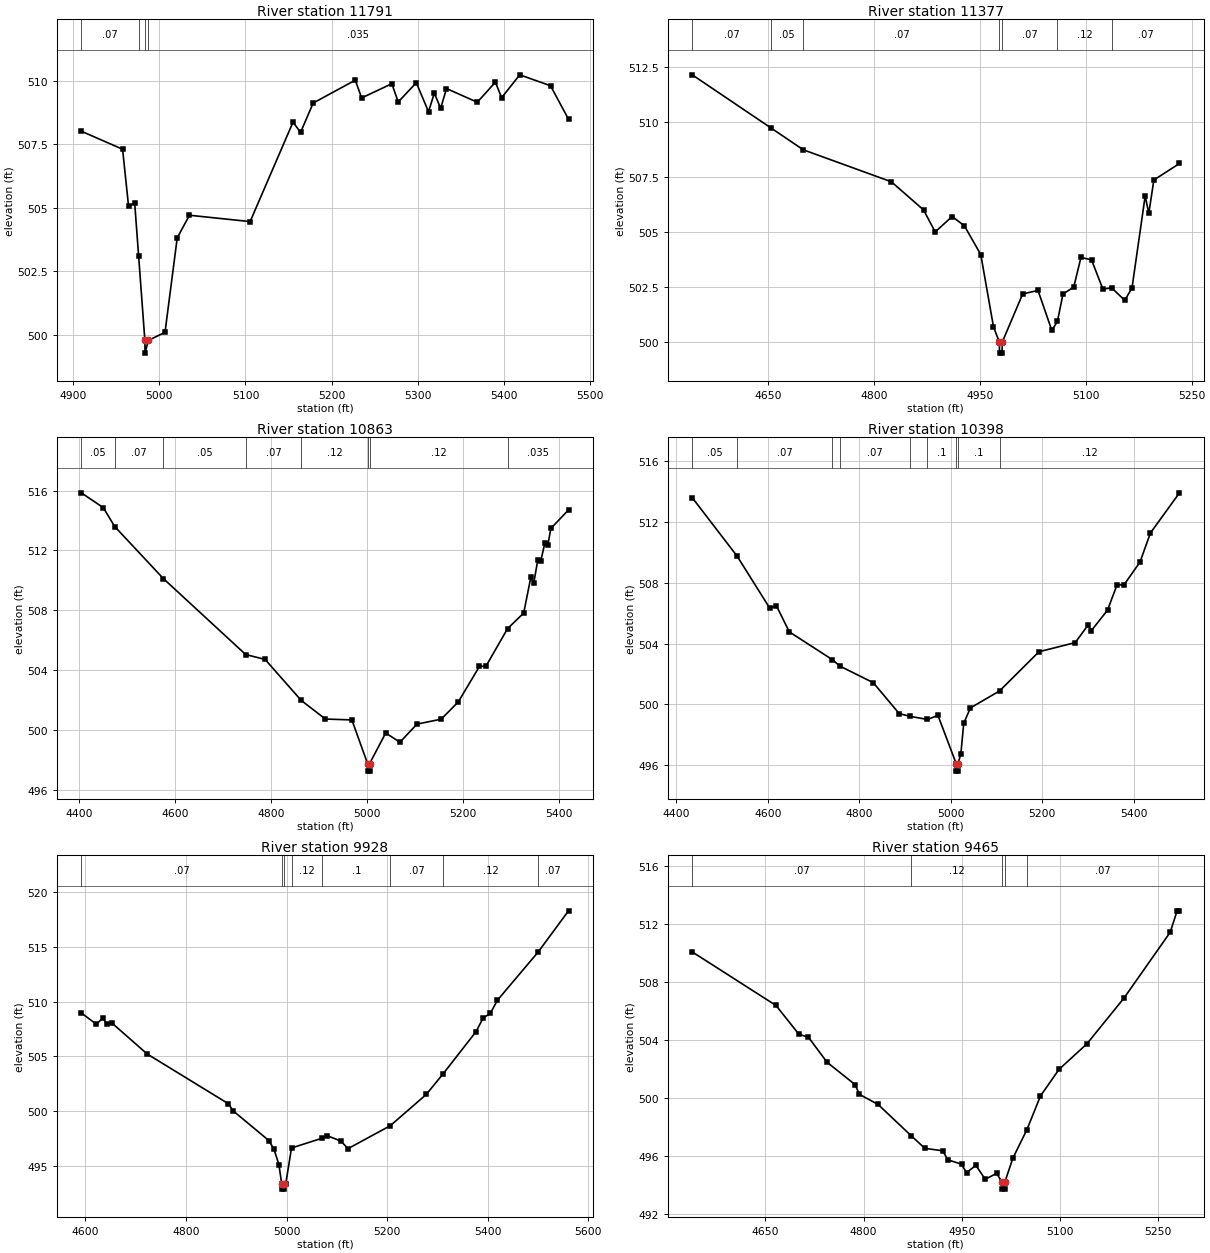
Type RM Length L Ch R = 1,11791,414,414,414
BEGIN DESCRIPTION:
GUADALUPE TRIBUTARY 13 26.0
END DESCRIPTION:
XS GIS Cut Line= 4
      2295689.79     13740737.35      2295812.77     13740621.38
      2295920.09     13740546.10      2296100.06     13740350.13
#Sta/Elev= 30
  4909.2  508.01  4957.2  507.30  4964.1  505.07  4971.3  505.17  4975.8  503.11
  4983.1  499.77  4983.3  499.27  4987.1  499.77  5006.5  500.09  5020.7  503.81
  5034.9  504.70  5105.4  504.45  5155.3  508.37  5164.0  507.96  5178.7  509.12
  5227.6  510.02  5235.0  509.32  5270.1  509.88  5277.5  509.16  5298.5  509.92
  5312.7  508.78  5319.5  509.51  5326.8  508.91  5333.6  509.69  5369.4  509.15
  5390.4  509.94  5397.7  509.33  5418.7  510.23  5454.5  509.80  5475.4  508.48
#Mann=4,-1,0
  4909.2    0.07       0  4975.8   0.035       0  4983.1   0.035       0
  4987.1   0.035       0
Bank Sta=4983.1,4987.1
Exp/Cntr=0.3,0.1

Type RM Length L Ch R = 1,11377,514,514,514
BEGIN DESCRIPTION:
GUADALUPE TRIBUTARY 13 25.0
END DESCRIPTION:
XS GIS Cut Line= 2
      2296017.84     13741218.21      2296191.43     13740549.89
#Sta/Elev= 30
  4542.2  512.16  4654.0  509.74  4699.7  508.75  4824.3  507.30  4870.0  506.02
  4886.5  505.02  4910.5  505.72  4927.8  505.30  4951.1  503.99  4969.1  500.71
  4977.4  500.01  4977.7  499.51  4981.3  499.51  4981.5  500.01  5010.5  502.20
  5032.2  502.36  5051.8  500.54  5059.7  500.95  5067.6  502.20  5082.8  502.51
  5093.1  503.86  5108.1  503.75  5124.1  502.42  5136.5  502.48  5155.1  501.91
  5165.4  502.47  5184.1  506.66  5189.2  505.86  5196.4  507.38  5232.7  508.13
#Mann=7,-1,0
  4542.2    0.07       0  4654.0    0.05       0  4699.7    0.07       0
  4977.4    0.05       0  4981.5    0.07       0  5059.7    0.12       0
  5136.5    0.07       0
Bank Sta=4977.4,4981.5
Exp/Cntr=0.3,0.1

Type RM Length L Ch R = 1,10863,465,465,465
BEGIN DESCRIPTION:
GUADALUPE TRIBUTARY 13 24.0
END DESCRIPTION:
XS GIS Cut Line= 3
      2296375.00     13741224.99      2296575.00     13740675.00
      2296824.97     13740325.04
#Sta/Elev= 30
  4405.2  515.85  4451.1  514.86  4474.8  513.60  4576.3  510.12  4747.7  505.05
  4788.3  504.72  4863.6  501.98  4913.9  500.74  4969.1  500.68  5001.8  497.76
  5002.1  497.26  5005.8  497.26  5006.0  497.76  5039.6  499.81  5069.1  499.19
  5104.7  500.40  5155.1  500.73  5190.7  501.88  5235.0  504.26  5248.5  504.27
  5293.5  506.78  5327.1  507.82  5341.9  510.20  5348.0  509.81  5356.6  511.39
  5362.8  511.31  5371.4  512.53  5377.5  512.38  5383.7  513.47  5420.5  514.71
#Mann=8,-1,0
  4405.2    0.05       0  4474.8    0.07       0  4576.3    0.05       0
  4747.7    0.07       0  4863.6    0.12       0  5001.8    0.05       0
  5006.0    0.12       0  5293.5   0.035       0
Bank Sta=5001.8,5006
Exp/Cntr=0.3,0.1

Type RM Length L Ch R = 1,10398,470,470,470
BEGIN DESCRIPTION:
GUADALUPE TRIBUTARY 13 23.0
END DESCRIPTION:
XS GIS Cut Line= 3
      2296524.98     13741225.02      2296925.00     13740825.00
      2297324.99     13740525.01
#Sta/Elev= 30
  4434.5  513.60  4532.7  509.75  4604.2  506.32  4618.4  506.50  4646.7  504.77
  4740.8  502.94  4757.7  502.51  4830.5  501.42  4887.1  499.39  4910.2  499.21
  4949.0  499.00  4971.9  499.27  5011.7  496.10  5011.9  495.60  5015.6  495.60
  5015.9  496.10  5022.1  496.76  5028.3  498.75  5042.9  499.76  5106.7  500.88
  5192.9  503.46  5272.1  504.06  5300.2  505.21  5307.5  504.85  5342.9  506.20
  5363.8  507.88  5378.3  507.84  5413.8  509.36  5436.7  511.28  5500.2  513.92
#Mann=9,-1,0
  4434.5    0.05       0  4532.7    0.07       0  4740.8    0.05       0
  4757.7    0.07       0  4910.2    0.12       0  4949.0     0.1       0
  5011.7    0.05       0  5015.9     0.1       0  5106.7    0.12       0
Bank Sta=5011.7,5015.9
Exp/Cntr=0.3,0.1

Type RM Length L Ch R = 1,9928,463,463,463
BEGIN DESCRIPTION:
GUADALUPE TRIBUTARY 13 22.0
END DESCRIPTION:
XS GIS Cut Line= 3
      2297325.00     13741524.98      2297275.00     13741125.00
      2297675.02     13740724.98
#Sta/Elev= 30
  4591.9  508.97  4622.1  507.93  4634.7  508.52  4642.3  507.96  4652.3  508.07
  4722.9  505.22  4884.1  500.68  4894.2  500.01  4964.8  497.31  4974.8  496.54
  4984.9  495.11  4990.3  493.37  4990.6  492.87  4994.4  492.87  4994.6  493.37
  4998.5  493.37  5009.9  496.63  5071.2  497.53  5079.8  497.77  5108.1  497.26
  5122.3  496.57  5206.4  498.67  5277.8  501.52  5311.6  503.42  5376.8  507.26
  5391.0  508.51  5405.1  508.92  5419.3  510.13  5500.2  514.53  5560.7  518.30
#Mann=8,-1,0
  4591.9    0.07       0  4990.3    0.05       0  4994.6    0.07       0
  5009.9    0.12       0  5071.2     0.1       0  5206.4    0.07       0
  5311.6    0.12       0  5500.2    0.07       0
Bank Sta=4990.3,4994.6
Exp/Cntr=0.3,0.1

Type RM Length L Ch R = 1,9465,476,476,476
BEGIN DESCRIPTION:
GUADALUPE TRIBUTARY 13 21.0
END DESCRIPTION:
XS GIS Cut Line= 3
      2297374.97     13741575.04      2297675.00     13741225.00
      2297875.02     13741024.98
#Sta/Elev= 30
  4538.5  510.08  4666.4  506.39  4701.5  504.40  4715.8  504.21  4744.3  502.48
  4787.1  500.94  4793.7  500.27  4822.3  499.57  4872.5  497.43  4893.6  496.55
  4921.0  496.38  4928.7  495.76  4949.6  495.46  4957.3  494.87  4971.5  495.38
  4985.8  494.42  5003.1  494.82  5011.5  494.24  5011.8  493.74  5015.6  493.74
  5015.9  494.24  5027.8  495.85  5049.5  497.84  5070.2  500.16  5098.5  501.99
  5140.9  503.74  5197.5  506.89  5268.2  511.43  5278.8  512.91  5282.4  512.91
#Mann=5,-1,0
  4538.5    0.07       0  4872.5    0.12       0  5011.5    0.05       0
  5015.9    0.12       0  5049.5    0.07       0
Bank Sta=5011.5,5015.9
Exp/Cntr=0.3,0.1

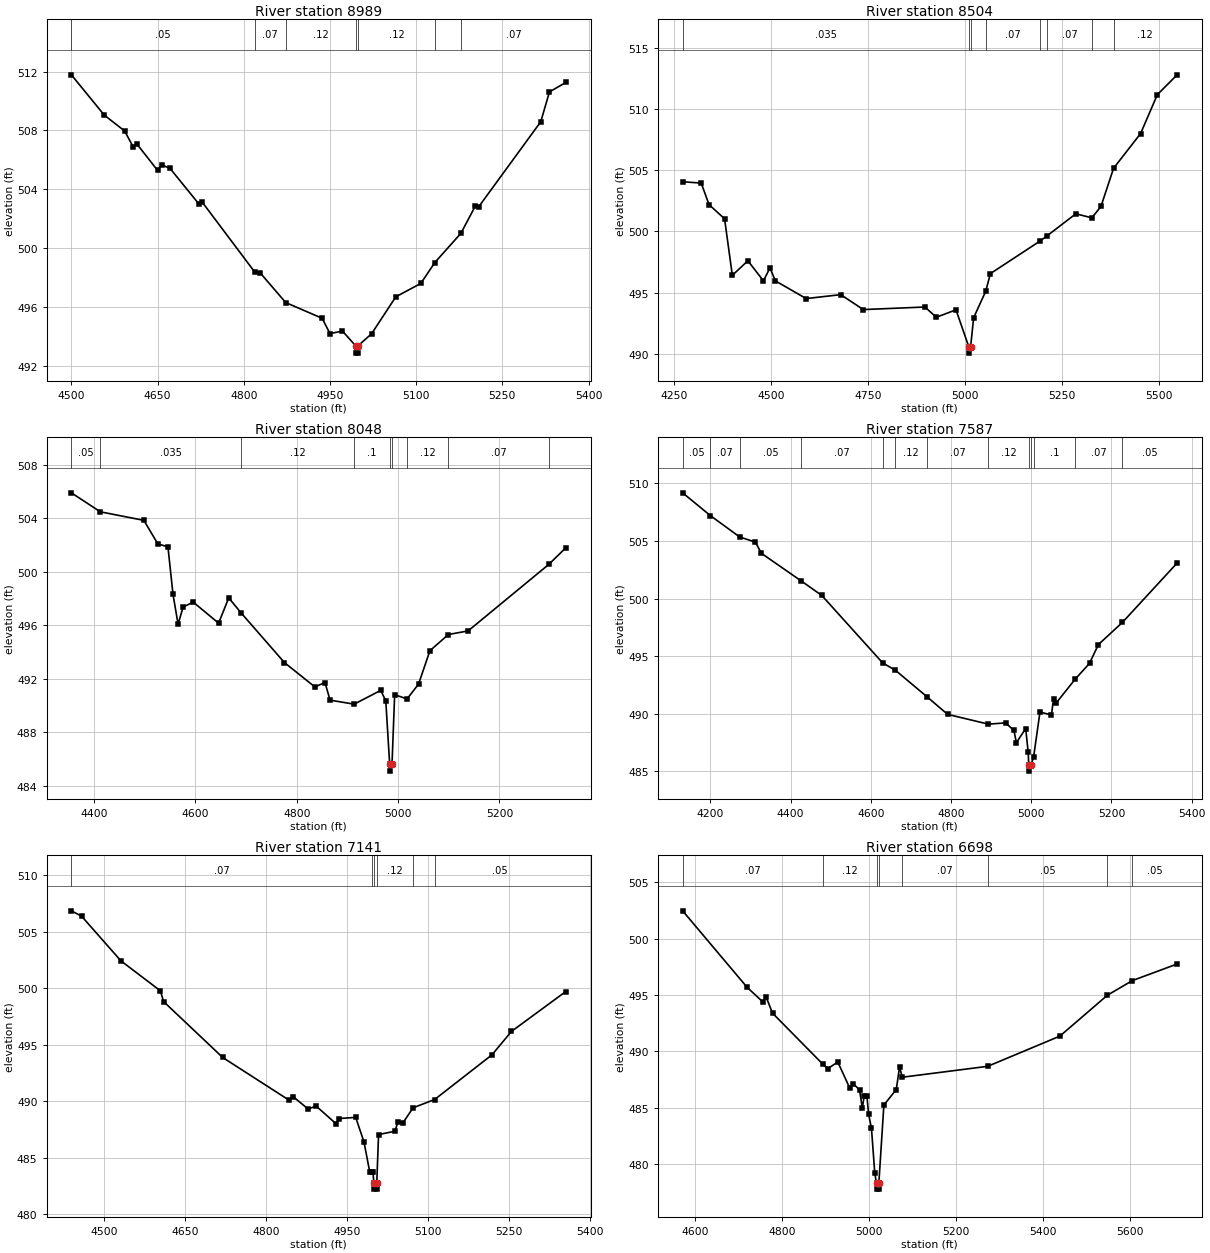
Type RM Length L Ch R = 1,8989,485,485,485
BEGIN DESCRIPTION:
GUADALUPE TRIBUTARY 13 20.0
END DESCRIPTION:
XS GIS Cut Line= 3
      2297525.03     13741874.97      2297925.00     13741575.00
      2298124.99     13741275.01
#Sta/Elev= 30
  4500.0  511.78  4557.2  509.04  4592.7  507.96  4607.2  506.90  4613.5  507.10
  4650.0  505.28  4657.2  505.66  4671.8  505.41  4721.8  503.00  4728.1  503.10
  4818.8  498.38  4828.1  498.33  4873.0  496.29  4936.4  495.22  4950.0  494.18
  4971.8  494.35  4994.6  493.35  4994.9  492.85  4998.7  492.85  4999.0  493.35
  5022.5  494.17  5064.6  496.68  5108.1  497.59  5132.5  499.01  5177.9  501.00
  5202.8  502.84  5208.8  502.80  5316.9  508.59  5332.0  510.62  5360.5  511.26
#Mann=7,-1,0
  4500.0    0.05       0  4818.8    0.07       0  4873.0    0.12       0
  4994.6    0.05       0  4999.0    0.12       0  5132.5    0.12       0
  5177.9    0.07       0
Bank Sta=4994.6,4999
Exp/Cntr=0.3,0.1

Type RM Length L Ch R = 1,8504,456,456,456
BEGIN DESCRIPTION:
GUADALUPE TRIBUTARY 13 19.0
END DESCRIPTION:
XS GIS Cut Line= 4
      2297627.17     13742414.75      2297853.80     13742400.00
      2298096.19     13742000.22      2298600.00     13741712.33
#Sta/Elev= 30
  4272.1  504.06  4320.0  503.95  4340.1  502.19  4380.2  501.03  4400.2  496.41
  4440.3  497.60  4480.4  495.96  4497.3  497.02  4511.0  495.96  4590.5  494.51
  4679.7  494.83  4737.9  493.61  4896.9  493.82  4926.1  492.98  4976.9  493.59
  5010.1  490.55  5010.4  490.05  5014.6  490.55  5022.4  492.94  5053.7  495.12
  5065.6  496.55  5194.5  499.23  5211.8  499.64  5285.9  501.44  5327.2  501.11
  5350.7  502.04  5383.2  505.16  5452.9  508.00  5496.1  511.18  5547.0  512.80
#Mann=8,-1,0
  4272.1   0.035       0  5010.1   0.035       0  5014.6   0.035       0
  5053.7    0.07       0  5194.5    0.05       0  5211.8    0.07       0
  5327.2    0.05       0  5383.2    0.12       0
Bank Sta=5010.1,5014.6
Exp/Cntr=0.3,0.1

Type RM Length L Ch R = 1,8048,461,461,461
BEGIN DESCRIPTION:
GUADALUPE TRIBUTARY 13 18.0
END DESCRIPTION:
XS GIS Cut Line= 4
      2297534.42     13742425.00      2297675.00     13742425.00
      2298175.00     13742425.00      2298475.01     13742275.00
#Sta/Elev= 30
  4355.1  505.91  4412.2  504.49  4498.2  503.85  4525.7  502.09  4545.7  501.87
  4555.7  498.31  4565.7  496.08  4575.7  497.37  4595.7  497.73  4645.7  496.16
  4665.7  498.05  4690.7  496.90  4775.7  493.21  4835.7  491.39  4855.7  491.72
  4865.7  490.40  4913.3  490.10  4965.7  491.13  4975.7  490.35  4983.4  485.59
  4983.7  485.09  4988.0  485.59  4993.2  490.81  5017.7  490.49  5040.4  491.60
  5062.8  494.10  5099.3  495.31  5138.2  495.58  5297.6  500.56  5331.1  501.80
#Mann=9,-1,0
  4355.1    0.05       0  4412.2   0.035       0  4690.7    0.12       0
  4913.3     0.1       0  4983.4    0.05       0  4988.0     0.1       0
  5017.7    0.12       0  5099.3    0.07       0  5297.6    0.05       0
Bank Sta=4983.4,4988
Exp/Cntr=0.3,0.1

Type RM Length L Ch R = 1,7587,446,446,446
BEGIN DESCRIPTION:
GUADALUPE TRIBUTARY 13 17.0
END DESCRIPTION:
XS GIS Cut Line= 4
      2297863.94     13743477.70      2297975.00     13743325.00
      2298375.00     13742775.00      2298725.01     13742675.00
#Sta/Elev= 30
  4130.8  509.18  4200.0  507.20  4273.3  505.34  4312.3  504.90  4327.0  503.93
  4425.9  501.54  4477.7  500.27  4629.5  494.41  4661.3  493.77  4739.7  491.48
  4791.4  489.94  4893.3  489.09  4935.9  489.20  4956.8  488.55  4963.0  487.48
  4986.2  488.71  4992.3  486.69  4994.0  485.51  4994.4  485.01  4999.2  485.51
  5006.0  486.26  5021.8  490.14  5050.4  489.89  5055.6  491.28  5062.1  490.92
  5109.2  492.98  5145.3  494.37  5167.4  496.00  5227.2  497.92  5363.7  503.08
#Mann=13,-1,0
  4130.8    0.05       0  4200.0    0.07       0  4273.3    0.05       0
  4425.9    0.07       0  4629.5    0.05       0  4661.3    0.12       0
  4739.7    0.07       0  4893.3    0.12       0  4994.0    0.05       0
  4999.2    0.12       0  5006.0     0.1       0  5109.2    0.07       0
  5227.2    0.05       0
Bank Sta=4994,4999.2
Exp/Cntr=0.3,0.1

Type RM Length L Ch R = 1,7141,443,443,443
BEGIN DESCRIPTION:
GUADALUPE TRIBUTARY 13 16.0
END DESCRIPTION:
XS GIS Cut Line= 4
      2298230.37     13743646.40      2298275.00     13743575.00
      2298525.00     13743175.00      2298725.02     13742874.96
#Sta/Elev= 30
  4438.7  506.87  4457.5  506.40  4530.6  502.44  4603.7  499.79  4609.6  498.84
  4719.2  493.89  4841.3  490.14  4850.1  490.41  4877.3  489.34  4892.6  489.58
  4929.2  488.03  4935.6  488.49  4965.7  488.59  4981.0  486.43  4991.7  483.77
  4996.0  483.77  4997.6  483.77  4999.5  482.74  4999.9  482.24  5004.3  482.24
  5004.7  482.74  5008.1  487.07  5038.2  487.36  5044.2  488.18  5053.2  488.10
  5072.1  489.44  5112.0  490.17  5218.4  494.13  5254.5  496.20  5355.2  499.73
#Mann=6,-1,0
  4438.7    0.07       0  4996.0    0.12       0  4999.5    0.05       0
  5004.7    0.12       0  5072.1    0.07       0  5112.0    0.05       0
Bank Sta=4999.5,5004.7
Exp/Cntr=0.3,0.1

Type RM Length L Ch R = 1,6698,447,447,447
BEGIN DESCRIPTION:
GUADALUPE TRIBUTARY 13 15.0
END DESCRIPTION:
XS GIS Cut Line= 5
      2298489.02     13743726.98      2298625.00     13743625.00
      2298825.00     13743475.00      2299175.00     13743075.00
      2299296.31     13742936.36
#Sta/Elev= 30
  4572.0  502.46  4720.1  495.67  4755.5  494.40  4763.8  494.81  4778.4  493.38
  4894.5  488.83  4905.5  488.46  4928.4  489.04  4955.5  486.76  4963.8  487.12
  4978.4  486.56  4984.7  484.92  4988.8  486.00  4995.3  486.00  4999.1  484.42
  5005.7  483.16  5013.3  479.17  5017.3  478.26  5017.7  477.76  5022.2  477.76
  5022.6  478.26  5034.2  485.22  5062.7  486.60  5070.3  488.62  5076.3  487.69
  5272.7  488.66  5438.5  491.34  5547.6  494.97  5605.1  496.27  5707.7  497.74
#Mann=8,-1,0
  4572.0    0.07       0  4894.5    0.12       0  5017.3    0.05       0
  5022.6    0.12       0  5076.3    0.07       0  5272.7    0.05       0
  5547.6    0.07       0  5605.1    0.05       0
Bank Sta=5017.3,5022.6
Exp/Cntr=0.3,0.1

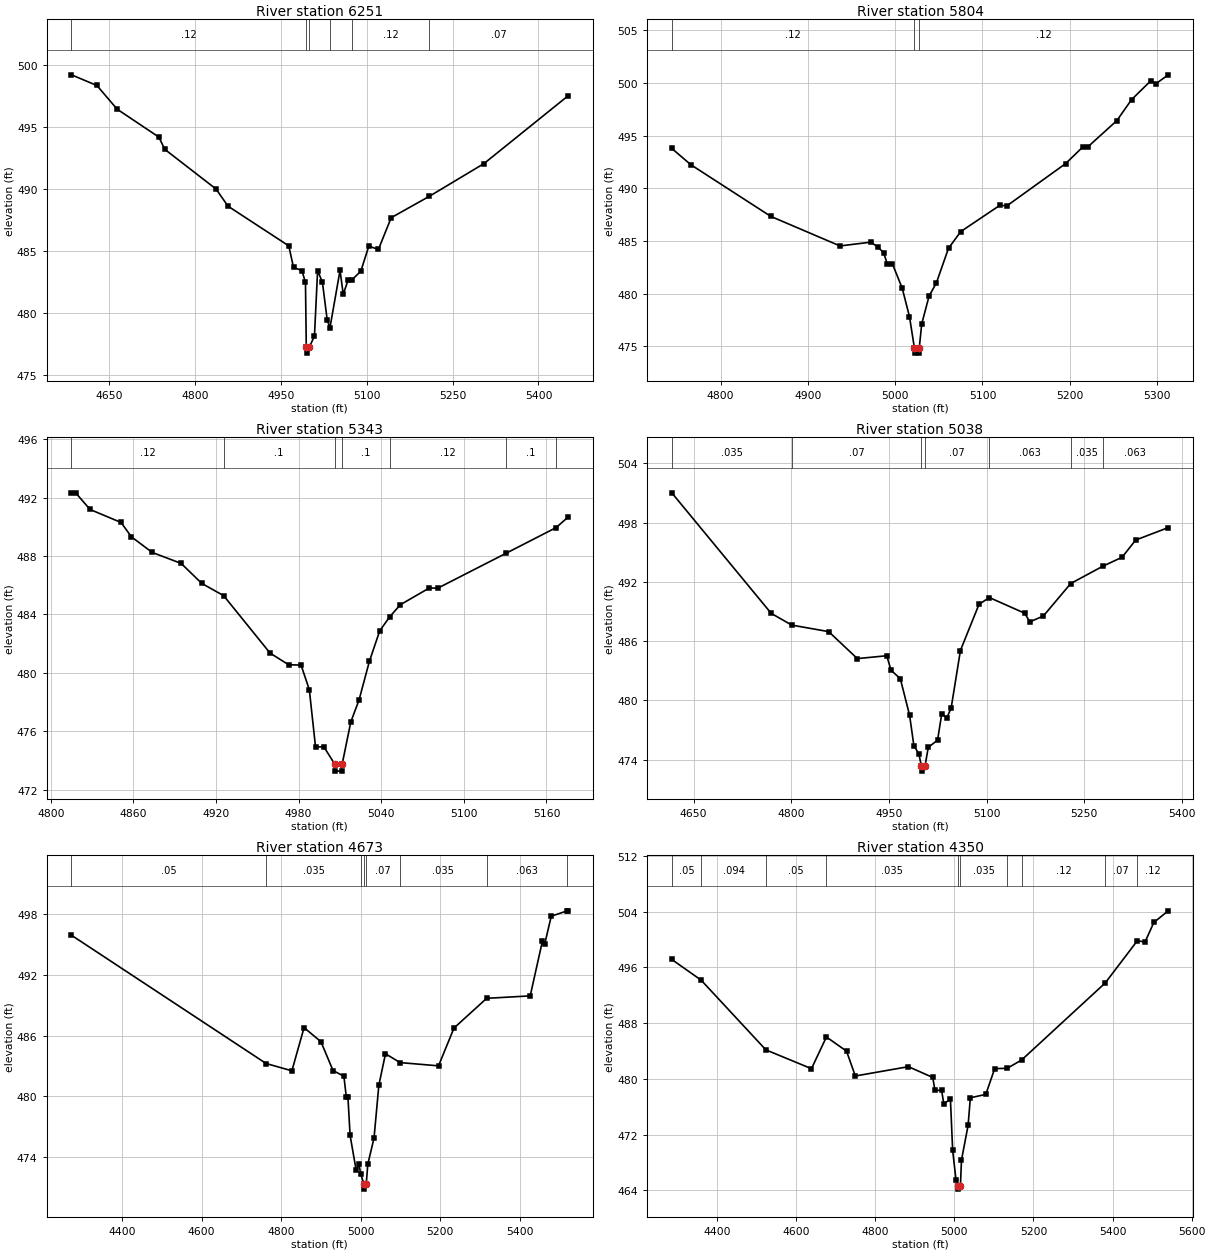
Type RM Length L Ch R = 1,6251,447,447,447
BEGIN DESCRIPTION:
GUADALUPE TRIBUTARY 13 14.0
END DESCRIPTION:
XS GIS Cut Line= 5
      2298975.24     13743858.01      2299075.00     13743725.00
      2299225.00     13743525.00      2299525.00     13743375.00
      2299628.86     13743323.07
#Sta/Elev= 30
  4583.7  499.18  4628.1  498.32  4663.5  496.41  4736.4  494.16  4746.8  493.17
  4836.4  489.97  4857.3  488.59  4963.5  485.39  4971.8  483.65  4986.4  483.40
  4992.7  482.44  4994.1  477.24  4994.5  476.74  4999.6  477.24  5008.4  478.12
  5013.9  483.39  5022.3  482.46  5030.7  479.40  5035.5  478.79  5053.1  483.41
  5058.7  481.49  5067.1  482.61  5074.2  482.67  5089.4  483.34  5103.4  485.37
  5120.2  485.10  5142.5  487.66  5209.4  489.39  5304.6  492.02  5451.5  497.48
#Mann=6,-1,0
  4583.7    0.12       0  4994.1    0.05       0  4999.6    0.12       0
  5035.5     0.1       0  5074.2    0.12       0  5209.4    0.07       0
Bank Sta=4994.1,4999.6
Exp/Cntr=0.3,0.1

Type RM Length L Ch R = 1,5804,461,461,461
BEGIN DESCRIPTION:
GUADALUPE TRIBUTARY 13 13.0
END DESCRIPTION:
XS GIS Cut Line= 4
      2299374.97     13744025.04      2299525.00     13743825.00
      2299725.00     13743725.00      2299810.19     13743682.41
#Sta/Elev= 30
  4744.0  493.80  4765.9  492.25  4857.6  487.34  4936.8  484.54  4972.2  484.90
  4980.5  484.41  4986.8  483.89  4990.9  482.84  4996.8  482.84  5008.0  480.54
  5016.4  477.82  5022.0  474.86  5022.4  474.36  5027.1  474.36  5027.6  474.86
  5030.4  477.13  5038.8  479.77  5047.2  481.03  5061.1  484.32  5075.1  485.90
  5119.8  488.39  5128.2  488.36  5195.3  492.36  5214.9  493.93  5220.5  493.93
  5254.0  496.44  5270.8  498.43  5293.1  500.24  5298.7  499.94  5312.9  500.79
#Mann=3,-1,0
  4744.0    0.12       0  5022.0    0.05       0  5027.6    0.12       0
Bank Sta=5022,5027.6
Exp/Cntr=0.3,0.1

Type RM Length L Ch R = 1,5343,305,305,305
BEGIN DESCRIPTION:
GUADALUPE TRIBUTARY 13 12.0
END DESCRIPTION:
XS GIS Cut Line= 3
      2299625.02     13744274.98      2299775.00     13744175.00
      2299924.98     13744075.01
#Sta/Elev= 30
  4815.1  492.32  4818.1  492.32  4828.6  491.18  4851.1  490.29  4858.6  489.31
  4873.7  488.24  4894.7  487.49  4909.7  486.12  4925.6  485.28  4959.3  481.35
  4972.8  480.55  4981.8  480.53  4987.8  478.84  4992.3  474.93  4998.4  474.93
  5006.1  473.77  5006.5  473.27  5011.2  473.27  5011.7  473.77  5017.9  476.63
  5023.9  478.14  5031.4  480.78  5038.9  482.87  5046.3  483.85  5053.9  484.66
  5075.0  485.81  5081.0  485.79  5130.4  488.17  5167.0  489.94  5175.6  490.65
#Mann=7,-1,0
  4815.1    0.12       0  4925.6     0.1       0  5006.1    0.05       0
  5011.7     0.1       0  5046.3    0.12       0  5130.4     0.1       0
  5167.0   0.035       0
Bank Sta=5006.1,5011.7
Exp/Cntr=0.3,0.1

Type RM Length L Ch R = 1,5038,365,365,365
BEGIN DESCRIPTION:
GUADALUPE TRIBUTARY 13 11.0
END DESCRIPTION:
XS GIS Cut Line= 3
      2299624.96     13744475.01      2299928.37     13744417.80
      2300275.00     13744125.00
#Sta/Elev= 30
  4616.5  501.02  4769.2  488.82  4800.8  487.63  4857.5  486.97  4901.5  484.24
  4946.7  484.53  4953.2  483.06  4967.5  482.21  4981.8  478.49  4988.3  475.43
  4996.1  474.59  4999.8  473.35  5000.3  472.85  5005.4  473.35  5010.4  475.25
  5024.7  475.99  5031.2  478.68  5038.7  478.22  5045.5  479.21  5059.8  485.06
  5088.4  489.74  5104.3  490.42  5158.6  488.83  5166.4  487.96  5187.2  488.55
  5229.2  491.84  5278.2  493.58  5308.1  494.50  5329.0  496.24  5379.0  497.50
#Mann=7,-1,0
  4616.5   0.035       0  4800.8    0.07       0  4999.8    0.05       0
  5005.4    0.07       0  5104.3   0.063       0  5229.2   0.035       0
  5278.2   0.063       0
Bank Sta=4999.8,5005.4
Exp/Cntr=0.3,0.1

Type RM Length L Ch R = 1,4673,323,323,323
BEGIN DESCRIPTION:
A19148
END DESCRIPTION:
XS GIS Cut Line= 3
      2299667.99     13744993.17      2300256.85     13744623.42
      2300507.93     13744130.39
#Sta/Elev= 30
  4272.9  495.89  4762.4  483.24  4827.2  482.52  4857.8  486.78  4900.3  485.39
  4930.6  482.55  4958.0  481.98  4964.2  479.89  4968.2  479.89  4973.6  476.15
  4988.9  472.70  4995.8  473.31  5000.5  472.32  5008.4  471.35  5008.9  470.85
  5014.2  471.35  5018.1  473.30  5033.8  475.90  5045.9  481.10  5062.6  484.20
  5099.4  483.33  5196.0  483.01  5234.9  486.74  5317.1  489.67  5426.6  489.91
  5457.3  495.32  5462.9  495.00  5479.5  497.77  5519.7  498.30  5521.5  498.30
#Mann=8,-1,0
  4272.9    0.05       0  4762.4   0.035       0  5000.5    0.07       0
  5008.4   0.035       0  5014.2    0.07       0  5099.4   0.035       0
  5317.1   0.063       0  5519.7    0.07       0
Bank Sta=5008.4,5014.2
Exp/Cntr=0.3,0.1

Type RM Length L Ch R = 1,4350,287,287,287
BEGIN DESCRIPTION:
GUADALUPE TRIBUTARY 13 10.0
END DESCRIPTION:
XS GIS Cut Line= 3
      2299924.96     13745125.02      2300225.00     13744925.00
      2301024.98     13744525.01
#Sta/Elev= 30
  4285.8  497.14  4360.0  494.17  4523.7  484.16  4638.9  481.46  4676.7  486.01
  4727.5  483.98  4749.8  480.41  4884.0  481.75  4945.5  480.20  4951.1  478.33
  4967.8  478.37  4973.4  476.43  4990.2  477.07  4995.8  469.74  5004.2  465.54
  5009.7  464.67  5010.1  464.17  5015.5  464.67  5018.1  468.33  5034.9  473.34
  5040.5  477.28  5079.6  477.77  5102.0  481.46  5134.0  481.52  5170.4  482.72
  5381.4  493.76  5462.6  499.82  5482.1  499.65  5504.5  502.46  5540.8  504.12
#Mann=10,-1,0
  4285.8    0.05       0  4360.0   0.094       0  4523.7    0.05       0
  4676.7   0.035       0  5009.7   0.035       0  5015.5   0.035       0
  5134.0    0.07       0  5170.4    0.12       0  5381.4    0.07       0
  5462.6    0.12       0
Bank Sta=5009.7,5015.5
Exp/Cntr=0.3,0.1

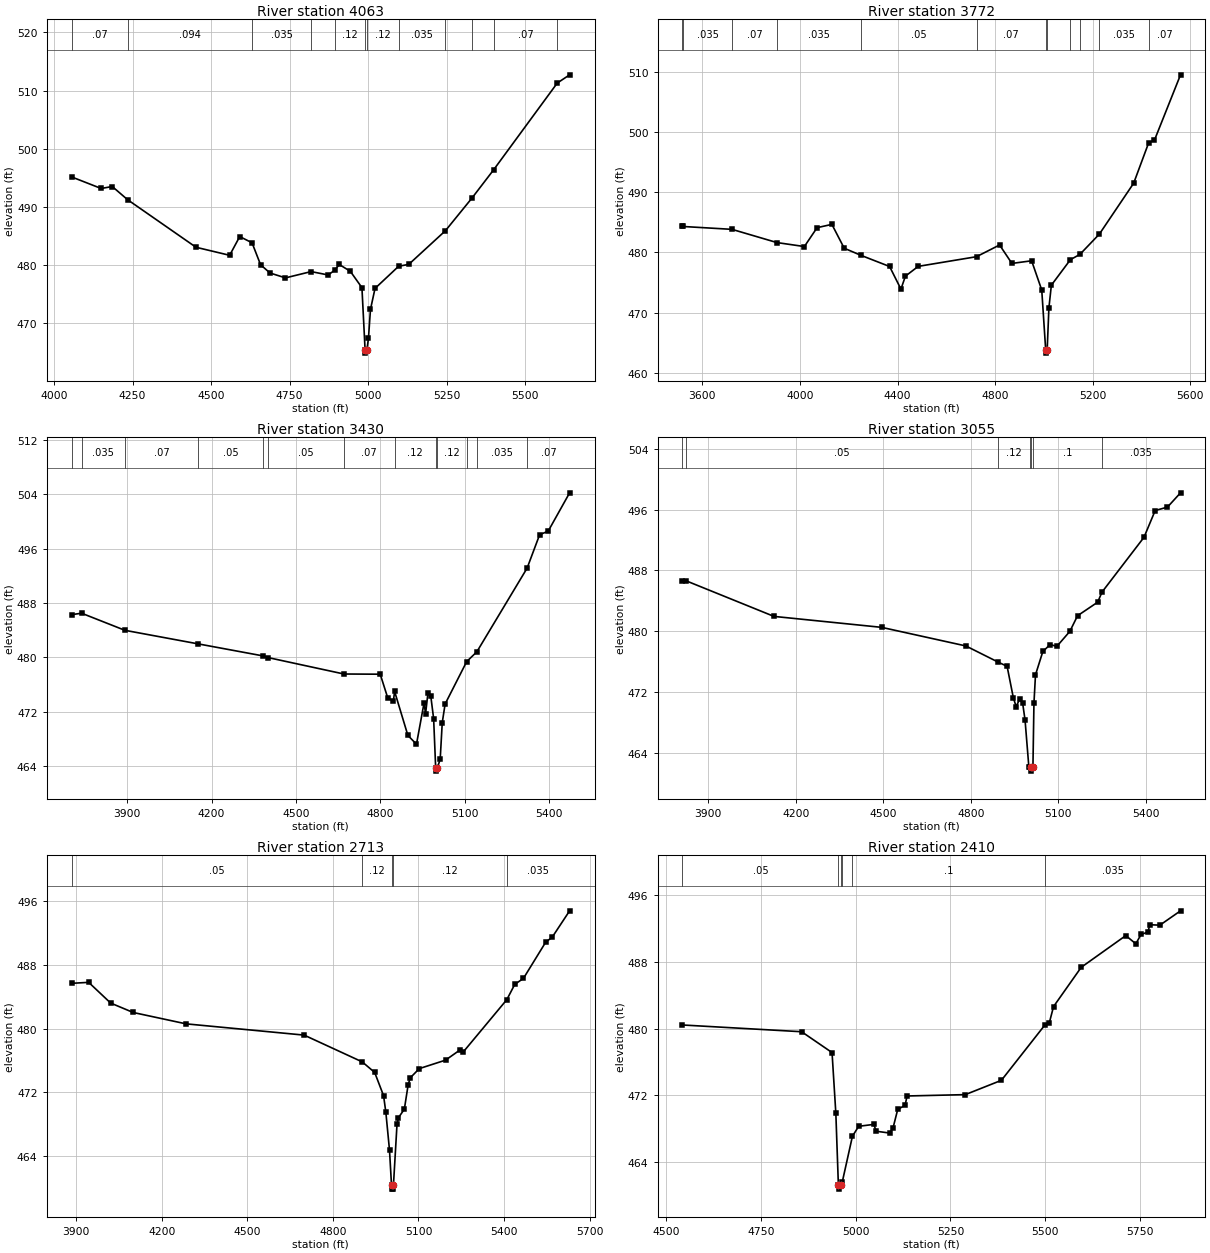
Type RM Length L Ch R = 1,4063,291,291,291
BEGIN DESCRIPTION:
GUADALUPE TRIBUTARY 13 9.0
END DESCRIPTION:
XS GIS Cut Line= 3
      2299875.00     13745375.00      2300525.00     13745125.00
      2301224.97     13744575.03
#Sta/Elev= 30
  4055.6  495.18  4149.9  493.19  4185.2  493.53  4234.2  491.26  4452.0  483.09
  4559.2  481.71  4591.3  484.93  4630.5  483.86  4657.7  480.09  4687.7  478.67
  4737.0  477.83  4818.7  478.91  4873.1  478.33  4894.1  479.16  4908.4  480.13
  4943.6  478.96  4980.6  476.15  4990.7  465.40  4991.2  464.90  4996.5  465.40
  5001.5  467.55  5007.8  472.41  5022.3  476.02  5097.6  479.83  5129.8  480.15
  5246.5  485.93  5331.5  491.57  5400.0  496.39  5602.9  511.31  5642.2  512.72
#Mann=12,-1,0
  4055.6    0.07       0  4234.2   0.094       0  4630.5   0.035       0
  4818.7    0.07       0  4894.1    0.12       0  4990.7    0.05       0
  4996.5    0.12       0  5097.6   0.035       0  5246.5    0.07       0
  5331.5    0.12       0  5400.0    0.07       0  5602.9   0.035       0
Bank Sta=4990.7,4996.5
Exp/Cntr=0.3,0.1

Type RM Length L Ch R = 1,3772,342,342,342
BEGIN DESCRIPTION:
A19147
END DESCRIPTION:
XS GIS Cut Line= 3
      2300727.06     13746590.92      2300959.87     13745002.32
      2301229.22     13744659.93
#Sta/Elev= 30
  3518.3  484.33  3520.0  484.32  3721.4  483.84  3905.5  481.64  4017.9  480.98
  4070.0  484.12  4130.7  484.67  4181.2  480.70  4250.2  479.51  4367.2  477.66
  4413.7  473.89  4432.0  476.05  4484.4  477.68  4723.4  479.29  4818.0  481.24
  4868.5  478.17  4949.3  478.61  4990.8  473.74  5007.0  463.74  5007.5  463.24
  5013.0  463.74  5020.1  470.76  5030.2  474.55  5108.3  478.80  5147.1  479.67
  5227.1  483.06  5367.6  491.53  5429.1  498.26  5452.6  498.67  5559.5  509.56
#Mann=12,-1,0
  3518.3    0.07       0  3520.0   0.035       0  3721.4    0.07       0
  3905.5   0.035       0  4250.2    0.05       0  4723.4    0.07       0
  5007.0    0.05       0  5013.0    0.07       0  5108.3   0.035       0
  5147.1    0.12       0  5227.1   0.035       0  5429.1    0.07       0
Bank Sta=5007,5013
Exp/Cntr=0.3,0.1

Type RM Length L Ch R = 1,3430,375,375,375
BEGIN DESCRIPTION:
A19146
END DESCRIPTION:
XS GIS Cut Line= 2
      2301023.78     13746449.44      2301357.03     13744710.18
#Sta/Elev= 30
  3702.3  486.28  3738.0  486.49  3892.0  483.98  4153.2  481.98  4381.6  480.23
  4401.3  479.97  4670.8  477.56  4799.8  477.53  4826.8  474.01  4846.7  473.61
  4850.9  475.00  4898.1  468.54  4928.7  467.24  4955.8  473.35  4960.9  471.68
  4969.4  474.75  4979.6  474.30  4989.7  471.00  4996.9  463.79  4997.4  463.29
  5003.0  463.79  5013.0  465.03  5020.3  470.41  5030.5  473.15  5107.3  479.39
  5143.3  480.82  5322.1  493.12  5366.5  498.02  5397.0  498.55  5473.2  504.18
#Mann=13,-1,0
  3702.3    0.07       0  3738.0   0.035       0  3892.0    0.07       0
  4153.2    0.05       0  4381.6    0.07       0  4401.3    0.05       0
  4670.8    0.07       0  4850.9    0.12       0  4996.9    0.05       0
  5003.0    0.12       0  5107.3     0.1       0  5143.3   0.035       0
  5322.1    0.07       0
Bank Sta=4996.9,5003
Exp/Cntr=0.3,0.1

Type RM Length L Ch R = 1,3055,342,342,342
BEGIN DESCRIPTION:
A19145
END DESCRIPTION:
XS GIS Cut Line= 3
      2301174.43     13746449.45      2301621.80     13745230.57
      2301749.62     13744842.57
#Sta/Elev= 30
  3811.5  486.59  3824.4  486.63  4125.2  481.95  4493.9  480.51  4782.8  478.06
  4893.5  475.93  4924.1  475.38  4945.4  471.25  4955.1  470.08  4966.7  471.02
  4977.3  470.54  4985.6  468.31  4998.6  462.15  5002.3  462.11  5005.9  462.08
  5006.4  461.58  5012.6  462.08  5016.1  470.53  5021.4  474.26  5046.6  477.33
  5071.8  478.25  5094.5  478.00  5139.1  479.98  5165.6  482.04  5234.4  483.82
  5249.5  485.16  5393.3  492.37  5431.6  495.89  5473.7  496.34  5518.4  498.22
#Mann=7,-1,0
  3811.5    0.07       0  3824.4    0.05       0  4893.5    0.12       0
  5002.3     0.1       0  5005.9    0.05       0  5012.6     0.1       0
  5249.5   0.035       0
Bank Sta=5005.9,5012.6
Exp/Cntr=0.3,0.1

Type RM Length L Ch R = 1,2713,303,303,303
BEGIN DESCRIPTION:
A19144
END DESCRIPTION:
XS GIS Cut Line= 4
      2301210.92     13746454.04      2301808.97     13745664.25
      2301886.58     13745390.35      2301818.10     13744924.71
#Sta/Elev= 30
  3883.9  485.66  3943.9  485.78  4020.9  483.19  4100.0  482.01  4285.1  480.59
  4699.2  479.18  4902.9  475.83  4946.5  474.51  4977.7  471.60  4985.7  469.51
  4998.5  464.78  5005.5  460.41  5006.0  459.91  5011.8  459.91  5012.3  460.41
  5024.8  468.03  5030.0  468.86  5050.5  469.91  5063.9  472.98  5071.3  473.84
  5103.0  474.99  5195.0  476.05  5245.5  477.32  5255.6  477.01  5409.8  483.62
  5437.6  485.53  5467.9  486.27  5545.9  490.80  5569.0  491.44  5629.9  494.73
#Mann=5,-1,0
  3883.9    0.05       0  4902.9    0.12       0  5005.5    0.05       0
  5012.3    0.12       0  5409.8   0.035       0
Bank Sta=5005.5,5012.3
Exp/Cntr=0.3,0.1

Type RM Length L Ch R = 1,2410,725,725,725
BEGIN DESCRIPTION:
A19143
END DESCRIPTION:
XS GIS Cut Line= 4
      2302060.05     13746061.41      2302142.22     13745878.81
      2302114.83     13745568.38      2301863.76     13744806.03
#Sta/Elev= 30
  4542.9  480.44  4857.4  479.63  4937.7  477.13  4947.7  469.84  4954.4  461.24
  4954.9  460.74  4961.2  461.24  4964.7  461.60  4991.5  467.09  5008.0  468.28
  5048.1  468.51  5054.0  467.69  5089.9  467.47  5098.7  468.09  5111.0  470.30
  5130.5  470.81  5135.7  471.92  5289.3  472.08  5384.7  473.80  5499.3  480.43
  5511.0  480.68  5522.3  482.65  5595.3  487.36  5713.0  491.17  5739.5  490.18
  5753.2  491.31  5771.2  491.58  5776.5  492.47  5803.0  492.42  5857.4  494.14
#Mann=6,-1,0
  4542.9    0.05       0  4954.4    0.05       0  4961.2    0.05       0
  4964.7    0.12       0  4991.5     0.1       0  5499.3   0.035       0
Bank Sta=4954.4,4961.2
Exp/Cntr=0.3,0.1