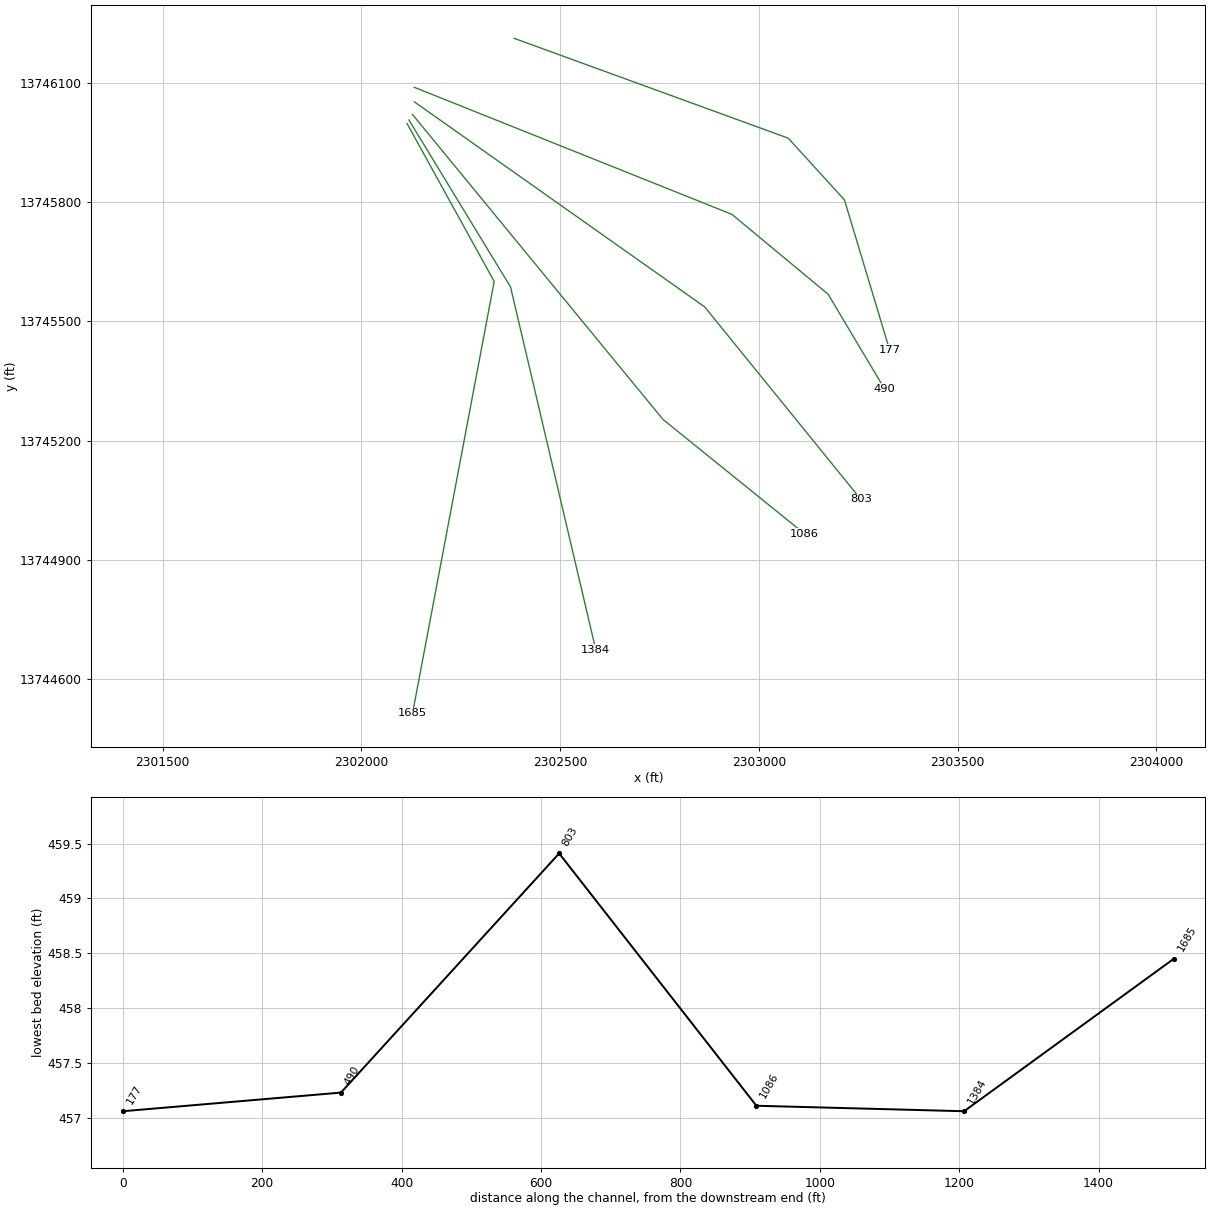
HEC-RAS study GUADALUPE TRIBUTARY 13.prj: GUADALUPE TRIBUTARY 13 Base Level Engineering

--- GUADALUPE TRIBUTARY 13.g01 (geometry) --- (continued)

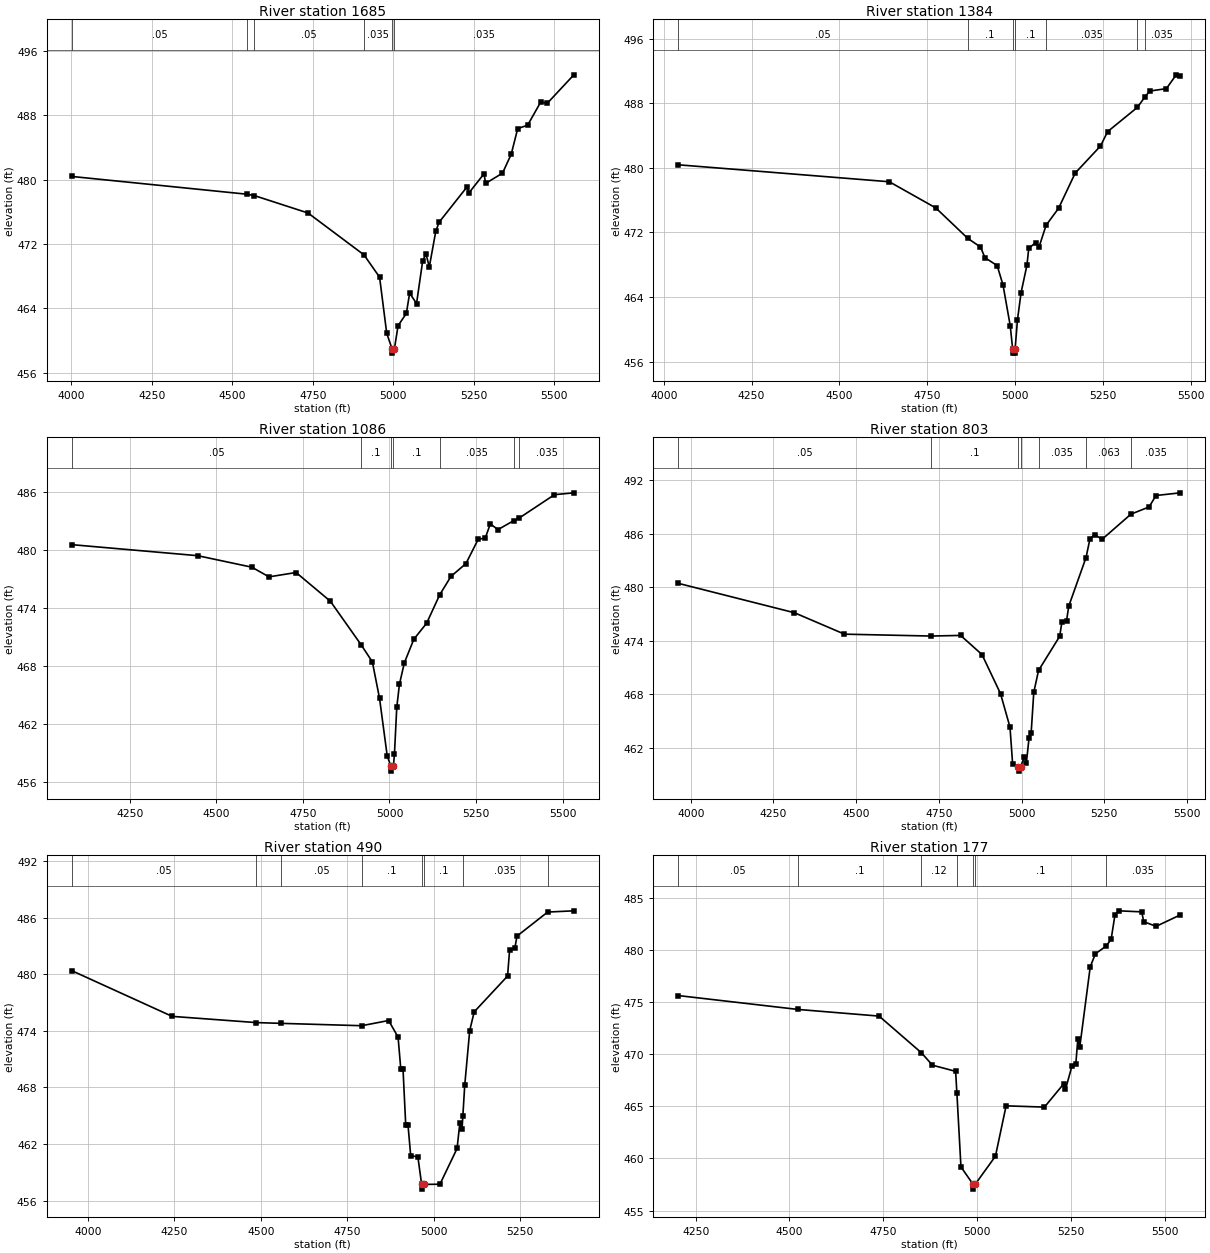
Type RM Length L Ch R = 1,1685,301,301,301
BEGIN DESCRIPTION:
A19142
END DESCRIPTION:
XS GIS Cut Line= 3
      2302114.84     13745997.49      2302333.95     13745600.34
      2302128.53     13744513.88
#Sta/Elev= 30
  4001.7  480.39  4546.7  478.18  4569.0  478.01  4735.5  475.85  4909.3  470.65
  4957.7  467.88  4979.8  460.92  4996.7  458.95  4997.2  458.45  5003.6  458.95
  5015.1  461.86  5040.8  463.38  5051.0  465.90  5072.5  464.61  5091.7  469.95
  5101.9  470.75  5112.1  469.16  5132.4  473.62  5142.6  474.71  5229.6  479.11
  5234.7  478.32  5282.0  480.72  5287.1  479.53  5339.4  480.80  5366.5  483.15
  5386.7  486.34  5417.4  486.75  5458.1  489.63  5478.4  489.47  5561.0  493.01
#Mann=6,-1,0
  4001.7    0.05       0  4546.7     0.1       0  4569.0    0.05       0
  4909.3   0.035       0  4996.7   0.035       0  5003.6   0.035       0
Bank Sta=4996.7,5003.6
Exp/Cntr=0.3,0.1

Type RM Length L Ch R = 1,1384,298,298,298
BEGIN DESCRIPTION:
A19141
END DESCRIPTION:
XS GIS Cut Line= 3
      2302119.38     13746006.66      2302375.04     13745586.64
      2302589.60     13744673.62
#Sta/Elev= 30
  4041.3  480.38  4642.3  478.28  4774.7  475.04  4865.7  471.27  4901.9  470.20
  4914.8  468.87  4949.4  467.90  4966.1  465.49  4986.7  460.43  4993.5  457.56
  4994.0  457.06  5000.0  457.06  5000.5  457.56  5007.2  461.17  5017.5  464.55
  5034.2  467.95  5039.4  470.05  5058.6  470.72  5068.9  470.24  5088.8  472.90
  5124.2  474.99  5171.7  479.36  5243.5  482.70  5264.0  484.49  5348.9  487.50
  5369.1  488.72  5383.7  489.51  5431.2  489.81  5459.2  491.52  5470.9  491.32
#Mann=7,-1,0
  4041.3    0.05       0  4865.7     0.1       0  4993.5    0.05       0
  5000.5     0.1       0  5088.8   0.035       0  5348.9   0.063       0
  5369.1   0.035       0
Bank Sta=4993.5,5000.5
Exp/Cntr=0.3,0.1

Type RM Length L Ch R = 1,1086,283,283,283
BEGIN DESCRIPTION:
A19140
END DESCRIPTION:
XS GIS Cut Line= 3
      2302128.52     13746020.33      2302758.50     13745253.40
      2303114.56     13744965.81
#Sta/Elev= 30
  4082.3  480.53  4446.0  479.39  4602.4  478.20  4652.0  477.20  4730.2  477.65
  4829.2  474.68  4917.8  470.19  4950.5  468.41  4971.3  464.63  4993.5  458.66
  5004.3  457.61  5004.8  457.11  5011.3  457.61  5014.3  458.85  5021.0  463.69
  5028.7  466.09  5043.0  468.32  5070.5  470.76  5107.2  472.40  5145.0  475.34
  5177.6  477.25  5220.8  478.57  5256.0  481.07  5276.8  481.23  5291.2  482.67
  5313.5  482.09  5359.2  483.02  5375.4  483.30  5476.6  485.70  5532.5  485.89
#Mann=7,-1,0
  4082.3    0.05       0  4917.8     0.1       0  5004.3    0.05       0
  5011.3     0.1       0  5145.0   0.035       0  5359.2   0.063       0
  5375.4   0.035       0
Bank Sta=5004.3,5011.3
Exp/Cntr=0.3,0.1

Type RM Length L Ch R = 1,803,313,313,313
BEGIN DESCRIPTION:
A19139
END DESCRIPTION:
XS GIS Cut Line= 3
      2302133.09     13746052.28      2302863.50     13745536.43
      2303256.07     13745052.56
#Sta/Elev= 30
  3962.2  480.43  4313.2  477.14  4464.6  474.74  4725.3  474.53  4815.5  474.60
  4880.1  472.46  4936.1  468.09  4964.8  464.33  4972.8  460.18  4990.1  459.91
  4990.6  459.41  4997.1  459.91  5008.0  461.02  5014.4  460.37  5022.3  463.09
  5028.8  463.73  5036.7  468.24  5051.1  470.68  5115.0  474.50  5121.5  476.07
  5135.8  476.26  5142.3  477.87  5194.6  483.32  5206.2  485.37  5220.6  485.89
  5242.9  485.35  5330.2  488.17  5385.1  488.98  5406.0  490.26  5479.5  490.56
#Mann=7,-1,0
  3962.2    0.05       0  4725.3     0.1       0  4990.1    0.05       0
  4997.1     0.1       0  5051.1   0.035       0  5194.6   0.063       0
  5330.2   0.035       0
Bank Sta=4990.1,4997.1
Exp/Cntr=0.3,0.1

Type RM Length L Ch R = 1,490,313,313,313
BEGIN DESCRIPTION:
A19138
END DESCRIPTION:
XS GIS Cut Line= 4
      2302133.08     13746088.81      2302931.98     13745769.25
      2303173.92     13745568.38      2303315.46     13745330.97
#Sta/Elev= 30
  3953.6  480.37  4243.8  475.53  4487.2  474.87  4558.9  474.79  4791.6  474.54
  4869.5  475.09  4896.8  473.34  4904.6  469.99  4911.1  469.96  4918.9  464.05
  4925.4  464.07  4933.3  460.78  4954.1  460.64  4964.9  457.73  4965.4  457.23
  4972.0  457.73  5017.9  457.75  5067.4  461.54  5075.2  464.19  5081.7  463.58
  5084.0  464.95  5089.5  468.23  5103.9  474.03  5116.9  476.01  5213.3  479.80
  5219.1  482.51  5234.7  482.82  5240.5  484.03  5329.2  486.58  5404.9  486.71
#Mann=8,-1,0
  3953.6    0.05       0  4487.2     0.1       0  4558.9    0.05       0
  4791.6     0.1       0  4964.9    0.05       0  4972.0     0.1       0
  5084.0   0.035       0  5329.2   0.063       0
Bank Sta=4964.9,4972
Exp/Cntr=0.3,0.1

Type RM Length L Ch R = 1,177,0,0,0
BEGIN DESCRIPTION:
A19137
END DESCRIPTION:
XS GIS Cut Line= 4
      2302384.15     13746212.07      2303073.49     13745960.98
      2303215.01     13745805.77      2303328.67     13745428.41
#Sta/Elev= 30
  4203.6  475.63  4522.3  474.30  4738.8  473.66  4851.3  470.15  4881.0  468.95
  4942.7  468.36  4946.1  466.27  4956.9  459.19  4988.5  457.56  4989.0  457.06
  4995.6  457.56  5048.8  460.22  5077.2  465.05  5179.4  464.93  5230.2  467.14
  5235.4  466.62  5252.5  468.85  5263.0  469.08  5268.4  471.50  5273.6  470.72
  5301.4  478.39  5315.2  479.64  5343.1  480.36  5357.0  481.01  5367.4  483.40
  5377.9  483.76  5438.6  483.66  5443.9  482.72  5476.9  482.27  5541.4  483.37
#Mann=7,-1,0
  4203.6    0.05       0  4522.3     0.1       0  4851.3    0.12       0
  4946.1     0.1       0  4988.5    0.05       0  4995.6     0.1       0
  5343.1   0.035       0
Bank Sta=4988.5,4995.6
Exp/Cntr=0.3,0.1

Chan Stop Cuts=-1