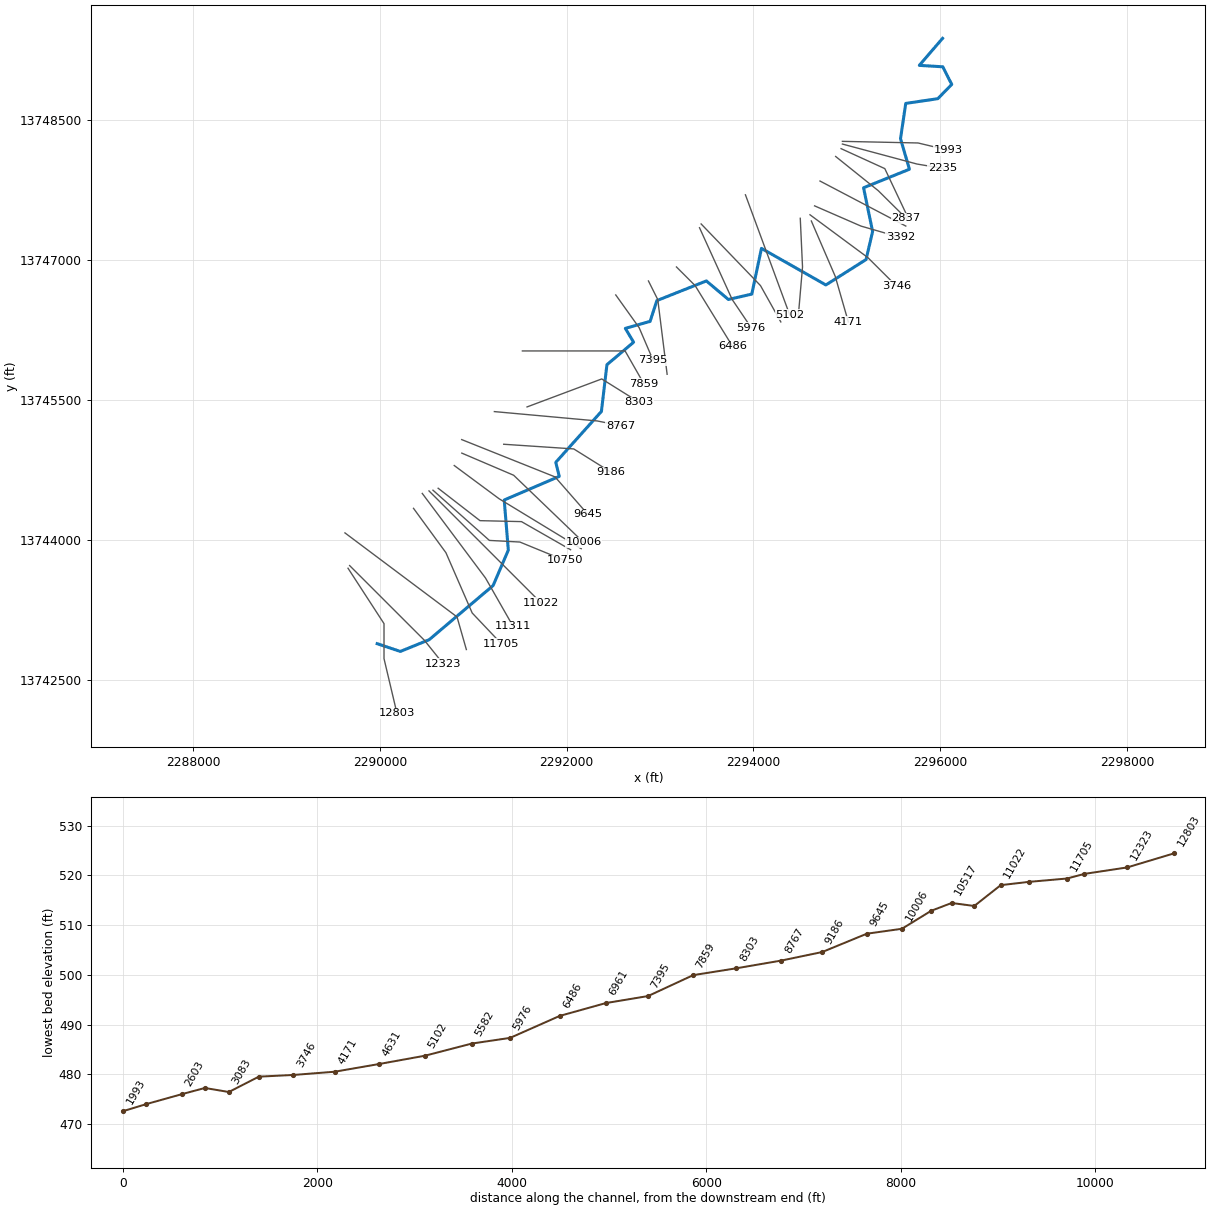
--- GUADALUPE TRIBUTARY 15.prj (project) ---

Proj Title=GUADALUPE TRIBUTARY 15 Base Level Engineering
Current Plan=p01
Default Exp/Contr=0.3,0.1
English Units
Geom File=g01
Flow File=f01
Plan File=p01
Y Axis Title=Elevation
X Axis Title(PF)=Main Channel Distance
X Axis Title(XS)=Station
BEGIN DESCRIPTION:
GUADALUPE TRIBUTARY 15
END DESCRIPTION:
DSS Export Rating Curves= 0
DSS Export Rating Curve Sorted= 0
DSS Export Volume Flow Curves= 0
DXF OffsetX= 0
DXF OffsetY= 0
DXF ScaleX= 1
DXF ScaleY= 10

--- GUADALUPE TRIBUTARY 15.p01 (plan) ---

Plan Title=Multiple Run
Short Identifier=Multiple
Geom File=g01
Flow File=f01
Subcritical Flow
K Sum by GR= 0
Std Step Tol= 0.01
Critical Tol= 0.01
Num of Std Step Trials= 20
Max Error Tol= 0.3
Flow Tol Ratio= 0.001
Split Flow NTrial= 30
Split Flow Tol= 0.02
Split Flow Ratio= 0.02
Log Output Level= 0
Friction Slope Method= 1
Unsteady Friction Slope Method= 2
Unsteady Bridges Friction Slope Method= 1
Parabolic Critical Depth
Global Vel Dist=  1 , 1 , 1
Global Log Level= 0
CheckData=True
Encroach Param= -1, 0, 0, 0
BEGIN DESCRIPTION:
Multiple Run
END DESCRIPTION:

--- GUADALUPE TRIBUTARY 15.f01 (steady flow) ---

Flow Title=Multiple
Number of Profiles=7
Profile Names=10-year,25-year,50-year,1pct_min,100-year,1pct_plu,500-year
River Rch & RM= GUADALUPE TRIBUT,Reach-1,12803
     795    1314    1795    1187    2369    4727    4092
River Rch & RM= GUADALUPE TRIBUT,Reach-1,11311
     925    1537    2106    1396    2786    5559    4835
River Rch & RM= GUADALUPE TRIBUT,Reach-1,7859
    1083    1805    2479    1646    3284    6552    5714
River Rch & RM= GUADALUPE TRIBUT,Reach-1,2235
    1070    1780    2440    1616    3225    6435    5588
Boundary for River Rch & Prof#=GUADALUPE TRIBUT,Reach-1,1
Up Type=0
Dn Type=3
Dn Slope=0.005
Boundary for River Rch & Prof#=GUADALUPE TRIBUT,Reach-1,2
Up Type=0
Dn Type=3
Dn Slope=0.005
Boundary for River Rch & Prof#=GUADALUPE TRIBUT,Reach-1,3
Up Type=0
Dn Type=3
Dn Slope=0.005
Boundary for River Rch & Prof#=GUADALUPE TRIBUT,Reach-1,4
Up Type=0
Dn Type=3
Dn Slope=0.005
Boundary for River Rch & Prof#=GUADALUPE TRIBUT,Reach-1,5
Up Type=0
Dn Type=3
Dn Slope=0.005
Boundary for River Rch & Prof#=GUADALUPE TRIBUT,Reach-1,6
Up Type=0
Dn Type=3
Dn Slope=0.005
Boundary for River Rch & Prof#=GUADALUPE TRIBUT,Reach-1,7
Up Type=0
Dn Type=3
Dn Slope=0.005

--- GUADALUPE TRIBUTARY 15.g01 (geometry) ---

Geom Title=Existing Conditions
Program Version=4.10

River Reach=GUADALUPE TRIBUT,Reach-1
Reach XY= 30
      2289969.46     13742887.99      2290218.06     13742804.71
       2290527.3     13742930.83       2291211.6     13743510.91
      2291374.48     13743890.22      2291330.46     13744427.45
      2291920.22     13744680.61      2291882.48     13744831.07
      2292371.25     13745376.55      2292430.41     13745877.71
      2292716.04     13746118.33      2292627.43     13746266.89
      2292892.57     13746341.63      2292965.19     13746564.49
      2293495.18      13746775.3      2293730.87      13746576.5
      2293981.75     13746634.14      2294085.27     13747124.04
        2294775.     13746732.08      2295205.58     13747004.46
      2295275.46     13747304.84      2295178.53     13747773.55
      2295669.64     13747972.22      2295574.51     13748299.96
      2295630.36      13748677.7      2295973.37     13748728.13
      2296123.04     13748880.89      2296027.31     13749069.92
      2295775.86     13749085.31        2296025.       13749375.

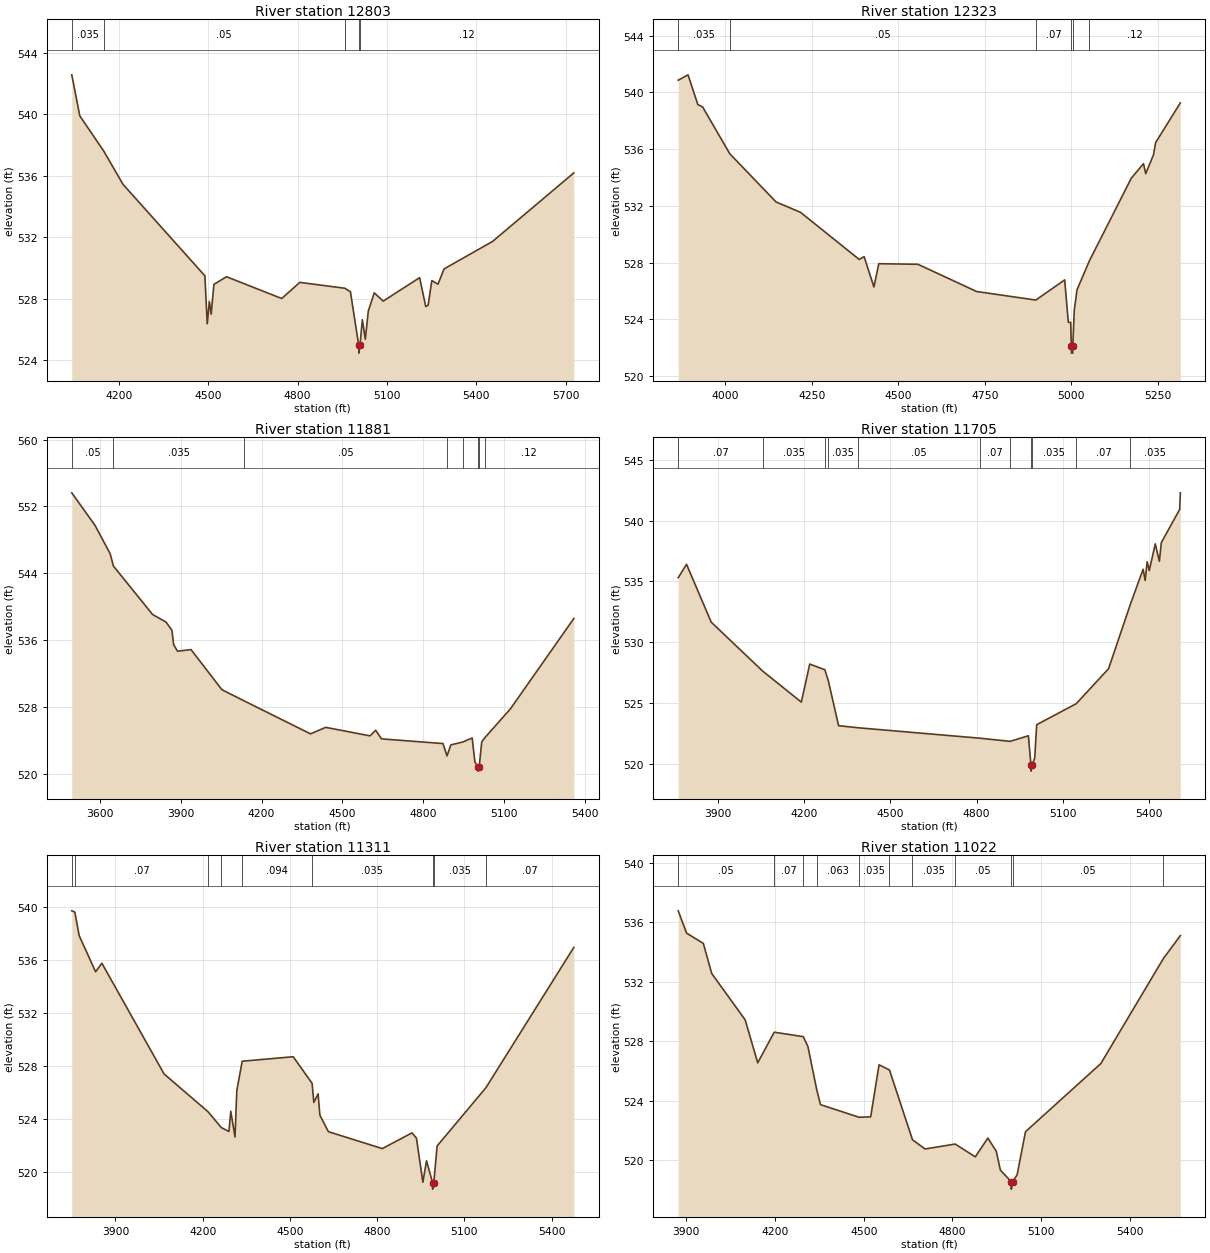
Type RM Length L Ch R = 1 ,12803   ,480,480,480
BEGIN DESCRIPTION:
A19165
END DESCRIPTION:
XS GIS Cut Line= 4
      2289657.73     13743696.59      2290043.13     13743102.87
      2290043.13     13742727.87      2290182.03     13742141.02
#Sta/Elev= 30
  4041.6  542.58  4068.7   539.9  4148.7  537.62  4213.7  535.44  4488.6  529.48
  4496.5  526.35  4503.7  527.81  4509.7  526.98  4518.9  528.92  4561.1  529.42
  4746.6     528  4807.3  529.05  4958.4  528.67  4977.3  528.44  5005.3  524.94
  5005.6  524.44  5009.3  524.94  5017.3  526.62  5027.3  525.35  5037.3  527.18
  5057.3  528.37  5087.3  527.83  5209.6  529.36  5230.2  527.48  5238.2  527.56
  5250.7  529.17  5271.3  528.93  5291.8  529.93  5454.6  531.72  5727.5  536.19
#Mann= 5 ,-1 , 0
  4041.6    .035       0  4148.7     .05       0  4958.4     .12       0
  5005.3     .05       0  5009.3     .12       0
Bank Sta=5005.3,5009.3
XS Rating Curve= 0 ,0
Exp/Cntr=0.3,0.1

Type RM Length L Ch R = 1 ,12323   ,442,442,442
BEGIN DESCRIPTION:
GUADALUPE TRIBUTARY 15 27.0
END DESCRIPTION:
XS GIS Cut Line= 3
      2289674.99     13743725.01        2290475.       13742925.
      2290674.98     13742675.03
#Sta/Elev= 30
  3863.8  540.85  3892.1  541.23  3920.4  539.14  3934.5  538.96  4012.8  535.67
  4146.7  532.27  4217.4  531.54  4387.1  528.22  4401.2  528.42  4429.5  526.28
  4443.6  527.92  4556.8  527.88  4726.5  525.96  4897.6  525.36    4981  526.78
  4991.6  523.79  4998.4  523.79  5000.3  522.12  5000.6  521.62  5004.2  521.62
  5004.4  522.12  5008.8  524.66  5016.8  526.09  5052.4  528.12  5173.7  533.95
  5208.9  534.97  5215.3  534.27  5237.7  535.59  5244.1  536.46  5315.3  539.25
#Mann= 6 ,-1 , 0
  3863.8    .035       0  4012.8     .05       0  4897.6     .07       0
  5000.3     .05       0  5004.4     .07       0  5052.4     .12       0
Bank Sta=5000.3,5004.4
XS Rating Curve= 0 ,0
Exp/Cntr=0.3,0.1

Type RM Length L Ch R = 1 ,11881   ,176,176,176
BEGIN DESCRIPTION:
GUADALUPE TRIBUTARY 15 26.0
END DESCRIPTION:
XS GIS Cut Line= 3
      2289624.98     13744075.02        2290825.       13743175.
      2290924.99     13742825.03
#Sta/Elev= 30
  3495.6  553.62  3582.1  549.72  3638.3  546.32  3650.2  544.86  3795.6  539.06
  3845.6  538.15  3867.5  537.16  3873.8  535.45  3888.3  534.66  3938.3  534.86
  4052.9  530.06  4135.4  528.72  4382.1  524.77  4438.3  525.55  4602.9  524.53
  4623.8   525.2  4645.6  524.17  4873.8  523.61  4888.8  522.13  4902.9  523.45
  4947.8   523.8  4982.1  524.28  4992.5  521.38    5004  520.81  5004.2  520.31
  5008.1  520.81  5017.7  523.82  5028.4  524.28  5124.3  527.77  5359.6  538.58
#Mann= 8 ,-1 , 0
  3495.6     .05       0  3650.2    .035       0  4135.4     .05       0
  4888.8     .07       0  4947.8    .035       0    5004    .035       0
  5008.1    .035       0  5028.4     .12       0
Bank Sta=5004,5008.1
XS Rating Curve= 0 ,0
Exp/Cntr=0.3,0.1

Type RM Length L Ch R = 1 ,11705   ,394,394,394
BEGIN DESCRIPTION:
A19164
END DESCRIPTION:
XS GIS Cut Line= 4
      2290359.08     13744338.31      2290706.32     13743862.59
      2290987.57     13743216.76      2291300.02     13742886.95
#Sta/Elev= 30
  3761.3  535.31  3790.2  536.41  3876.1  531.65  4055.4  527.62  4189.7  525.07
  4219.1   528.2  4271.9  527.73  4283.9  526.81  4319.5  523.13  4386.6  522.96
  4810.7   522.1  4916.7  521.84  4980.2   522.3  4989.1  519.89  4989.4  519.39
  4993.3  519.89  5002.1  520.46  5009.1  523.21  5146.8  524.94  5259.3  527.82
  5335.5  533.14  5379.5     536  5386.7  535.08  5393.6  536.62  5400.9  535.89
  5421.9  538.09  5436.1  536.66    5443   538.2  5506.9  540.93    5509  542.29
#Mann= 11 ,-1 , 0
  3761.3     .07       0  4055.4    .035       0  4271.9    .094       0
  4283.9    .035       0  4386.6     .05       0  4810.7     .07       0
  4916.7    .035       0  4989.1    .035       0  4993.3    .035       0
  5146.8     .07       0  5335.5    .035       0
Bank Sta=4989.1,4993.3
XS Rating Curve= 0 ,0
Exp/Cntr=0.3,0.1

Type RM Length L Ch R = 1 ,11311   ,289,289,289
BEGIN DESCRIPTION:
GUADALUPE TRIBUTARY 15 25.0
END DESCRIPTION:
XS GIS Cut Line= 3
      2290452.84     13744498.02      2291129.94     13743591.76
      2291424.98     13743075.03
#Sta/Elev= 30
  3749.9  539.73  3760.4  539.64  3775.5  537.85  3831.8  535.13  3853.5  535.77
  4067.3  527.41  4218.2  524.56  4264.1  523.36  4290.3  523.06  4296.6  524.59
  4311.2  522.65  4317.4  526.16  4335.9  528.37  4511.3  528.71  4576.3   526.7
  4582.2  525.26  4596.8  525.91    4603   524.3  4632.2  523.05  4817.7  521.77
  4919.7  522.96    4935  522.56  4957.1  519.23  4969.6  520.85  4990.4  519.21
  4990.7  518.71  4994.7  519.21  5006.1  521.97  5173.9  526.37  5476.2  536.97
#Mann= 9 ,-1 , 0
  3749.9     .05       0  3760.4     .07       0  4218.2    .035       0
  4264.1    .063       0  4335.9    .094       0  4576.3    .035       0
  4990.4    .035       0  4994.7    .035       0  5173.9     .07       0
Bank Sta=4990.4,4994.7
XS Rating Curve= 0 ,0
Exp/Cntr=0.3,0.1

Type RM Length L Ch R = 1 ,11022   ,272,272,272
BEGIN DESCRIPTION:
GUADALUPE TRIBUTARY 15 24.0
END DESCRIPTION:
XS GIS Cut Line= 3
        2290525.       13744525.        2291325.       13743725.
      2291725.03     13743324.97
#Sta/Elev= 30
    3873  536.76  3901.3  535.26  3957.9  534.57  3986.1  532.55  4099.3  529.43
  4141.7  526.54  4197.4   528.6  4295.7   528.3  4311.4  527.63  4340.9  524.76
  4353.8  523.73  4484.4  522.88  4523.5  522.91  4551.8  526.41    4587  526.06
  4664.8  521.37  4707.4  520.75  4809.2  521.08  4877.1  520.22  4919.5  521.48
  4947.8  520.61  4961.9  519.33  4998.6  518.55  4998.9  518.05    5003  518.55
  5018.5  519.01  5046.8  521.91  5301.4  526.49  5512.8  533.55  5570.1  535.09
#Mann= 11 ,-1 , 0
    3873     .05       0  4197.4     .07       0  4295.7    .035       0
  4340.9    .063       0  4484.4    .035       0    4587    .063       0
  4664.8    .035       0  4809.2     .05       0  4998.6     .05       0
    5003     .05       0  5512.8     .12       0
Bank Sta=4998.6,5003
XS Rating Curve= 0 ,0
Exp/Cntr=0.3,0.1

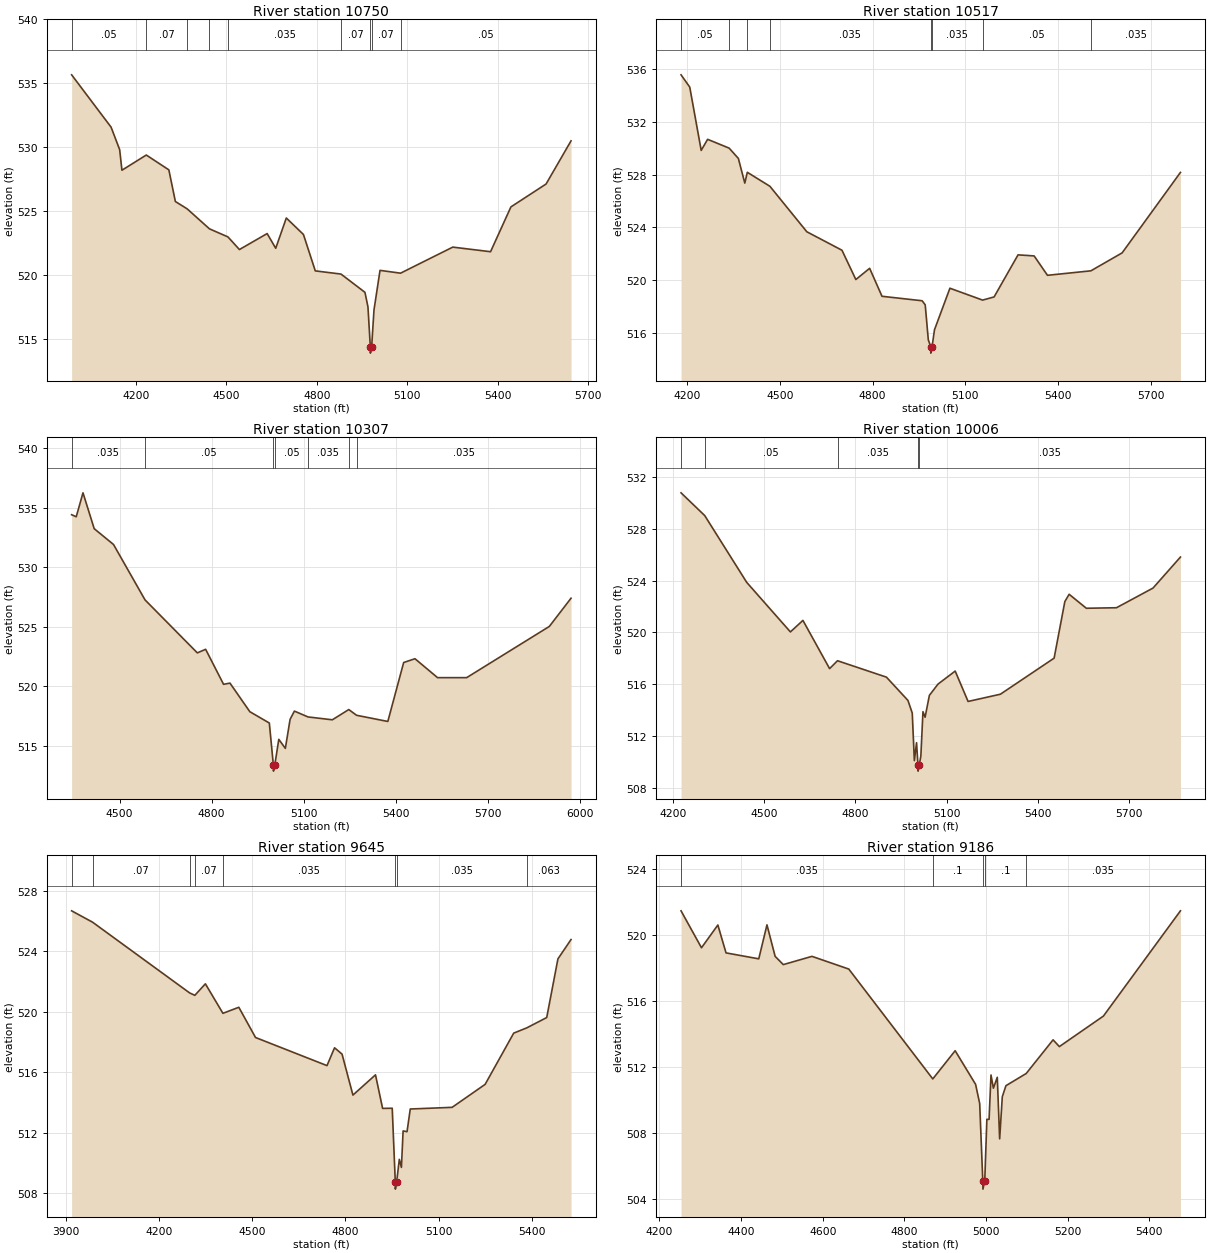
Type RM Length L Ch R = 1 ,10750   ,233,233,233
BEGIN DESCRIPTION:
A19163
END DESCRIPTION:
XS GIS Cut Line= 4
      2290567.42     13744532.74       2291171.6     13743994.53
      2291497.99     13743977.17      2291979.39     13743779.76
#Sta/Elev= 30
    3987  535.65  4117.9  531.55  4146.3  529.79  4153.8  528.18  4234.6  529.37
  4309.4  528.21  4331.1  525.73    4370  525.16  4444.2  523.59  4505.4  522.96
  4543.5  521.97  4635.4  523.22  4663.9  522.07    4699  524.44  4755.8  523.15
  4795.1   520.3  4880.4  520.05  4959.8  518.62  4969.8  517.48  4977.6  514.36
  4977.9  513.86    4982  514.36  4989.8  517.24  5009.8  520.34  5077.9  520.12
  5251.1  522.16  5376.4   521.8    5444  525.31  5560.5   527.1  5643.3  530.48
#Mann= 9 ,-1 , 0
    3987     .05       0  4234.6     .07       0    4370    .035       0
  4444.2    .063       0  4505.4    .035       0  4880.4     .07       0
  4977.6     .05       0    4982     .07       0  5077.9     .05       0
Bank Sta=4977.6,4982
XS Rating Curve= 0 ,0
Exp/Cntr=0.3,0.1

Type RM Length L Ch R = 1 ,10517   ,210,210,210
BEGIN DESCRIPTION:
A19162
END DESCRIPTION:
XS GIS Cut Line= 4
      2290622.98     13744553.57      2291070.91     13744206.34
      2291515.35     13744195.92      2292041.53     13743894.75
#Sta/Elev= 30
  4179.3  535.56  4207.5  534.63  4244.6  529.83  4265.4  530.67  4335.2     530
    4365  529.22  4385.8  527.35    4394  528.17  4467.1  527.11  4586.8  523.66
  4700.6  522.26  4745.5  520.04  4790.2  520.89  4830.2  518.77  4960.2  518.43
  4970.2  518.12  4980.2  515.47    4988  514.96  4988.3  514.46  4992.5  514.96
  5000.2  516.23  5050.2  519.38  5156.1  518.48  5193.3  518.72  5270.9  521.91
    5323  521.83  5366.2  520.36  5506.8   520.7    5608  522.06  5796.9  528.16
#Mann= 8 ,-1 , 0
  4179.3     .05       0  4335.2    .035       0    4394     .07       0
  4467.1    .035       0    4988    .035       0  4992.5    .035       0
  5156.1     .05       0  5506.8    .035       0
Bank Sta=4988,4992.5
XS Rating Curve= 0 ,0
Exp/Cntr=0.3,0.1

Type RM Length L Ch R = 1 ,10307   ,301,301,301
BEGIN DESCRIPTION:
GUADALUPE TRIBUTARY 15 23.0
END DESCRIPTION:
XS GIS Cut Line= 3
       2290795.3     13744796.98       2291275.5     13744441.17
       2292154.9     13743906.01
#Sta/Elev= 30
  4343.8  534.42  4358.8  534.25  4380.8  536.26  4417.3  533.25  4480.3  531.92
  4582.9  527.27  4753.3  522.82  4780.4  523.12  4838.8  520.18  4859.7  520.28
  4924.4  517.88  4987.9  516.93  5001.1  513.39  5001.4  512.89  5005.6  513.39
  5018.8  515.56  5040.1   514.8  5055.6  517.24  5069.6  517.93    5114  517.44
  5193.2   517.2  5246.8  518.06  5272.1  517.58    5374  517.06  5425.6  522.01
  5462.4  522.33    5536  520.74  5630.9  520.74  5900.2  525.04  5970.9  527.41
#Mann= 7 ,-1 , 0
  4343.8    .035       0  4582.9     .05       0  5001.1     .05       0
  5005.6     .05       0    5114    .035       0  5246.8     .05       0
  5272.1    .035       0
Bank Sta=5001.1,5005.6
XS Rating Curve= 0 ,0
Exp/Cntr=0.3,0.1

Type RM Length L Ch R = 1 ,10006   ,361,361,361
BEGIN DESCRIPTION:
GUADALUPE TRIBUTARY 15 22.0
END DESCRIPTION:
XS GIS Cut Line= 3
      2290876.29     13744930.04      2291431.71     13744692.83
      2292180.46     13743972.99
#Sta/Elev= 30
  4226.3   530.8  4304.2  529.04  4442.4  523.87    4586  520.04  4627.2  520.93
  4714.9   517.2  4740.9  517.81  4901.9  516.54  4972.6  514.74  4986.8  513.76
  4993.7  510.08  5000.9  511.47  5005.5  509.77  5005.9  509.27  5010.1  509.77
  5015.1  510.44    5022  513.87    5029  513.44  5043.1  515.13  5071.4     516
    5128  517.01  5170.4  514.66  5276.7  515.22  5453.4  518.01  5488.7  522.39
  5502.8  522.95  5559.4  521.87  5658.5  521.91  5778.6  523.43  5868.9  525.83
#Mann= 5 ,-1 , 0
  4226.3    .035       0  4304.2     .05       0  4740.9    .035       0
  5005.5    .035       0  5010.1    .035       0
Bank Sta=5005.5,5010.1
XS Rating Curve= 0 ,0
Exp/Cntr=0.3,0.1

Type RM Length L Ch R = 1 ,9645    ,459,459,459
BEGIN DESCRIPTION:
GUADALUPE TRIBUTARY 15 21.0
END DESCRIPTION:
XS GIS Cut Line= 3
      2290875.04     13745074.98        2291875.       13744675.
        2292225.     13744274.99
#Sta/Elev= 30
    3918  526.69  3985.3  525.94    4298  521.26  4314.8   521.1  4348.8  521.86
  4405.3  519.91  4456.5  520.31  4510.3  518.31  4740.5  516.45  4764.8  517.63
    4789  517.21    4824   514.5  4896.7  515.84  4919.6  513.62  4950.6  513.63
  4960.4  508.78  4960.7  508.28    4965  508.78  4973.4  510.25  4980.2  509.72
  4985.6  512.13  4998.3  512.08  5008.7  513.58  5143.5  513.69  5249.8  515.21
  5341.9   518.6  5384.2  518.95  5448.2  519.63  5484.3  523.51  5526.5  524.79
#Mann= 8 ,-1 , 0
    3918     .05       0  3985.3     .07       0    4298    .035       0
  4314.8     .07       0  4405.3    .035       0  4960.4    .035       0
    4965    .035       0  5384.2    .063       0
Bank Sta=4960.4,4965
XS Rating Curve= 0 ,0
Exp/Cntr=0.3,0.1

Type RM Length L Ch R = 1 ,9186    ,419,419,419
BEGIN DESCRIPTION:
GUADALUPE TRIBUTARY 15 20.0
END DESCRIPTION:
XS GIS Cut Line= 3
      2291325.01       13745025.        2292075.       13744975.
      2292475.04     13744724.98
#Sta/Elev= 30
  4252.8  521.46  4302.9  519.22    4343   520.6    4363  518.91  4443.2  518.55
  4463.3  520.61  4483.3   518.7  4503.3   518.2  4573.5   518.7  4663.7  517.93
  4869.5  511.27  4924.3  512.98  4974.4  510.94  4984.4  509.78    4992  505.09
  4992.4  504.59  4996.8  505.09    5002  508.82  5007.4  508.82  5012.1  511.51
    5018  510.71  5027.5  511.37  5033.3  507.64  5039.8  510.19  5048.7  510.86
  5098.4   511.6  5164.2  513.64  5179.6  513.23  5287.5  515.08  5476.2  521.46
#Mann= 5 ,-1 , 0
  4252.8    .035       0  4869.5      .1       0    4992     .05       0
  4996.8      .1       0  5098.4    .035       0
Bank Sta=4992,4996.8
XS Rating Curve= 0 ,0
Exp/Cntr=0.3,0.1

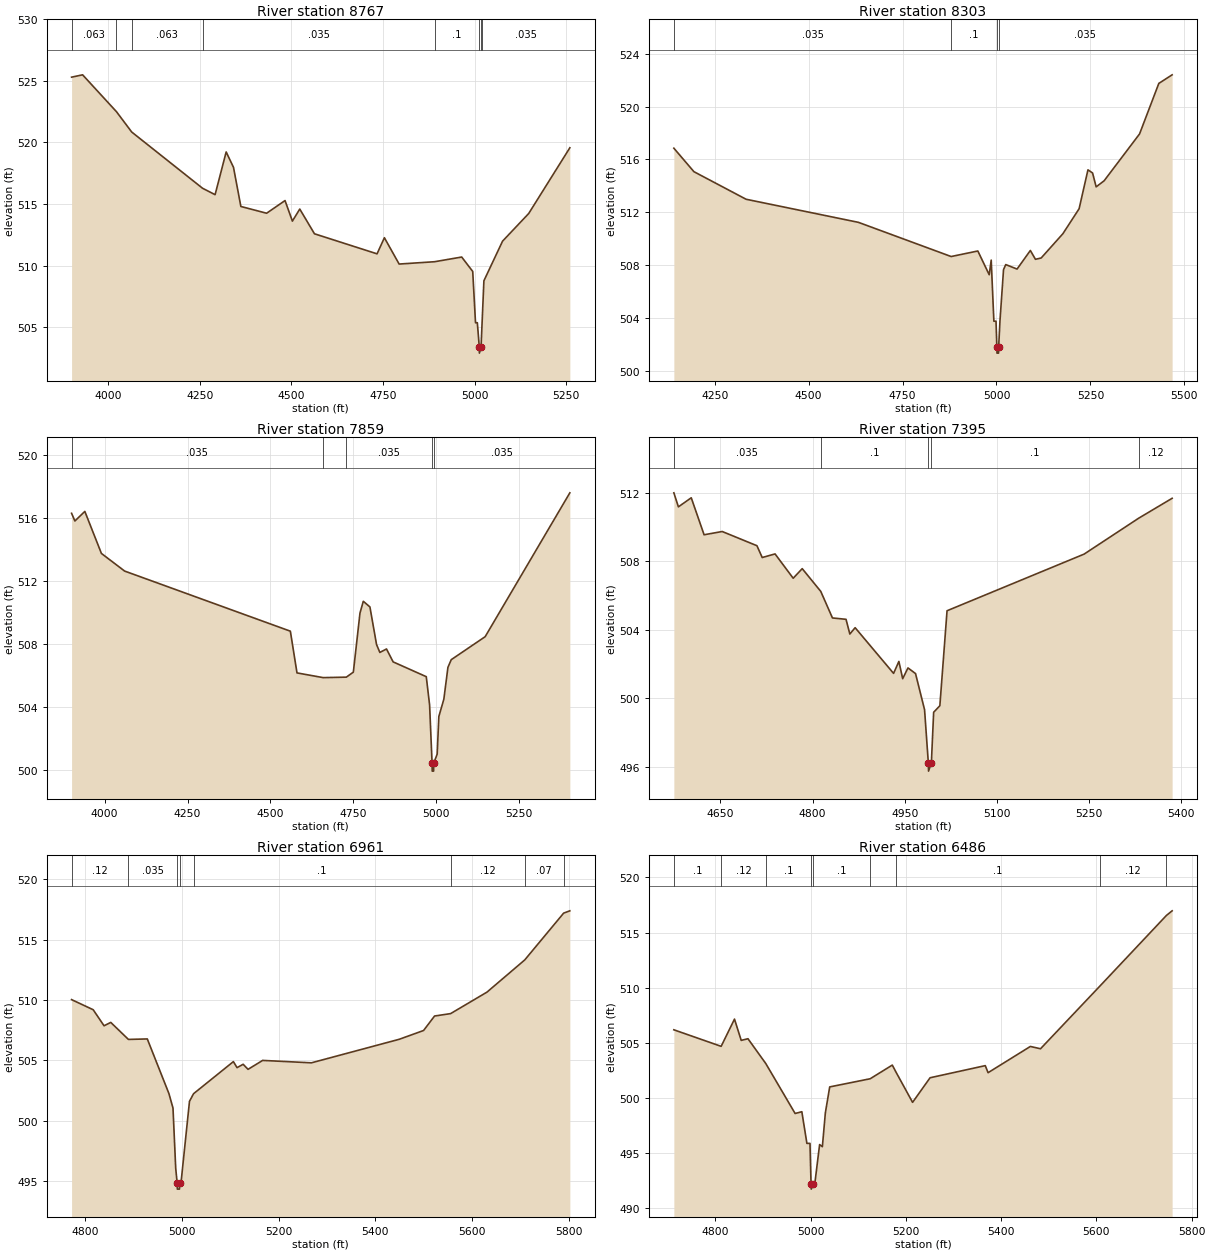
Type RM Length L Ch R = 1 ,8767    ,464,464,464
BEGIN DESCRIPTION:
GUADALUPE TRIBUTARY 15 19.0
END DESCRIPTION:
XS GIS Cut Line= 3
      2291224.97       13745375.        2292325.       13745275.
      2292574.99       13745225.
#Sta/Elev= 30
    3900  525.31  3930.1   525.5  4022.3  522.51  4064.1  520.85  4257.4  516.28
  4291.6  515.76  4321.8  519.23  4341.8  517.98  4361.9   514.8  4432.2  514.25
  4482.4  515.28  4502.5  513.61  4522.6  514.59  4562.7  512.58  4733.5  510.95
  4753.5  512.26  4793.7  510.12  4890.7  510.31  4964.4  510.69  4994.5  509.52
  5002.1  505.35  5007.1  505.35  5012.4  503.38  5012.7  502.88  5017.2  503.38
  5019.8  505.17    5025  508.76  5075.9  511.98  5147.3  514.23  5259.5  519.57
#Mann= 8 ,-1 , 0
    3900    .063       0  4022.3    .035       0  4064.1    .063       0
  4257.4    .035       0  4890.7      .1       0  5012.4     .05       0
  5017.2      .1       0  5019.8    .035       0
Bank Sta=5012.4,5017.2
XS Rating Curve= 0 ,0
Exp/Cntr=0.3,0.1

Type RM Length L Ch R = 1 ,8303    ,444,444,444
BEGIN DESCRIPTION:
GUADALUPE TRIBUTARY 15 18.0
END DESCRIPTION:
XS GIS Cut Line= 3
      2291574.99       13745425.        2292375.       13745725.
      2292774.99     13745475.01
#Sta/Elev= 30
  4141.4  516.85  4194.8  515.07  4333.7  512.98  4632.7  511.23  4879.4  508.64
  4950.4  509.06  4980.7  507.26    4986  508.37  4993.1  503.74  4998.8  503.74
    5001  501.82  5001.4  501.32  5005.5  501.32  5005.9  501.82  5009.4   503.8
  5018.8  507.65  5024.7  508.03  5054.8  507.69  5090.2   509.1  5103.7  508.43
    5119  508.53  5176.8  510.37  5219.9  512.26  5243.5  515.21  5255.8  514.97
  5265.3  513.92  5286.5  514.38  5380.8  517.93  5432.1  521.76  5467.5  522.41
#Mann= 4 ,-1 , 0
  4141.4    .035       0  4879.4      .1       0    5001     .05       0
  5005.9    .035       0
Bank Sta=5001,5005.9
XS Rating Curve= 0 ,0
Exp/Cntr=0.3,0.1

Type RM Length L Ch R = 1 ,7859    ,464,464,464
BEGIN DESCRIPTION:
GUADALUPE TRIBUTARY 15 17.0
END DESCRIPTION:
XS GIS Cut Line= 3
      2291525.02       13746025.        2292625.       13746025.
        2292825.       13745675.
#Sta/Elev= 30
  3900.2  516.32  3910.2  515.83  3940.2  516.44  3990.2  513.77  4060.2  512.65
  4560.2  508.83  4580.2  506.18  4659.2  505.88  4729.1  505.91  4750.2  506.23
  4770.2  509.98  4780.2  510.73  4800.2  510.37  4820.2  507.98  4830.2  507.48
  4850.2   507.7  4870.2  506.88  4970.2  505.94  4980.2  504.15  4987.7  500.44
  4988.1  499.94  4992.3  499.94  4992.6  500.44  5003.1  501.02  5008.1  503.41
  5023.2  504.51  5035.5  506.53  5045.5  507.02  5147.8  508.48  5403.3  517.62
#Mann= 5 ,-1 , 0
  3900.2    .035       0  4659.2      .1       0  4729.1    .035       0
  4987.7    .035       0  4992.6    .035       0
Bank Sta=4987.7,4992.6
XS Rating Curve= 0 ,0
Exp/Cntr=0.3,0.1

Type RM Length L Ch R = 1 ,7395    ,434,434,434
BEGIN DESCRIPTION:
GUADALUPE TRIBUTARY 15 16.0
END DESCRIPTION:
XS GIS Cut Line= 3
      2292524.99     13746625.02        2292775.       13746275.
      2292924.99     13745925.03
#Sta/Elev= 30
  4574.1  511.99  4581.5  511.17  4602.4   511.7  4623.3  509.54  4652.8  509.73
  4709.3   508.9  4717.9  508.21  4738.8  508.42  4768.3     507    4783  507.56
  4813.2  506.23  4832.2  504.68  4854.3   504.6  4860.5  503.74  4869.1  504.11
  4931.7  501.44  4940.3  502.14  4946.5  501.13  4955.1  501.76  4967.4  501.43
  4982.1  499.32  4988.2  496.23  4988.6  495.73  4993.2  496.23  4996.9  499.17
    5007  499.55  5018.7   505.1  5241.8  508.41  5330.7  510.51    5385  511.67
#Mann= 5 ,-1 , 0
  4574.1    .035       0  4813.2      .1       0  4988.2     .05       0
  4993.2      .1       0  5330.7     .12       0
Bank Sta=4988.2,4993.2
XS Rating Curve= 0 ,0
Exp/Cntr=0.3,0.1

Type RM Length L Ch R = 1 ,6961    ,475,475,475
BEGIN DESCRIPTION:
GUADALUPE TRIBUTARY 15 15.0
END DESCRIPTION:
XS GIS Cut Line= 3
      2292875.01     13746774.98        2292975.       13746575.
        2293075.     13745775.01
#Sta/Elev= 30
  4772.3  510.03    4817  509.19  4839.4  507.86  4853.3  508.14  4889.8  506.73
  4928.8  506.77  4973.5  502.24  4981.9  501.04  4987.5  496.06  4990.5  494.82
  4990.9  494.32  4995.2  494.32  4995.6  494.82  4998.4  494.82    5016   501.6
  5024.4  502.23  5106.7  504.89  5114.3  504.39  5126.9  504.67    5137  504.25
  5167.2  504.99    5268  504.79  5449.4  506.74  5499.8  507.47  5522.5  508.67
  5555.7  508.87  5630.8  510.65  5708.9  513.32  5789.3   517.2  5802.1  517.39
#Mann= 8 ,-1 , 0
  4772.3     .12       0  4889.8    .035       0  4990.5    .035       0
  4995.6    .035       0  5024.4      .1       0  5555.7     .12       0
  5708.9     .07       0  5789.3     .12       0
Bank Sta=4990.5,4995.6
XS Rating Curve= 0 ,0
Exp/Cntr=0.3,0.1

Type RM Length L Ch R = 1 ,6486    ,510,510,510
BEGIN DESCRIPTION:
GUADALUPE TRIBUTARY 15 14.0
END DESCRIPTION:
XS GIS Cut Line= 3
        2293175.       13746925.        2293375.       13746725.
      2293775.02     13746074.97
#Sta/Elev= 30
  4712.9  506.18  4812.2  504.68  4840.2  507.15  4854.3  505.22  4868.5  505.37
  4905.9  503.12  4967.5  498.59  4981.6  498.75  4992.2  495.88  4998.7  495.88
  5000.9  492.23  5001.3  491.73    5006  492.23  5009.3   492.4  5018.9  495.77
  5024.7  495.58    5031  498.66  5040.1     501  5125.1  501.74  5171.5  502.98
  5179.3  502.34  5214.1   499.6  5250.8  501.83  5366.7  502.93  5372.6  502.29
  5461.4  504.67  5482.7  504.46  5607.9  510.17    5747  516.55    5759  516.97
#Mann= 9 ,-1 , 0
  4712.9      .1       0  4812.2     .12       0  4905.9      .1       0
  5000.9     .05       0    5006      .1       0  5125.1     .12       0
  5179.3      .1       0  5607.9     .12       0    5747    .035       0
Bank Sta=5000.9,5006
XS Rating Curve= 0 ,0
Exp/Cntr=0.3,0.1

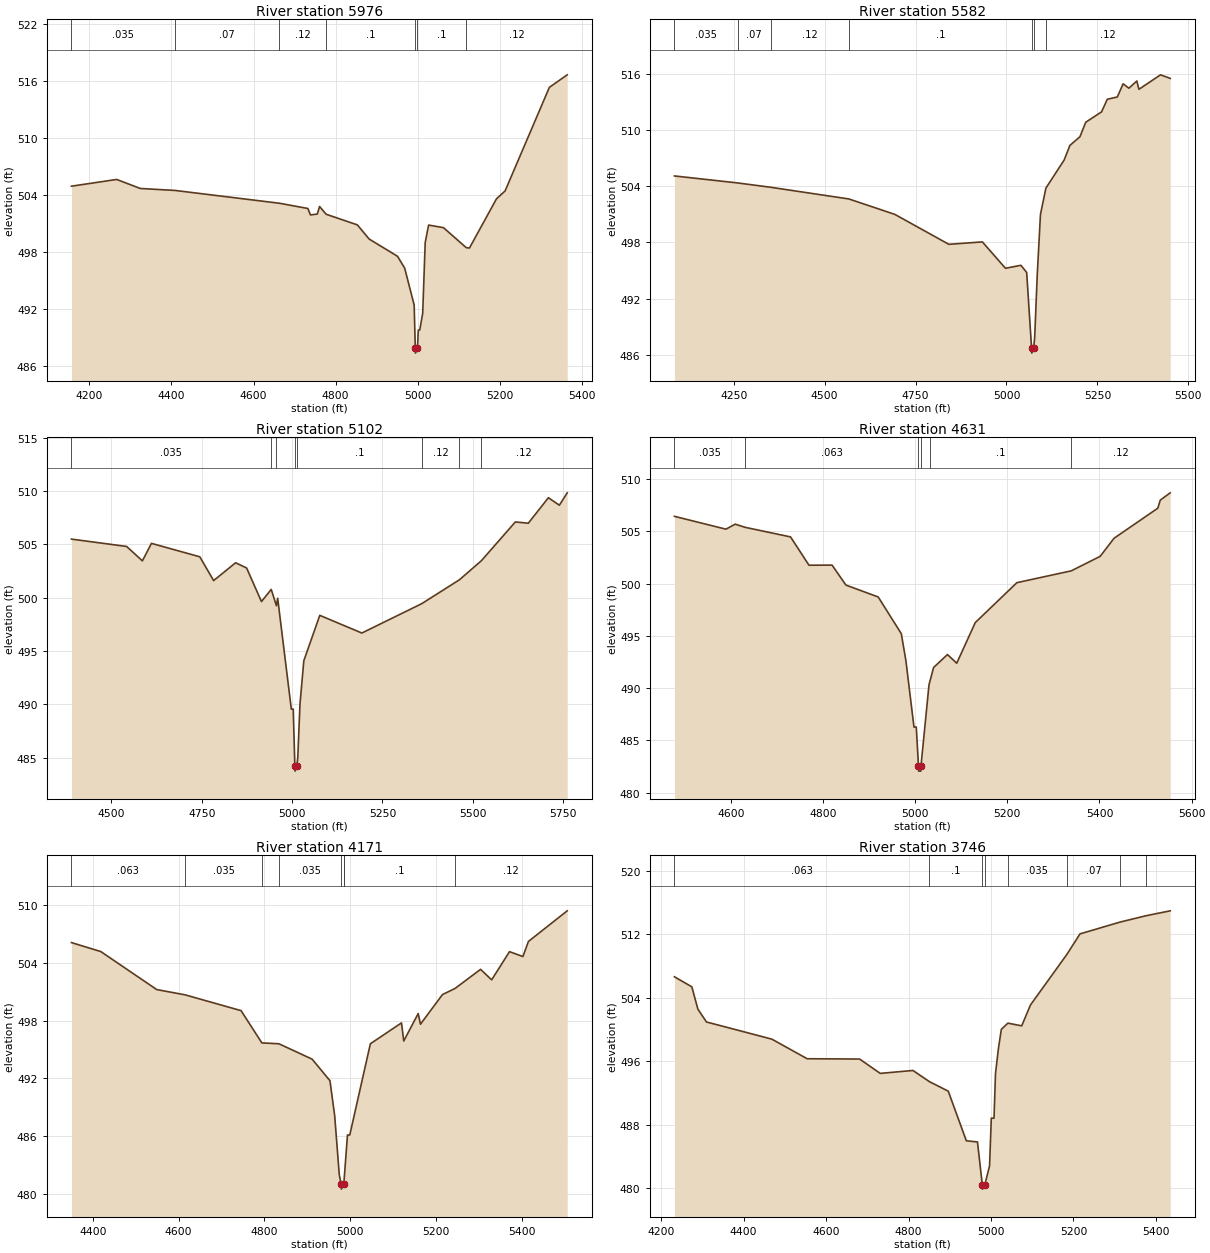
Type RM Length L Ch R = 1 ,5976    ,394,394,394
BEGIN DESCRIPTION:
GUADALUPE TRIBUTARY 15 13.0
END DESCRIPTION:
XS GIS Cut Line= 3
      2293421.84     13747345.44      2293771.87     13746575.95
      2293975.03     13746274.96
#Sta/Elev= 30
  4156.2  504.91  4266.5  505.62  4323.9  504.67  4408.9  504.46  4663.3  503.11
  4732.4  502.56  4738.9  501.88  4755.5  501.97    4761  502.77  4777.1  501.95
  4853.2  500.83  4881.8  499.34    4951  497.52  4968.5  496.27  4991.6  492.38
  4994.4  487.81  4994.8  487.31  4999.7  487.81  5001.6  489.74  5005.2  489.74
  5012.4  491.52  5018.5  498.97  5026.8  500.81    5063  500.54  5118.5  498.43
  5126.4  498.39  5192.3  503.58  5213.3  504.41  5321.2  515.33  5364.7  516.65
#Mann= 7 ,-1 , 0
  4156.2    .035       0  4408.9     .07       0  4663.3     .12       0
  4777.1      .1       0  4994.4     .05       0  4999.7      .1       0
  5118.5     .12       0
Bank Sta=4994.4,4999.7
XS Rating Curve= 0 ,0
Exp/Cntr=0.3,0.1

Type RM Length L Ch R = 1 ,5582    ,480,480,480
BEGIN DESCRIPTION:
GUADALUPE TRIBUTARY 15 12.0
END DESCRIPTION:
XS GIS Cut Line= 3
       2293439.2     13747385.91        2294075.       13746725.
      2294292.54     13746335.87
#Sta/Elev= 30
  4087.2  505.11  4261.4  504.36  4351.7   503.9  4566.8  502.65  4693.1     501
  4841.6   497.8  4933.7  498.06  4997.2  495.24  5039.7  495.56  5055.5  494.79
    5069  486.67  5069.4  486.17  5074.3  486.67  5077.4  487.76  5084.5   494.5
  5093.4     501  5108.3  503.81  5158.5  506.81  5174.4  508.38  5201.9   509.3
  5217.8  510.85  5261.3  511.96  5277.2  513.31  5304.7  513.55  5320.6  514.96
  5336.5  514.49  5358.3  515.26    5364  514.37  5423.4  515.92  5450.1  515.54
#Mann= 7 ,-1 , 0
  4087.2    .035       0  4261.4     .07       0  4351.7     .12       0
  4566.8      .1       0    5069     .05       0  5074.3      .1       0
  5108.3     .12       0
Bank Sta=5069,5074.3
XS Rating Curve= 0 ,0
Exp/Cntr=0.3,0.1

Type RM Length L Ch R = 1 ,5102    ,471,471,471
BEGIN DESCRIPTION:
GUADALUPE TRIBUTARY 15 11.0
END DESCRIPTION:
XS GIS Cut Line= 3
      2293913.61     13747698.31        2294125.       13747125.
      2294388.01     13746411.05
#Sta/Elev= 30
  4389.5  505.49  4542.2   504.8  4585.8  503.45  4610.9  505.09  4744.7  503.83
  4782.9   501.6  4843.8  503.27  4874.2  502.78  4915.3  499.63  4942.3  500.77
  4956.8  499.24  4960.2  499.94  4997.9  489.55  5003.2  489.55  5007.7  484.23
  5008.2  483.73  5013.1  484.23  5015.8  484.98  5021.9  490.03  5032.5  494.08
  5076.7  498.34  5193.1  496.68  5359.1  499.44  5462.9  501.67  5523.8  503.46
  5617.9   507.1  5653.7  506.98  5709.3  509.37  5739.7  508.67  5761.4  509.83
#Mann= 8 ,-1 , 0
  4389.5    .035       0  4942.3     .12       0  4956.8      .1       0
  5007.7     .05       0  5013.1      .1       0  5359.1     .12       0
  5462.9      .1       0  5523.8     .12       0
Bank Sta=5007.7,5013.1
XS Rating Curve= 0 ,0
Exp/Cntr=0.3,0.1

Type RM Length L Ch R = 1 ,4631    ,460,460,460
BEGIN DESCRIPTION:
GUADALUPE TRIBUTARY 15 10.0
END DESCRIPTION:
XS GIS Cut Line= 3
      2294500.82     13747446.62        2294525.       13746925.
      2294477.68     13746373.51
#Sta/Elev= 30
  4477.8  506.45  4589.5  505.22  4609.6   505.7    4631   505.4  4729.7  504.48
  4769.7  501.77  4819.8  501.78  4849.8  499.87  4919.9  498.73    4970  495.22
    4980  492.63  4997.5  486.28  5002.5  486.28  5007.3  482.56  5007.7  482.06
  5012.3  482.06  5012.7  482.56  5030.1  490.32  5032.3  490.69  5040.1  491.98
  5070.2  493.22  5090.3  492.39  5130.5  496.28  5220.8   500.1  5338.7  501.23
  5401.5  502.62  5431.6  504.35  5526.6  507.23  5531.9     508  5553.5   508.7
#Mann= 6 ,-1 , 0
  4477.8    .035       0    4631    .063       0  5007.3     .05       0
  5012.7    .063       0  5032.3      .1       0  5338.7     .12       0
Bank Sta=5007.3,5012.7
XS Rating Curve= 0 ,0
Exp/Cntr=0.3,0.1

Type RM Length L Ch R = 1 ,4171    ,425,425,425
BEGIN DESCRIPTION:
GUADALUPE TRIBUTARY 15 9.0
END DESCRIPTION:
XS GIS Cut Line= 3
       2294619.4     13747417.75        2294875.       13746825.
      2295015.72     13746335.85
#Sta/Elev= 30
  4350.5  506.11  4418.8  505.18  4549.1  501.23  4615.4  500.68  4745.5  499.04
  4793.9  495.69  4833.6   495.6    4911     494  4952.5  491.76  4963.5  488.13
  4974.2  481.98  4978.7     481  4979.1   480.5  4984.4     481  4985.2  481.32
  4993.3  486.12  4998.6  486.12  5046.6   495.6  5119.1  497.77  5124.3  495.89
    5158  498.74  5163.2  497.63  5214.5  500.71  5243.9  501.35  5303.2  503.33
    5329  502.24  5370.6  505.17  5401.8  504.66  5414.7  506.23    5505  509.41
#Mann= 8 ,-1 , 0
  4350.5    .063       0  4615.4    .035       0  4793.9    .063       0
  4833.6    .035       0  4978.7     .05       0  4984.4    .035       0
  4985.2      .1       0  5243.9     .12       0
Bank Sta=4978.7,4984.4
XS Rating Curve= 0 ,0
Exp/Cntr=0.3,0.1

Type RM Length L Ch R = 1 ,3746    ,354,354,354
BEGIN DESCRIPTION:
GUADALUPE TRIBUTARY 15 8.0
END DESCRIPTION:
XS GIS Cut Line= 3
      2294604.96     13747484.24        2295225.       13747025.
      2295530.29      13746720.9
#Sta/Elev= 30
  4232.2  506.64  4274.4  505.37    4289  502.56  4309.8  500.94  4468.5  498.77
  4554.1   496.3  4681.3  496.26  4731.4  494.45  4810.7  494.82  4850.6  493.41
  4896.3  492.21  4940.2  485.95  4967.2   485.8    4979  480.35  4979.4  479.85
  4984.8  480.35  4996.5  482.79  5000.7   488.8  5007.3   488.8  5010.9  494.42
  5017.9  497.55    5025     500  5040.9  500.79  5074.5  500.45  5095.7  503.08
  5183.9  509.45  5215.9  512.05    5313  513.54  5375.9  514.34  5434.7  514.96
#Mann= 8 ,-1 , 0
  4232.2    .063       0  4850.6      .1       0    4979     .05       0
  4984.8      .1       0  5040.9    .035       0  5183.9     .07       0
    5313    .035       0  5375.9     .07       0
Bank Sta=4979,4984.8
XS Rating Curve= 0 ,0
Exp/Cntr=0.3,0.1

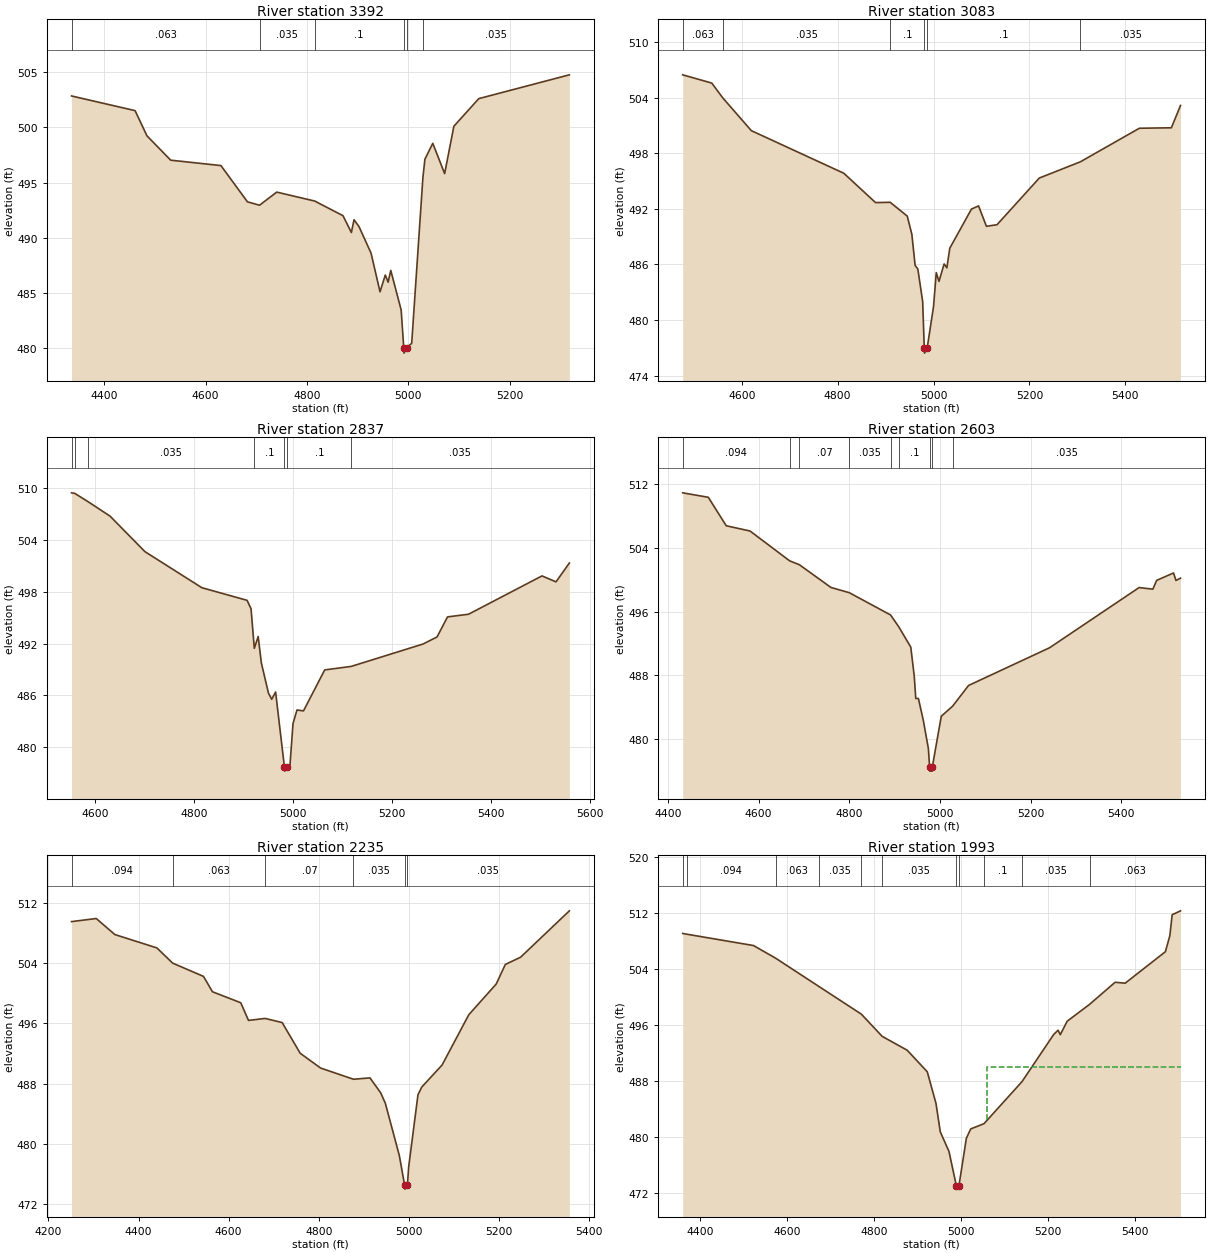
Type RM Length L Ch R = 1 ,3392    ,309,309,309
BEGIN DESCRIPTION:
A19161
END DESCRIPTION:
XS GIS Cut Line= 3
      2294654.17     13747579.69      2295151.67     13747362.75
        2295574.     13747241.26
#Sta/Elev= 30
  4335.4  502.86  4460.7  501.53  4484.2  499.24    4531  497.03  4630.1  496.54
  4682.4  493.25  4706.3  492.94  4740.2  494.13  4815.1  493.32  4870.9  491.99
  4887.5  490.46  4892.7  491.62  4902.4  491.01  4926.3  488.59    4944  485.08
  4954.4   486.6    4960  485.95  4965.2  487.02  4985.7  483.43  4990.8  480.01
  4991.3  479.51  4996.6  480.01  5006.5   480.4  5028.6  495.44  5032.6  497.12
  5048.1  498.56  5071.5  495.81  5089.7  500.11  5138.9  502.62  5317.6  504.78
#Mann= 6 ,-1 , 0
  4335.4    .063       0  4706.3    .035       0  4815.1      .1       0
  4990.8     .05       0  4996.6      .1       0  5028.6    .035       0
Bank Sta=4990.8,4996.6
XS Rating Curve= 0 ,0
Exp/Cntr=0.3,0.1

Type RM Length L Ch R = 1 ,3083    ,246,246,246
BEGIN DESCRIPTION:
A19160
END DESCRIPTION:
XS GIS Cut Line= 2
      2294711.96     13747845.84      2295630.94     13747363.23
#Sta/Elev= 30
    4477  506.48  4537.6  505.59  4560.7  503.98  4620.1  500.45  4812.9  495.85
  4879.1  492.68  4909.7  492.71  4945.2  491.22  4954.8  489.25  4961.6   485.9
  4967.3   485.5  4977.4  481.97  4980.7  476.92  4981.2  476.42  4986.6  476.92
    5000  481.44  5005.7  485.11  5011.4  484.17  5022.1  486.05  5027.8  485.63
  5033.9  487.75  5079.1  491.98  5093.9  492.32  5110.3  490.12  5132.4  490.29
  5220.5  495.33  5306.4  497.09  5429.2  500.71  5495.9  500.76    5515  503.17
#Mann= 6 ,-1 , 0
    4477    .063       0  4560.7    .035       0  4909.7      .1       0
  4980.7     .05       0  4986.6      .1       0  5306.4    .035       0
Bank Sta=4980.7,4986.6
XS Rating Curve= 0 ,0
Exp/Cntr=0.3,0.1

Type RM Length L Ch R = 1 ,2837    ,234,234,234
BEGIN DESCRIPTION:
A19159
END DESCRIPTION:
XS GIS Cut Line= 3
      2294879.77     13748109.05       2295336.8     13747741.69
      2295634.75     13747446.63
#Sta/Elev= 30
  4552.9  509.46  4559.3   509.4  4586.9  508.41  4630.7  506.76  4701.1  502.65
  4816.2  498.47  4907.5  497.01  4915.5  496.03  4922.1  491.45  4929.9  492.82
  4936.3  489.77  4950.7  486.26  4957.3  485.55  4965.1   486.4  4982.9  477.73
  4983.4  477.23  4988.8  477.73  4993.9  477.74  5000.3  482.74  5008.3  484.31
  5021.5  484.21  5064.3  488.95    5118  489.36    5263  491.95  5291.3  492.77
  5312.4  495.09  5354.9   495.4  5503.3  499.84  5531.6  499.15  5558.6  501.33
#Mann= 7 ,-1 , 0
  4552.9    .063       0  4559.3    .094       0  4586.9    .035       0
  4922.1      .1       0  4982.9     .05       0  4988.8      .1       0
    5118    .035       0
Bank Sta=4982.9,4988.8
XS Rating Curve= 0 ,0
Exp/Cntr=0.3,0.1

Type RM Length L Ch R = 1 ,2603    ,368,368,368
BEGIN DESCRIPTION:
A19158
END DESCRIPTION:
XS GIS Cut Line= 3
      2294937.64     13748192.93      2295406.22     13747978.89
      2295654.97     13747452.46
#Sta/Elev= 30
  4432.9   510.9  4489.3  510.34  4528.9  506.77  4581.4  506.11  4668.7  502.37
  4690.2  501.88  4759.8  499.03    4800  498.38  4891.2  495.58  4909.7  494.05
  4935.7  491.55  4943.3  487.91  4946.7  485.11  4952.5  485.11  4963.4  482.34
  4974.5  478.82  4977.2   476.5  4977.7     476  4982.7     476  4983.1   476.5
  5002.9  482.88    5028  484.15    5063  486.74  5241.6  491.47    5439  499.02
  5469.3  498.82  5477.7  499.92  5514.8  500.85  5520.3  499.91  5530.3   500.2
#Mann= 9 ,-1 , 0
  4432.9    .094       0  4668.7    .035       0  4690.2     .07       0
    4800    .035       0  4891.2     .07       0  4909.7      .1       0
  4977.2     .05       0  4983.1      .1       0    5028    .035       0
Bank Sta=4977.2,4983.1
XS Rating Curve= 0 ,0
Exp/Cntr=0.3,0.1

Type RM Length L Ch R = 1 ,2235    ,242,242,242
BEGIN DESCRIPTION:
A19157
END DESCRIPTION:
XS GIS Cut Line= 3
       2294952.1     13748242.12      2295750.45     13748028.06
      2296025.23     13747981.79
#Sta/Elev= 30
  4251.3  509.49  4306.1   509.9  4347.5  507.77  4440.7     506  4475.7  503.98
  4544.2  502.22  4564.1  500.18    4627  498.72  4644.1  496.38  4681.2  496.64
  4718.9  496.09  4758.9  492.02  4804.1  490.06  4877.2  488.57  4913.8  488.75
  4937.6  486.77    4948  485.37    4979  478.44  4990.8  474.49  4991.3  473.99
  4996.9  474.49  4999.7  476.93  5020.4  486.51  5028.7  487.53  5073.9  490.46
  5133.2  497.13    5194   501.2  5214.3   503.8  5248.3  504.77  5356.5  510.92
#Mann= 6 ,-1 , 0
  4251.3    .094       0  4475.7    .063       0  4681.2     .07       0
  4877.2    .035       0  4990.8    .035       0  4996.9    .035       0
Bank Sta=4990.8,4996.9
XS Rating Curve= 0 ,0
Exp/Cntr=0.3,0.1

Type RM Length L Ch R = 1 ,1993    ,244,244,244
BEGIN DESCRIPTION:
A19156
END DESCRIPTION:
XS GIS Cut Line= 3
      2294952.08     13748271.05      2295762.02     13748253.69
      2296088.89     13748175.59
#Sta/Elev= 30
  4359.6  509.09  4369.1  508.98  4522.6  507.36  4573.9  505.54  4672.5  501.54
    4771  497.55  4818.9  494.38  4876.5   492.4  4922.7  489.32  4942.7  484.82
  4952.7  480.73  4972.7  477.94  4989.6  473.05  4990.1  472.55  4995.7  473.05
  5012.7  479.82  5022.7  481.15  5053.3   481.9  5140.8  487.91  5213.9  494.66
  5223.9  495.26    5229  494.62  5244.8  496.54  5296.3  498.95  5355.2  502.11
  5378.4  501.98    5471  506.48  5481.2  508.77  5486.6  511.76  5505.8  512.32
#Mann= 11 ,-1 , 0
  4359.6    .063       0  4369.1    .094       0  4573.9    .063       0
  4672.5    .035       0    4771     .07       0  4818.9    .035       0
  4989.6    .035       0  4995.7    .035       0  5053.3      .1       0
  5140.8    .035       0  5296.3    .063       0
#XS Ineff= 2 , 0
       0                    5060       0     490
Permanent Ineff=
       F       F
Bank Sta=4989.6,4995.7
XS Rating Curve= 0 ,0
Exp/Cntr=0.3,0.1