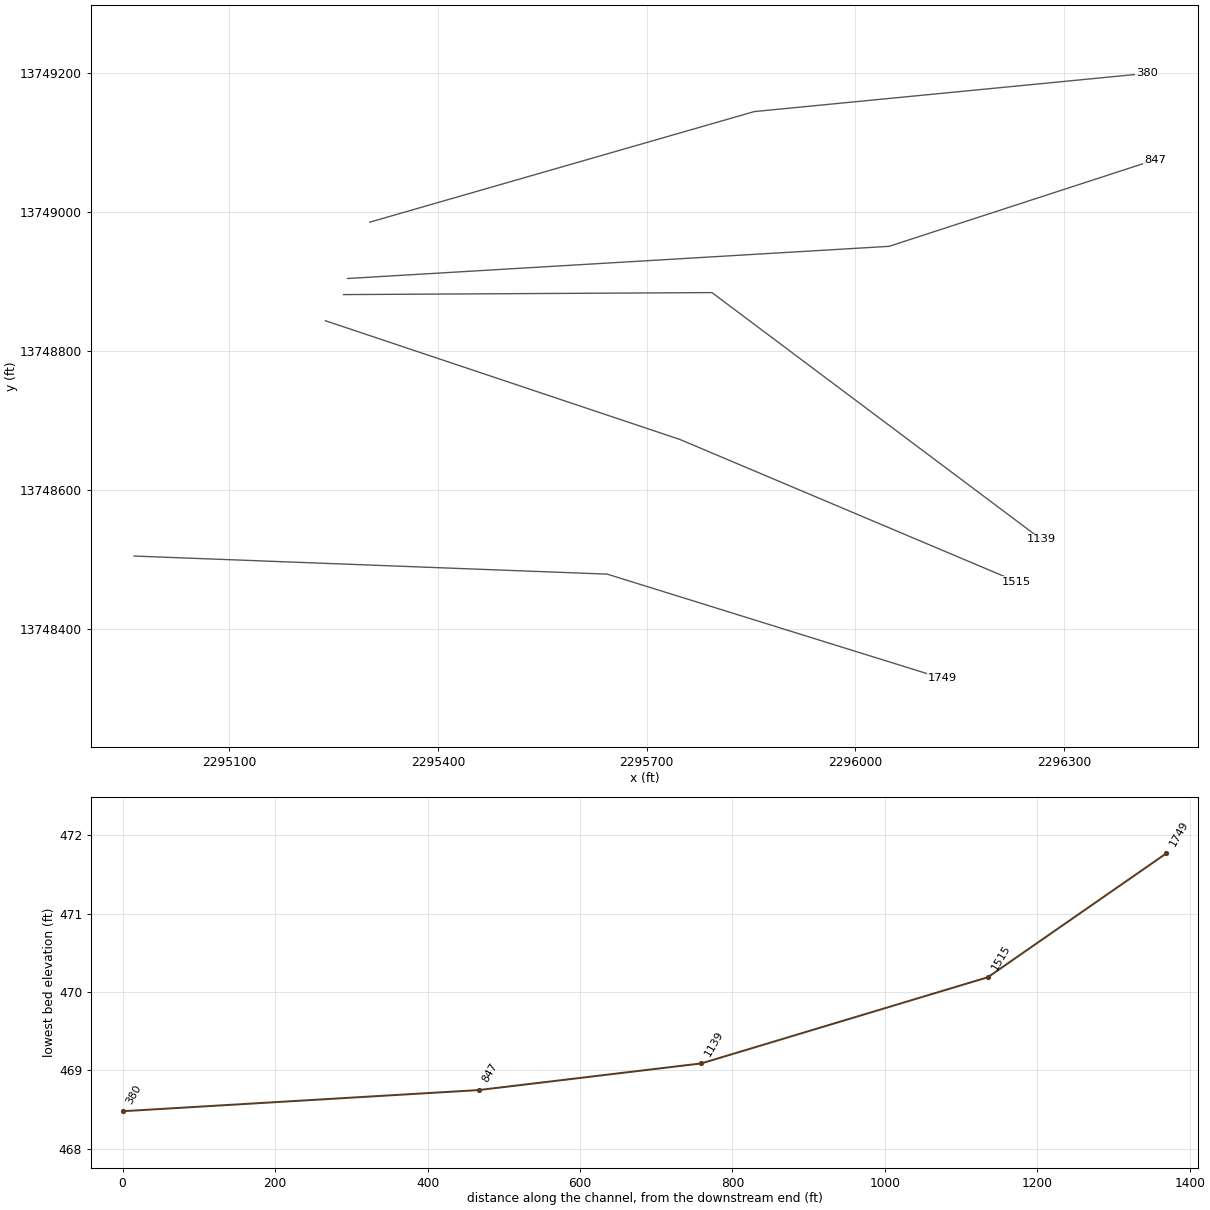
HEC-RAS study GUADALUPE TRIBUTARY 15.prj: GUADALUPE TRIBUTARY 15 Base Level Engineering

--- GUADALUPE TRIBUTARY 15.g01 (geometry) --- (continued)

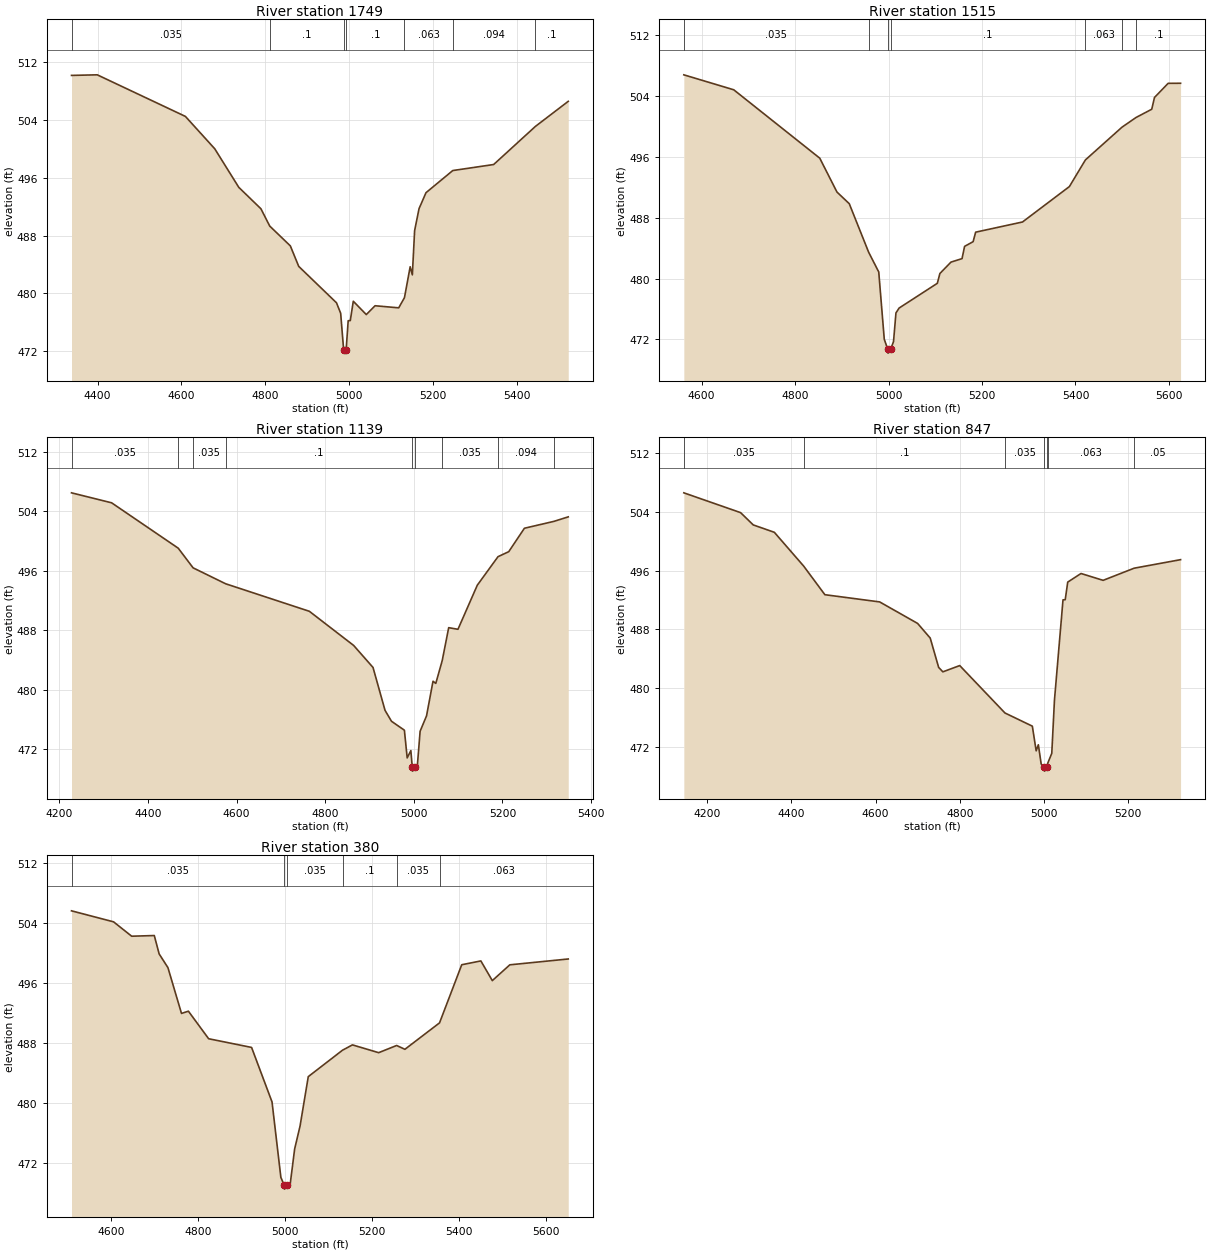
Type RM Length L Ch R = 1 ,1749    ,234,234,234
BEGIN DESCRIPTION:
A19155
END DESCRIPTION:
XS GIS Cut Line= 3
      2294963.63     13748505.35      2295643.42     13748479.32
      2296124.74     13748329.45
#Sta/Elev= 30
  4337.8   510.1  4399.2  510.18  4609.4  504.44  4679.4  499.97  4736.7  494.65
  4789.5  491.69  4810.4  489.31  4859.6  486.57  4879.6  483.74  4969.6  478.72
  4979.6  477.27  4986.6  472.27  4987.1  471.77  4992.7  472.27  4997.5  476.24
  5002.5  476.26  5009.7  478.93  5040.7  477.09  5061.6  478.31    5118  478.02
  5131.7  479.43  5145.3  483.69  5150.5  482.57  5155.9  488.67  5166.4   491.7
    5183  493.91  5246.9  496.97  5344.4   497.8  5443.9  503.06  5522.2  506.52
#Mann= 7 ,-1 , 0
  4337.8    .035       0  4810.4      .1       0  4986.6     .05       0
  4992.7      .1       0  5131.7    .063       0  5246.9    .094       0
  5443.9      .1       0
Bank Sta=4986.6,4992.7
XS Rating Curve= 0 ,0
Exp/Cntr=0.3,0.1

Type RM Length L Ch R = 1 ,1515    ,376,376,376
BEGIN DESCRIPTION:
A19154
END DESCRIPTION:
XS GIS Cut Line= 3
       2295238.4     13748843.81      2295747.56     13748673.13
      2296231.79     13748468.48
#Sta/Elev= 30
  4562.1  506.82  4668.9  504.85  4852.9  495.85  4889.7  491.39    4916  489.86
  4957.5  483.47  4979.1  480.87  4990.9  472.02  4998.4  470.69  4998.9  470.19
  5004.5  470.69  5010.7  471.71  5015.9  475.48  5022.6  476.12  5104.4  479.38
  5109.9  480.67  5133.6  482.17  5157.3  482.63  5162.7  484.24    5181  484.86
  5186.4  486.11  5286.6  487.45  5386.9  492.11  5421.2  495.62  5499.5  499.93
  5529.4   501.2  5563.1  502.29    5569  503.84  5598.2   505.7  5624.8  505.71
#Mann= 7 ,-1 , 0
  4562.1    .035       0  4957.5      .1       0  4998.4     .05       0
  5004.5      .1       0  5421.2    .063       0  5499.5    .094       0
  5529.4      .1       0
Bank Sta=4998.4,5004.5
XS Rating Curve= 0 ,0
Exp/Cntr=0.3,0.1

Type RM Length L Ch R = 1 ,1139    ,292,292,292
BEGIN DESCRIPTION:
A19153
END DESCRIPTION:
XS GIS Cut Line= 3
      2295264.51      13748881.4      2295793.84     13748884.29
      2296267.25     13748529.23
#Sta/Elev= 30
  4227.4  506.49  4317.9  505.15  4468.3  499.05  4501.8  496.41  4575.2  494.27
  4764.2  490.57  4864.2  485.98  4907.9  483.02    4935  477.26  4949.6  475.79
  4978.7  474.59    4985  470.87  4993.3  471.85  4996.5  469.59    4997  469.09
  5002.6  469.59  5007.9  469.78  5014.2  474.45  5028.7  476.52  5043.3  481.17
  5049.6  480.88  5064.1  483.95  5078.7  488.37  5099.6  488.15  5143.3  494.08
    5190  497.91  5214.2  498.58  5249.6  501.73  5315.9  502.65  5348.5  503.26
#Mann= 9 ,-1 , 0
  4227.4    .035       0  4468.3      .1       0  4501.8    .035       0
  4575.2      .1       0  4996.5     .05       0  5002.6      .1       0
  5064.1    .035       0    5190    .094       0  5315.9    .035       0
Bank Sta=4996.5,5002.6
XS Rating Curve= 0 ,0
Exp/Cntr=0.3,0.1

Type RM Length L Ch R = 1 ,847     ,467,467,467
BEGIN DESCRIPTION:
A19152
END DESCRIPTION:
XS GIS Cut Line= 3
       2295270.3     13748904.54      2296048.39     13748950.82
      2296430.08     13749075.16
#Sta/Elev= 30
  4144.1  506.56    4279  503.87  4309.1   502.2  4359.2   501.2  4428.8  496.62
  4479.4  492.72  4609.6  491.74  4699.8  488.82  4729.8  486.83  4749.9  482.84
  4759.9  482.24    4800  483.09  4907.5  476.65  4972.6  474.86  4981.7  471.51
  4986.9  472.33  4993.6  469.72    5001  469.25  5001.5  468.75  5007.2  469.25
  5009.4  469.85  5018.8  471.17  5025.2   478.4  5045.5  492.02  5050.8  492.04
  5056.7  494.43  5088.3   495.6  5140.9  494.67  5214.6  496.32    5325  497.48
#Mann= 7 ,-1 , 0
  4144.1    .035       0  4428.8      .1       0  4907.5    .035       0
    5001    .035       0  5007.2    .035       0  5009.4    .063       0
  5214.6     .05       0
Bank Sta=5001,5007.2
XS Rating Curve= 0 ,0
Exp/Cntr=0.3,0.1

Type RM Length L Ch R = 1 ,380     ,0,0,0
BEGIN DESCRIPTION:
A19151
END DESCRIPTION:
XS GIS Cut Line= 3
       2295302.1     13748985.54      2295854.58     13749144.63
      2296418.68     13749199.59
#Sta/Elev= 30
  4508.8  505.64  4605.5  504.17  4647.1  502.25  4699.1  502.34  4710.2  499.89
  4730.4  498.06  4761.6  491.94  4777.5  492.24    4824  488.56  4922.7   487.4
  4969.7  480.12    4990  470.05  4997.8  468.98  4998.3  468.48    5004  468.98
  5011.3  469.09  5021.7  473.85  5034.1   476.9    5053   483.5  5131.7  487.03
  5154.5  487.74  5214.8   486.7  5256.1  487.66  5275.1  487.15  5354.7  490.68
  5405.7  498.44  5449.7  498.95    5476  496.32  5516.2  498.43  5650.5  499.21
#Mann= 6 ,-1 , 0
  4508.8    .035       0  4997.8    .035       0    5004    .035       0
  5131.7      .1       0  5256.1    .035       0  5354.7    .063       0
Bank Sta=4997.8,5004
XS Rating Curve= 0 ,0
Exp/Cntr=0.3,0.1

Chan Stop Cuts=-1
Use User Specified Reach Order=0
Composite Channel Slope=5