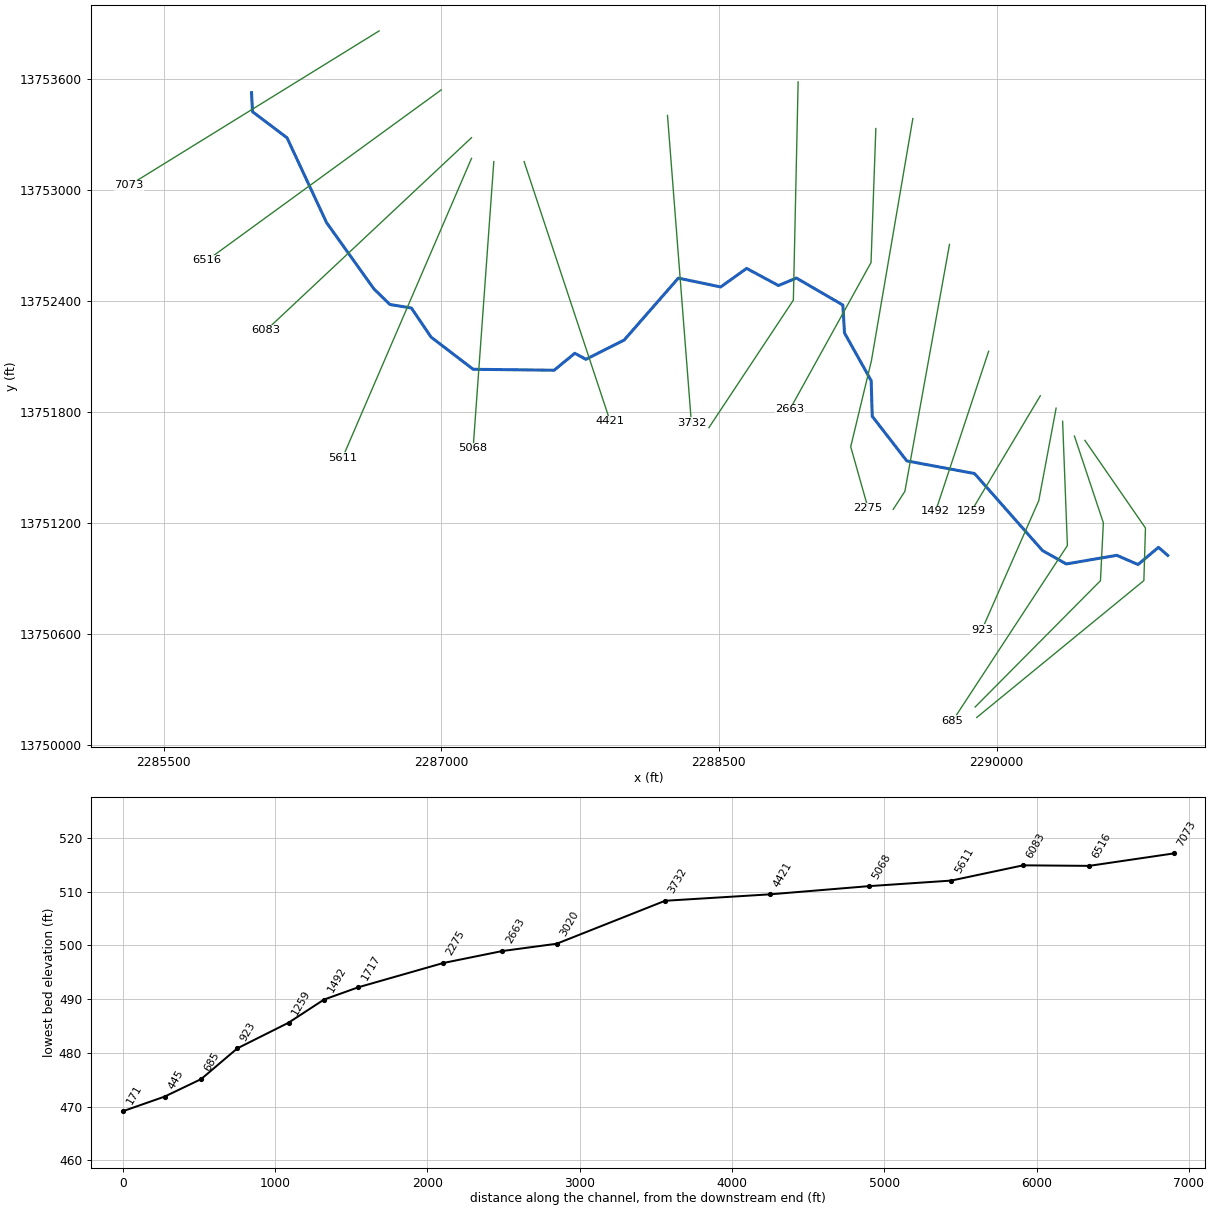
--- GUADALUPE TRIBUTARY 16 2.prj (project) ---

Proj Title=GUADALUPE TRIBUTARY 16 2 Base Level Engineering
Current Plan=p01
Default Exp/Contr=0.3,0.1
English Units
Geom File=g01
Flow File=f01
Plan File=p01
BEGIN DESCRIPTION:
GUADALUPE TRIBUTARY 16 2
END DESCRIPTION:

--- GUADALUPE TRIBUTARY 16 2.p01 (plan) ---

Plan Title=Multiple Run
Short Identifier=Multiple
Geom File=g01
Flow File=f01
Subcritical Flow
K Sum by GR= 0
Std Step Tol= 0.01
Critical Tol= 0.01
Num of Std Step Trials= 20
Max Error Tol= 0.3
Flow Tol Ratio= 0.001
Split Flow NTrial= 30
Split Flow Tol= 0.02
Split Flow Ratio= 0.02
Log Output Level= 0
Friction Slope Method= 1
Unsteady Friction Slope Method= 2
Unsteady Bridges Friction Slope Method= 1
Parabolic Critical Depth
Global Vel Dist=  1 , 1 , 1
Global Log Level= 0
CheckData=True
Encroach Param= -1, 0, 0, 0
BEGIN DESCRIPTION:
Multiple Run
END DESCRIPTION:

--- GUADALUPE TRIBUTARY 16 2.f01 (steady flow) ---

Flow Title=Multiple
Number of Profiles=7
Profile Names=10-year,25-year,50-year,1pct_min,100-year,1pct_plu,500-year
River Rch & RM= GUADALUPE TRIBUT,Reach-1,7073
     510     795    1042     660    1316    2626    2080
River Rch & RM= GUADALUPE TRIBUT,Reach-1,3732
     712    1138    1516     976    1947    3885    3185
River Rch & RM= GUADALUPE TRIBUT,Reach-1,923
     792    1275    1707    1104    2204    4397    3640
Boundary for River Rch & Prof#=GUADALUPE TRIBUT,Reach-1,1
Up Type=0
Dn Type=3
Dn Slope=0.005
Boundary for River Rch & Prof#=GUADALUPE TRIBUT,Reach-1,2
Up Type=0
Dn Type=3
Dn Slope=0.005
Boundary for River Rch & Prof#=GUADALUPE TRIBUT,Reach-1,3
Up Type=0
Dn Type=3
Dn Slope=0.005
Boundary for River Rch & Prof#=GUADALUPE TRIBUT,Reach-1,4
Up Type=0
Dn Type=3
Dn Slope=0.005
Boundary for River Rch & Prof#=GUADALUPE TRIBUT,Reach-1,5
Up Type=0
Dn Type=3
Dn Slope=0.005
Boundary for River Rch & Prof#=GUADALUPE TRIBUT,Reach-1,6
Up Type=0
Dn Type=3
Dn Slope=0.005
Boundary for River Rch & Prof#=GUADALUPE TRIBUT,Reach-1,7
Up Type=0
Dn Type=3
Dn Slope=0.005

--- GUADALUPE TRIBUTARY 16 2.g01 (geometry) ---

Geom Title=Existing Conditions

River Reach=GUADALUPE TRIBUT,Reach-1
Reach XY= 30
      2285975.00     13753525.00      2285980.23     13753422.22
      2286166.85     13753281.07      2286380.52     13752822.57
      2286635.77     13752465.30      2286722.56     13752380.52
      2286838.65     13752361.74      2286944.77     13752204.58
      2287172.55     13752030.46      2287609.84     13752025.39
      2287721.67     13752116.98      2287781.66     13752084.32
      2287988.30     13752188.40      2288280.89     13752523.04
      2288509.78     13752475.25      2288649.97     13752575.50
      2288821.69     13752483.07      2288918.95     13752523.33
      2289169.65     13752377.73      2289178.76     13752226.56
      2289322.76     13751969.07      2289328.55     13751776.47
      2289515.18     13751535.47      2289881.19     13751467.18
      2290248.18     13751051.29      2290376.55     13750978.75
      2290650.00     13751025.39      2290764.38     13750975.61
      2290875.01     13751068.41      2290925.00     13751025.00

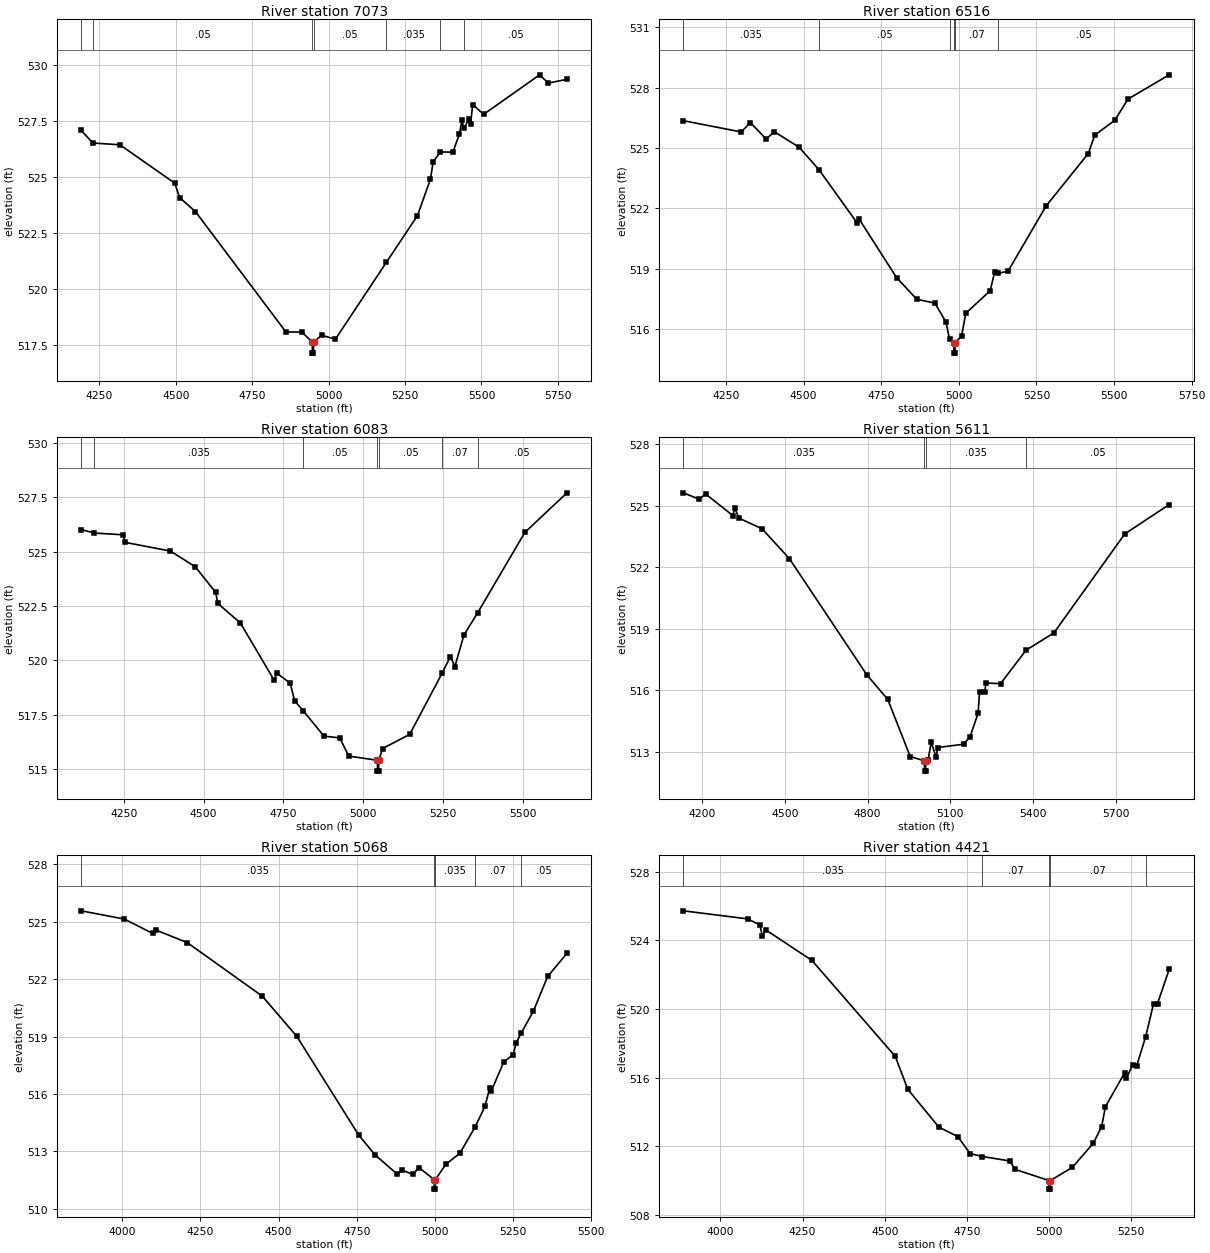
Type RM Length L Ch R = 1,7073,557,557,557
BEGIN DESCRIPTION:
GUADALUPE TRIBUTARY 16 210457
END DESCRIPTION:
XS GIS Cut Line= 2
      2286664.37     13753858.59      2285312.91     13753023.61
#Sta/Elev= 30
  4191.0  527.09  4229.3  526.53  4317.6  526.45  4497.2  524.73  4512.6  524.09
  4564.7  523.46  4860.3  518.08  4912.2  518.07  4946.9  517.63  4947.1  517.13
  4950.6  517.13  4950.9  517.63  4977.8  517.93  5022.2  517.75  5189.4  521.20
  5290.6  523.28  5333.1  524.91  5342.2  525.70  5366.0  526.13  5406.4  526.12
  5427.7  526.92  5436.3  527.55  5442.5  527.18  5458.5  527.59  5464.3  527.40
  5471.5  528.25  5506.9  527.81  5690.2  529.58  5718.4  529.21  5779.6  529.38
#Mann=7,-1,0
  4191.0   0.035       0  4229.3    0.05       0  4946.9    0.05       0
  4950.9    0.05       0  5189.4   0.035       0  5366.0    0.07       0
  5442.5    0.05       0
Bank Sta=4946.9,4950.9
Exp/Cntr=0.3,0.1

Type RM Length L Ch R = 1,6516,433,433,433
BEGIN DESCRIPTION:
GUADALUPE TRIBUTARY 16 210456
END DESCRIPTION:
XS GIS Cut Line= 2
      2287000.07     13753540.10      2285735.33     13752619.51
#Sta/Elev= 30
  4113.4  526.36  4299.7  525.80  4329.1  526.27  4379.3  525.45  4406.4  525.81
  4486.0  525.04  4550.6  523.91  4672.2  521.29  4678.4  521.49  4799.9  518.56
  4864.6  517.49  4923.3  517.29  4958.9  516.35  4970.3  515.50  4983.9  515.31
  4984.1  514.81  4987.7  514.81  4988.0  515.31  5009.1  515.67  5022.6  516.79
  5101.0  517.91  5115.7  518.84  5127.9  518.78  5158.6  518.88  5281.1  522.12
  5417.1  524.73  5437.9  525.64  5502.9  526.39  5544.6  527.43  5677.7  528.64
#Mann=6,-1,0
  4113.4   0.035       0  4550.6    0.05       0  4970.3    0.07       0
  4983.9    0.05       0  4988.0    0.07       0  5127.9    0.05       0
Bank Sta=4983.9,4988
Exp/Cntr=0.3,0.1

Type RM Length L Ch R = 1,6083,472,472,472
BEGIN DESCRIPTION:
GUADALUPE TRIBUTARY 16 210455
END DESCRIPTION:
XS GIS Cut Line= 2
      2287163.58     13753281.83      2286053.20     13752240.32
#Sta/Elev= 30
  4116.4  526.02  4157.7  525.86  4247.7  525.78  4254.5  525.43  4396.2  525.03
  4473.8  524.31  4537.8  523.13  4544.7  522.62  4615.5  521.72  4721.5  519.08
  4728.8  519.42  4771.3  518.96  4785.4  518.14  4812.0  517.69  4877.3  516.52
  4926.6  516.44  4955.0  515.60  5044.7  515.41  5045.0  514.91  5048.6  514.91
  5048.9  515.41  5061.0  515.95  5145.9  516.60  5247.7  519.42  5273.4  520.18
  5287.6  519.72  5315.9  521.17  5358.8  522.19  5506.9  525.89  5638.8  527.71
#Mann=7,-1,0
  4116.4    0.07       0  4157.7   0.035       0  4812.0    0.05       0
  5044.7    0.05       0  5048.9    0.05       0  5247.7    0.07       0
  5358.8    0.05       0
Bank Sta=5044.7,5048.9
Exp/Cntr=0.3,0.1

Type RM Length L Ch R = 1,5611,543,543,543
BEGIN DESCRIPTION:
GUADALUPE TRIBUTARY 16 210454
END DESCRIPTION:
XS GIS Cut Line= 2
      2287163.58     13753169.91      2286466.38     13751551.72
#Sta/Elev= 30
  4131.9  525.62  4188.9  525.31  4212.4  525.56  4311.5  524.51  4317.4  524.89
  4333.2  524.39  4416.9  523.87  4516.5  522.41  4797.0  516.76  4873.0  515.56
  4954.5  512.78  5006.2  512.57  5006.5  512.07  5010.2  512.07  5010.4  512.57
  5019.2  512.60  5030.5  513.48  5048.6  512.74  5054.0  513.22  5148.1  513.38
  5171.7  513.75  5200.6  514.89  5206.1  515.94  5224.2  515.91  5229.6  516.36
  5282.1  516.33  5374.7  517.96  5475.7  518.80  5732.8  523.62  5893.9  525.05
#Mann=4,-1,0
  4131.9   0.035       0  5006.2   0.035       0  5010.4   0.035       0
  5374.7    0.05       0
Bank Sta=5006.2,5010.4
Exp/Cntr=0.3,0.1

Type RM Length L Ch R = 1,5068,647,647,647
BEGIN DESCRIPTION:
GUADALUPE TRIBUTARY 16 210453
END DESCRIPTION:
XS GIS Cut Line= 2
      2287284.10     13753152.71      2287172.21     13751603.35
#Sta/Elev= 30
  3869.0  525.57  4007.1  525.14  4097.3  524.39  4107.3  524.57  4208.1  523.91
  4448.2  521.11  4558.5  519.01  4756.5  513.85  4809.2  512.81  4879.3  511.82
  4896.1  512.01  4929.5  511.81  4949.5  512.15  4997.5  511.53  4997.8  511.03
  5001.5  511.03  5001.8  511.53  5035.6  512.34  5079.9  512.90  5129.1  514.29
  5160.1  515.35  5175.2  516.30  5180.3  516.15  5220.2  517.67  5250.3  518.06
  5260.3  518.69  5275.8  519.18  5314.8  520.32  5360.6  522.14  5422.4  523.35
#Mann=5,-1,0
  3869.0   0.035       0  4997.5   0.035       0  5001.8   0.035       0
  5129.1    0.07       0  5275.8    0.05       0
Bank Sta=4997.5,5001.8
Exp/Cntr=0.3,0.1

Type RM Length L Ch R = 1,4421,689,689,689
BEGIN DESCRIPTION:
GUADALUPE TRIBUTARY 16 210452
END DESCRIPTION:
XS GIS Cut Line= 2
      2287447.65     13753152.74      2287912.42     13751749.83
#Sta/Elev= 30
  3887.6  525.72  4083.0  525.25  4120.0  524.90  4127.5  524.27  4138.1  524.61
  4278.5  522.83  4532.1  517.24  4570.0  515.33  4664.8  513.12  4722.3  512.57
  4759.6  511.58  4796.7  511.41  4880.8  511.15  4896.5  510.66  4999.7  510.01
  5000.0  509.51  5003.8  509.51  5004.0  510.01  5071.0  510.78  5134.4  512.18
  5159.9  513.15  5171.4  514.31  5229.5  516.27  5234.8  515.96  5254.7  516.76
  5266.5  516.69  5293.7  518.38  5317.9  520.31  5329.9  520.32  5365.5  522.31
#Mann=5,-1,0
  3887.6   0.035       0  4796.7    0.07       0  4999.7    0.05       0
  5004.0    0.07       0  5293.7    0.12       0
Bank Sta=4999.7,5004
Exp/Cntr=0.3,0.1

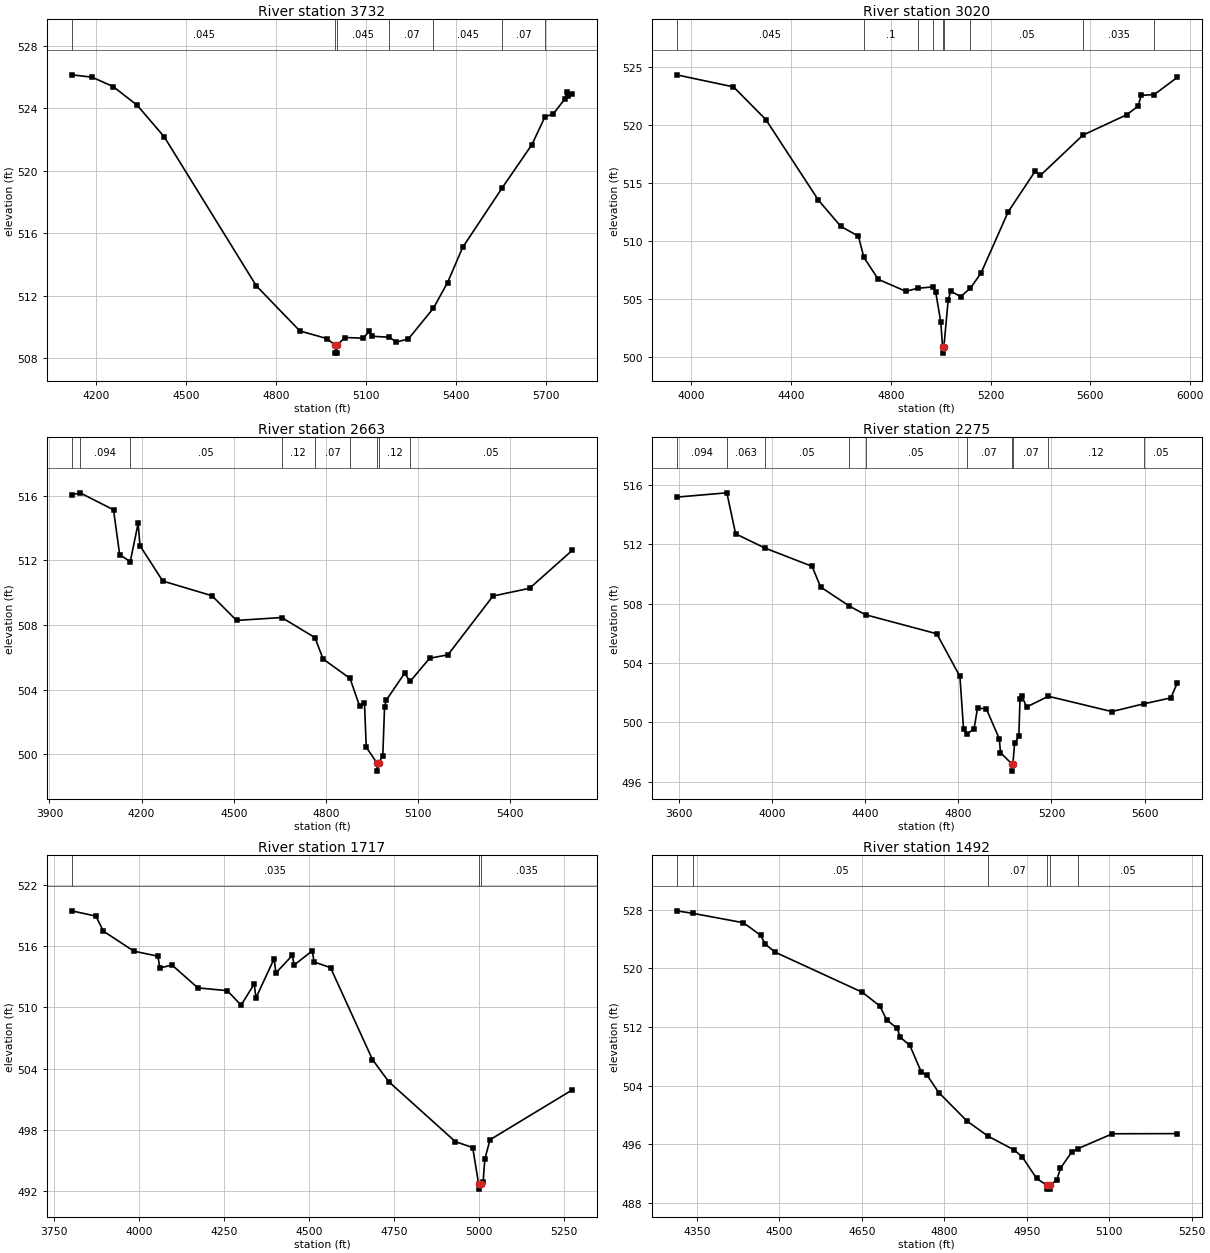
Type RM Length L Ch R = 1,3732,712,712,712
BEGIN DESCRIPTION:
GUADALUPE TRIBUTARY 16 210451
END DESCRIPTION:
XS GIS Cut Line= 2
      2288222.35     13753402.34      2288351.47     13751741.05
#Sta/Elev= 30
  4119.8  526.14  4187.3  525.99  4257.6  525.39  4337.8  524.19  4428.1  522.16
  4734.3  512.62  4879.4  509.73  4969.7  509.24  4997.3  508.81  4997.7  508.31
  5001.9  508.31  5002.2  508.81  5029.9  509.31  5090.1  509.27  5110.1  509.71
  5118.5  509.39  5177.3  509.33  5200.4  509.02  5240.5  509.22  5323.2  511.17
  5370.9  512.83  5421.1  515.08  5552.8  518.90  5651.7  521.67  5695.4  523.46
  5722.0  523.62  5762.1  524.61  5767.1  525.06  5772.1  524.80  5786.1  524.93
#Mann=7,-1,0
  4119.8   0.045       0  4997.3   0.045       0  5002.2   0.045       0
  5177.3    0.07       0  5323.2   0.045       0  5552.8    0.07       0
  5695.4    0.12       0
Bank Sta=4997.3,5002.2
Exp/Cntr=0.3,0.1

Type RM Length L Ch R = 1,3020,357,357,357
BEGIN DESCRIPTION:
GUADALUPE TRIBUTARY 16 210450
END DESCRIPTION:
XS GIS Cut Line= 3
      2288928.19     13753583.15      2288902.37     13752403.86
      2288446.16     13751715.25
#Sta/Elev= 30
  3941.9  524.30  4170.1  523.26  4300.1  520.43  4510.2  513.50  4600.2  511.23
  4670.2  510.40  4692.6  508.56  4750.2  506.67  4860.3  505.64  4908.2  505.90
  4969.1  506.02  4980.3  505.56  5000.3  503.03  5007.9  500.81  5008.2  500.31
  5012.8  500.81  5030.3  504.91  5040.3  505.65  5080.3  505.18  5119.3  505.91
  5162.0  507.22  5270.3  512.48  5378.6  515.99  5399.7  515.63  5569.9  519.10
  5745.6  520.86  5790.8  521.60  5803.8  522.53  5855.7  522.60  5947.5  524.07
#Mann=9,-1,0
  3941.9   0.045       0  4692.6     0.1       0  4908.2    0.12       0
  4969.1     0.1       0  5007.9    0.05       0  5012.8     0.1       0
  5119.3    0.05       0  5569.9   0.035       0  5855.7    0.07       0
Bank Sta=5007.9,5012.8
Exp/Cntr=0.3,0.1

Type RM Length L Ch R = 1,2663,388,388,388
BEGIN DESCRIPTION:
A19176
END DESCRIPTION:
XS GIS Cut Line= 3
      2289348.02     13753331.02      2289321.98     13752607.05
      2288884.46     13751815.34
#Sta/Elev= 30
  3972.6  516.05  3999.8  516.18  4108.7  515.13  4128.7  512.35  4163.1  511.92
  4188.8  514.29  4194.8  512.91  4268.8  510.72  4428.9  509.81  4509.0  508.28
  4656.1  508.46  4763.9  507.22  4790.8  505.89  4878.3  504.69  4909.3  502.99
  4925.4  503.16  4931.1  500.43  4966.1  499.45  4966.6  498.95  4971.6  499.45
  4984.9  499.91  4990.7  502.93  4996.4  503.35  5055.9  505.01  5073.8  504.50
  5137.3  505.94  5196.9  506.15  5343.5  509.79  5462.6  510.27  5601.6  512.62
#Mann=9,-1,0
  3972.6   0.063       0  3999.8   0.094       0  4163.1    0.05       0
  4656.1    0.12       0  4763.9    0.07       0  4878.3    0.12       0
  4966.1    0.05       0  4971.6    0.12       0  5073.8    0.05       0
Bank Sta=4966.1,4971.6
Exp/Cntr=0.3,0.1

Type RM Length L Ch R = 1,2275,558,558,558
BEGIN DESCRIPTION:
GUADALUPE TRIBUTARY 16 210449
END DESCRIPTION:
XS GIS Cut Line= 4
      2289547.95     13753385.18      2289324.15     13752076.77
      2289212.25     13751611.95      2289306.20     13751279.48
#Sta/Elev= 30
  3588.9  515.17  3805.1  515.46  3842.7  512.70  3967.6  511.75  4171.2  510.51
  4207.9  509.12  4331.8  507.83  4400.9  507.25  4706.9  505.97  4806.5  503.10
  4822.0  499.59  4835.8  499.20  4867.4  499.58  4882.1  500.96  4919.8  500.92
  4975.7  498.90  4980.9  497.97  5028.5  497.22  5028.9  496.72  5034.1  497.22
  5041.6  498.60  5059.6  499.06  5064.7  501.56  5072.4  501.79  5093.0  501.04
  5186.8  501.76  5459.2  500.73  5596.2  501.25  5712.6  501.65  5739.9  502.63
#Mann=10,-1,0
  3588.9   0.094       0  3805.1   0.063       0  3967.6    0.05       0
  4331.8    0.07       0  4400.9    0.05       0  4835.8    0.07       0
  5028.5    0.05       0  5034.1    0.07       0  5186.8    0.12       0
  5596.2    0.05       0
Bank Sta=5028.5,5034.1
Exp/Cntr=0.3,0.1

Type RM Length L Ch R = 1,1717,225,225,225
BEGIN DESCRIPTION:
GUADALUPE TRIBUTARY 16 210448
END DESCRIPTION:
XS GIS Cut Line= 3
      2289745.92     13752705.11      2289504.91     13751370.93
      2289441.77     13751273.71
#Sta/Elev= 30
  3802.4  519.43  3873.6  518.91  3895.5  517.44  3985.4  515.48  4056.1  514.99
  4061.2  513.83  4097.2  514.13  4173.3  511.89  4259.8  511.62  4300.4  510.20
  4339.0  512.28  4344.1  510.91  4397.6  514.75  4402.7  513.35  4451.1  515.07
  4456.2  514.12  4509.8  515.52  4514.8  514.43  4563.3  513.87  4686.6  504.88
  4734.0  502.73  4930.5  496.84  4981.3  496.27  4998.7  492.70  4999.2  492.20
  5004.5  492.70  5011.8  492.86  5016.9  495.13  5032.1  497.03  5274.1  501.91
#Mann=3,-1,0
  3802.4   0.035       0  4998.7   0.035       0  5004.5   0.035       0
Bank Sta=4998.7,5004.5
Exp/Cntr=0.3,0.1

Type RM Length L Ch R = 1,1492,233,233,233
BEGIN DESCRIPTION:
A19175
END DESCRIPTION:
XS GIS Cut Line= 2
      2289957.39     13752127.87      2289670.94     13751263.29
#Sta/Elev= 30
  4312.7  527.86  4342.9  527.51  4434.2  526.24  4465.9  524.52  4473.7  523.34
  4492.4  522.21  4650.9  516.75  4682.6  514.88  4695.0  513.00  4714.3  511.82
  4719.5  510.63  4737.1  509.53  4758.2  505.84  4768.7  505.42  4789.8  503.08
  4841.1  499.20  4879.5  497.13  4926.7  495.26  4941.4  494.34  4967.9  491.36
  4987.0  490.41  4987.5  489.91  4992.4  489.91  4992.9  490.41  5004.8  491.22
  5011.0  492.73  5031.3  494.93  5042.4  495.41  5105.8  497.46  5223.5  497.48
#Mann=6,-1,0
  4312.7   0.094       0  4342.9    0.05       0  4879.5    0.07       0
  4987.0    0.05       0  4992.9    0.07       0  5042.4    0.05       0
Bank Sta=4987,4992.9
Exp/Cntr=0.3,0.1

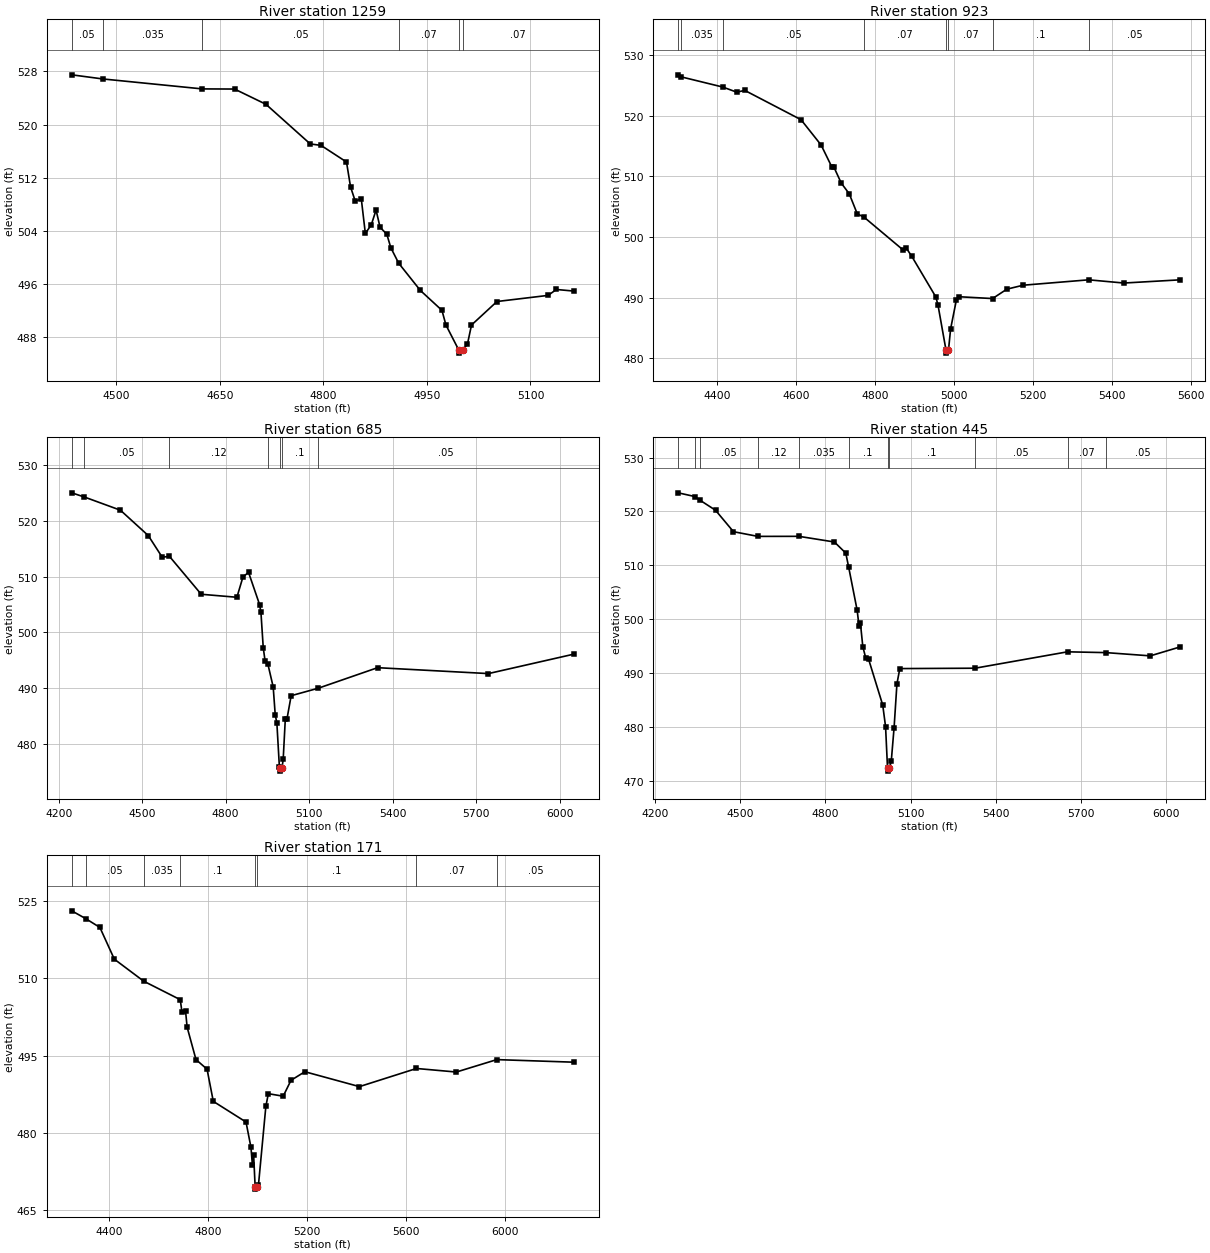
Type RM Length L Ch R = 1,1259,336,336,336
BEGIN DESCRIPTION:
GUADALUPE TRIBUTARY 16 210447
END DESCRIPTION:
XS GIS Cut Line= 2
      2290236.55     13751887.35      2289863.64     13751263.28
#Sta/Elev= 30
  4435.8  527.49  4480.7  526.87  4624.9  525.37  4671.5  525.35  4716.9  523.06
  4781.1  517.09  4796.7  516.87  4833.6  514.37  4839.5  510.61  4846.3  508.46
  4855.0  508.84  4860.9  503.61  4869.6  504.94  4876.4  507.14  4882.2  504.55
  4892.0  503.49  4897.8  501.46  4909.2  499.13  4940.6  495.03  4971.8  492.04
  4977.6  489.83  4996.0  486.10  4996.5  485.60  5001.9  486.10  5008.7  486.94
  5014.6  489.83  5051.5  493.37  5125.5  494.29  5137.5  495.18  5162.8  494.94
#Mann=6,-1,0
  4435.8    0.05       0  4480.7   0.035       0  4624.9    0.05       0
  4909.2    0.07       0  4996.0    0.05       0  5001.9    0.07       0
Bank Sta=4996,5001.9
Exp/Cntr=0.3,0.1

Type RM Length L Ch R = 1,923,238,238,238
BEGIN DESCRIPTION:
A19174
END DESCRIPTION:
XS GIS Cut Line= 3
      2290321.99     13751820.61      2290228.23     13751320.59
      2289920.94     13750622.67
#Sta/Elev= 30
  4302.5  526.73  4309.0  526.41  4415.5  524.71  4450.6  523.87  4471.0  524.16
  4613.4  519.33  4664.3  515.15  4691.4  511.54  4696.5  511.53  4715.2  508.88
  4735.5  507.11  4755.9  503.79  4772.7  503.27  4872.0  497.84  4879.4  498.21
  4893.8  496.80  4954.8  490.09  4960.3  488.73  4980.5  481.33  4981.0  480.83
  4986.8  481.33  4992.2  484.84  5007.0  489.66  5014.0  490.13  5098.4  489.83
  5134.6  491.38  5175.8  492.03  5341.7  492.92  5431.0  492.39  5573.8  492.92
#Mann=8,-1,0
  4302.5    0.05       0  4309.0   0.035       0  4415.5    0.05       0
  4772.7    0.07       0  4980.5    0.05       0  4986.8    0.07       0
  5098.4     0.1       0  5341.7    0.05       0
Bank Sta=4980.5,4986.8
Exp/Cntr=0.3,0.1

Type RM Length L Ch R = 1,685,240,240,240
BEGIN DESCRIPTION:
GUADALUPE TRIBUTARY 16 210446
END DESCRIPTION:
XS GIS Cut Line= 3
      2290357.08     13751749.67      2290382.90     13751078.26
      2289763.12     13750131.37
#Sta/Elev= 30
  4247.1  525.06  4292.8  524.30  4421.9  521.94  4522.0  517.38  4572.0  513.50
  4597.9  513.66  4712.1  506.85  4840.3  506.31  4862.2  509.98  4882.2  510.77
  4921.7  505.01  4926.6  503.63  4934.9  497.28  4941.7  494.81  4951.8  494.27
  4970.7  490.21  4977.9  485.25  4983.9  483.71  4993.0  475.81  4995.8  475.60
  4996.3  475.10  5002.1  475.60  5006.6  477.23  5014.1  484.37  5020.0  484.42
  5035.2  488.64  5133.0  489.99  5345.7  493.67  5743.8  492.61  6050.7  496.10
#Mann=7,-1,0
  4247.1   0.035       0  4292.8    0.05       0  4597.9    0.12       0
  4951.8     0.1       0  4995.8    0.05       0  5002.1     0.1       0
  5133.0    0.05       0
Bank Sta=4995.8,5002.1
Exp/Cntr=0.3,0.1

Type RM Length L Ch R = 1,445,274,274,274
BEGIN DESCRIPTION:
A19173
END DESCRIPTION:
XS GIS Cut Line= 4
      2290420.94     13751669.54      2290577.19     13751200.80
      2290561.57     13750888.30      2289884.49     13750206.02
#Sta/Elev= 30
  4281.4  523.46  4339.9  522.77  4356.5  522.14  4412.7  520.23  4475.9  516.25
  4562.1  515.38  4706.3  515.39  4831.4  514.34  4871.4  512.28  4881.2  509.79
  4911.5  501.68  4918.0  498.80  4923.0  499.29  4931.5  494.89  4941.5  492.89
  4951.5  492.65  5001.6  484.09  5011.6  480.08  5018.5  472.34  5019.0  471.84
  5024.8  472.34  5031.6  473.65  5041.6  479.92  5051.6  488.03  5061.7  490.86
  5326.7  490.93  5652.3  493.97  5788.3  493.82  5943.9  493.22  6049.6  494.89
#Mann=11,-1,0
  4281.4    0.05       0  4339.9   0.035       0  4356.5    0.05       0
  4562.1    0.12       0  4706.3   0.035       0  4881.2     0.1       0
  5018.5    0.05       0  5024.8     0.1       0  5326.7    0.05       0
  5652.3    0.07       0  5788.3    0.05       0
Bank Sta=5018.5,5024.8
Exp/Cntr=0.3,0.1

Type RM Length L Ch R = 1,171,0,0,0
BEGIN DESCRIPTION:
GUADALUPE TRIBUTARY 16 210445
END DESCRIPTION:
XS GIS Cut Line= 4
      2290477.60     13751646.37      2290804.68     13751172.95
      2290796.08     13750888.89      2289893.10     13750149.32
#Sta/Elev= 30
  4250.3  523.12  4306.4  521.61  4363.8  519.90  4422.1  513.74  4540.6  509.47
  4688.2  505.88  4695.0  503.54  4709.8  503.60  4715.9  500.56  4751.7  494.26
  4796.4  492.39  4821.6  486.15  4953.7  482.14  4973.7  477.22  4979.5  473.78
  4984.5  475.72  4990.5  469.62  4991.0  469.12  4996.9  469.62  5003.8  469.84
  5033.8  485.18  5043.8  487.64  5103.8  487.15  5135.2  490.23  5191.2  491.90
  5411.5  489.01  5641.8  492.53  5802.7  491.84  5966.0  494.25  6277.1  493.75
#Mann=8,-1,0
  4250.3   0.035       0  4306.4    0.05       0  4540.6   0.035       0
  4688.2     0.1       0  4990.5    0.05       0  4996.9     0.1       0
  5641.8    0.07       0  5966.0    0.05       0
Bank Sta=4990.5,4996.9
Exp/Cntr=0.3,0.1

Chan Stop Cuts=-1