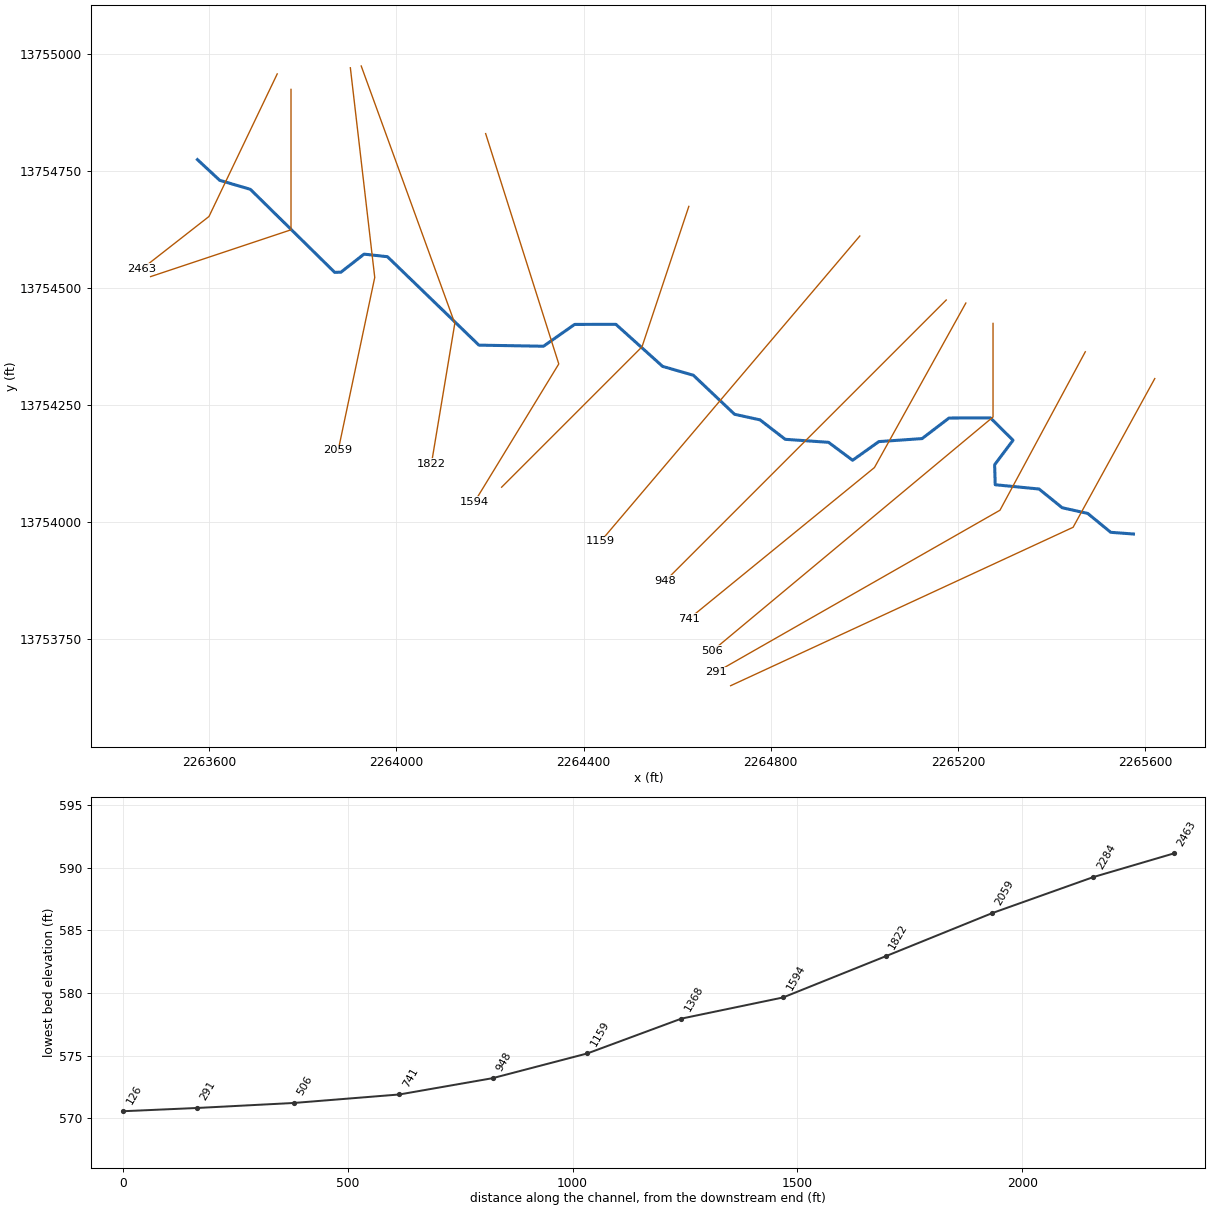
--- GUADALUPE TRIBUTARY 1D.prj (project) ---

Proj Title=GUADALUPE TRIBUTARY 1D Base Level Engineering
Current Plan=p01
Default Exp/Contr=0.3,0.1
English Units
Geom File=g01
Flow File=f01
Plan File=p01
BEGIN DESCRIPTION:
GUADALUPE TRIBUTARY 1D
END DESCRIPTION:

--- GUADALUPE TRIBUTARY 1D.p01 (plan) ---

Plan Title=Multiple Run
Short Identifier=Multiple
Geom File=g01
Flow File=f01
Subcritical Flow
K Sum by GR= 0
Std Step Tol= 0.01
Critical Tol= 0.01
Num of Std Step Trials= 20
Max Error Tol= 0.3
Flow Tol Ratio= 0.001
Split Flow NTrial= 30
Split Flow Tol= 0.02
Split Flow Ratio= 0.02
Log Output Level= 0
Friction Slope Method= 1
Unsteady Friction Slope Method= 2
Unsteady Bridges Friction Slope Method= 1
Parabolic Critical Depth
Global Vel Dist=  1 , 1 , 1
Global Log Level= 0
CheckData=True
Encroach Param= -1, 0, 0, 0
BEGIN DESCRIPTION:
Multiple Run
END DESCRIPTION:

--- GUADALUPE TRIBUTARY 1D.f01 (steady flow) ---

Flow Title=Multiple
Number of Profiles=7
Profile Names=10-year,25-year,50-year,1pct_min,100-year,1pct_plu,500-year
River Rch & RM= GUADALUPE TRIBUT,Reach-1,2463
     352     549     720     459     916    1827    1462
Boundary for River Rch & Prof#=GUADALUPE TRIBUT,Reach-1,1
Up Type=0
Dn Type=3
Dn Slope=0.005
Boundary for River Rch & Prof#=GUADALUPE TRIBUT,Reach-1,2
Up Type=0
Dn Type=3
Dn Slope=0.005
Boundary for River Rch & Prof#=GUADALUPE TRIBUT,Reach-1,3
Up Type=0
Dn Type=3
Dn Slope=0.005
Boundary for River Rch & Prof#=GUADALUPE TRIBUT,Reach-1,4
Up Type=0
Dn Type=3
Dn Slope=0.005
Boundary for River Rch & Prof#=GUADALUPE TRIBUT,Reach-1,5
Up Type=0
Dn Type=3
Dn Slope=0.005
Boundary for River Rch & Prof#=GUADALUPE TRIBUT,Reach-1,6
Up Type=0
Dn Type=3
Dn Slope=0.005
Boundary for River Rch & Prof#=GUADALUPE TRIBUT,Reach-1,7
Up Type=0
Dn Type=3
Dn Slope=0.005

--- GUADALUPE TRIBUTARY 1D.g01 (geometry) ---

Geom Title=Existing Conditions

River Reach=GUADALUPE TRIBUT,Reach-1
Reach XY= 30
      2263575.00     13754775.00      2263622.65     13754730.71
      2263688.23     13754711.43      2263868.27     13754534.15
      2263881.55     13754534.33      2263931.05     13754573.01
      2263981.05     13754567.50      2264176.47     13754378.53
      2264314.49     13754376.21      2264380.98     13754422.84
      2264469.11     13754423.03      2264568.96     13754333.18
      2264634.67     13754314.20      2264722.71     13754230.84
      2264777.17     13754218.86      2264830.97     13754177.33
      2264923.50     13754170.91      2264975.00     13754132.56
      2265030.89     13754172.45      2265123.40     13754178.86
      2265180.98     13754222.84      2265269.51     13754223.04
      2265317.74     13754175.31      2265278.41     13754122.93
      2265279.66     13754080.26      2265373.33     13754071.14
      2265422.81     13754031.10      2265477.25     13754019.05
      2265526.49     13753978.60      2265575.00     13753975.00

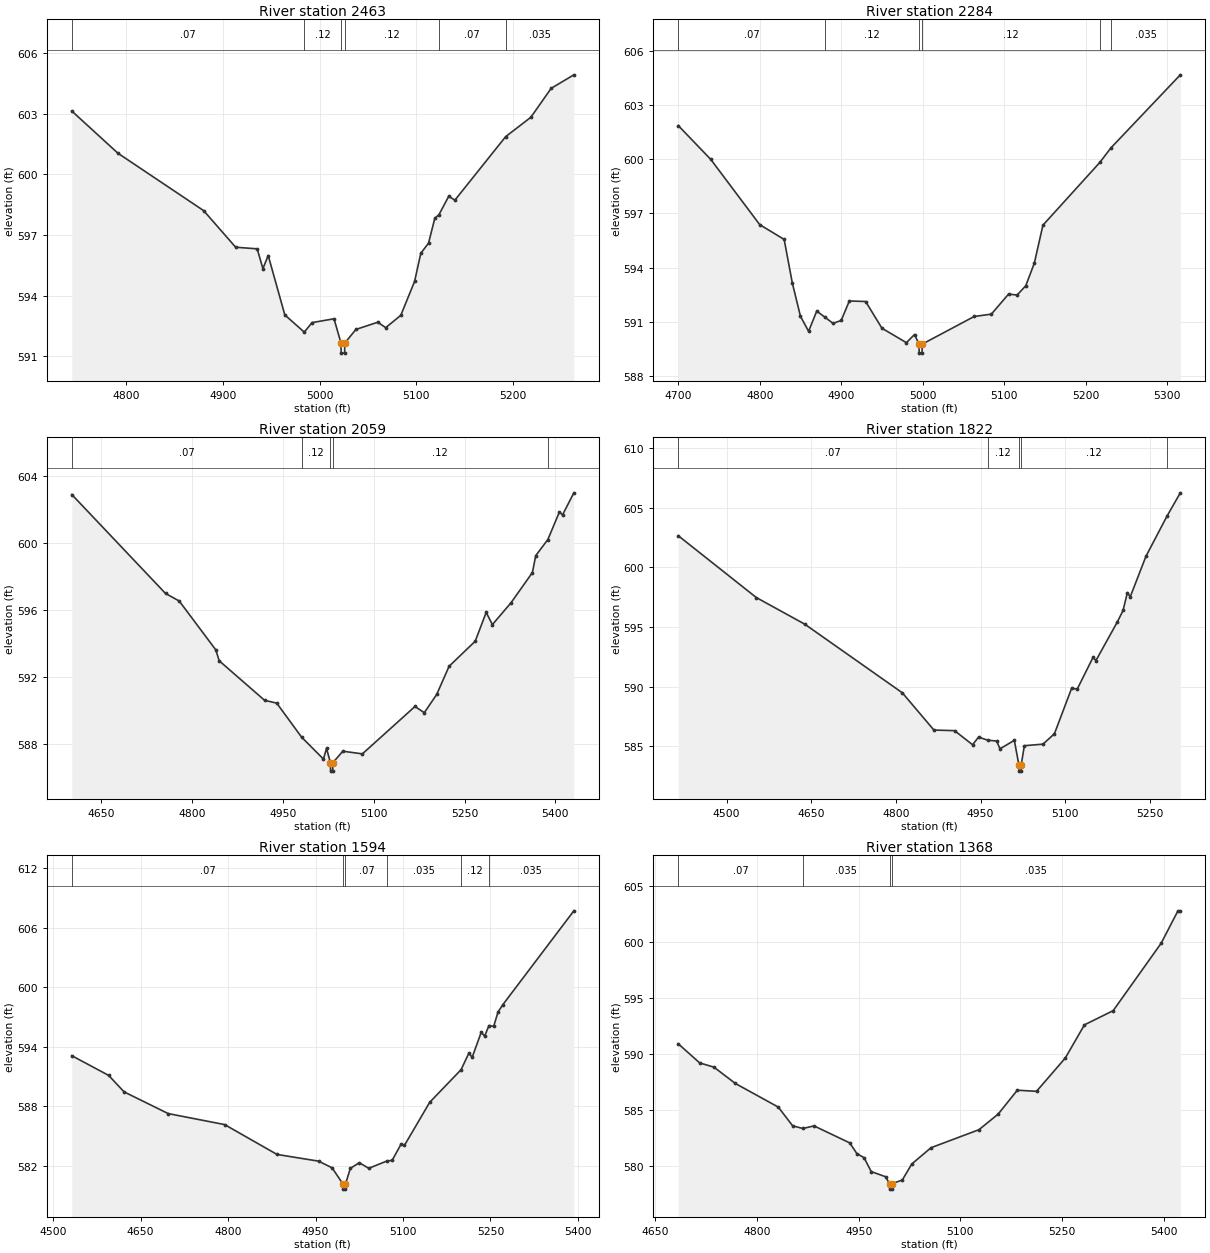
Type RM Length L Ch R = 1,2463,179,179,179
BEGIN DESCRIPTION:
A19191
END DESCRIPTION:
XS GIS Cut Line= 3
      2263745.56     13754958.09      2263599.74     13754653.44
      2263456.48     13754541.43
#Sta/Elev= 30
  4743.6  603.13  4791.4  601.04  4880.1  598.20  4913.2  596.39  4935.5  596.31
  4941.4  595.33  4946.9  595.98  4964.1  593.04  4984.2  592.19  4992.3  592.66
  5015.0  592.85  5022.2  591.65  5022.4  591.15  5025.9  591.15  5026.2  591.65
  5037.6  592.32  5060.3  592.68  5068.5  592.41  5084.1  593.02  5098.4  594.70
  5104.8  596.09  5112.8  596.59  5119.3  597.82  5123.6  598.00  5133.7  598.91
  5140.1  598.72  5192.6  601.86  5218.7  602.82  5239.7  604.25  5263.2  604.92
#Mann=6,-1,0
  4743.6    0.07       0  4984.2    0.12       0  5022.2    0.05       0
  5026.2    0.12       0  5123.6    0.07       0  5192.6   0.035       0
Bank Sta=5022.2,5026.2
Exp/Cntr=0.3,0.1

Type RM Length L Ch R = 1,2284,225,225,225
BEGIN DESCRIPTION:
GUADALUPE TRIBUTARY 1D 5.0
END DESCRIPTION:
XS GIS Cut Line= 3
      2263775.00     13754924.98      2263775.00     13754625.00
      2263475.01     13754525.00
#Sta/Elev= 30
  4700.0  601.87  4740.0  599.99  4800.0  596.38  4830.0  595.56  4840.0  593.15
  4850.0  591.30  4860.0  590.47  4870.0  591.59  4880.0  591.25  4890.0  590.91
  4900.0  591.07  4910.0  592.15  4930.0  592.12  4950.0  590.64  4980.0  589.84
  4990.0  590.29  4995.5  589.76  4995.7  589.26  4999.2  589.26  4999.5  589.76
  5063.2  591.29  5084.3  591.42  5105.4  592.53  5115.9  592.48  5126.5  592.99
  5137.0  594.24  5147.6  596.35  5217.5  599.83  5231.0  600.63  5316.2  604.68
#Mann=6,-1,0
  4700.0    0.07       0  4880.0    0.12       0  4995.5    0.05       0
  4999.5    0.12       0  5217.5    0.07       0  5231.0   0.035       0
Bank Sta=4995.5,4999.5
Exp/Cntr=0.3,0.1

Type RM Length L Ch R = 1,2059,237,237,237
BEGIN DESCRIPTION:
A19190
END DESCRIPTION:
XS GIS Cut Line= 3
      2263901.82     13754971.17      2263953.91     13754523.23
      2263875.78     13754153.45
#Sta/Elev= 30
  4601.5  602.90  4756.3  596.99  4778.9  596.54  4839.3  593.62  4844.9  592.97
  4919.8  590.61  4939.9  590.44  4980.9  588.41  5017.0  587.10  5022.1  587.74
  5028.5  586.88  5028.8  586.38  5032.3  586.38  5032.5  586.88  5049.0  587.57
  5081.3  587.41  5168.1  590.24  5183.5  589.87  5204.0  590.96  5224.4  592.64
  5267.6  594.14  5285.7  595.86  5295.9  595.13  5326.6  596.43  5362.0  598.24
  5367.5  599.25  5387.5  600.21  5406.6  601.86  5411.7  601.68  5430.4  603.00
#Mann=5,-1,0
  4601.5    0.07       0  4980.9    0.12       0  5028.5    0.05       0
  5032.5    0.12       0  5387.5   0.035       0
Bank Sta=5028.5,5032.5
Exp/Cntr=0.3,0.1

Type RM Length L Ch R = 1,1822,228,228,228
BEGIN DESCRIPTION:
GUADALUPE TRIBUTARY 1D 4.0
END DESCRIPTION:
XS GIS Cut Line= 3
      2263925.00     13754975.01      2264125.00     13754425.00
      2264075.00     13754124.98
#Sta/Elev= 30
  4414.4  602.65  4552.7  597.47  4638.5  595.24  4811.4  589.49  4867.3  586.37
  4903.9  586.32  4935.8  585.14  4946.4  585.78  4962.7  585.52  4978.4  585.45
  4984.4  584.80  5009.8  585.51  5017.9  583.43  5018.2  582.93  5021.7  582.93
  5021.9  583.43  5027.5  585.06  5060.5  585.19  5080.8  586.06  5111.2  589.86
  5121.3  589.81  5149.2  592.46  5154.3  592.19  5192.3  595.43  5202.4  596.39
  5210.0  597.88  5215.1  597.53  5243.0  600.93  5280.0  604.27  5303.8  606.24
#Mann=5,-1,0
  4414.4    0.07       0  4962.7    0.12       0  5017.9    0.05       0
  5021.9    0.12       0  5280.0   0.035       0
Bank Sta=5017.9,5021.9
Exp/Cntr=0.3,0.1

Type RM Length L Ch R = 1,1594,226,226,226
BEGIN DESCRIPTION:
A19189
END DESCRIPTION:
XS GIS Cut Line= 3
      2264190.88     13754830.52      2264347.14     13754338.33
      2264167.44     13754044.06
#Sta/Elev= 30
  4531.8  593.10  4595.1  591.11  4621.5  589.45  4697.2  587.26  4794.0  586.15
  4883.8  583.14  4955.3  582.46  4978.3  581.79  4997.2  580.14  4997.5  579.64
  5001.0  579.64  5001.2  580.14  5009.7  581.74  5025.0  582.30  5041.2  581.74
  5072.9  582.49  5081.2  582.53  5096.7  584.18  5102.5  584.06  5145.8  588.40
  5199.6  591.69  5212.8  593.34  5218.7  592.95  5234.2  595.47  5240.0  595.07
  5247.4  596.14  5255.5  596.06  5263.0  597.51  5270.9  598.22  5393.0  607.71
#Mann=6,-1,0
  4531.8    0.07       0  4997.2    0.05       0  5001.2    0.07       0
  5072.9   0.035       0  5199.6    0.12       0  5247.4   0.035       0
Bank Sta=4997.2,5001.2
Exp/Cntr=0.3,0.1

Type RM Length L Ch R = 1,1368,209,209,209
BEGIN DESCRIPTION:
GUADALUPE TRIBUTARY 1D 3.0
END DESCRIPTION:
XS GIS Cut Line= 3
      2264625.00     13754675.01      2264525.00     13754375.00
      2264225.00     13754075.00
#Sta/Elev= 30
  4683.8  590.94  4715.4  589.23  4736.5  588.85  4768.1  587.39  4831.4  585.28
  4852.5  583.61  4867.5  583.37  4884.1  583.60  4936.8  582.08  4947.3  581.12
  4957.9  580.76  4968.4  579.52  4989.5  579.06  4995.4  578.45  4995.7  577.95
  4999.2  577.95  4999.4  578.45  5014.2  578.76  5028.3  580.20  5056.6  581.65
  5127.3  583.26  5155.6  584.65  5183.9  586.79  5212.2  586.69  5254.6  589.66
  5282.9  592.63  5325.3  593.90  5396.0  599.92  5420.8  602.82  5424.3  602.82
#Mann=4,-1,0
  4683.8    0.07       0  4867.5   0.035       0  4995.4   0.035       0
  4999.4   0.035       0
Bank Sta=4995.4,4999.4
Exp/Cntr=0.3,0.1

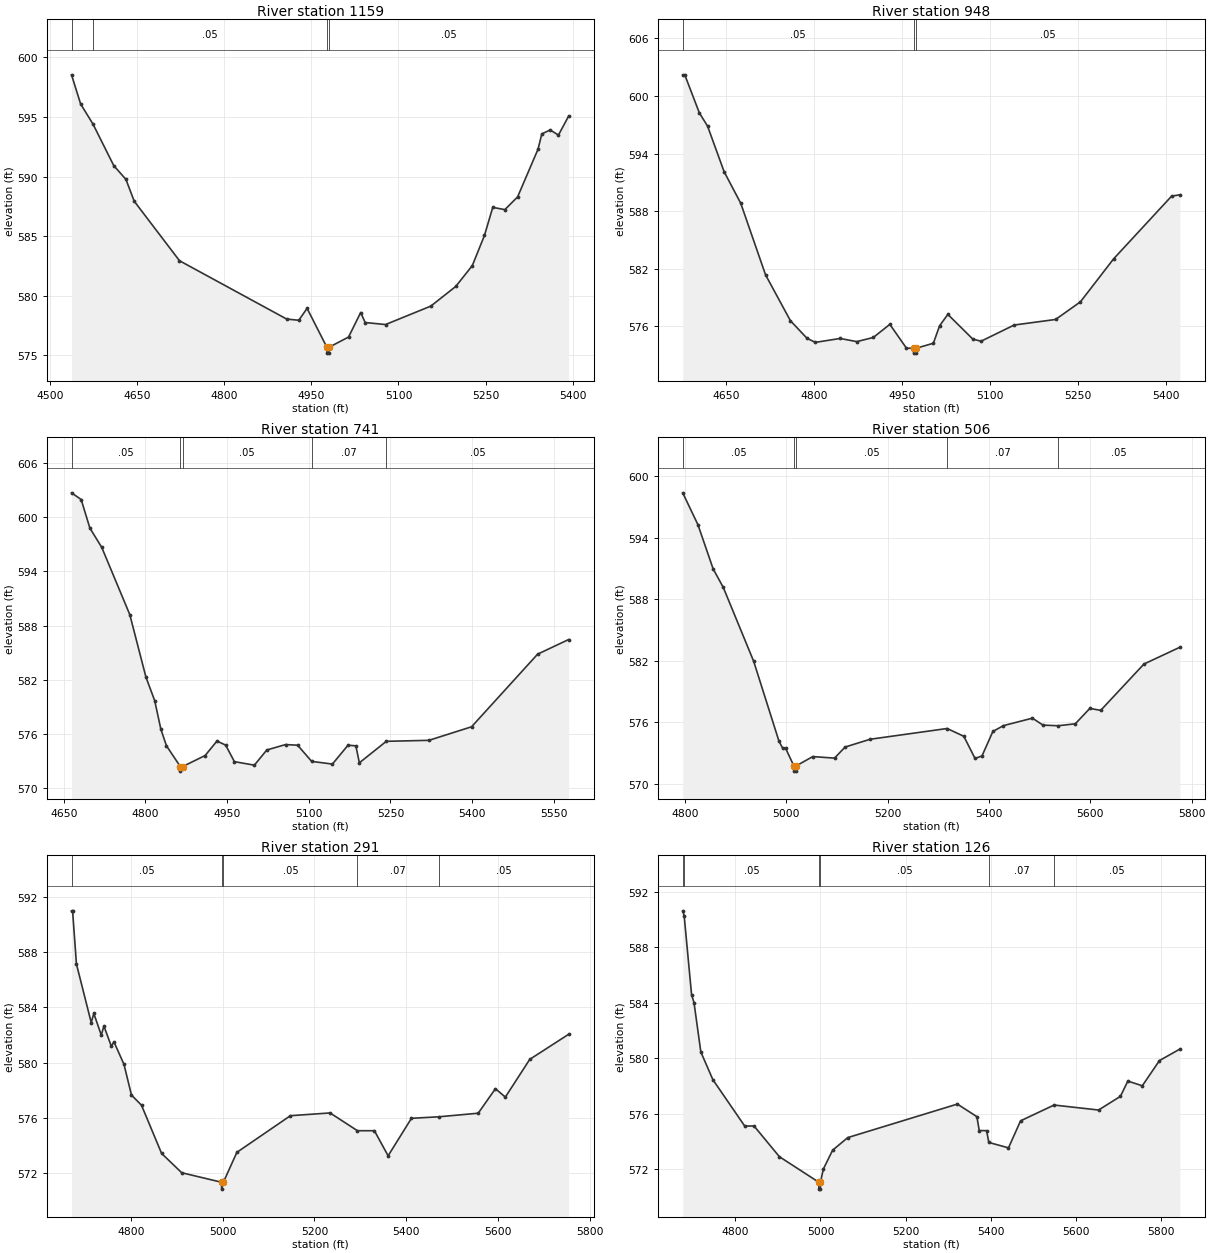
Type RM Length L Ch R = 1,1159,211,211,211
BEGIN DESCRIPTION:
A19188
END DESCRIPTION:
XS GIS Cut Line= 2
      2264990.33     13754611.73      2264436.47     13753959.06
#Sta/Elev= 30
  4537.1  598.54  4552.8  596.09  4574.0  594.41  4609.9  590.91  4630.8  589.76
  4645.0  587.93  4723.0  582.93  4907.6  578.03  4928.4  577.93  4942.7  578.93
  4976.7  575.67  4977.0  575.17  4980.5  575.17  4980.7  575.67  5014.1  576.52
  5035.0  578.58  5042.7  577.74  5077.8  577.57  5155.8  579.12  5198.7  580.77
  5227.2  582.52  5248.1  585.05  5262.4  587.41  5283.2  587.22  5305.2  588.29
  5340.3  592.29  5346.9  593.58  5361.2  593.91  5375.5  593.48  5393.1  595.08
#Mann=4,-1,0
  4537.1   0.035       0  4574.0    0.05       0  4976.7    0.05       0
  4980.7    0.05       0
Bank Sta=4976.7,4980.7
Exp/Cntr=0.3,0.1

Type RM Length L Ch R = 1,948,207,207,207
BEGIN DESCRIPTION:
GUADALUPE TRIBUTARY 1D 2.0
END DESCRIPTION:
XS GIS Cut Line= 3
      2265174.98     13754474.98      2264875.00     13754175.00
      2264575.00     13753875.00
#Sta/Elev= 30
  4575.7  602.21  4579.2  602.21  4604.0  598.25  4618.1  596.86  4646.4  592.10
  4674.7  588.82  4717.1  581.35  4759.5  576.57  4787.8  574.74  4802.0  574.31
  4844.4  574.72  4872.7  574.39  4900.9  574.82  4929.2  576.19  4957.5  573.71
  4969.7  573.69  4969.9  573.19  4973.4  573.19  4973.7  573.69  5003.5  574.22
  5014.1  576.04  5028.2  577.23  5070.7  574.66  5084.8  574.43  5141.4  576.12
  5212.1  576.70  5254.5  578.54  5311.1  583.02  5410.1  589.56  5424.2  589.70
#Mann=3,-1,0
  4575.7    0.05       0  4969.7    0.05       0  4973.7    0.05       0
Bank Sta=4969.7,4973.7
Exp/Cntr=0.3,0.1

Type RM Length L Ch R = 1,741,235,235,235
BEGIN DESCRIPTION:
A19187
END DESCRIPTION:
XS GIS Cut Line= 3
      2265216.92     13754468.52      2265021.61     13754116.98
      2264625.78     13753794.06
#Sta/Elev= 30
  4664.2  602.70  4681.9  601.96  4697.9  598.80  4719.7  596.66  4771.2  589.22
  4800.9  582.29  4816.9  579.70  4828.4  576.50  4838.6  574.69  4864.1  572.39
  4864.3  571.89  4868.1  572.39  4909.6  573.62  4931.3  575.22  4947.3  574.77
  4963.3  572.94  5000.0  572.55  5022.8  574.23  5057.2  574.83  5079.4  574.76
  5105.2  572.97  5143.3  572.67  5172.0  574.76  5186.4  574.69  5192.8  572.81
  5242.3  575.19  5320.6  575.30  5398.9  576.80  5520.2  584.84  5577.2  586.46
#Mann=5,-1,0
  4664.2    0.05       0  4864.1    0.05       0  4868.1    0.05       0
  5105.2    0.07       0  5242.3    0.05       0
Bank Sta=4864.1,4868.1
Exp/Cntr=0.3,0.1

Type RM Length L Ch R = 1,506,215,215,215
BEGIN DESCRIPTION:
GUADALUPE TRIBUTARY 1D 1.0
END DESCRIPTION:
XS GIS Cut Line= 3
      2265275.00     13754424.97      2265275.00     13754225.00
      2264674.99     13753725.00
#Sta/Elev= 30
  4795.8  598.37  4825.8  595.26  4855.8  590.95  4875.8  589.14  4935.8  581.93
  4985.8  574.12  4993.3  573.42  4999.0  573.42  5015.2  571.71  5015.5  571.21
  5019.0  571.21  5019.2  571.71  5052.4  572.63  5095.3  572.48  5116.2  573.56
  5165.6  574.32  5317.5  575.37  5350.5  574.61  5372.6  572.45  5386.3  572.69
  5407.8  575.08  5428.6  575.65  5485.9  576.38  5506.7  575.70  5536.7  575.64
  5570.5  575.83  5599.1  577.33  5620.6  577.14  5705.9  581.66  5776.8  583.30
#Mann=5,-1,0
  4795.8    0.05       0  5015.2    0.05       0  5019.2    0.05       0
  5317.5    0.07       0  5536.7    0.05       0
Bank Sta=5015.2,5019.2
Exp/Cntr=0.3,0.1

Type RM Length L Ch R = 1,291,165,165,165
BEGIN DESCRIPTION:
A19186
END DESCRIPTION:
XS GIS Cut Line= 3
      2265472.15     13754364.41      2265289.84     13754025.83
      2264683.51     13753679.73
#Sta/Elev= 30
  4671.0  591.01  4673.3  591.01  4681.7  587.15  4713.9  582.90  4719.6  583.56
  4735.8  581.99  4741.5  582.65  4757.7  581.18  4763.4  581.50  4785.3  579.86
  4801.5  577.64  4823.4  576.90  4867.2  573.40  4911.0  572.00  4997.7  571.31
  4997.9  570.81  5001.7  571.31  5031.1  573.48  5147.7  576.14  5234.1  576.34
  5293.7  575.05  5330.6  575.05  5360.5  573.23  5411.3  575.95  5470.7  576.06
  5556.7  576.32  5594.2  578.10  5615.8  577.49  5669.0  580.23  5753.7  582.05
#Mann=5,-1,0
  4671.0    0.05       0  4997.7    0.05       0  5001.7    0.05       0
  5293.7    0.07       0  5470.7    0.05       0
Bank Sta=4997.7,5001.7
Exp/Cntr=0.3,0.1

Type RM Length L Ch R = 1,126,0,0,0
BEGIN DESCRIPTION:
A19185
END DESCRIPTION:
XS GIS Cut Line= 3
      2265620.59     13754307.12      2265446.09     13753989.37
      2264714.32     13753650.83
#Sta/Elev= 30
  4676.2  590.64  4679.6  590.28  4697.0  584.59  4702.7  584.02  4718.8  580.45
  4747.1  578.45  4822.0  575.10  4843.8  575.11  4903.5  572.89  4996.1  571.05
  4996.3  570.55  4999.8  570.55  5000.1  571.05  5006.8  572.00  5028.6  573.36
  5064.2  574.27  5321.9  576.69  5367.8  575.78  5373.3  574.78  5390.7  574.77
  5395.8  573.92  5442.1  573.53  5470.5  575.48  5549.2  576.62  5653.9  576.26
  5705.3  577.25  5722.7  578.35  5756.7  578.01  5797.0  579.83  5845.0  580.66
#Mann=6,-1,0
  4676.2    0.07       0  4679.6    0.05       0  4996.1    0.05       0
  5000.1    0.05       0  5395.8    0.07       0  5549.2    0.05       0
Bank Sta=4996.1,5000.1
Exp/Cntr=0.3,0.1

Chan Stop Cuts=-1