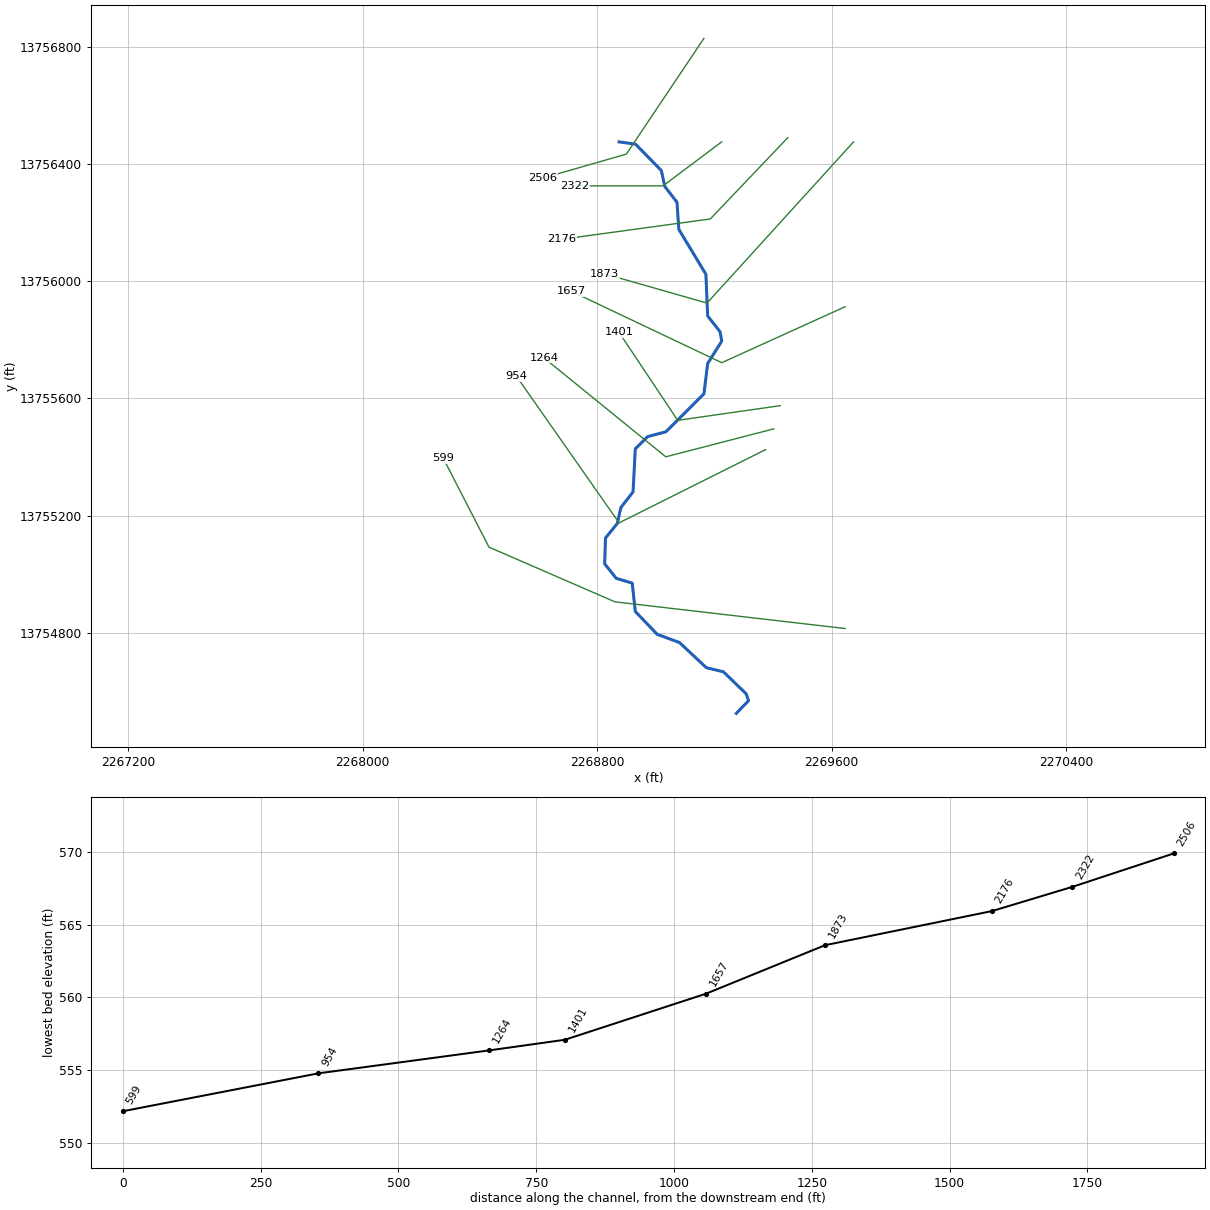
--- GUADALUPE TRIBUTARY 1J.prj (project) ---

Proj Title=GUADALUPE TRIBUTARY 1J Base Level Engineering
Current Plan=p01
Default Exp/Contr=0.3,0.1
English Units
Geom File=g01
Flow File=f01
Plan File=p01
BEGIN DESCRIPTION:
GUADALUPE TRIBUTARY 1J
END DESCRIPTION:

--- GUADALUPE TRIBUTARY 1J.p01 (plan) ---

Plan Title=Multiple Run
Short Identifier=Multiple
Geom File=g01
Flow File=f01
Subcritical Flow
K Sum by GR= 0
Std Step Tol= 0.01
Critical Tol= 0.01
Num of Std Step Trials= 20
Max Error Tol= 0.3
Flow Tol Ratio= 0.001
Split Flow NTrial= 30
Split Flow Tol= 0.02
Split Flow Ratio= 0.02
Log Output Level= 0
Friction Slope Method= 1
Unsteady Friction Slope Method= 2
Unsteady Bridges Friction Slope Method= 1
Parabolic Critical Depth
Global Vel Dist=  1 , 1 , 1
Global Log Level= 0
CheckData=True
Encroach Param= -1, 0, 0, 0
BEGIN DESCRIPTION:
Multiple Run
END DESCRIPTION:

--- GUADALUPE TRIBUTARY 1J.f01 (steady flow) ---

Flow Title=Multiple
Number of Profiles=7
Profile Names=10-year,25-year,50-year,1pct_min,100-year,1pct_plu,500-year
River Rch & RM= GUADALUPE TRIBUT,Reach-1,2506
     298     463     607     387     773    1542    1237
Boundary for River Rch & Prof#=GUADALUPE TRIBUT,Reach-1,1
Up Type=0
Dn Type=3
Dn Slope=0.005
Boundary for River Rch & Prof#=GUADALUPE TRIBUT,Reach-1,2
Up Type=0
Dn Type=3
Dn Slope=0.005
Boundary for River Rch & Prof#=GUADALUPE TRIBUT,Reach-1,3
Up Type=0
Dn Type=3
Dn Slope=0.005
Boundary for River Rch & Prof#=GUADALUPE TRIBUT,Reach-1,4
Up Type=0
Dn Type=3
Dn Slope=0.005
Boundary for River Rch & Prof#=GUADALUPE TRIBUT,Reach-1,5
Up Type=0
Dn Type=3
Dn Slope=0.005
Boundary for River Rch & Prof#=GUADALUPE TRIBUT,Reach-1,6
Up Type=0
Dn Type=3
Dn Slope=0.005
Boundary for River Rch & Prof#=GUADALUPE TRIBUT,Reach-1,7
Up Type=0
Dn Type=3
Dn Slope=0.005

--- GUADALUPE TRIBUTARY 1J.g01 (geometry) ---

Geom Title=Existing Conditions

River Reach=GUADALUPE TRIBUT,Reach-1
Reach XY= 30
      2268875.00     13756475.00      2268931.24     13756467.25
      2269019.18     13756377.31      2269031.14     13756322.83
      2269072.67     13756269.03      2269078.83     13756176.58
      2269171.24     13756023.44      2269177.30     13755880.93
      2269219.62     13755827.18      2269225.28     13755795.18
      2269177.38     13755719.03      2269164.48     13755615.21
      2269034.66     13755485.79      2268972.43     13755469.26
      2268930.36     13755427.70      2268922.75     13755280.93
      2268881.12     13755227.18      2268868.88     13755172.82
      2268828.67     13755123.41      2268825.89     13755035.34
      2268865.24     13754985.75      2268919.71     13754969.51
      2268930.54     13754872.62      2269004.87     13754794.77
      2269081.04     13754766.82      2269172.72     13754680.87
      2269231.08     13754666.85      2269308.73     13754591.71
      2269316.81     13754568.34      2269275.00     13754525.00

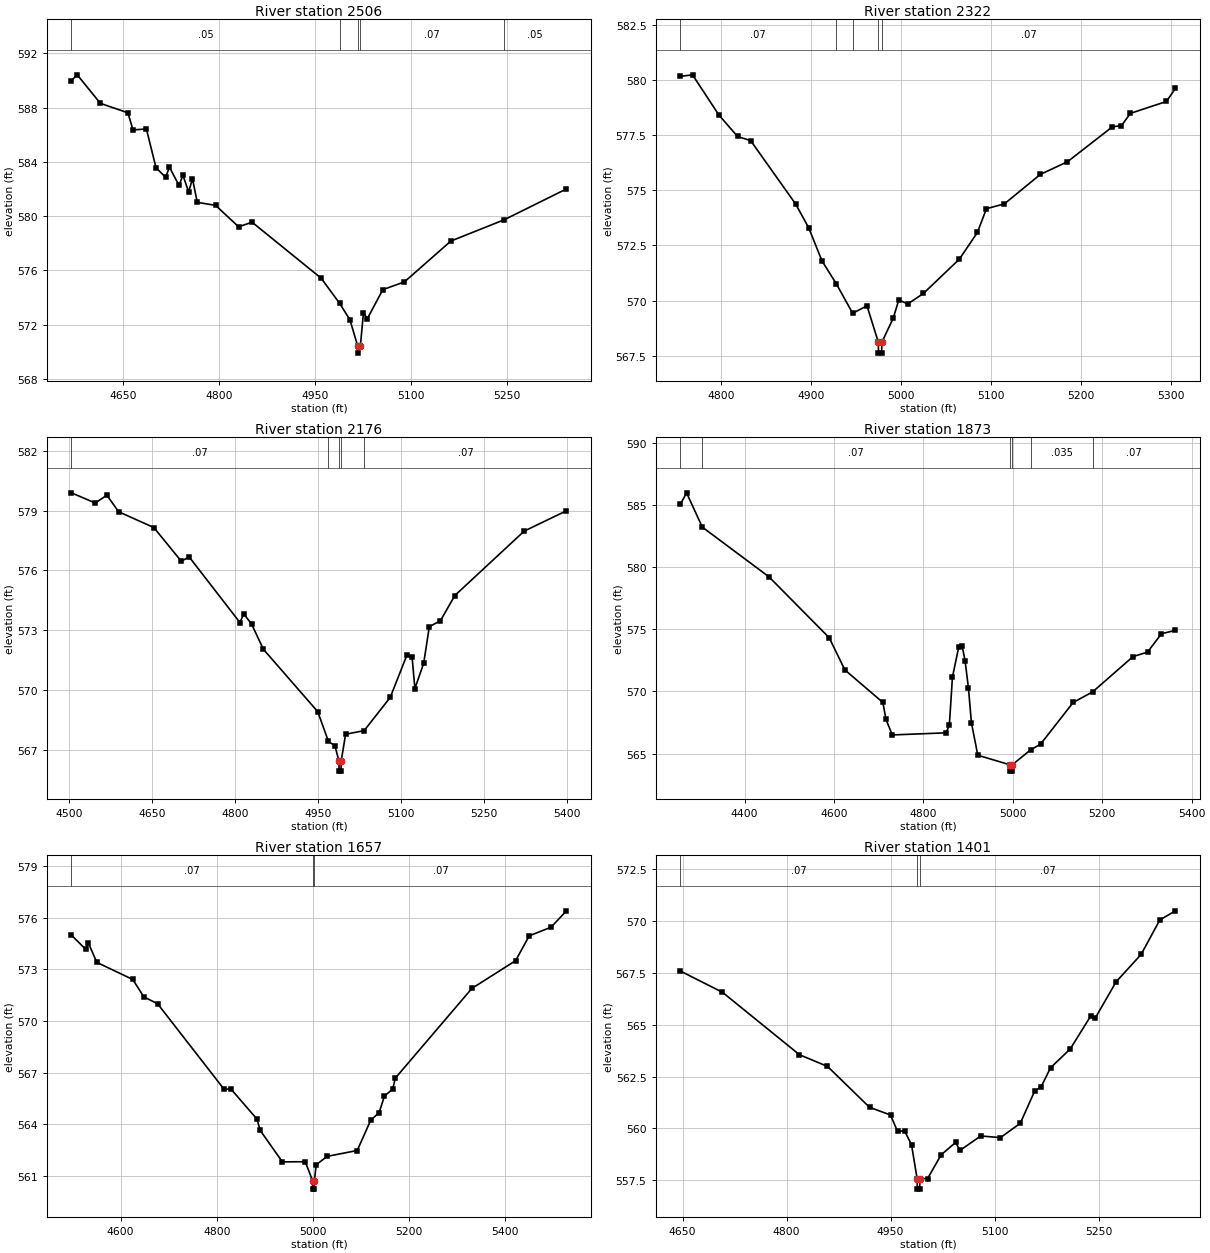
Type RM Length L Ch R = 1,2506,184,184,184
BEGIN DESCRIPTION:
A19193
END DESCRIPTION:
XS GIS Cut Line= 3
      2269164.58     13756828.35      2268899.84     13756433.41
      2268613.34     13756350.93
#Sta/Elev= 30
  4569.8  589.99  4578.9  590.42  4615.0  588.32  4658.1  587.62  4666.0  586.36
  4687.0  586.43  4702.0  583.57  4717.0  582.87  4723.0  583.61  4738.0  582.27
  4744.0  583.02  4753.0  581.80  4759.0  582.76  4766.5  581.02  4795.1  580.80
  4831.1  579.22  4852.1  579.56  4960.1  575.43  4988.9  573.58  5005.1  572.36
  5017.3  570.41  5017.5  569.91  5021.3  570.41  5026.2  572.89  5032.2  572.45
  5056.5  574.59  5090.2  575.16  5162.8  578.17  5245.7  579.73  5343.4  582.01
#Mann=5,-1,0
  4569.8    0.05       0  4988.9    0.07       0  5017.3    0.05       0
  5021.3    0.07       0  5245.7    0.05       0
Bank Sta=5017.3,5021.3
Exp/Cntr=0.3,0.1

Type RM Length L Ch R = 1,2322,146,146,146
BEGIN DESCRIPTION:
GUADALUPE TRIBUTARY 1J 4.0
END DESCRIPTION:
XS GIS Cut Line= 3
      2269225.00     13756475.00      2269025.00     13756325.00
      2268725.00     13756325.00
#Sta/Elev= 30
  4754.8  580.18  4768.3  580.25  4797.5  578.43  4818.3  577.45  4832.9  577.26
  4882.9  574.38  4897.5  573.29  4912.1  571.80  4927.9  570.77  4946.2  569.42
  4962.1  569.76  4974.7  568.11  4974.9  567.61  4978.4  567.61  4978.7  568.11
  4991.3  569.20  4997.5  570.03  5007.3  569.84  5024.8  570.32  5064.8  571.88
  5084.8  573.09  5094.8  574.17  5114.8  574.39  5154.8  575.73  5184.8  576.30
  5234.8  577.89  5244.8  577.94  5254.8  578.50  5294.8  579.04  5304.8  579.63
#Mann=5,-1,0
  4754.8    0.07       0  4927.9   0.035       0  4946.2    0.07       0
  4974.7    0.05       0  4978.7    0.07       0
Bank Sta=4974.7,4978.7
Exp/Cntr=0.3,0.1

Type RM Length L Ch R = 1,2176,303,303,303
BEGIN DESCRIPTION:
A19196
END DESCRIPTION:
XS GIS Cut Line= 3
      2269451.04     13756489.81      2269186.30     13756212.06
      2268679.23     13756142.71
#Sta/Elev= 30
  4504.1  579.89  4547.2  579.38  4568.2  579.77  4589.6  578.94  4653.2  578.15
  4702.9  576.46  4717.0  576.68  4808.9  573.39  4815.8  573.82  4829.9  573.32
  4851.3  572.05  4949.7  568.92  4968.9  567.44  4980.9  567.20  4988.1  566.44
  4988.3  565.94  4991.8  565.94  4992.1  566.44  5000.1  567.79  5033.7  567.97
  5080.9  569.64  5111.2  571.77  5120.3  571.68  5125.4  570.08  5141.4  571.35
  5151.5  573.18  5171.7  573.48  5197.6  574.74  5323.1  577.97  5399.6  578.99
#Mann=5,-1,0
  4504.1    0.07       0  4968.9   0.035       0  4988.1   0.035       0
  4992.1   0.035       0  5033.7    0.07       0
Bank Sta=4988.1,4992.1
Exp/Cntr=0.3,0.1

Type RM Length L Ch R = 1,1873,216,216,216
BEGIN DESCRIPTION:
GUADALUPE TRIBUTARY 1J 3.0
END DESCRIPTION:
XS GIS Cut Line= 3
      2269674.97     13756474.97      2269175.00     13755925.00
      2268824.97     13756025.01
#Sta/Elev= 30
  4256.4  585.05  4270.2  585.97  4305.5  583.21  4454.7  579.21  4589.2  574.32
  4624.3  571.73  4709.4  569.11  4716.2  567.76  4730.4  566.50  4851.0  566.67
  4858.1  567.33  4864.9  571.14  4879.0  573.57  4886.5  573.66  4893.2  572.47
  4900.7  570.28  4907.4  567.48  4921.6  564.87  4994.3  564.09  4994.5  563.59
  4998.0  563.59  4998.3  564.09  5039.8  565.30  5062.1  565.76  5134.9  569.11
  5178.8  569.97  5268.8  572.80  5301.3  573.16  5332.5  574.64  5363.7  574.91
#Mann=6,-1,0
  4256.4    0.05       0  4305.5    0.07       0  4994.3    0.05       0
  4998.3    0.07       0  5039.8   0.035       0  5178.8    0.07       0
Bank Sta=4994.3,4998.3
Exp/Cntr=0.3,0.1

Type RM Length L Ch R = 1,1657,256,256,256
BEGIN DESCRIPTION:
A19195
END DESCRIPTION:
XS GIS Cut Line= 3
      2269646.34     13755912.56      2269225.37     13755721.60
      2268713.18     13755964.68
#Sta/Elev= 30
  4497.9  574.98  4527.6  574.16  4533.1  574.53  4550.7  573.40  4625.4  572.41
  4648.5  571.40  4677.1  571.00  4815.6  566.03  4828.8  566.08  4883.7  564.31
  4890.3  563.66  4936.5  561.83  4984.0  561.84  4999.2  560.75  4999.4  560.25
  5002.9  560.25  5003.2  560.75  5006.7  561.66  5029.5  562.15  5092.1  562.49
  5120.4  564.26  5137.6  564.68  5148.7  565.65  5165.8  566.05  5171.4  566.69
  5330.5  571.89  5421.4  573.50  5449.7  574.94  5495.1  575.44  5527.1  576.39
#Mann=3,-1,0
  4497.9    0.07       0  4999.2    0.05       0  5003.2    0.07       0
Bank Sta=4999.2,5003.2
Exp/Cntr=0.3,0.1

Type RM Length L Ch R = 1,1401,137,137,137
BEGIN DESCRIPTION:
GUADALUPE TRIBUTARY 1J 2.0
END DESCRIPTION:
XS GIS Cut Line= 3
      2269425.03     13755575.00      2269075.00     13755525.00
      2268875.02     13755824.97
#Sta/Elev= 30
  4646.8  567.58  4707.4  566.56  4818.6  563.55  4859.0  562.99  4919.6  561.02
  4949.9  560.65  4960.0  559.86  4970.1  559.89  4980.2  559.22  4988.3  557.58
  4988.5  557.08  4992.0  557.08  4992.3  557.58  5003.4  557.59  5022.9  558.73
  5043.9  559.33  5050.0  558.94  5080.0  559.64  5108.5  559.56  5137.1  560.25
  5158.1  561.82  5167.1  562.00  5180.7  562.92  5209.2  563.83  5239.2  565.44
  5245.3  565.32  5275.3  567.06  5311.4  568.38  5338.4  570.04  5360.9  570.48
#Mann=3,-1,0
  4646.8    0.07       0  4988.3    0.05       0  4992.3    0.07       0
Bank Sta=4988.3,4992.3
Exp/Cntr=0.3,0.1

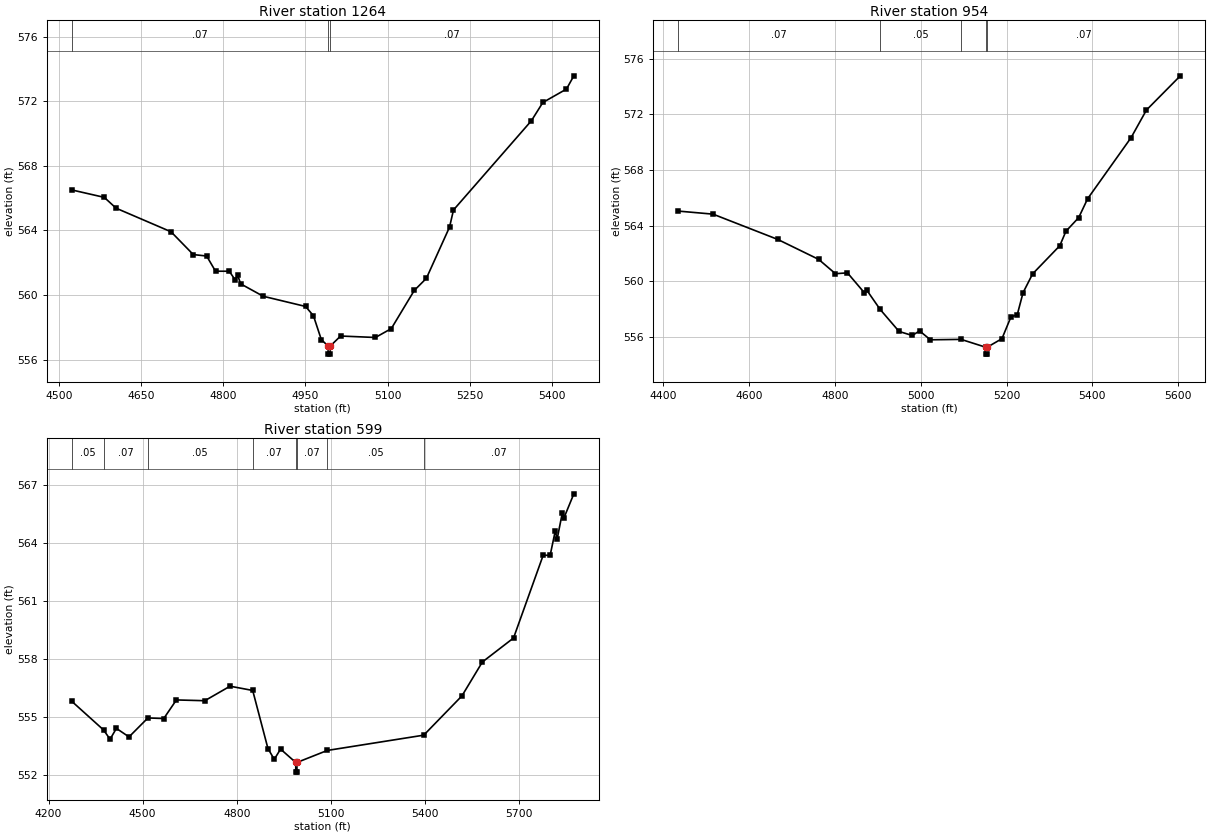
Type RM Length L Ch R = 1,1264,310,310,310
BEGIN DESCRIPTION:
A19194
END DESCRIPTION:
XS GIS Cut Line= 3
      2269403.37     13755495.92      2269034.39     13755400.42
      2268618.89     13755738.02
#Sta/Elev= 30
  4523.4  566.51  4582.7  566.05  4604.3  565.38  4704.6  563.92  4745.2  562.51
  4769.6  562.42  4785.8  561.48  4810.9  561.48  4821.3  560.96  4826.4  561.22
  4831.6  560.70  4872.9  559.93  4950.1  559.30  4964.5  558.73  4978.9  557.25
  4991.3  556.85  4991.5  556.35  4995.0  556.35  4995.3  556.85  5014.1  557.47
  5077.7  557.38  5106.7  557.93  5148.6  560.29  5170.7  561.04  5213.0  564.21
  5220.2  565.27  5362.4  570.79  5383.3  571.92  5426.4  572.75  5439.9  573.57
#Mann=3,-1,0
  4523.4    0.07       0  4991.3    0.05       0  4995.3    0.07       0
Bank Sta=4991.3,4995.3
Exp/Cntr=0.3,0.1

Type RM Length L Ch R = 1,954,355,355,355
BEGIN DESCRIPTION:
GUADALUPE TRIBUTARY 1J 1.0
END DESCRIPTION:
XS GIS Cut Line= 3
      2269374.97     13755424.99      2268875.00     13755175.00
      2268525.01     13755674.99
#Sta/Elev= 30
  4435.4  565.05  4516.4  564.83  4667.4  563.01  4762.4  561.58  4801.5  560.55
  4829.5  560.61  4868.6  559.19  4874.2  559.38  4905.7  557.98  4949.7  556.40
  4980.4  556.11  4997.4  556.44  5022.7  555.80  5094.1  555.83  5151.1  555.27
  5151.3  554.77  5154.8  554.77  5155.1  555.27  5189.3  555.88  5210.2  557.44
  5225.0  557.61  5238.5  559.19  5260.8  560.54  5324.0  562.56  5338.3  563.60
  5368.0  564.58  5388.9  565.94  5490.1  570.33  5525.8  572.31  5604.7  574.77
#Mann=5,-1,0
  4435.4    0.07       0  4905.7    0.05       0  5094.1    0.07       0
  5151.1    0.05       0  5155.1    0.07       0
Bank Sta=5151.1,5155.1
Exp/Cntr=0.3,0.1

Type RM Length L Ch R = 1,599,0,0,0
BEGIN DESCRIPTION:
A19192
END DESCRIPTION:
XS GIS Cut Line= 4
      2269646.33     13754814.49      2268860.78     13754905.63
      2268431.09     13755092.26      2268274.86     13755396.05
#Sta/Elev= 30
  4273.9  555.82  4375.2  554.34  4396.0  553.86  4416.2  554.42  4456.4  553.98
  4516.7  554.96  4567.2  554.93  4607.5  555.89  4698.1  555.85  4778.6  556.60
  4850.8  556.38  4899.4  553.38  4919.5  552.82  4939.7  553.35  4988.0  552.66
  4988.3  552.16  4991.8  552.16  4992.0  552.66  5088.6  553.28  5396.2  554.07
  5518.0  556.10  5583.1  557.85  5682.5  559.09  5777.1  563.37  5799.2  563.36
  5815.8  564.64  5821.4  564.19  5838.0  565.55  5843.6  565.31  5874.8  566.54
#Mann=8,-1,0
  4273.9    0.05       0  4375.2    0.07       0  4516.7    0.05       0
  4850.8    0.07       0  4988.0    0.05       0  4992.0    0.07       0
  5088.6    0.05       0  5396.2    0.07       0
Bank Sta=4988,4992
Exp/Cntr=0.3,0.1

Chan Stop Cuts=-1