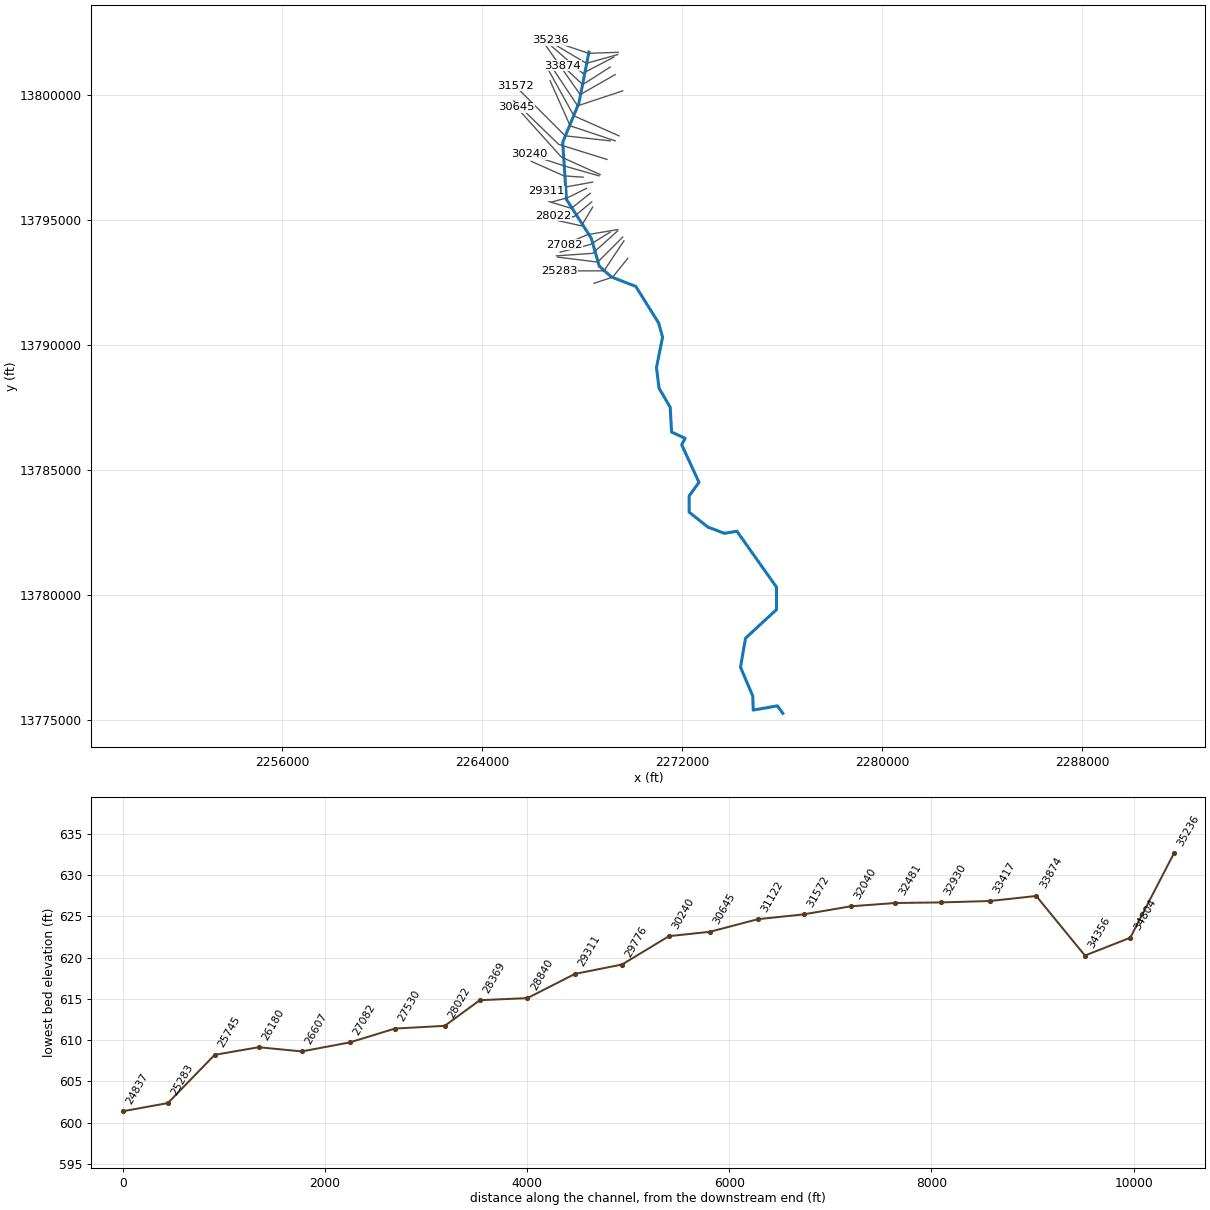
--- GUADALUPE TRIBUTARY 20.prj (project) ---

Proj Title=GUADALUPE TRIBUTARY 20 Base Level Engineering
Current Plan=p01
Default Exp/Contr=0.3,0.1
English Units
Geom File=g01
Flow File=f01
Plan File=p01
Y Axis Title=Elevation
X Axis Title(PF)=Main Channel Distance
X Axis Title(XS)=Station
BEGIN DESCRIPTION:
GUADALUPE TRIBUTARY 20
END DESCRIPTION:
DSS Export Rating Curves= 0
DSS Export Rating Curve Sorted= 0
DSS Export Volume Flow Curves= 0
DXF OffsetX= 0
DXF OffsetY= 0
DXF ScaleX= 1
DXF ScaleY= 10

--- GUADALUPE TRIBUTARY 20.p01 (plan) ---

Plan Title=Multiple Run
Program Version=4.10
Short Identifier=Multiple
Geom File=g01
Flow File=f01
Subcritical Flow
K Sum by GR= 0
Std Step Tol= 0.01
Critical Tol= 0.01
Num of Std Step Trials= 20
Max Error Tol= 0.3
Flow Tol Ratio= 0.001
Split Flow NTrial= 30
Split Flow Tol= 0.02
Split Flow Ratio= 0.02
Log Output Level= 0
Friction Slope Method= 1
Unsteady Friction Slope Method= 2
Unsteady Bridges Friction Slope Method= 1
Parabolic Critical Depth
Global Vel Dist= 1 , 1 , 1
Global Log Level= 0
CheckData=True
Encroach Param=-1 ,0,0, 0
BEGIN DESCRIPTION:
Multiple Run
END DESCRIPTION:
Computation Interval=1HOUR
Output Interval=1HOUR
Run HTab= 0
Run UNet= 0
Run PostProcess= 0
Run WQNet= 0
UNET Theta= 1
UNET Theta Warmup= 1
UNET ZTol= 0.02
UNET ZSATol= 0.05
UNET MxIter= 20
UNET MaxInSteps= 0
UNET DtIC= 0
UNET DtMin= 0
UNET MaxCRTS= 20
UNET WFStab= 2
UNET SFStab= 1
UNET WFX= 1
UNET SFX= 1
UNET DSS MLevel= 4
UNET DZMax Abort= 100
UNET Convert EG Bridges= 0
UNET Use Existing IB Tables=-1
UNET Froude Reduction=False
UNET Froude Limit= 1
UNET Froude Power= 10
UNET Time Slicing=0,0, 5
UNET Junction Losses=0
Instantaneous Interval=1HOUR
Write IC File= 0
Write IC File at Sim End=0
Echo Input=False
Echo Parameters=False
Echo Output=False
Write Detailed= 0
WQ AD Non Conservative
WQ ULTIMATE=-1
WQ Max Comp Step=1HOUR
WQ Output Interval=15MIN
WQ Output Selected Increments= 0
WQ Output face flow=0
WQ Output face velocity=0
WQ Output face area=0
WQ Output face dispersion=0
WQ Output cell volume=0
WQ Output cell surface area=0
WQ Output cell continuity=0
WQ Output cumulative cell continuity=0
WQ Output face conc=0
WQ Output face dconc_dx=0
WQ Output face courant=0
WQ Output face peclet=0
WQ Output face adv mass=0
WQ Output face disp mass=0
WQ Output cell mass=0
WQ Output cell source sink temp=0
WQ Output cell source sink nsm=0
WQ Output MaxMinRange=-1
WQ Daily Max Min Mean=-1
WQ Daily Range=0
WQ Daily Time=0
WQ Create Restart=0
WQ Fixed Restart=0
WQ System Summary=0
WQ Use Fixed Temperature=0
Sorting and Armoring Iterations= 10
XS Update Threshold= 0.02
Hydraulics Update Threshold= 0.02
Energy Slope Method= 1
Volume Change Method= 0
XS Weighting Method= 0
Number of US Weighted Cross Sections= 1
Number of DS Weighted Cross Sections= 1
Upstream XS Weight=0.25
Main XS Weight=0.5
Downstream XS Weight=0.25
Number of DS XS's Weighted with US Boundary= 1
Upstream Boundary Weight= 1
Weight of XSs Associated with US Boundary= 0
Number of US XS's Weighted with DS Boundary= 1
Downstream Boundary Weight= 0.5
Weight of XSs Associated with DS Boundary= 0.5
Sediment Output Level= 4
Mass or Volume Output= 0
Output Increment Type= 1
Profile and TS Output Increment= 10
XS Output Flag= 0
XS Output Increment= 10
Disregard all LS=0
Disregard all Conn=0
Disregard all Breaches=0
Disregard all Pumps=0

--- GUADALUPE TRIBUTARY 20.f01 (steady flow) ---

Flow Title=Multiple
Program Version=4.10
Number of Profiles= 7
Profile Names=10-year,25-year,50-year,1pct_min,100-year,1pct_plu,500-year
River Rch & RM=GUADALUPE TRIBUT,Reach-1         ,35236
     832    1349    1817    1182    2359    4707    3939
River Rch & RM=GUADALUPE TRIBUT,Reach-1         ,31572
     874    1407    1883    1217    2429    4846    3999
River Rch & RM=GUADALUPE TRIBUT,Reach-1         ,27530
    1210    1982    2688    1758    3507    6997    5912
River Rch & RM=GUADALUPE TRIBUT,Reach-1         ,21192
    1493    2470    3372    2218    4426    8831    7554
River Rch & RM=GUADALUPE TRIBUT,Reach-1         ,17696
    1765    2946    4043    2674    5335   10644    9200
River Rch & RM=GUADALUPE TRIBUT,Reach-1         ,9231
    2718    4620    6421    4294    8568   17096   15118
Boundary for River Rch & Prof#=GUADALUPE TRIBUT,Reach-1         , 1
Up Type= 0
Dn Type= 3
Dn Slope=0.005
Boundary for River Rch & Prof#=GUADALUPE TRIBUT,Reach-1         , 2
Up Type= 0
Dn Type= 3
Dn Slope=0.005
Boundary for River Rch & Prof#=GUADALUPE TRIBUT,Reach-1         , 3
Up Type= 0
Dn Type= 3
Dn Slope=0.005
Boundary for River Rch & Prof#=GUADALUPE TRIBUT,Reach-1         , 4
Up Type= 0
Dn Type= 3
Dn Slope=0.005
Boundary for River Rch & Prof#=GUADALUPE TRIBUT,Reach-1         , 5
Up Type= 0
Dn Type= 3
Dn Slope=0.005
Boundary for River Rch & Prof#=GUADALUPE TRIBUT,Reach-1         , 6
Up Type= 0
Dn Type= 3
Dn Slope=0.005
Boundary for River Rch & Prof#=GUADALUPE TRIBUT,Reach-1         , 7
Up Type= 0
Dn Type= 3
Dn Slope=0.005
DSS Import GetInterval= 0
DSS Import GetPeak= 0
DSS Import FillOption= 0

--- GUADALUPE TRIBUTARY 20.g01 (geometry) ---

Geom Title=Existing Conditions
Program Version=4.10

River Reach=GUADALUPE TRIBUT,Reach-1
Reach XY= 30
        2268275.       13801725.      2267872.73     13799680.94
      2267226.11     13798114.45      2267377.27     13795830.94
      2268371.54      13794273.5      2268685.69     13793165.02
      2269172.55     13792730.46      2270148.41     13792352.56
      2271065.69     13790881.66      2271217.44       13790325.
      2270974.94     13789105.01       2271076.8     13788281.11
      2271522.94     13787519.14      2271578.53     13786526.45
      2272119.91      13786277.3      2271982.61     13786021.67
      2272674.07     13784514.85      2272282.85     13783978.23
      2272280.45     13783322.55      2273026.65     13782728.17
      2273690.27     13782475.37      2274188.24     13782561.88
      2275771.73     13780323.64      2275771.48     13779426.28
      2274533.16     13778281.05      2274332.59     13777125.01
      2274823.34     13775968.95      2274841.42      13775408.2
      2275809.79     13775574.49        2276025.       13775275.

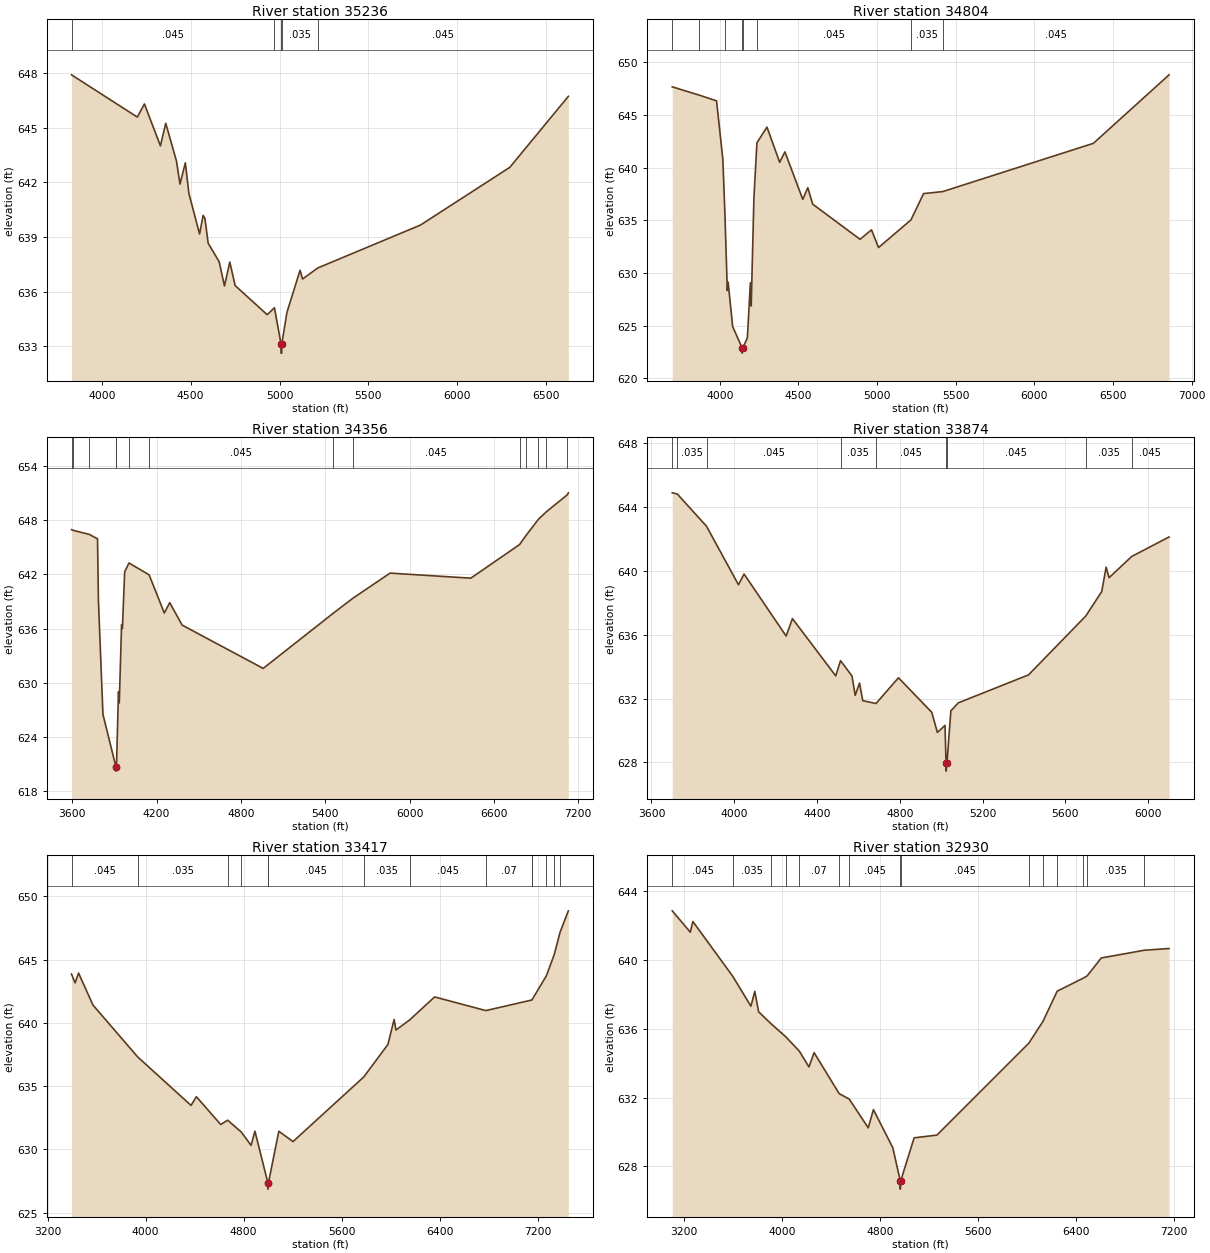
Type RM Length L Ch R = 1 ,35236   ,432,432,432
BEGIN DESCRIPTION:
A19215
END DESCRIPTION:
XS GIS Cut Line= 3
      2269444.85     13801715.73      2268252.22     13801675.98
      2266738.31     13802197.16
#Sta/Elev= 30
  3830.1   647.9  4200.2  645.58  4240.2   646.3  4330.2     644  4360.2  645.24
  4420.3  643.17  4440.3   641.9  4470.3  643.07  4490.3  641.39  4550.4  639.16
  4570.4  640.18  4580.4  640.02  4598.9  638.65  4660.4  637.64  4690.4  636.31
  4720.4  637.62  4750.5  636.33  4930.6  634.73  4971.5  635.11  5008.6  633.12
  5008.9  632.62  5012.4  632.62  5012.7  633.12  5041.6  634.85  5115.6  637.17
  5129.7  636.69    5216   637.3  5792.5  639.65  6295.1  642.82  6624.5  646.72
#Mann= 5 ,-1 , 0
  3830.1    .045       0  4971.5    .035       0  5008.6    .035       0
  5012.7    .035       0    5216    .045       0
Bank Sta=5008.6,5012.7
XS Rating Curve= 0 ,0
Exp/Cntr=0.3,0.1

Type RM Length L Ch R = 1 ,34804   ,448,448,448
BEGIN DESCRIPTION:
GUADALUPE TRIBUTARY 20 65.0
END DESCRIPTION:
XS GIS Cut Line= 3
      2269424.97     13801624.99        2268175.       13801275.
      2266575.02     13802224.99
#Sta/Elev= 30
  3697.7  647.67  3867.9  646.89  3979.5  646.34  4019.6  640.77  4033.3  635.35
  4047.8  628.34    4053  629.14  4081.9  624.92  4142.1   622.9  4142.4   622.4
  4146.4   622.9  4175.4  623.85  4194.6  629.08  4199.8  626.87  4216.9  637.09
  4236.1  642.36    4300  643.85  4380.8  640.51  4414.2   641.5  4527.7  636.99
  4559.6   638.1  4590.7  636.54  4891.9   633.2  4964.6   634.1  5009.4  632.42
  5215.3  635.04  5295.8  637.54  5417.6  637.73  6375.3  642.31  6856.5  648.81
#Mann= 8 ,-1 , 0
  3697.7    .035       0  3867.9    .045       0  4033.3     .07       0
  4142.1    .045       0  4146.4     .07       0  4236.1    .045       0
  5215.3    .035       0  5417.6    .045       0
Bank Sta=4142.1,4146.4
XS Rating Curve= 0 ,0
Exp/Cntr=0.3,0.1

Type RM Length L Ch R = 1 ,34356   ,482,482,482
BEGIN DESCRIPTION:
GUADALUPE TRIBUTARY 20 64.0
END DESCRIPTION:
XS GIS Cut Line= 3
      2269274.97     13801524.98        2268025.       13800875.
        2266425.       13802275.
#Sta/Elev= 30
  3595.2  646.95  3608.9  646.86  3722.5  646.42  3780.3  645.93  3786.8  639.08
  3818.9  626.52  3910.8  620.74    3911  620.24  3915.1  620.74  3929.4  629.03
    3935  627.78  3951.5  636.44  3957.1  636.01  3973.6  642.28  4003.8  643.26
  4147.4  641.95  4255.4  637.73    4294  638.87  4382.4  636.39    4959   631.6
    5458  637.71    5597  639.36  5861.6  642.14  6435.8  641.58  6783.1   645.3
  6827.9  646.28  6917.5   648.1  6972.4  648.91  7122.4   650.8  7130.1  651.02
#Mann= 14 ,-1 , 0
  3595.2    .035       0  3608.9    .045       0  3722.5     .07       0
  3910.8    .045       0  3915.1     .07       0  4003.8    .035       0
  4147.4    .045       0    5458    .035       0    5597    .045       0
  6783.1    .035       0  6827.9    .045       0  6917.5    .035       0
  6972.4    .045       0  7122.4    .035       0
Bank Sta=3910.8,3915.1
XS Rating Curve= 0 ,0
Exp/Cntr=0.3,0.1

Type RM Length L Ch R = 1 ,33874   ,457,457,457
BEGIN DESCRIPTION:
GUADALUPE TRIBUTARY 20 63.0
END DESCRIPTION:
XS GIS Cut Line= 3
      2269124.98     13801124.99        2268025.       13800425.
        2267225.       13801175.
#Sta/Elev= 30
  3700.5  644.87  3724.7   644.8  3866.1  642.78  4020.5  639.12  4047.6  639.79
  4250.8  635.91  4281.3     637  4490.4  633.42  4513.6  634.37  4569.1  633.41
  4584.4   632.2  4605.5  632.97  4620.8  631.87  4684.9  631.69  4793.5   633.3
  4954.4  631.14  4981.5  629.88  5018.3  630.32  5023.4  627.96  5023.7  627.46
  5027.8  627.96  5046.6  631.23  5082.2  631.73  5421.7  633.48  5698.2  637.16
  5775.4  638.69  5796.8  640.22    5811  639.56  5920.4  640.89  6100.9  642.11
#Mann= 9 ,-1 , 0
  3700.5     .07       0  3724.7    .035       0  3866.1    .045       0
  4513.6    .035       0  4684.9    .045       0  5023.4    .045       0
  5027.8    .045       0  5698.2    .035       0  5920.4    .045       0
Bank Sta=5023.4,5027.8
XS Rating Curve= 0 ,0
Exp/Cntr=0.3,0.1

Type RM Length L Ch R = 1 ,33417   ,487,487,487
BEGIN DESCRIPTION:
GUADALUPE TRIBUTARY 20 62.0
END DESCRIPTION:
XS GIS Cut Line= 3
      2269324.99       13800825.        2267925.       13800025.
      2266524.97     13802025.04
#Sta/Elev= 30
  3395.3  643.86  3424.8  643.16  3452.9  643.94  3570.2  641.41  3935.7   637.3
  4370.7  633.47  4413.9  634.16  4612.6  631.96  4669.4   632.3    4781  631.36
  4860.2  630.31  4891.8  631.43  4997.5  627.35  4997.8  626.85  5002.2  627.35
  5086.7  631.43  5202.6  630.61  5779.7  635.72  5976.9  638.29  6027.4  640.27
  6042.3  639.43  6155.3  640.24  6357.9  642.05  6775.7  640.97  7152.4  641.81
  7154.4  641.85  7270.1  643.73  7333.8   645.4  7381.5  647.17  7449.1  648.86
#Mann= 14 ,-1 , 0
  3395.3    .045       0  3935.7    .035       0  4669.4     .07       0
    4781    .045       0  4997.5    .045       0  5002.2    .045       0
  5779.7    .035       0  6155.3    .045       0  6775.7     .07       0
  7152.4     .05       0  7154.4     .07       0  7270.1     .05       0
  7333.8     .07       0  7381.5     .05       0
Bank Sta=4997.5,5002.2
XS Rating Curve= 0 ,0
Exp/Cntr=0.3,0.1

Type RM Length L Ch R = 1 ,32930   ,449,449,449
BEGIN DESCRIPTION:
GUADALUPE TRIBUTARY 20 61.0
END DESCRIPTION:
XS GIS Cut Line= 3
      2269625.04     13800175.01        2267825.       13799575.
      2266625.02     13801374.97
#Sta/Elev= 30
  3102.6  642.85  3250.2  641.61  3271.3  642.23  3597.8  639.04  3745.6  637.31
  3777.3  638.17  3808.9  636.98  3913.2  636.27  4029.2  635.54  4141.1   634.7
    4220  633.78  4262.1  634.61    4467  632.23  4549.3  631.91  4704.9  630.24
    4747   631.3  4905.1  629.09    4966  627.18  4966.3  626.68  4970.8  627.18
  5079.6  629.66  5265.9  629.82  6016.8  635.16  6132.8  636.43  6248.7  638.18
  6462.1  638.94  6493.6  639.07    6609  640.11  6960.2  640.56  7163.3  640.66
#Mann= 15 ,-1 , 0
  3102.6    .045       0  3597.8    .035       0  3913.2     .07       0
  4029.2    .035       0  4141.1     .07       0    4467    .035       0
  4549.3    .045       0    4966    .045       0  4970.8    .045       0
  6016.8    .035       0  6132.8    .045       0  6248.7    .035       0
  6462.1    .045       0  6493.6    .035       0  6960.2    .045       0
Bank Sta=4966,4970.8
XS Rating Curve= 0 ,0
Exp/Cntr=0.3,0.1

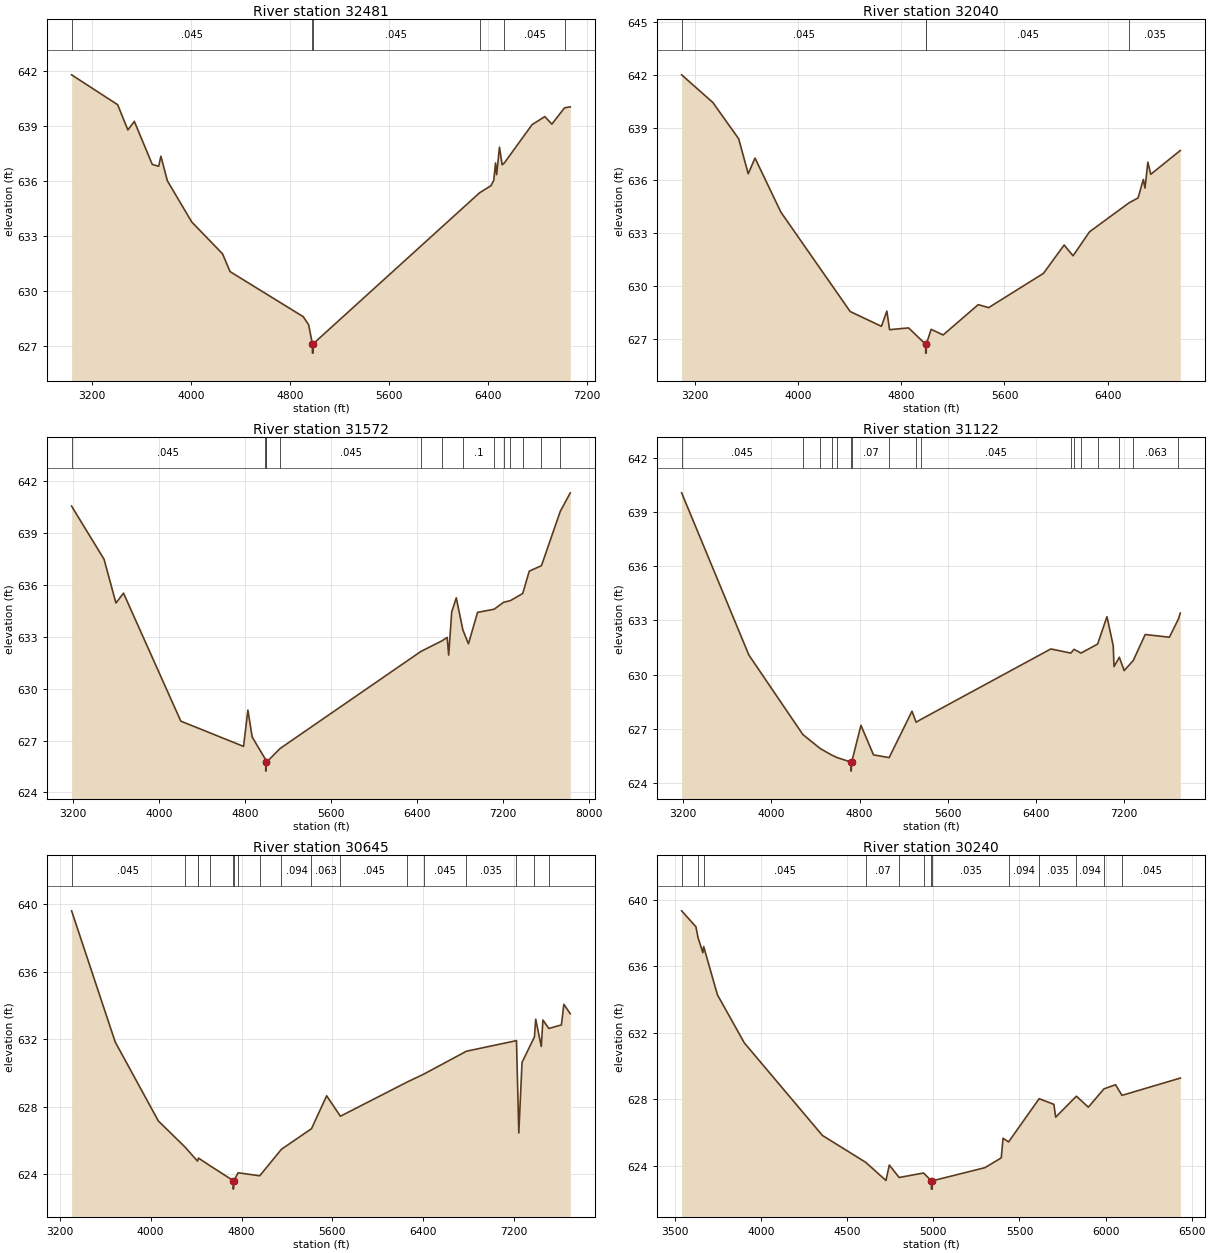
Type RM Length L Ch R = 1 ,32481   ,441,441,441
BEGIN DESCRIPTION:
GUADALUPE TRIBUTARY 20 60.0
END DESCRIPTION:
XS GIS Cut Line= 3
      2269474.98     13798375.01        2267675.       13799175.
      2266674.99     13800975.02
#Sta/Elev= 30
  3034.8   641.8  3406.8  640.17  3489.6  638.79  3541.6  639.26  3686.6  636.91
  3738.6  636.81  3756.3  637.36  3808.3  636.02  4005.3  633.77  4254.3  632.03
  4315.1  631.06  4906.1   628.6  4949.8  628.16  4980.2  627.11  4980.6  626.61
  4984.8  626.61  4985.1  627.11  6330.6  635.36  6423.1  635.75  6445.9  636.05
  6459.7  636.99  6468.8  636.35  6491.7  637.85  6513.4  636.89    6531  636.99
  6754.8  639.08  6857.8  639.52    6915  639.11  7017.3     640  7063.7  640.05
#Mann= 6 ,-1 , 0
  3034.8    .045       0  4980.2    .045       0  4985.1    .045       0
  6330.6    .035       0    6531    .045       0  7017.3    .035       0
Bank Sta=4980.2,4985.1
XS Rating Curve= 0 ,0
Exp/Cntr=0.3,0.1

Type RM Length L Ch R = 1 ,32040   ,468,468,468
BEGIN DESCRIPTION:
GUADALUPE TRIBUTARY 20 59.0
END DESCRIPTION:
XS GIS Cut Line= 3
      2269324.95     13798175.02        2267525.       13798775.
        2266725.     13800575.01
#Sta/Elev= 30
  3096.6  641.99    3339  640.42  3539.3  638.36  3613.1  636.38  3665.8  637.27
    3866  634.21  4403.6  628.57  4646.1  627.73  4688.2  628.59  4709.3  627.54
  4856.9  627.64  4988.8  626.71  4989.2  626.21  4993.4  626.21  4993.7  626.71
  5031.5  627.56  5124.6  627.24  5396.8  628.96  5477.5  628.79  5902.2  630.73
  6062.9  632.34    6132  631.73  6259.9  633.09  6565.9  634.73  6636.1  635.01
  6677.1  636.06  6690.1  635.57    6712  637.04  6734.6  636.35  6963.7   637.7
#Mann= 4 ,-1 , 0
  3096.6    .045       0  4988.8    .045       0  4993.7    .045       0
  6565.9    .035       0
Bank Sta=4988.8,4993.7
XS Rating Curve= 0 ,0
Exp/Cntr=0.3,0.1

Type RM Length L Ch R = 1 ,31572   ,450,450,450
BEGIN DESCRIPTION:
GUADALUPE TRIBUTARY 20 58.0
END DESCRIPTION:
XS GIS Cut Line= 3
      2269125.02       13798175.        2267325.       13798375.
      2265325.02     13800374.98
#Sta/Elev= 30
  3188.9  640.55  3490.8  637.48  3601.4  634.95  3671.9  635.52  4205.1  628.12
  4788.7  626.66  4828.9  628.76  4869.2   627.2  4987.9  625.96  4994.9  625.73
  4995.3  625.23  5000.1  625.73  5128.8  626.54  6438.8  632.15  6633.4  632.76
  6682.9  632.96  6697.1  631.94  6725.3  634.43  6767.8  635.25    6829   633.4
  6880.9  632.59  6965.8  634.41  7120.1  634.59  7207.7  634.99  7271.9  635.09
  7385.9   635.5  7446.6  636.79  7560.3  637.11  7735.4  640.25  7828.4  641.32
#Mann= 14 ,-1 , 0
  3188.9    .045       0  4987.9    .035       0  4994.9    .035       0
  5000.1    .035       0  5128.8    .045       0  6438.8    .035       0
  6633.4    .094       0    6829      .1       0  7120.1    .094       0
  7207.7      .1       0  7271.9    .094       0  7385.9    .063       0
  7560.3     .07       0  7735.4    .035       0
Bank Sta=4994.9,5000.1
XS Rating Curve= 0 ,0
Exp/Cntr=0.3,0.1

Type RM Length L Ch R = 1 ,31122   ,477,477,477
BEGIN DESCRIPTION:
GUADALUPE TRIBUTARY 20 57.0
END DESCRIPTION:
XS GIS Cut Line= 3
      2268997.62     13797432.07      2267064.52     13798033.37
        2265275.       13799775.
#Sta/Elev= 30
    3187  640.07  3797.2  631.08  4286.1  626.68  4444.1   625.9  4548.2  625.54
  4596.9   625.4  4723.7  625.15  4724.1  624.65    4729  625.15    4813  627.19
  4926.9  625.55  5068.8   625.4    5276  627.97  5313.6  627.36    5361  627.53
  6534.8  631.42    6716  631.19  6745.2   631.4  6807.7  631.19  6958.8  631.69
  7043.8  633.21  7100.4   631.6  7107.6  630.44    7156  630.96  7199.4  630.22
  7282.2  630.78  7390.3  632.22  7609.7  632.07  7691.6  633.08  7708.6  633.41
#Mann= 17 ,-1 , 0
    3187    .045       0  4286.1    .035       0  4444.1     .07       0
  4548.2    .045       0  4596.9     .07       0  4723.7     .05       0
    4729     .07       0  5068.8    .094       0  5313.6    .063       0
    5361    .045       0    6716    .035       0  6745.2    .045       0
  6807.7    .035       0  6958.8    .063       0    7156    .094       0
  7282.2    .063       0  7691.6    .094       0
Bank Sta=4723.7,4729
XS Rating Curve= 0 ,0
Exp/Cntr=0.3,0.1

Type RM Length L Ch R = 1 ,30645   ,405,405,405
BEGIN DESCRIPTION:
GUADALUPE TRIBUTARY 20 56.0
END DESCRIPTION:
XS GIS Cut Line= 3
      2268724.99     13796825.01        2267175.       13797525.
      2265375.03     13799524.97
#Sta/Elev= 30
  3303.8  639.61  3687.8  631.84  4067.7  627.16  4303.2  625.61  4412.7  624.78
  4421.2  624.96  4522.3  624.51  4727.8  623.62  4728.2  623.12  4733.1  623.62
  4770.3  624.09  4960.4  623.91  5151.5  625.48  5416.2   626.7  5549.8  628.65
    5671  627.44  6257.3  629.46  6406.8  629.94  6780.2  631.29  7221.5  631.92
  7241.9  626.45  7270.3  630.63  7379.6  632.14  7390.7  633.19    7440  631.57
  7454.2  633.14  7506.3  632.64  7617.1  632.85  7638.8  634.07  7695.2  633.51
#Mann= 18 ,-1 , 0
  3303.8    .045       0  4303.2    .035       0  4412.7     .07       0
  4421.2    .045       0  4522.3     .07       0  4727.8    .035       0
  4733.1     .07       0  4770.3    .045       0  4960.4    .035       0
  5151.5    .094       0  5416.2    .063       0    5671    .045       0
  6257.3    .035       0  6406.8    .045       0  6780.2    .035       0
  7221.5    .063       0  7379.6    .094       0  7506.3    .063       0
Bank Sta=4727.8,4733.1
XS Rating Curve= 0 ,0
Exp/Cntr=0.3,0.1

Type RM Length L Ch R = 1 ,30240   ,464,464,464
BEGIN DESCRIPTION:
GUADALUPE TRIBUTARY 20 55.0
END DESCRIPTION:
XS GIS Cut Line= 3
      2268674.98     13796775.01        2267275.       13797175.
      2265908.32     13797630.56
#Sta/Elev= 30
  3537.7  639.33  3620.9  638.37  3632.8  637.73  3661.2  636.81  3665.8  637.18
  3745.7  634.28  3901.7  631.39  4355.4  625.82  4607.4   624.2  4724.6  623.11
  4744.1  624.04  4801.1  623.29  4942.8  623.56  4988.3  623.09  4988.7  622.59
  4993.4  622.59  4993.9  623.09  5299.4  623.88  5394.3  624.47  5404.8  625.65
  5436.9  625.43  5614.4  628.03  5699.9  627.69  5710.5  626.92  5830.7  628.18
  5900.2  627.52  5990.7  628.62  6058.3  628.87  6095.5  628.23  6434.3  629.27
#Mann= 13 ,-1 , 0
  3537.7    .045       0  3632.8    .035       0  3665.8    .045       0
  4607.4     .07       0  4801.1    .045       0  4942.8    .035       0
  4988.3    .035       0  4993.9    .035       0  5436.9    .094       0
  5614.4    .035       0  5830.7    .094       0  5990.7    .035       0
  6095.5    .045       0
Bank Sta=4988.3,4993.9
XS Rating Curve= 0 ,0
Exp/Cntr=0.3,0.1

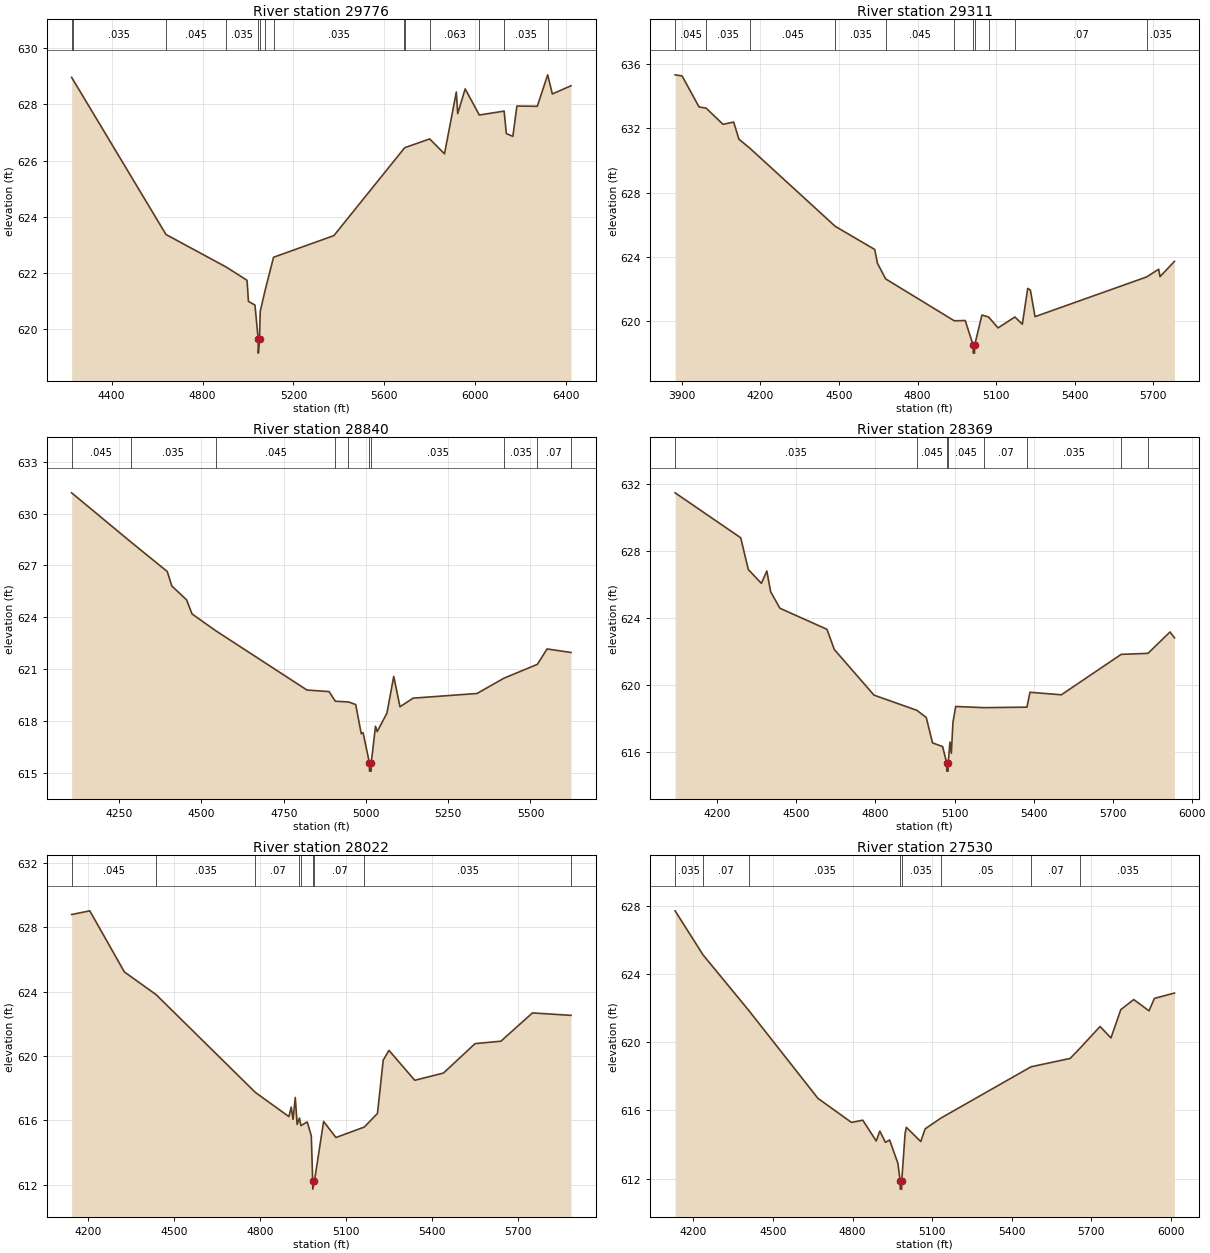
Type RM Length L Ch R = 1 ,29776   ,465,465,465
BEGIN DESCRIPTION:
GUADALUPE TRIBUTARY 20 54.0
END DESCRIPTION:
XS GIS Cut Line= 3
      2268042.51     13796720.18        2267275.       13796775.
      2265969.32      13797355.3
#Sta/Elev= 30
  4223.7  628.96  4228.9  628.89  4639.1  623.37  4904.7  622.21  4995.9  621.74
  5002.1  620.99  5030.8  620.86    5045  619.65  5045.5  619.15  5050.8  619.65
    5054  620.64  5076.5  621.42  5112.6  622.56  5378.2  623.33  5686.1  626.42
  5690.8  626.46    5800  626.77  5865.2  626.24  5917.2  628.44  5923.3  627.67
  5956.2  628.55  6018.5  627.62  6127.7  627.76  6137.4  626.96  6166.1  626.86
  6183.9  627.94  6273.5  627.93  6319.4  629.05  6339.9  628.37    6422  628.66
#Mann= 14 ,-1 , 0
  4223.7    .045       0  4228.9    .035       0  4639.1    .045       0
  4904.7    .035       0    5045    .035       0  5050.8    .035       0
  5076.5     .07       0  5112.6    .035       0  5686.1    .063       0
  5690.8    .094       0    5800    .063       0  6018.5    .094       0
  6127.7    .035       0  6319.4    .045       0
Bank Sta=5045,5050.8
XS Rating Curve= 0 ,0
Exp/Cntr=0.3,0.1

Type RM Length L Ch R = 1 ,29311   ,471,471,471
BEGIN DESCRIPTION:
GUADALUPE TRIBUTARY 20 53.0
END DESCRIPTION:
XS GIS Cut Line= 4
      2268425.01       13796525.        2267325.       13796325.
       2267306.3     13796335.39      2266560.04     13796156.24
#Sta/Elev= 30
  3874.4  635.34  3901.1  635.27  3965.9  633.34  3992.7  633.27  4057.4  632.26
    4098   632.4  4118.3  631.33  4159.4  630.78    4486  625.91  4636.7  624.47
  4646.9  623.62  4678.4  622.64  4940.7  620.03  4982.3  620.05  5012.4  618.52
  5012.9  618.02  5017.8  618.02  5018.3  618.52    5046  620.39  5071.3  620.27
  5107.7  619.59  5171.9  620.27  5200.3  619.82  5220.9  622.05  5231.1  621.94
  5248.8  620.29  5674.8  622.76    5721  623.24  5726.1  622.78  5781.3  623.73
#Mann= 11 ,-1 , 0
  3874.4    .045       0  3992.7    .035       0  4159.4    .045       0
    4486    .035       0  4678.4    .045       0  4940.7     .07       0
  5012.4     .05       0  5018.3     .07       0  5071.3    .035       0
  5171.9     .07       0  5674.8    .035       0
Bank Sta=5012.4,5018.3
XS Rating Curve= 0 ,0
Exp/Cntr=0.3,0.1

Type RM Length L Ch R = 1 ,28840   ,471,471,471
BEGIN DESCRIPTION:
GUADALUPE TRIBUTARY 20 52.0
END DESCRIPTION:
XS GIS Cut Line= 4
      2268174.99       13796275.        2267375.       13795875.
      2267360.54     13795883.68      2266774.77     13795725.24
#Sta/Elev= 30
  4105.2  631.21  4285.4  628.36  4395.9  626.65  4409.9  625.81  4454.6  625.01
  4471.3  624.19  4543.1  623.22  4820.7  619.78  4887.8  619.69  4906.9  619.13
  4946.8  619.09  4968.9  618.94  4985.6  617.25  4991.2  617.31  5010.3  615.58
  5010.8  615.08  5015.7  615.08  5016.2  615.58    5029  617.68  5034.2  617.37
  5063.7  618.44  5084.4  620.57  5103.5  618.81  5143.4  619.31  5337.6  619.58
  5419.9  620.47  5521.2  621.27  5550.5  622.16  5622.4  621.96  5623.3  621.96
#Mann= 10 ,-1 , 0
  4105.2    .045       0  4285.4    .035       0  4543.1    .045       0
  4906.9     .07       0  4946.8    .035       0  5010.3    .035       0
  5016.2    .035       0  5419.9    .035       0  5521.2     .07       0
  5622.4    .035       0
Bank Sta=5010.3,5016.2
XS Rating Curve= 0 ,0
Exp/Cntr=0.3,0.1

Type RM Length L Ch R = 1 ,28369   ,347,347,347
BEGIN DESCRIPTION:
GUADALUPE TRIBUTARY 20 51.0
END DESCRIPTION:
XS GIS Cut Line= 3
      2268325.03     13796075.02        2267575.       13795475.
      2266679.63     13795743.61
#Sta/Elev= 30
  4039.5  631.49  4288.5   628.8  4317.3   626.9  4366.9  626.07  4387.7  626.81
  4402.1  625.57  4437.3  624.58  4615.8  623.32  4643.8  622.11  4794.3  619.38
  4957.1  618.47  4992.8  618.04  5016.5  616.52  5054.8   616.3  5070.1  615.33
  5070.6  614.83  5075.6  614.83  5076.1  615.33  5082.7  616.57  5087.9   615.9
    5094  617.75  5104.4   618.7  5211.7  618.63  5374.9  618.66  5386.3  619.55
  5505.5   619.4  5732.5  621.82  5834.2  621.88  5917.9  623.16  5934.8  622.81
#Mann= 8 ,-1 , 0
  4039.5    .035       0  4957.1    .045       0  5070.1    .045       0
  5076.1    .045       0  5211.7     .07       0  5374.9    .035       0
  5732.5     .07       0  5834.2    .035       0
Bank Sta=5070.1,5076.1
XS Rating Curve= 0 ,0
Exp/Cntr=0.3,0.1

Type RM Length L Ch R = 1 ,28022   ,492,492,492
BEGIN DESCRIPTION:
A19214
END DESCRIPTION:
XS GIS Cut Line= 3
      2268386.42     13795732.53       2267670.8     13795136.17
      2266860.75     13795185.87
#Sta/Elev= 30
  4141.9   628.8  4205.3  629.03    4326  625.23  4436.6  623.82    4783  617.74
  4900.4  616.23  4908.3  616.82  4914.8  616.06  4922.6  617.42  4929.1  615.74
  4937.1  616.14  4942.4  615.67  4964.2   615.9  4978.5  615.04  4983.4  612.22
  4983.9  611.72  4989.4  612.22  5021.5  615.93  5064.5  614.93  5163.4  615.58
  5209.5  616.43  5229.5  619.74  5249.6  620.35  5339.7  618.49  5439.9  618.94
  5550.1  620.77  5640.3  620.92  5750.5  622.68  5884.2  622.53    5885  622.53
#Mann= 9 ,-1 , 0
  4141.9    .045       0  4436.6    .035       0    4783     .07       0
  4937.1    .035       0  4942.4     .07       0  4983.4     .05       0
  4989.4     .07       0  5163.4    .035       0  5884.2    .094       0
Bank Sta=4983.4,4989.4
XS Rating Curve= 0 ,0
Exp/Cntr=0.3,0.1

Type RM Length L Ch R = 1 ,27530   ,448,448,448
BEGIN DESCRIPTION:
GUADALUPE TRIBUTARY 20 49.0
END DESCRIPTION:
XS GIS Cut Line= 3
      2268425.02     13795525.03        2267975.       13794775.
      2266991.27     13794993.61
#Sta/Elev= 30
    4131   627.7  4236.3  625.12  4408.8  621.86  4669.4  616.71  4795.8   615.3
  4838.5  615.43  4889.1  614.21  4902.7  614.79    4924  614.13  4939.6  614.27
  4970.7  612.91  4979.3  611.89  4979.8  611.39  4984.9  611.39  4985.4  611.89
  4997.9  614.65  5002.8  615.01  5056.9  614.18  5073.5  614.92  5132.5  615.55
  5472.7  618.56  5620.3  619.05  5659.1  619.68    5733  620.92    5774  620.25
  5811.1  621.91  5859.8   622.5  5917.4  621.84  5937.9  622.57  6013.4  622.88
#Mann= 8 ,-1 , 0
    4131    .035       0  4236.3     .07       0  4408.8    .035       0
  4979.3    .035       0  4985.4    .035       0  5132.5     .05       0
  5472.7     .07       0  5659.1    .035       0
Bank Sta=4979.3,4985.4
XS Rating Curve= 0 ,0
Exp/Cntr=0.3,0.1

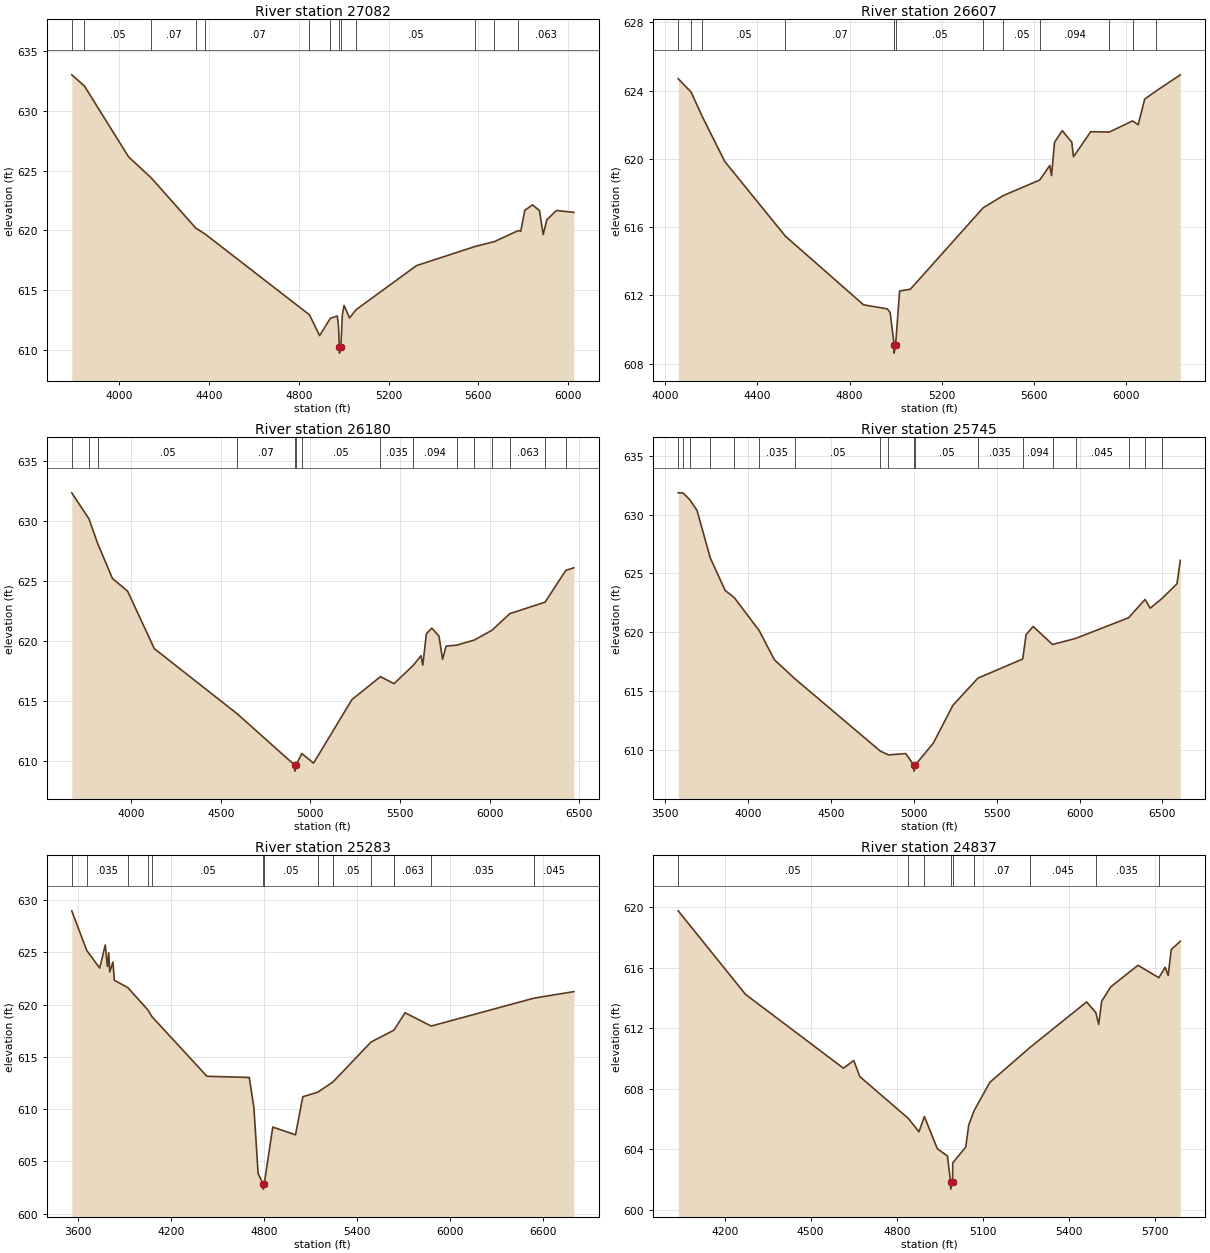
Type RM Length L Ch R = 1 ,27082   ,475,475,475
BEGIN DESCRIPTION:
GUADALUPE TRIBUTARY 20 48.0
END DESCRIPTION:
XS GIS Cut Line= 3
      2269424.99       13794625.        2268225.       13794425.
      2267283.99     13794026.88
#Sta/Elev= 30
  3787.9  633.04  3844.1  632.11  4041.3  626.16  4142.2   624.4  4340.9  620.19
  4382.6  619.69  4847.7  612.92  4892.9  611.18  4940.7  612.63  4971.5  612.82
  4976.6  612.09  4980.8  610.21  4981.3  609.71  4987.5  610.21  4994.3  612.94
  5001.9  613.71  5026.2  612.66  5055.3  613.35    5325  617.05    5586  618.65
  5672.2  619.06  5777.8  619.98  5789.4  619.93  5807.7  621.68  5842.2  622.14
  5873.1  621.65  5889.6  619.65  5905.7  620.89  5949.1  621.67  6026.2  621.51
#Mann= 13 ,-1 , 0
  3787.9    .035       0  3844.1     .05       0  4142.2     .07       0
  4340.9     .05       0  4382.6     .07       0  4847.7     .05       0
  4940.7     .07       0  4980.8     .05       0  4987.5     .07       0
  5055.3     .05       0    5586    .035       0  5672.2     .05       0
  5777.8    .063       0
Bank Sta=4980.8,4987.5
XS Rating Curve= 0 ,0
Exp/Cntr=0.3,0.1

Type RM Length L Ch R = 1 ,26607   ,427,427,427
BEGIN DESCRIPTION:
GUADALUPE TRIBUTARY 20 47.0
END DESCRIPTION:
XS GIS Cut Line= 3
      2269125.01     13794525.01        2268325.       13794025.
      2267125.04     13793725.01
#Sta/Elev= 30
  4056.1  624.69    4112  623.91  4159.3  622.51  4258.4  619.84  4521.5  615.47
  4860.9  611.45  4964.1  611.21  4976.5  610.99  4992.8  609.21  4993.2  609.12
  4993.7  608.62    5000  609.12  5017.5  612.26  5063.9  612.36  5380.2  617.13
  5466.5  617.84    5626  618.76  5669.5  619.61  5677.2  619.02  5690.1  620.96
  5723.6  621.65  5764.9  620.98  5772.6  620.12  5847.3  621.59  5928.3  621.57
  6029.1  622.22  6053.5     622  6081.8   623.5  6129.9  623.96  6236.4  624.92
#Mann= 13 ,-1 , 0
  4056.1     .05       0    4112     .07       0  4159.3     .05       0
  4521.5     .07       0  4992.8     .05       0  4993.2     .05       0
    5000     .05       0  5380.2    .035       0  5466.5     .05       0
    5626    .094       0  5928.3    .063       0  6029.1    .035       0
  6129.9    .094       0
Bank Sta=4993.2,5000
XS Rating Curve= 0 ,0
Exp/Cntr=0.3,0.1

Type RM Length L Ch R = 1 ,26180   ,435,435,435
BEGIN DESCRIPTION:
GUADALUPE TRIBUTARY 20 46.0
END DESCRIPTION:
XS GIS Cut Line= 3
      2269424.97     13794574.98        2268425.       13793675.
      2266974.97       13793575.
#Sta/Elev= 30
  3669.7  632.37  3765.5   630.2  3813.5  628.16  3896.5  625.22    3981  624.16
  4129.7  619.36  4591.7  613.92  4912.6  609.63  4913.1  609.13  4919.4  609.63
  4951.8   610.6  5017.5   609.8  5231.8  615.11  5390.6  617.02  5466.1  616.43
  5574.2  617.98  5616.5  618.77  5626.5  617.98  5646.5   620.6  5676.6  621.07
  5716.7  620.41  5736.7  618.47  5756.8  619.57  5815.7  619.65  5914.2  620.08
  6012.7   620.9  6111.3  622.28  6308.3  623.24  6423.5  625.89  6468.5  626.11
#Mann= 15 ,-1 , 0
  3669.7     .05       0  3765.5    .035       0  3813.5     .05       0
  4591.7     .07       0  4912.6     .05       0  4919.4     .07       0
  4951.8     .05       0  5390.6    .035       0  5574.2    .094       0
  5815.7    .035       0  5914.2    .045       0  6012.7    .094       0
  6111.3    .063       0  6308.3    .094       0  6423.5    .035       0
Bank Sta=4912.6,4919.4
XS Rating Curve= 0 ,0
Exp/Cntr=0.3,0.1

Type RM Length L Ch R = 1 ,25745   ,462,462,462
BEGIN DESCRIPTION:
GUADALUPE TRIBUTARY 20 45.0
END DESCRIPTION:
XS GIS Cut Line= 3
        2269625.       13794325.        2268625.       13793325.
      2267024.96       13793525.
#Sta/Elev= 30
  3580.7  631.85  3609.2  631.84  3649.1  631.29  3693.8  630.36  3773.8  626.32
  3863.5  623.56  3918.9  622.94  4068.8  620.14  4160.5  617.66  4283.2  616.06
  4798.3  609.91    4848  609.58  4952.5  609.69  5001.5   608.7    5002   608.2
  5008.4   608.7  5118.4  610.58  5236.8   613.8  5387.1   616.1  5657.5  617.73
  5677.7   619.8  5720.5  620.49  5837.4  618.96  5976.6  619.48  6295.2  621.23
  6394.9  622.79    6426  622.05  6494.5  622.84  6587.2  624.12  6607.4  626.11
#Mann= 18 ,-1 , 0
  3580.7     .05       0  3609.2    .035       0  3649.1     .07       0
  3773.8    .035       0  3918.9     .05       0  4068.8    .035       0
  4283.2     .05       0  4798.3     .07       0    4848     .05       0
  5001.5     .05       0  5008.4     .05       0  5387.1    .035       0
  5657.5    .094       0  5837.4    .035       0  5976.6    .045       0
  6295.2    .094       0  6394.9    .063       0  6494.5    .035       0
Bank Sta=5001.5,5008.4
XS Rating Curve= 0 ,0
Exp/Cntr=0.3,0.1

Type RM Length L Ch R = 1 ,25283   ,446,446,446
BEGIN DESCRIPTION:
GUADALUPE TRIBUTARY 20 44.0
END DESCRIPTION:
XS GIS Cut Line= 3
        2269675.     13794175.01        2268875.       13792975.
      2267075.03       13792975.
#Sta/Elev= 30
  3557.4  628.95  3654.8  625.15  3737.7  623.48  3773.7  625.69  3787.3  623.64
  3796.3  624.95  3802.3  623.11  3823.3  624.06  3832.3  622.32  3919.6  621.61
  4047.9   619.5  4075.2  618.84  4430.3  613.14  4703.7  613.03  4733.7  610.12
  4760.8  603.84  4793.4  602.86  4793.9  602.36  4800.3  602.86  4855.4  608.29
  5002.1  607.55  5049.6  611.19  5145.8  611.62  5244.3   612.6  5489.7  616.41
  5638.3  617.55  5709.6  619.21  5878.5  617.94  6543.1  620.61  6799.6  621.23
#Mann= 13 ,-1 , 0
  3557.4     .07       0  3654.8    .035       0  3919.6     .05       0
  4047.9    .035       0  4075.2     .05       0  4793.4     .05       0
  4800.3     .05       0  5145.8    .035       0  5244.3     .05       0
  5489.7    .035       0  5638.3    .063       0  5878.5    .035       0
  6543.1    .045       0
Bank Sta=4793.4,4800.3
XS Rating Curve= 0 ,0
Exp/Cntr=0.3,0.1

Type RM Length L Ch R = 1 ,24837   ,477,477,477
BEGIN DESCRIPTION:
GUADALUPE TRIBUTARY 20 43.0
END DESCRIPTION:
XS GIS Cut Line= 3
      2269825.03     13793475.03        2269225.       13792725.
      2268474.98     13792474.99
#Sta/Elev= 30
  4038.1  619.76  4272.7  614.24  4614.4  609.36  4650.4  609.87  4671.2  608.81
  4840.8  606.04  4877.7  605.16  4896.6  606.17  4941.8  604.04    4977  603.56
  4987.9  601.87  4988.4  601.37    4995  601.87  4995.4   603.1  5040.8  604.15
  5051.3  605.61  5070.4  606.57  5125.1  608.43  5265.5  610.74  5462.4  613.74
  5494.5  613.04  5504.6  612.26  5515.1  613.79  5546.7  614.74  5641.6  616.16
  5714.3  615.34  5736.5  616.03    5747  615.49  5757.6   617.2  5789.2  617.75
#Mann= 9 ,-1 , 0
  4038.1     .05       0  4840.8    .035       0  4896.6     .07       0
  4987.9    .045       0    4995     .07       0  5070.4     .07       0
  5265.5    .045       0  5494.5    .035       0  5714.3    .094       0
Bank Sta=4987.9,4995
XS Rating Curve= 0 ,0
Exp/Cntr=0.3,0.1