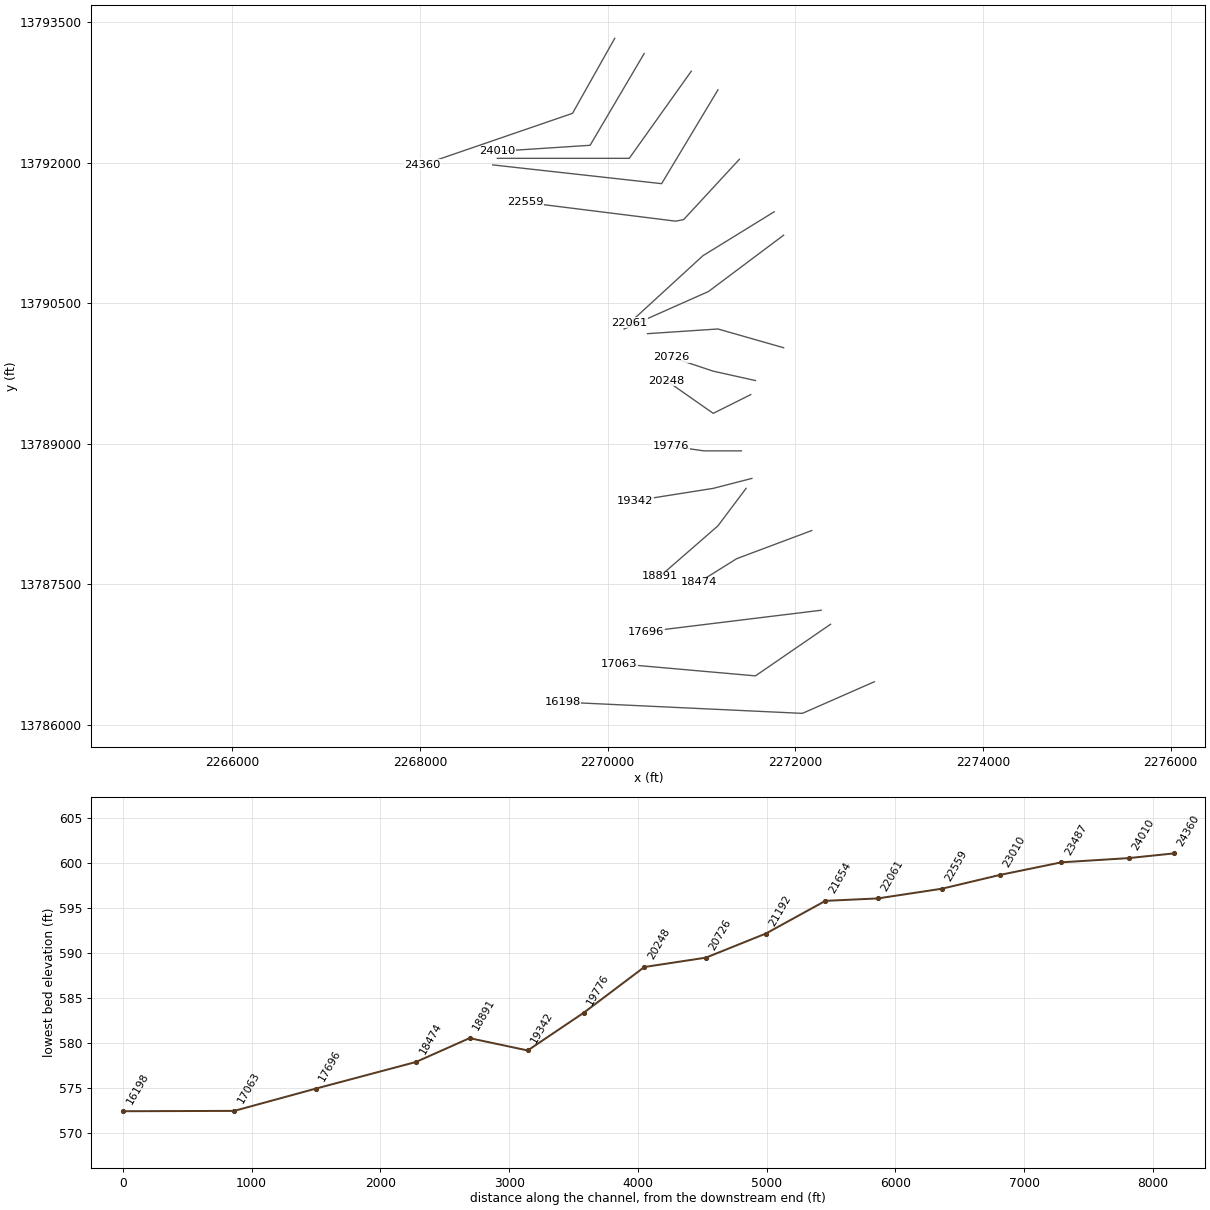
HEC-RAS study GUADALUPE TRIBUTARY 20.prj: GUADALUPE TRIBUTARY 20 Base Level Engineering

--- GUADALUPE TRIBUTARY 20.g01 (geometry) --- (continued)

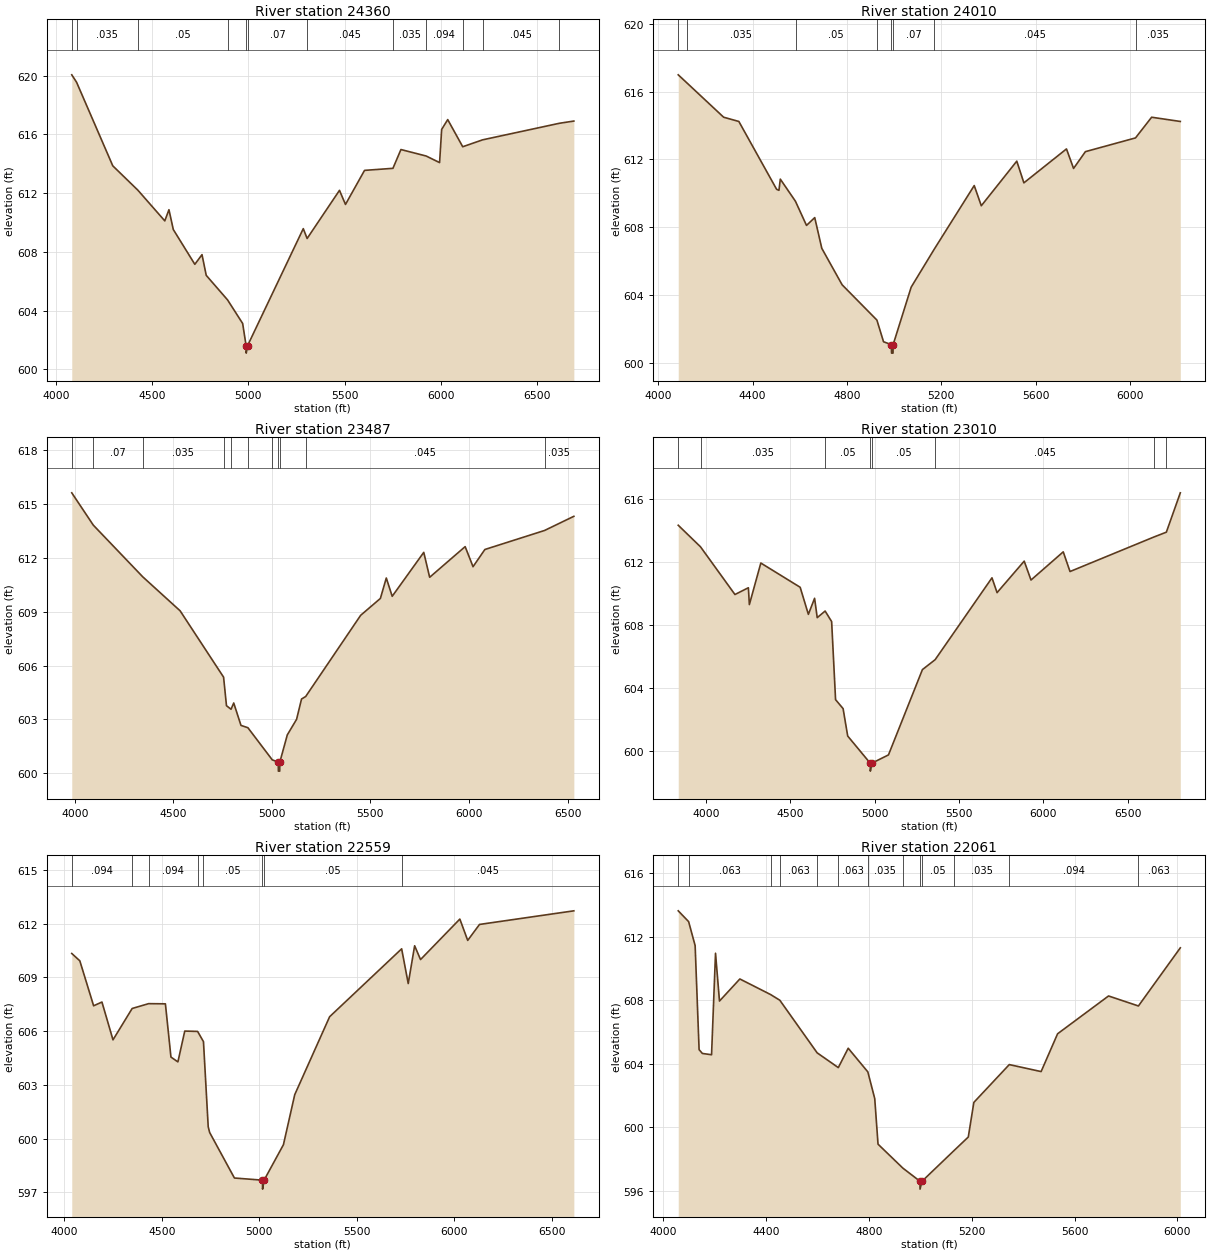
Type RM Length L Ch R = 1 ,24360   ,350,350,350
BEGIN DESCRIPTION:
GUADALUPE TRIBUTARY 20 42.0
END DESCRIPTION:
XS GIS Cut Line= 3
      2270075.01     13793325.02        2269625.       13792525.
      2268024.99       13791975.
#Sta/Elev= 30
  4082.1  620.06  4106.9  619.56  4295.3  613.86  4425.8   612.2  4565.6  610.11
  4587.3  610.87  4609.9  609.52  4721.8  607.15  4759.1  607.81    4781   606.4
  4891.7  604.73  4970.4  603.12  4988.4   601.6  4988.9   601.1  4995.7   601.6
  5285.5  609.58  5305.5  608.91  5473.7  612.19  5504.9  611.23  5603.9  613.55
  5751.6  613.69  5793.1  614.97    5924  614.53    5994  614.08  6004.8  616.34
  6036.3  617.01  6114.3  615.16  6217.4  615.63  6617.1  616.76  6691.9  616.91
#Mann= 12 ,-1 , 0
  4082.1     .05       0  4106.9    .035       0  4425.8     .05       0
  4891.7     .07       0  4988.4     .05       0  4995.7     .07       0
  5305.5    .045       0  5751.6    .035       0    5924    .094       0
  6114.3    .035       0  6217.4    .045       0  6617.1    .035       0
Bank Sta=4988.4,4995.7
XS Rating Curve= 0 ,0
Exp/Cntr=0.3,0.1

Type RM Length L Ch R = 1 ,24010   ,523,523,523
BEGIN DESCRIPTION:
A19213
END DESCRIPTION:
XS GIS Cut Line= 3
      2270389.08     13793163.28      2269812.63     13792184.31
      2268823.72     13792119.71
#Sta/Elev= 30
  4085.2  616.99  4121.5  616.52  4277.6  614.49    4342  614.24    4502  610.24
  4511.9  610.18  4517.7  610.84    4582  609.53  4628.6  608.11  4663.5  608.57
  4693.4  606.76  4779.5  604.61  4926.8  602.53    4955  601.25  4988.4  601.08
  4988.9  600.58  4995.2  600.58  4995.7  601.08  5072.1  604.47  5169.9  606.71
  5339.2  610.46  5369.2  609.27  5519.5   611.9  5549.6  610.62    5730  612.62
  5760.1  611.47  5810.2  612.46  6022.5  613.27  6090.8  614.49  6212.3  614.24
#Mann= 8 ,-1 , 0
  4085.2     .05       0  4121.5    .035       0    4582     .05       0
  4926.8     .07       0  4988.4     .05       0  4995.7     .07       0
  5169.9    .045       0  6022.5    .035       0
Bank Sta=4988.4,4995.7
XS Rating Curve= 0 ,0
Exp/Cntr=0.3,0.1

Type RM Length L Ch R = 1 ,23487   ,477,477,477
BEGIN DESCRIPTION:
A19212
END DESCRIPTION:
XS GIS Cut Line= 3
        2270891.     13792974.46      2270230.07     13792045.17
      2268823.72     13792045.17
#Sta/Elev= 30
  3985.2  615.63  4094.3  613.83  4344.8  610.95  4534.8  609.05  4755.3  605.35
  4769.9  603.76    4793  603.56  4806.7  603.91  4843.5  602.66  4878.7  602.53
  5002.1  600.74  5032.7  600.61  5033.2  600.11    5040  600.11  5040.5  600.61
  5078.4  602.13  5125.6     603  5150.6  604.13  5171.6  604.27  5450.6   608.8
  5550.6  609.74  5580.6  610.88  5610.6  609.86  5770.6  612.31  5800.6  610.92
  5980.6  612.63  6020.6  611.51  6080.6  612.47  6383.3  613.53  6531.9  614.32
#Mann= 11 ,-1 , 0
  3985.2     .05       0  4094.3     .07       0  4344.8    .035       0
  4755.3     .05       0    4793     .07       0  4878.7     .05       0
  5002.1     .07       0  5032.7     .05       0  5040.5     .07       0
  5171.6    .045       0  6383.3    .035       0
Bank Sta=5032.7,5040.5
XS Rating Curve= 0 ,0
Exp/Cntr=0.3,0.1

Type RM Length L Ch R = 1 ,23010   ,451,451,451
BEGIN DESCRIPTION:
GUADALUPE TRIBUTARY 20 41.0
END DESCRIPTION:
XS GIS Cut Line= 3
      2271175.02     13792775.04        2270575.       13791775.
      2268775.01       13791975.
#Sta/Elev= 30
  3834.4  614.33  3966.5  612.96  4170.7  609.93  4250.4  610.36  4256.2  609.29
  4324.2  611.93  4557.5  610.39  4606.1  608.67    4643  609.69  4658.6  608.46
  4705.5  608.88  4744.1  608.21  4767.4  603.25  4812.1  602.68  4839.3  600.94
  4973.2  599.21  4973.7  598.71  4981.4  599.21  5081.1  599.74  5282.4  605.16
  5357.9  605.79  5694.9  610.99  5725.1  610.05    5886  612.05  5926.3  610.85
  6117.5  612.64  6157.7  611.39  6654.5  613.58  6728.9  613.89  6811.7  616.39
#Mann= 8 ,-1 , 0
  3834.4     .07       0  3966.5    .035       0  4705.5     .05       0
  4973.2     .05       0  4981.4     .05       0  5357.9    .045       0
  6654.5    .035       0  6728.9    .094       0
Bank Sta=4973.2,4981.4
XS Rating Curve= 0 ,0
Exp/Cntr=0.3,0.1

Type RM Length L Ch R = 1 ,22559   ,498,498,498
BEGIN DESCRIPTION:
GUADALUPE TRIBUTARY 20 40.0
END DESCRIPTION:
XS GIS Cut Line= 4
      2271403.74     13792034.91      2270810.09     13791392.02
        2270725.       13791375.      2269124.99       13791575.
#Sta/Elev= 30
  4037.8  610.33  4079.1  609.92  4149.9  607.41  4192.5  607.62  4249.2  605.51
  4347.4  607.26  4431.9  607.53  4517.9  607.52  4546.3  604.55    4582  604.28
  4617.2     606    4683  605.98  4713.1  605.41  4737.4  600.66  4744.8  600.34
  4871.8   597.8  5015.6  597.68  5016.1  597.18  5023.9  597.68  5123.1  599.66
    5181  602.45  5359.9   606.8  5729.2  610.59    5763  608.65  5795.8  610.76
    5826  609.99  6027.6  612.25  6067.9  611.06  6128.4  611.95  6612.1  612.71
#Mann= 8 ,-1 , 0
  4037.8    .094       0  4347.4    .063       0  4431.9    .094       0
    4683    .035       0  4713.1     .05       0  5015.6     .05       0
  5023.9     .05       0  5729.2    .045       0
Bank Sta=5015.6,5023.9
XS Rating Curve= 0 ,0
Exp/Cntr=0.3,0.1

Type RM Length L Ch R = 1 ,22061   ,407,407,407
BEGIN DESCRIPTION:
GUADALUPE TRIBUTARY 20 39.0
END DESCRIPTION:
XS GIS Cut Line= 3
      2271775.03     13791475.02      2271015.24     13791006.55
      2270235.02     13790290.94
#Sta/Elev= 30
  4059.7  613.62  4100.1  612.94  4125.4  611.43  4140.8  604.88  4153.7  604.64
  4189.2  604.56  4204.6  610.95    4220  607.94  4299.2  609.33  4418.6  608.35
  4454.6  607.99  4599.6  604.68  4681.8  603.75  4720.3  604.97  4796.6  603.48
  4823.4   601.8  4836.2  598.93  4932.9  597.42    4999   596.6  4999.5   596.1
  5007.4   596.6  5132.4  598.54    5187  599.38  5208.6  601.56  5346.3  603.94
    5470   603.5  5534.1  605.88  5732.1  608.26  5848.2  607.63    6011  611.29
#Mann= 13 ,-1 , 0
  4059.7      .1       0  4100.1    .063       0  4418.6    .094       0
  4454.6    .063       0  4599.6    .094       0  4681.8    .063       0
  4796.6    .035       0  4932.9     .05       0    4999     .05       0
  5007.4     .05       0  5132.4    .035       0  5346.3    .094       0
  5848.2    .063       0
Bank Sta=4999,5007.4
XS Rating Curve= 0 ,0
Exp/Cntr=0.3,0.1

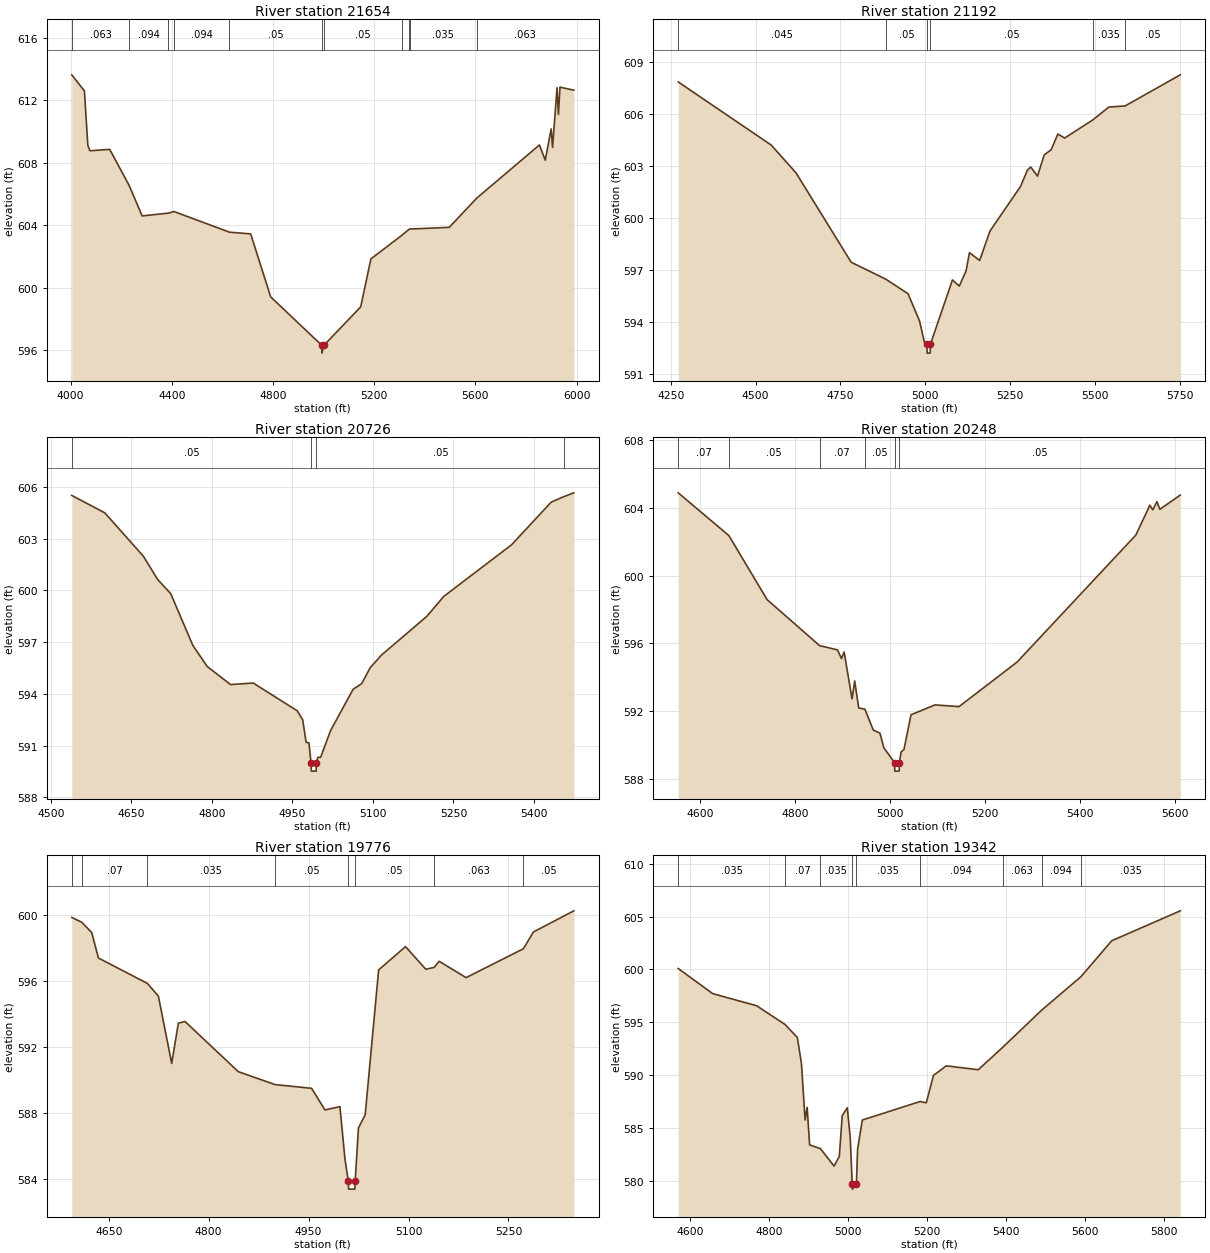
Type RM Length L Ch R = 1 ,21654   ,462,462,462
BEGIN DESCRIPTION:
GUADALUPE TRIBUTARY 20 38.0
END DESCRIPTION:
XS GIS Cut Line= 3
      2271874.97     13791224.98        2271075.       13790625.
      2270174.95     13790224.98
#Sta/Elev= 30
  4004.3  613.64  4054.3  612.61  4067.8  609.13  4076.1  608.78  4154.3  608.87
  4231.5  606.55  4282.4  604.61  4386.5  604.79  4408.8  604.89  4627.7  603.57
  4711.6  603.46  4790.7  599.43  4992.7  596.33  4993.2  595.83  5001.2  596.33
  5146.5  598.79  5186.9  601.86  5308.5  603.36  5335.9  603.73    5340  603.77
  5496.7  603.88  5605.4  605.75    5853  609.15  5876.3  608.18  5899.6  610.18
    5905     609  5922.8  612.81  5928.3  611.11  5934.4  612.85  5989.2  612.66
#Mann= 11 ,-1 , 0
  4004.3    .063       0  4231.5    .094       0  4386.5    .063       0
  4408.8    .094       0  4627.7     .05       0  4992.7     .05       0
  5001.2     .05       0  5308.5    .035       0  5335.9    .094       0
    5340    .035       0  5605.4    .063       0
Bank Sta=4992.7,5001.2
XS Rating Curve= 0 ,0
Exp/Cntr=0.3,0.1

Type RM Length L Ch R = 1 ,21192   ,466,466,466
BEGIN DESCRIPTION:
GUADALUPE TRIBUTARY 20 37.0
END DESCRIPTION:
XS GIS Cut Line= 3
      2271875.03     13790024.99        2271175.       13790225.
        2270425.       13790175.
#Sta/Elev= 30
    4272  607.86  4546.3  604.21  4619.1  602.61  4781.6  597.45  4883.9  596.47
  4949.3  595.63  4983.1  594.06  4997.4  592.84  5005.1   592.7  5005.6   592.2
  5014.6   592.2  5015.1   592.7  5080.2  596.43  5100.3  596.07  5120.3  596.95
  5130.3     598  5160.4  597.55  5190.5  599.24  5280.7  601.82  5300.7  602.75
  5310.7  602.95  5330.8  602.42  5350.8  603.65  5370.9  603.94  5390.9  604.85
  5410.9  604.62  5493.2  605.66  5541.2  606.41  5588.7  606.47  5751.7  608.27
#Mann= 6 ,-1 , 0
    4272    .045       0  4883.9     .05       0  5005.1     .05       0
  5015.1     .05       0  5493.2    .035       0  5588.7     .05       0
Bank Sta=5005.1,5015.1
XS Rating Curve= 0 ,0
Exp/Cntr=0.3,0.1

Type RM Length L Ch R = 1 ,20726   ,478,478,478
BEGIN DESCRIPTION:
GUADALUPE TRIBUTARY 20 36.0
END DESCRIPTION:
XS GIS Cut Line= 3
      2271574.99       13789675.        2271125.       13789775.
      2270675.01       13789925.
#Sta/Elev= 30
    4539  605.51  4600.5   604.5  4672.2  601.99  4699.1  600.63  4723.4  599.81
  4764.4  596.82  4791.3  595.59  4834.8  594.54    4877  594.63    4959  593.02
  4969.2   592.5  4975.6  591.19  4980.8  591.16  4984.7  590.02  4985.2  589.52
  4994.3  589.52  4994.8  590.02  4997.4  590.32  5002.6  590.32  5021.1  591.87
  5063.2  594.27    5079  594.59  5094.8  595.51  5115.9  596.25  5200.2  598.49
  5231.9  599.65  5358.4  602.65  5432.1  605.12  5456.6  605.45  5474.3  605.66
#Mann= 4 ,-1 , 0
    4539     .05       0  4984.7     .05       0  4994.8     .05       0
  5456.6    .035       0
Bank Sta=4984.7,4994.8
XS Rating Curve= 0 ,0
Exp/Cntr=0.3,0.1

Type RM Length L Ch R = 1 ,20248   ,472,472,472
BEGIN DESCRIPTION:
GUADALUPE TRIBUTARY 20 35.0
END DESCRIPTION:
XS GIS Cut Line= 3
      2271524.98     13789524.99        2271125.       13789325.
      2270625.01     13789674.99
#Sta/Elev= 30
  4553.3  604.87    4660  602.35  4740.5  598.58  4851.1  595.87  4888.7  595.62
  4897.1  595.11  4902.7   595.5  4919.4  592.73    4925  593.79  4933.4   592.2
  4946.5  592.13  4964.1   590.9  4978.1  590.72  4986.5  589.85    5009  588.98
  5009.5  588.48  5018.6  588.48  5019.1  588.98  5022.7  589.61  5028.8  589.76
  5043.6   591.8  5094.2  592.38  5144.8  592.28  5266.9   594.9  5517.1  602.38
  5546.7  604.14  5552.8  603.87  5561.6  604.35  5567.7   603.9  5610.8  604.74
#Mann= 6 ,-1 , 0
  4553.3     .07       0    4660     .05       0  4851.1     .07       0
  4946.5     .05       0    5009     .05       0  5019.1     .05       0
Bank Sta=5009,5019.1
XS Rating Curve= 0 ,0
Exp/Cntr=0.3,0.1

Type RM Length L Ch R = 1 ,19776   ,434,434,434
BEGIN DESCRIPTION:
GUADALUPE TRIBUTARY 20 34.0
END DESCRIPTION:
XS GIS Cut Line= 3
      2271425.02       13788925.        2271025.       13788925.
      2270674.97       13788975.
#Sta/Elev= 30
  4594.5  599.86  4609.5  599.57  4624.5  598.94  4634.5   597.4    4708  595.86
  4724.5  595.09  4744.5  591.01  4754.5  593.45  4764.5  593.55  4844.5  590.51
  4899.4  589.73  4954.5   589.5  4974.5  588.19    4997  588.39  5004.6   585.2
  5009.5  583.89    5010  583.39  5019.4  583.39  5019.9  583.89  5024.8   587.1
  5034.9  587.89  5055.1  596.68  5095.5  598.09  5125.8  596.72  5138.5  596.83
    5146   597.2  5186.4  596.21  5272.3  597.96  5287.5  598.98  5348.1  600.26
#Mann= 8 ,-1 , 0
  4594.5    .035       0  4609.5     .07       0    4708    .035       0
  4899.4     .05       0  5009.5     .05       0  5019.9     .05       0
  5138.5    .063       0  5272.3     .05       0
Bank Sta=5009.5,5019.9
XS Rating Curve= 0 ,0
Exp/Cntr=0.3,0.1

Type RM Length L Ch R = 1 ,19342   ,451,451,451
BEGIN DESCRIPTION:
GUADALUPE TRIBUTARY 20 33.0
END DESCRIPTION:
XS GIS Cut Line= 3
      2271537.07     13788631.16        2271125.       13788525.
      2270289.84     13788392.64
#Sta/Elev= 30
  4570.2  600.09  4657.6  597.71  4768.5  596.57  4840.4   594.8  4871.8  593.56
  4882.1  591.11  4891.4  585.75  4896.6  586.95  4902.8   583.4  4930.2  583.04
  4964.7  581.39    4978  582.31  4985.4  586.17  4998.3  586.91  5005.8  583.98
  5010.7  579.71  5011.2  579.21  5021.3  579.71  5024.3  582.99  5036.2  585.75
  5182.4   587.5  5198.2  587.38  5216.4  589.97  5248.8  590.88  5329.8  590.51
  5391.3  592.62  5490.6  596.16  5589.8  599.32  5667.8  602.72  5841.3  605.55
#Mann= 9 ,-1 , 0
  4570.2    .035       0  4840.4     .07       0  4930.2    .035       0
  5010.7    .035       0  5021.3    .035       0  5182.4    .094       0
  5391.3    .063       0  5490.6    .094       0  5589.8    .035       0
Bank Sta=5010.7,5021.3
XS Rating Curve= 0 ,0
Exp/Cntr=0.3,0.1

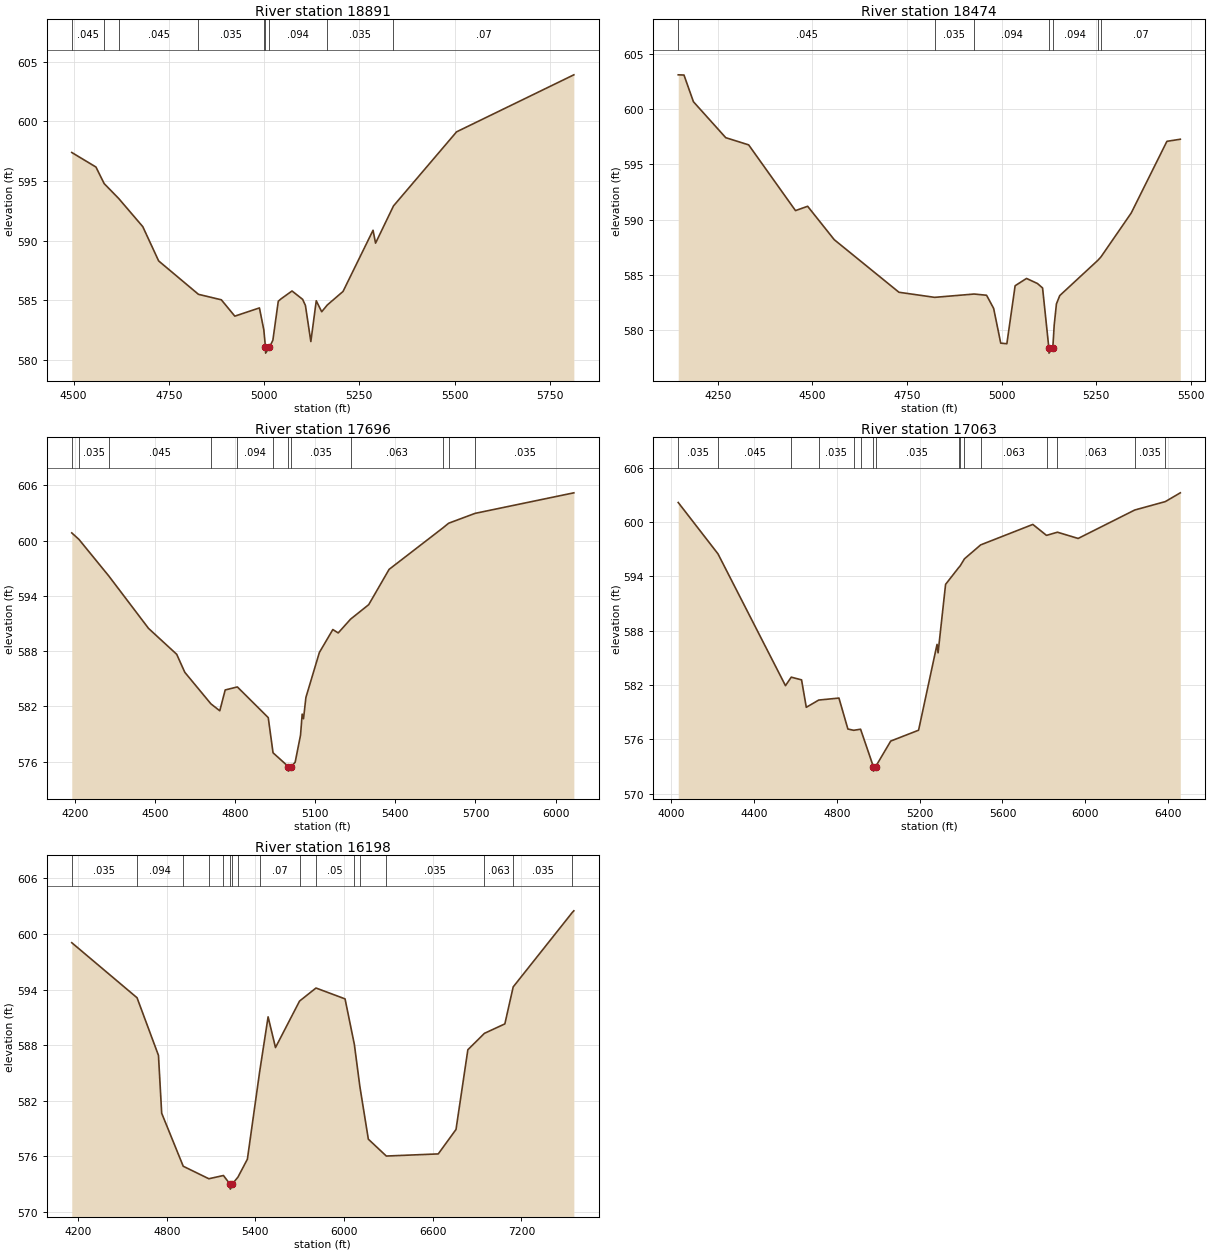
Type RM Length L Ch R = 1 ,18891   ,417,417,417
BEGIN DESCRIPTION:
GUADALUPE TRIBUTARY 20 32.0
END DESCRIPTION:
XS GIS Cut Line= 3
        2271475.       13788525.        2271175.       13788125.
      2270558.06     13787587.57
#Sta/Elev= 30
  4495.1   597.4  4558.6  596.18  4580.2  594.79  4618.4  593.54  4681.6  591.18
  4723.2  588.31  4827.7  585.51  4887.8  585.05  4923.2  583.68  4987.8  584.37
  4999.4  582.52  5003.6  581.08  5004.1  580.58  5014.2  581.08  5023.1  581.66
  5037.3  584.93    5045  585.14  5073.4  585.79  5101.2  585.09  5108.6  584.57
  5122.8  581.55    5137  584.97  5151.3  584.05  5166.1  584.62  5207.3  585.75
  5286.1  590.88  5292.7   589.8  5339.8  592.92  5505.4  599.13  5813.3  603.91
#Mann= 9 ,-1 , 0
  4495.1    .045       0  4580.2    .035       0  4618.4    .045       0
  4827.7    .035       0  4999.4    .094       0  5003.6     .05       0
  5014.2    .094       0  5166.1    .035       0  5339.8     .07       0
Bank Sta=5003.6,5014.2
XS Rating Curve= 0 ,0
Exp/Cntr=0.3,0.1

Type RM Length L Ch R = 1 ,18474   ,778,778,778
BEGIN DESCRIPTION:
GUADALUPE TRIBUTARY 20 31.0
END DESCRIPTION:
XS GIS Cut Line= 3
      2272175.02     13788075.01        2271375.       13787775.
      2270975.02     13787525.01
#Sta/Elev= 30
  4145.6  603.08  4160.8  603.06  4185.7  600.65  4271.1   597.4  4331.6  596.75
  4455.3  590.81  4487.4   591.2  4557.7  588.18  4728.6  583.43  4822.9  582.97
    4927  583.27    4960  583.16  4978.7  581.97  4997.4  578.83  5013.6  578.78
  5035.4  584.02  5065.5  584.68  5094.4  584.22  5107.9  583.82  5124.4  578.43
  5124.9  577.93    5135  578.43  5138.6  580.45  5144.5  582.38  5153.3  583.13
    5254  586.32    5262  586.62    5342  590.59  5436.3  597.07  5471.7  597.26
#Mann= 7 ,-1 , 0
  4145.6    .045       0  4822.9    .035       0    4927    .094       0
  5124.4     .05       0    5135    .094       0    5254    .035       0
    5262     .07       0
Bank Sta=5124.4,5135
XS Rating Curve= 0 ,0
Exp/Cntr=0.3,0.1

Type RM Length L Ch R = 1 ,17696   ,633,633,633
BEGIN DESCRIPTION:
GUADALUPE TRIBUTARY 20 29.0
END DESCRIPTION:
XS GIS Cut Line= 3
      2272275.01       13787225.      2271502.25     13787130.37
      2270409.48     13786996.26
#Sta/Elev= 30
  4188.7  600.83  4215.4  600.13  4327.4  596.15  4476.2  590.46  4581.6  587.65
  4611.8   585.7  4709.7  582.27  4742.8  581.52    4763  583.78  4808.6  584.11
  4924.2  580.78  4942.2  576.96  4999.2  575.47  4999.7  574.97  5010.3  575.47
  5024.9  575.93  5045.1  578.88  5051.2  581.16  5056.3  580.66  5065.2  582.97
  5115.6  587.85    5166  590.34  5186.1  589.97  5232.5  591.47  5300.3  593.04
  5376.6  596.87  5578.8  601.39  5599.5  601.88  5698.4  602.95  6068.2  605.18
#Mann= 12 ,-1 , 0
  4188.7    .045       0  4215.4    .035       0  4327.4    .045       0
  4709.7      .1       0  4808.6    .094       0  4942.2    .035       0
  4999.2    .035       0  5010.3    .035       0  5232.5    .063       0
  5578.8    .035       0  5599.5     .07       0  5698.4    .035       0
Bank Sta=4999.2,5010.3
XS Rating Curve= 0 ,0
Exp/Cntr=0.3,0.1

Type RM Length L Ch R = 1 ,17063   ,865,865,865
BEGIN DESCRIPTION:
GUADALUPE TRIBUTARY 20 28.0
END DESCRIPTION:
XS GIS Cut Line= 3
      2272375.03     13787075.02        2271575.       13786525.
      2270125.02     13786653.22
#Sta/Elev= 30
  4033.1  602.17  4225.2   596.5  4551.4  581.94  4579.3  582.88  4629.1  582.58
    4652  579.55  4712.1  580.35  4809.8  580.57  4853.1  577.15  4881.1  577.01
  4914.4  577.13  4976.1     573  4976.6   572.5  4987.2     573    5060  575.82
  5194.7  577.02  5283.9   586.5  5288.9  585.57  5325.2  593.13  5389.2     595
  5395.7  595.17  5416.4  595.95  5494.8  597.49  5746.9  599.75  5812.9  598.54
  5865.8  598.89  5965.8   598.2  6239.2  601.34    6387  602.27  6459.6  603.24
#Mann= 16 ,-1 , 0
  4033.1    .035       0  4225.2    .045       0  4579.3    .094       0
  4712.1    .035       0  4881.1     .07       0  4914.4    .035       0
  4976.1    .035       0  4987.2    .035       0  5389.2     .07       0
  5395.7    .035       0  5416.4     .07       0  5494.8    .063       0
  5812.9    .035       0  5865.8    .063       0  6239.2    .035       0
    6387    .063       0
Bank Sta=4976.1,4987.2
XS Rating Curve= 0 ,0
Exp/Cntr=0.3,0.1

Type RM Length L Ch R = 1 ,16198   ,902,902,902
BEGIN DESCRIPTION:
GUADALUPE TRIBUTARY 20 26.0
END DESCRIPTION:
XS GIS Cut Line= 3
      2272841.98     13786462.25        2272075.       13786125.
      2269518.67     13786245.17
#Sta/Elev= 30
  4157.5  599.05  4599.2  593.11  4744.1  586.89  4765.9  580.65  4911.6  574.93
  5084.9  573.58  5183.7  573.93    5230  572.96  5230.5  572.46  5241.2  572.96
  5282.4  573.77  5345.7  575.69  5428.8  585.14  5485.9  591.05  5535.9  587.74
  5698.6  592.75  5809.8  594.16  6006.5  592.99  6069.4  588.08  6106.9  583.52
  6164.1  577.85  6285.7  576.03  6637.2  576.26  6757.3   578.9  6837.4   587.5
  6949.5  589.27  7087.7  590.29  7144.1  594.28  7544.3  602.32  7554.5  602.49
#Mann= 17 ,-1 , 0
  4157.5    .035       0  4599.2    .094       0  4911.6    .035       0
  5084.9     .05       0  5183.7     .07       0    5230    .035       0
  5241.2     .07       0  5282.4     .05       0  5428.8     .07       0
  5698.6    .063       0  5809.8     .05       0  6069.4     .07       0
  6106.9     .05       0  6285.7    .035       0  6949.5    .063       0
  7144.1    .035       0  7544.3    .063       0
Bank Sta=5230,5241.2
XS Rating Curve= 0 ,0
Exp/Cntr=0.3,0.1