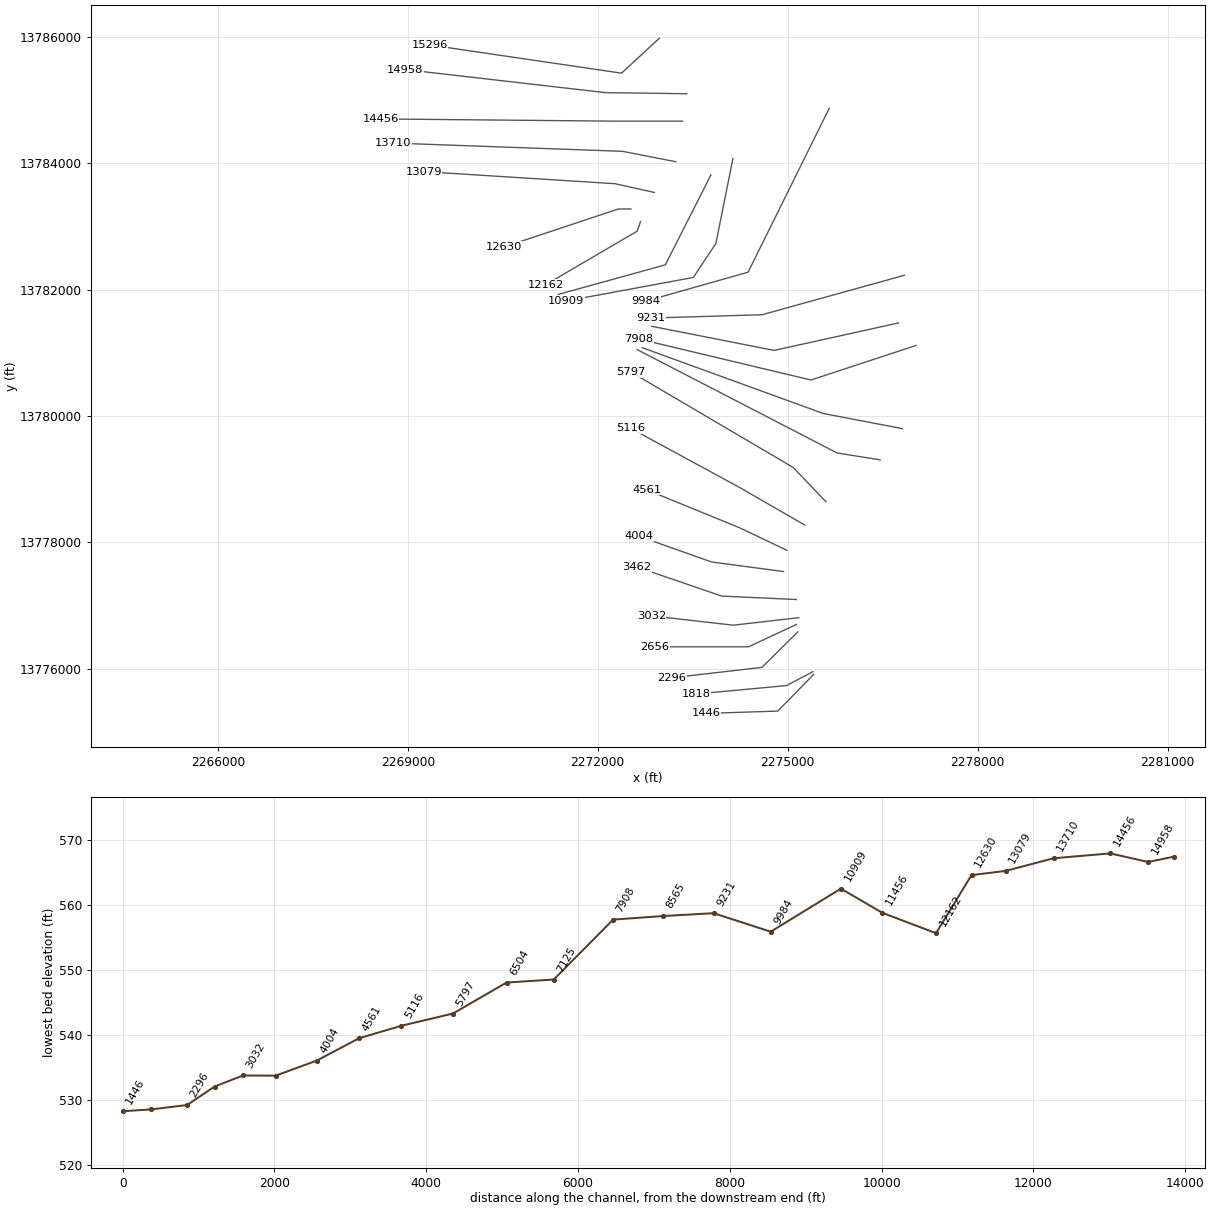
HEC-RAS study GUADALUPE TRIBUTARY 20.prj: GUADALUPE TRIBUTARY 20 Base Level Engineering

--- GUADALUPE TRIBUTARY 20.g01 (geometry) --- (continued)

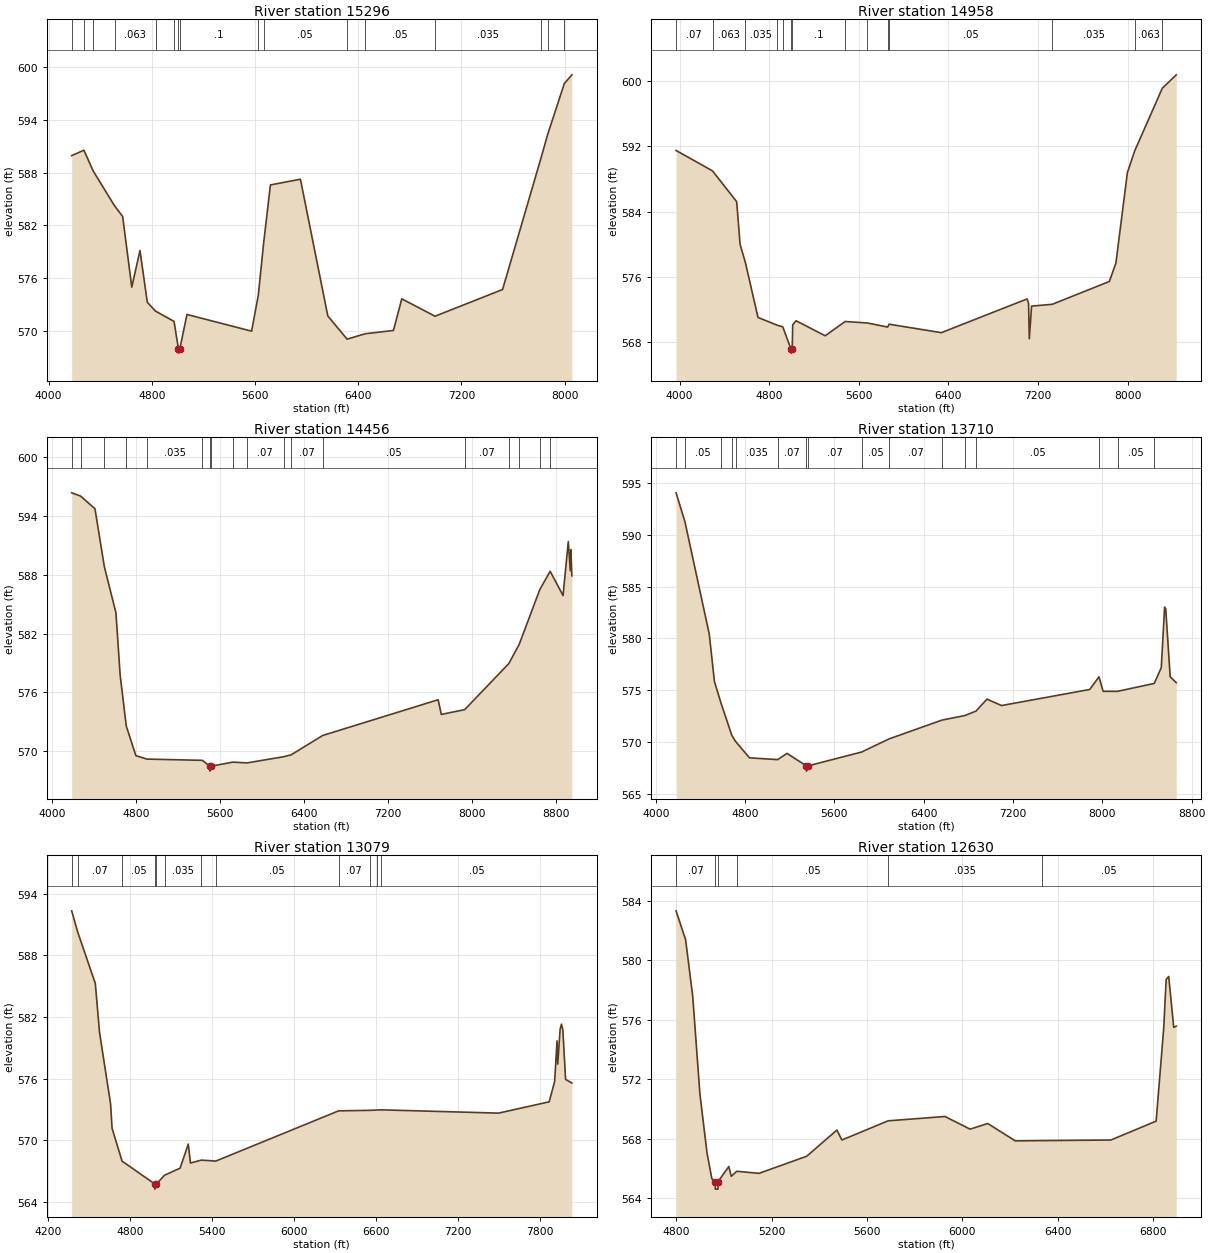
Type RM Length L Ch R = 1 ,15296   ,338,338,338
BEGIN DESCRIPTION:
GUADALUPE TRIBUTARY 20 24.0
END DESCRIPTION:
XS GIS Cut Line= 3
      2272972.19     13785976.13        2272375.       13785425.
      2269343.71     13785871.97
#Sta/Elev= 30
  4179.3  589.94  4274.2  590.55  4345.7   588.2  4511.7  584.22  4574.3  583.02
  4645.2  574.97  4708.7  579.14  4765.4  573.25    4829  572.24  4972.8  571.07
  5006.6  567.96  5007.1  567.46  5017.8  567.96  5072.8  571.86  5573.9  569.96
  5625.9  574.06  5666.1  579.85  5719.7   586.6  5952.2  587.25  6164.5  571.69
    6314  569.05  6453.3  569.66  6673.2  570.04  6737.8  573.64  6995.5  571.66
    7519   574.7  7819.9  589.81  7868.2  592.33  7997.4  598.13    8056  599.13
#Mann= 16 ,-1 , 0
  4179.3    .035       0  4274.2    .063       0  4345.7    .094       0
  4511.7    .063       0    4829    .035       0  4972.8      .1       0
  5006.6     .05       0  5017.8      .1       0  5625.9     .07       0
  5666.1     .05       0    6314    .035       0  6453.3     .05       0
  6995.5    .035       0  7819.9    .063       0  7868.2    .035       0
  7997.4    .063       0
Bank Sta=5006.6,5017.8
XS Rating Curve= 0 ,0
Exp/Cntr=0.3,0.1

Type RM Length L Ch R = 1 ,14958   ,502,502,502
BEGIN DESCRIPTION:
A19211
END DESCRIPTION:
XS GIS Cut Line= 3
      2273406.22      13785099.4       2272121.5     13785116.76
       2268961.8     13785481.34
#Sta/Elev= 30
  3968.2  591.51    4294     589  4509.5  585.22  4539.5  580.01  4587.3  577.75
  4699.5  571.02  4872.8  570.06  4920.8  569.87  4993.8  567.14  4994.3  566.64
  5005.2  567.14  5009.5  570.11  5039.5  570.61  5299.8  568.77  5477.9  570.52
  5675.4  570.34  5857.4  569.84  5869.8  570.19  6336.7  569.15  7101.7  573.29
  7115.1  572.77  7121.9   568.4    7142  572.41  7326.2  572.63  7836.6  575.43
  7895.2   577.7  7997.6   588.8  8063.2  591.47  8309.1  599.14  8433.7  600.79
#Mann= 14 ,-1 , 0
  3968.2     .07       0    4294    .063       0  4587.3    .035       0
  4872.8     .07       0  4920.8      .1       0  4993.8     .05       0
  5005.2      .1       0  5477.9     .07       0  5675.4     .05       0
  5857.4    .035       0  5869.8     .05       0  7326.2    .035       0
  8063.2    .063       0  8309.1    .035       0
Bank Sta=4993.8,5005.2
XS Rating Curve= 0 ,0
Exp/Cntr=0.3,0.1

Type RM Length L Ch R = 1 ,14456   ,746,746,746
BEGIN DESCRIPTION:
A19210
END DESCRIPTION:
XS GIS Cut Line= 3
      2273336.79     13784665.37      2272269.07     13784665.37
      2268571.15      13784700.1
#Sta/Elev= 30
  4188.1  596.38  4272.5  596.05  4409.9  594.76    4499  588.86  4609.9  584.12
  4649.9  577.78    4708  572.58  4799.9  569.54    4905  569.19  5434.4  569.06
  5504.2  568.46  5504.7  567.96  5515.6  568.46  5724.2  568.88  5858.6   568.8
  6207.4  569.43  6278.9  569.62  6579.7   571.6    7680  575.25    7710  573.75
  7932.8  574.24    8353  578.94  8451.6  580.89  8648.6   586.5  8747.1  588.37
    8870  585.89    8920  591.41  8939.4  588.42  8944.4  590.58  8953.9   587.9
#Mann= 18 ,-1 , 0
  4188.1     .05       0  4272.5    .063       0    4499    .035       0
    4708     .07       0    4905    .035       0  5434.4     .07       0
  5504.2    .035       0  5515.6     .07       0  5724.2    .035       0
  5858.6     .07       0  6207.4     .05       0  6278.9     .07       0
  6579.7     .05       0  7932.8     .07       0    8353     .05       0
  8451.6    .035       0  8648.6     .07       0  8747.1    .035       0
Bank Sta=5504.2,5515.6
XS Rating Curve= 0 ,0
Exp/Cntr=0.3,0.1

Type RM Length L Ch R = 1 ,13710   ,631,631,631
BEGIN DESCRIPTION:
GUADALUPE TRIBUTARY 20 23.0
END DESCRIPTION:
XS GIS Cut Line= 3
      2273232.61     13784023.01       2272390.6     13784187.94
      2268770.85     13784318.15
#Sta/Elev= 30
    4182  594.03  4261.2  591.26  4479.3  580.42  4525.7  575.85  4583.4  573.81
  4681.2  570.66  4714.4  570.08  4839.7  568.49    5092  568.32  5175.7  568.92
  5350.1  567.71  5350.6  567.21  5361.6  567.71  5843.8  569.05  6090.7  570.32
  6564.5  572.13  6769.2  572.57  6867.9  572.99  6966.9  574.15  7096.9  573.53
  7887.4  575.08  7969.7   576.3  8007.5   574.9  8136.4   574.9  8465.1  575.66
  8527.9  577.18  8557.9  583.01  8567.9  582.84  8607.9   576.3  8662.1  575.74
#Mann= 16 ,-1 , 0
    4182    .035       0  4261.2     .05       0  4583.4    .035       0
  4681.2     .05       0  4714.4    .035       0    5092     .07       0
  5350.1    .035       0  5361.6     .07       0  5843.8     .05       0
  6090.7     .07       0  6564.5     .05       0  6769.2     .07       0
  6867.9     .05       0  7969.7     .07       0  8136.4     .05       0
  8465.1     .07       0
Bank Sta=5350.1,5361.6
XS Rating Curve= 0 ,0
Exp/Cntr=0.3,0.1

Type RM Length L Ch R = 1 ,13079   ,449,449,449
BEGIN DESCRIPTION:
GUADALUPE TRIBUTARY 20 22.0
END DESCRIPTION:
XS GIS Cut Line= 3
       2272894.1     13783536.89        2272275.       13783675.
      2269249.08     13783866.71
#Sta/Elev= 30
  4370.9  592.32  4415.9  590.23  4544.2  585.26  4574.9  580.53  4656.2  573.53
  4667.1  571.18  4739.9  567.99    4980  565.76  4980.5  565.26  4992.1  565.76
  5051.5  566.61  5165.5   567.3  5225.7  569.64  5241.6   567.8  5321.5  568.08
  5427.7  567.99  6327.4  572.87  6557.1  572.92  6606.8  572.95  6637.4  572.97
  7500.2  572.65    7871  573.75    7911  575.73  7928.6  579.68  7933.6  577.42
  7951.1   580.8  7961.1   581.3  7971.2  580.74  7991.2  575.93  8037.2  575.58
#Mann= 12 ,-1 , 0
  4370.9     .05       0  4415.9     .07       0  4739.9     .05       0
    4980     .05       0  4992.1     .05       0  5051.5    .035       0
  5321.5     .07       0  5427.7     .05       0  6327.4     .07       0
  6557.1     .05       0  6606.8     .07       0  6637.4     .05       0
Bank Sta=4980,4992.1
XS Rating Curve= 0 ,0
Exp/Cntr=0.3,0.1

Type RM Length L Ch R = 1 ,12630   ,468,468,468
BEGIN DESCRIPTION:
GUADALUPE TRIBUTARY 20 21.0
END DESCRIPTION:
XS GIS Cut Line= 3
      2272525.02       13783275.        2272325.       13783275.
      2270524.99       13782675.
#Sta/Elev= 30
  4799.7  583.32  4839.7  581.38  4869.7  577.56  4899.7  571.01  4929.7  567.03
  4949.7  565.32  4963.7  565.12  4964.2  564.62  4975.3  564.62  4975.8  565.12
  5020.8  566.14  5031.3  565.48  5054.3  565.82  5147.3  565.68  5347.6  566.83
  5474.1  568.59  5495.1  567.92  5688.9  569.21  5927.3   569.5  6032.7  568.65
  6106.5  569.03  6222.5  567.86  6333.6  567.88    6623  567.92  6812.8  569.19
  6844.4  575.41  6854.9  578.71  6865.5  578.91  6886.5  575.49  6897.1  575.57
#Mann= 6 ,-1 , 0
  4799.7     .07       0  4963.7     .05       0  4975.8     .07       0
  5054.3     .05       0  5688.9    .035       0  6333.6     .05       0
Bank Sta=4963.7,4975.8
XS Rating Curve= 0 ,0
Exp/Cntr=0.3,0.1

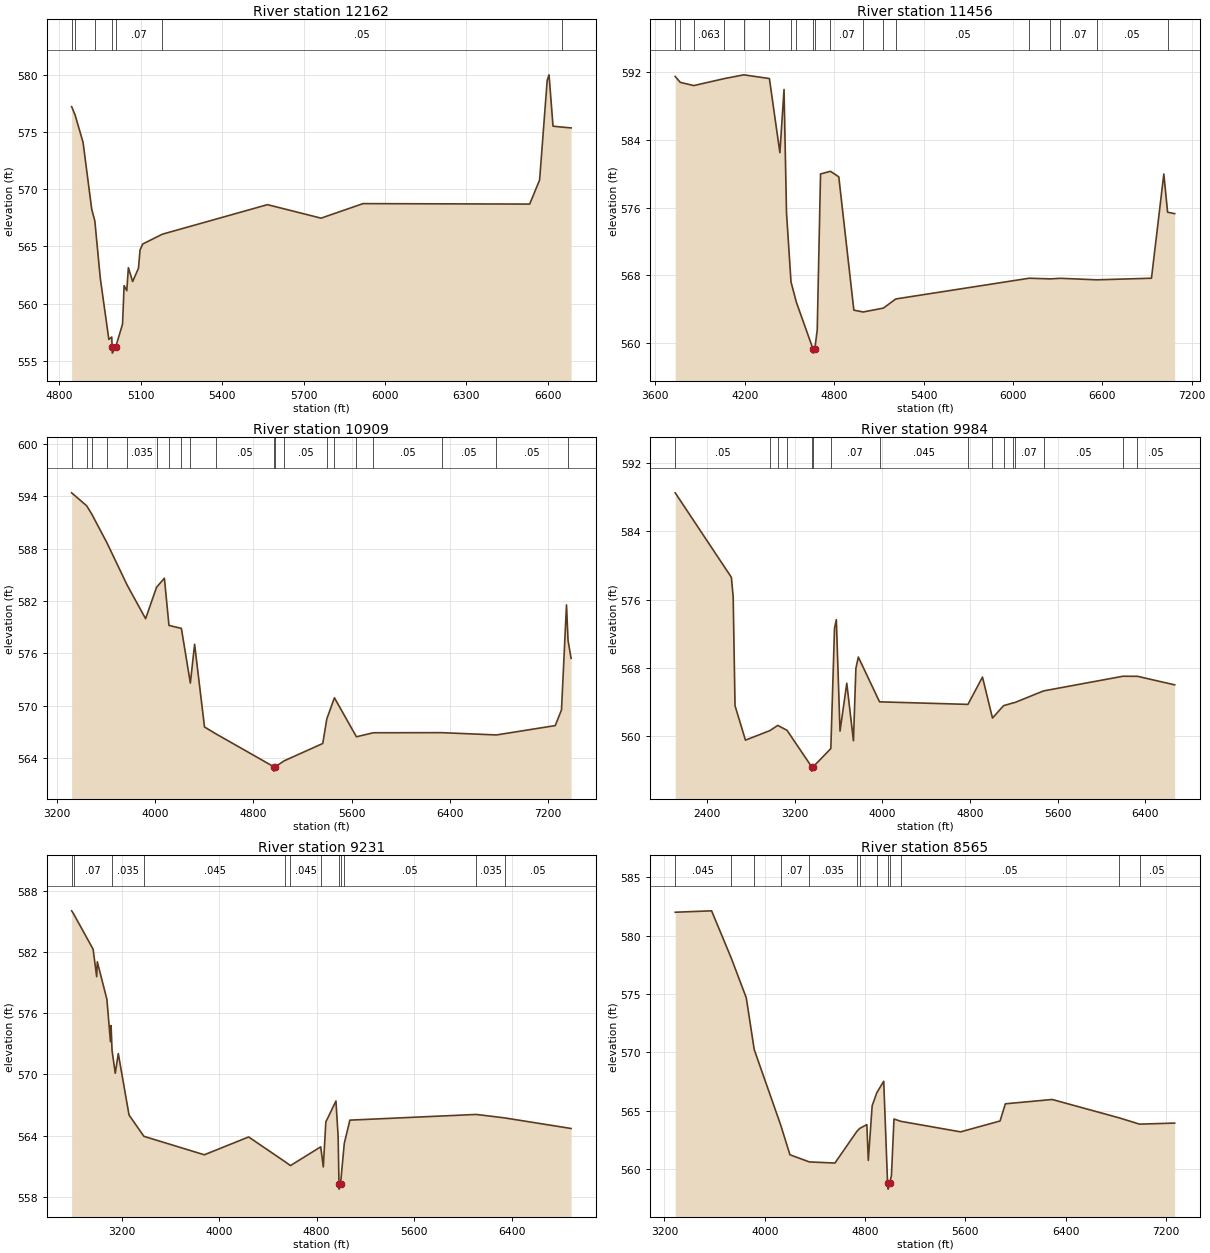
Type RM Length L Ch R = 1 ,12162   ,706,706,706
BEGIN DESCRIPTION:
GUADALUPE TRIBUTARY 20 20.0
END DESCRIPTION:
XS GIS Cut Line= 3
      2272674.99     13783074.98        2272625.       13782925.
      2271174.97     13782074.98
#Sta/Elev= 30
  4846.2  577.22  4859.1  576.48  4888.3  574.09    4920  568.27  4931.7  567.21
  4951.6  562.24  4983.2  556.87  4993.8  557.08  4995.5  556.17    4996  555.67
  5007.9  556.17  5033.6  558.21  5039.4  561.57  5049.3  561.13  5055.1  563.14
  5070.8  561.93  5092.3  563.09  5098.1  564.69  5107.9  565.21  5180.5  566.07
  5567.2  568.65  5764.6  567.47    5919  568.74  6532.7   568.7  6569.2  570.81
  6597.1  579.51  6603.9     580  6618.6  575.51  6652.3  575.43  6685.1  575.36
#Mann= 7 ,-1 , 0
  4846.2    .035       0  4859.1     .05       0  4931.7     .07       0
  4995.5     .05       0  5007.9     .07       0  5180.5     .05       0
  6652.3    .033       0
Bank Sta=4995.5,5007.9
XS Rating Curve= 0 ,0
Exp/Cntr=0.3,0.1

Type RM Length L Ch R = 1 ,11456   ,547,547,547
BEGIN DESCRIPTION:
A19209
END DESCRIPTION:
XS GIS Cut Line= 3
      2273788.17     13783814.69      2273067.68     13782391.07
      2271374.94     13781922.31
#Sta/Elev= 30
  3733.6  591.49  3767.5  590.79  3858.3  590.41  4064.3  591.24  4194.1  591.68
  4365.7  591.24    4436  582.49  4463.9  589.95  4480.5   575.4  4510.7  567.22
  4546.6  564.82  4658.2   559.3  4658.7   558.8  4670.6   559.3  4686.7  561.54
  4708.9  579.97  4775.4  580.28  4831.4  579.63  4932.5  563.88  4994.9  563.66
  5130.6  564.12    5214   565.2  6109.4  567.65  6250.7  567.57  6318.6  567.64
  6563.3  567.46  6929.9  567.65  7012.9  579.96  7038.1  575.45  7085.6  575.28
#Mann= 19 ,-1 , 0
  3733.6     .05       0  3767.5     .07       0  3858.3    .063       0
  4064.3    .035       0  4194.1     .05       0  4365.7    .035       0
  4510.7     .05       0  4546.6    .035       0  4658.2     .05       0
  4670.6    .035       0  4775.4     .07       0  4994.9     .05       0
  5130.6     .07       0    5214     .05       0  6109.4     .07       0
  6250.7     .05       0  6318.6     .07       0  6563.3     .05       0
  7038.1    .033       0
Bank Sta=4658.2,4670.6
XS Rating Curve= 0 ,0
Exp/Cntr=0.3,0.1

Type RM Length L Ch R = 1 ,10909   ,925,925,925
BEGIN DESCRIPTION:
GUADALUPE TRIBUTARY 20 19.0
END DESCRIPTION:
XS GIS Cut Line= 4
      2274135.39      13784075.1      2273866.29     13782729.61
      2273510.39     13782191.42      2271498.23     13781818.47
#Sta/Elev= 30
  3322.3  594.37  3444.6  592.89  3484.7  591.97  3609.4  588.66  3773.8  583.82
  3924.1  579.97  4013.3  583.57  4077.1   584.6  4114.3   579.2  4215.3  578.86
  4288.3   572.6  4322.8  577.05  4403.4  567.58  4494.5  566.81  4967.5  563.03
    4968  562.53    4980  563.03  5051.7  563.71  5365.5  565.69  5398.6  568.51
  5460.5  570.92  5639.6  566.46  5777.2  566.92  6334.3  566.93    6779  566.67
  7257.2  567.74    7308  569.54  7348.7  581.55  7361.4  577.49  7386.1  575.44
#Mann= 20 ,-1 , 0
  3322.3     .07       0  3444.6     .05       0  3484.7     .07       0
  3609.4     .05       0  3773.8    .035       0  4013.3     .07       0
  4114.3     .05       0  4215.3    .094       0  4288.3    .035       0
  4494.5     .05       0  4967.5     .05       0    4980     .07       0
  5051.7     .05       0  5398.6     .07       0  5460.5     .05       0
  5639.6     .07       0  5777.2     .05       0  6334.3     .05       0
    6779     .05       0  7361.4     .07       0
Bank Sta=4967.5,4980
XS Rating Curve= 0 ,0
Exp/Cntr=0.3,0.1

Type RM Length L Ch R = 1 ,9984    ,753,753,753
BEGIN DESCRIPTION:
GUADALUPE TRIBUTARY 20 18.0
END DESCRIPTION:
XS GIS Cut Line= 3
      2275654.49     13784865.03        2274375.       13782275.
      2272763.85     13781818.15
#Sta/Elev= 30
  2106.6  588.51  2619.7  578.61  2636.2  576.32  2653.1  563.57  2748.4  559.53
  2971.7  560.65  3043.8  561.26  3128.4  560.68  3353.7   556.4  3354.2   555.9
  3366.3   556.4  3528.3  558.54    3562  572.62  3578.8  573.65  3612.4  560.59
  3674.2   566.2  3735.1  559.46  3757.4  567.95  3779.7  569.27  3973.5  564.02
  4781.3  563.72  4914.1  566.92  5005.5  562.12    5107  563.57  5189.9  563.88
  5208.6  563.93  5472.2   565.3  6198.6  567.02  6330.3  567.01  6670.1  566.01
#Mann= 16 ,-1 , 0
  2106.6     .05       0  2971.7     .07       0  3043.8     .05       0
  3128.4    .035       0  3353.7     .05       0  3366.3    .035       0
  3528.3     .07       0  3973.5    .045       0  4781.3    .094       0
  5005.5    .035       0    5107     .07       0  5189.9    .035       0
  5208.6     .07       0  5472.2     .05       0  6198.6     .07       0
  6330.3     .05       0
Bank Sta=3353.7,3366.3
XS Rating Curve= 0 ,0
Exp/Cntr=0.3,0.1

Type RM Length L Ch R = 1 ,9231    ,666,666,666
BEGIN DESCRIPTION:
GUADALUPE TRIBUTARY 20 17.0
END DESCRIPTION:
XS GIS Cut Line= 3
      2276843.69     13782226.13      2274595.46     13781601.14
      2272833.32     13781549.05
#Sta/Elev= 30
  2790.9  586.06  2806.2  585.78  2967.2  582.29  2996.2   579.6  3001.4  581.06
  3080.2  577.37  3109.3  573.22  3114.5   574.8  3122.3  572.36  3148.7  570.12
  3173.6  572.05  3261.8  566.02  3383.8  563.93  3879.4  562.12  4242.6  563.87
  4544.9  561.41  4585.6  561.06  4833.9   562.9    4855  560.93  4875.8  565.34
  4958.8   567.4  4976.8  563.88  4983.6  559.25  4984.1  558.75  4996.2  559.25
  5026.9  563.23    5073  565.52  6109.5  566.08  6342.1  565.74  6887.3   564.7
#Mann= 12 ,-1 , 0
  2790.9    .035       0  2806.2     .07       0  3122.3    .035       0
  3383.8    .045       0  4544.9     .07       0  4585.6    .045       0
  4833.9    .094       0  4983.6     .05       0  4996.2    .094       0
  5026.9     .05       0  6109.5    .035       0  6342.1     .05       0
Bank Sta=4983.6,4996.2
XS Rating Curve= 0 ,0
Exp/Cntr=0.3,0.1

Type RM Length L Ch R = 1 ,8565    ,657,657,657
BEGIN DESCRIPTION:
GUADALUPE TRIBUTARY 20 16.0
END DESCRIPTION:
XS GIS Cut Line= 3
      2276748.27     13781470.94      2274786.43      13781036.9
      2272850.63     13781418.85
#Sta/Elev= 30
  3286.2     582  3576.3  582.12  3733.7  578.06  3852.8  574.68  3916.2  570.25
  4127.1   563.8  4201.1  561.25  4355.2  560.64  4559.5  560.54  4733.2  563.23
  4756.7   563.5  4814.3  563.83  4825.8  560.77  4856.5  565.44  4893.3  566.55
  4948.7  567.54  4979.4  558.84  4983.3  558.81  4983.8  558.31    4996  558.81
  5010.2  559.47  5030.7  564.31  5085.4  564.11  5561.9  563.21  5876.3  564.14
  5918.7  565.61  6291.9  565.98  6825.6  564.41  6988.5  563.87  7268.6  563.96
#Mann= 13 ,-1 , 0
  3286.2    .045       0  3733.7    .035       0  3916.2    .045       0
  4127.1     .07       0  4355.2    .035       0  4733.2     .07       0
  4756.7    .035       0  4893.3    .094       0  4983.3    .035       0
    4996    .094       0  5085.4     .05       0  6825.6    .035       0
  6988.5     .05       0
Bank Sta=4983.3,4996
XS Rating Curve= 0 ,0
Exp/Cntr=0.3,0.1

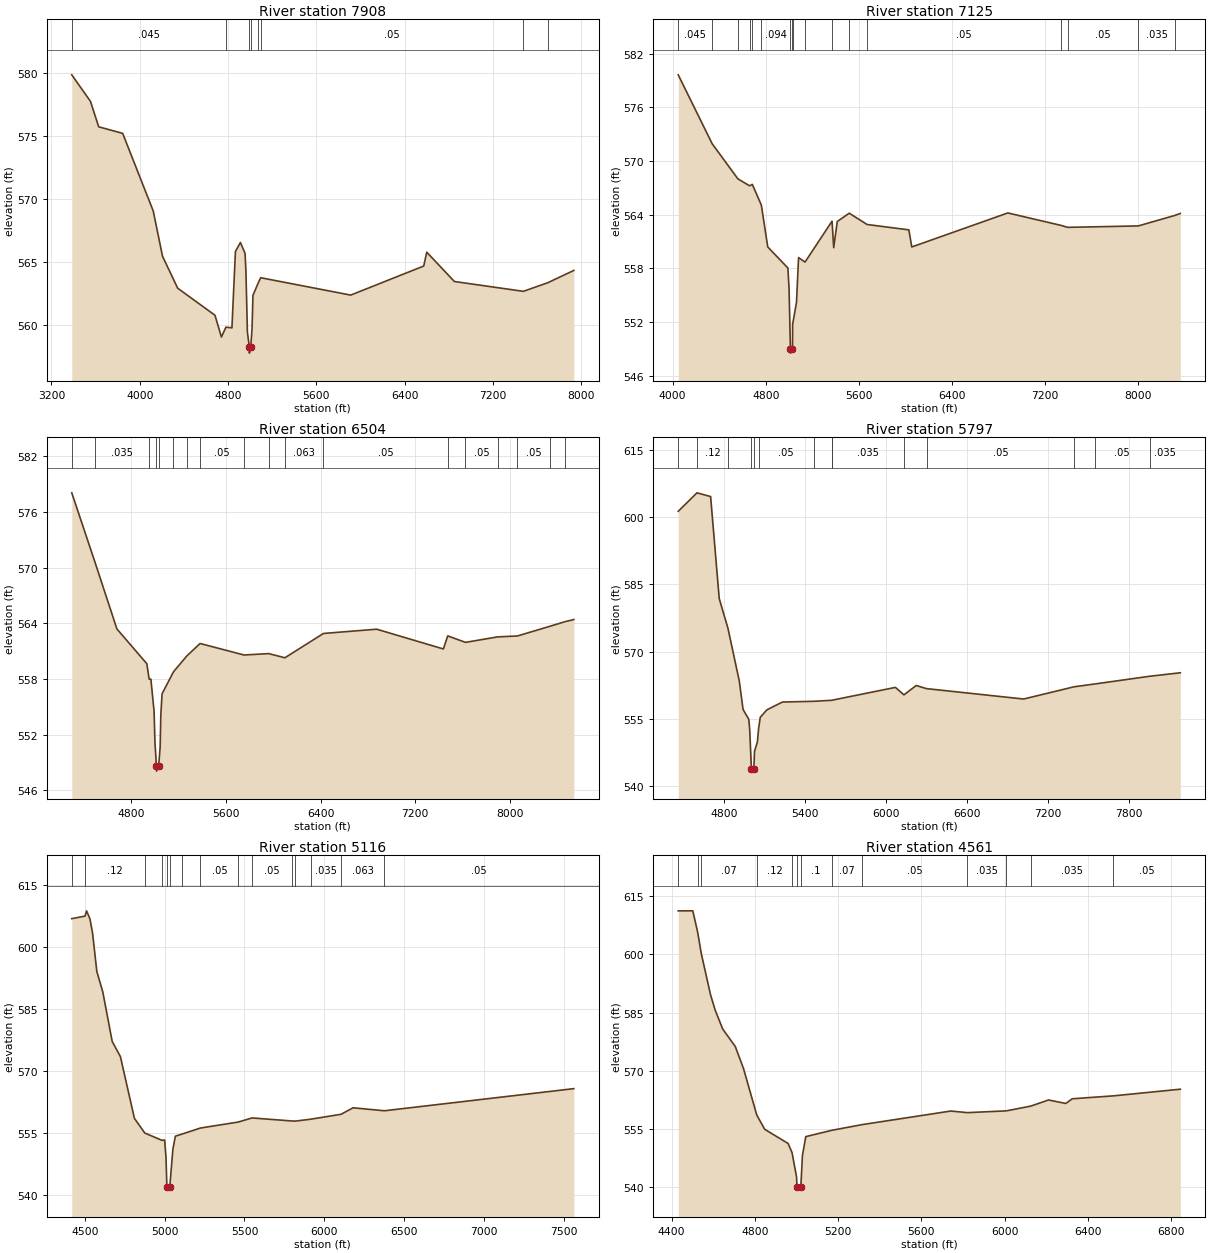
Type RM Length L Ch R = 1 ,7908    ,783,783,783
BEGIN DESCRIPTION:
GUADALUPE TRIBUTARY 20 15.0
END DESCRIPTION:
XS GIS Cut Line= 3
      2277026.03     13781115.03      2275368.03     13780568.15
      2272642.36     13781219.19
#Sta/Elev= 30
  3383.7  579.87  3553.3  577.76  3627.7  575.74  3844.8  575.22  4121.9  569.05
  4206.1  565.45    4343  562.92    4681  560.77  4739.2  559.04  4779.9  559.82
  4834.5  559.77  4866.3  565.84  4911.6  566.55  4953.7  565.68  4961.5  564.22
  4974.8  559.43  4992.2  558.26  4992.7  557.76  5004.9  558.26  5016.9  559.74
    5025  562.35    5075  563.38  5095.4  563.75  5910.6  562.37  6572.1  564.68
  6599.4  565.78  6849.7  563.45  7474.9  562.67    7695  563.35  7931.9  564.33
#Mann= 8 ,-1 , 0
  3383.7    .045       0  4779.9    .094       0  4992.2     .05       0
  5004.9    .094       0    5075    .063       0  5095.4     .05       0
  7474.9    .035       0    7695     .05       0
Bank Sta=4992.2,5004.9
XS Rating Curve= 0 ,0
Exp/Cntr=0.3,0.1

Type RM Length L Ch R = 1 ,7125    ,621,621,621
BEGIN DESCRIPTION:
A19208
END DESCRIPTION:
XS GIS Cut Line= 3
      2276810.71     13779799.06      2275560.74     13780038.64
      2272701.77     13781080.16
#Sta/Elev= 30
  4048.1  579.62  4339.4  571.93  4560.9     568  4661.7  567.22  4685.1  567.38
  4762.6  565.06  4817.6  560.39  4990.7  558.04  5000.8  555.68  5012.3  549.03
  5012.8  548.53  5030.2  549.03  5030.5  549.71  5031.4  551.75  5064.7  554.21
  5082.3   559.2  5137.9   558.7  5370.1  563.27  5384.4  560.31  5414.9  563.23
    5518  564.16  5671.6   562.9  6030.3   562.3  6055.6  560.39  6880.8  564.19
  7341.8  562.79  7395.3  562.58  8002.4  562.74  8316.1  563.91  8363.6  564.13
#Mann= 17 ,-1 , 0
  4048.1    .045       0  4339.4    .035       0  4560.9    .063       0
  4661.7    .094       0  4685.1    .063       0  4762.6    .094       0
  5012.3     .05       0  5030.2    .094       0  5030.5    .063       0
  5137.9    .035       0  5370.1     .05       0    5518    .035       0
  5671.6     .05       0  7341.8    .035       0  7395.3     .05       0
  8002.4    .035       0  8316.1     .05       0
Bank Sta=5012.3,5030.2
XS Rating Curve= 0 ,0
Exp/Cntr=0.3,0.1

Type RM Length L Ch R = 1 ,6504    ,707,707,707
BEGIN DESCRIPTION:
A19207
END DESCRIPTION:
XS GIS Cut Line= 3
      2276461.75     13779304.27      2275779.49     13779413.64
       2272623.2     13781049.07
#Sta/Elev= 30
    4296  578.05  4492.3  570.58  4677.6  563.39  4930.8  559.64  4950.5  557.97
  4965.1  557.98  4992.3  554.49  4999.2  551.21  5012.4  548.57  5012.9  548.07
  5030.4  548.57  5043.5  550.68  5049.1  554.13  5059.6   556.4  5155.7  558.76
  5268.3  560.47    5381  561.82  5752.4  560.58  5961.2  560.73  6098.2  560.28
  6424.4   562.9  6874.3  563.36  7438.5  561.23  7475.4  562.64  7625.4  561.94
  7896.5  562.53  8065.3  562.63  8343.7  563.69  8470.6  564.18  8541.8   564.4
#Mann= 18 ,-1 , 0
    4296     .07       0  4492.3    .035       0  4950.5     .07       0
  5012.4     .05       0  5030.4     .07       0  5155.7     .05       0
  5268.3    .035       0    5381     .05       0  5752.4    .035       0
  5961.2     .05       0  6098.2    .063       0  6424.4     .05       0
  7475.4    .035       0  7625.4     .05       0  7896.5    .035       0
  8065.3     .05       0  8343.7    .035       0  8470.6     .05       0
Bank Sta=5012.4,5030.4
XS Rating Curve= 0 ,0
Exp/Cntr=0.3,0.1

Type RM Length L Ch R = 1 ,5797    ,681,681,681
BEGIN DESCRIPTION:
A19206
END DESCRIPTION:
XS GIS Cut Line= 3
      2275602.38     13778642.83      2275086.78     13779184.47
       2272524.3     13780694.87
#Sta/Elev= 30
  4461.2   601.3  4600.2  605.43  4701.3   604.6  4765.1  581.82  4829.9  575.18
  4913.6  563.45  4941.9  557.05  4984.4  554.85  4991.3  552.46  5003.6  543.79
  5004.1  543.29  5021.7  543.79  5026.8  547.73  5047.9  549.77  5057.1  552.79
  5069.3  555.31  5118.7  556.98    5234  558.72  5465.2  558.88  5601.5  559.11
    5604  559.14  6071.3  561.99  6134.4  560.32  6225.5  562.41  6302.2  561.71
  7021.9  559.39  7396.1  562.12  7549.8  562.75  7955.5  564.47  8183.5  565.25
#Mann= 14 ,-1 , 0
  4461.2     .07       0  4600.2     .12       0  4829.9     .07       0
  5003.6     .05       0  5021.7     .07       0  5057.1     .05       0
  5465.2     .07       0  5601.5     .05       0    5604    .035       0
  6134.4    .063       0  6302.2     .05       0  7396.1    .035       0
  7549.8     .05       0  7955.5    .035       0
Bank Sta=5003.6,5021.7
XS Rating Curve= 0 ,0
Exp/Cntr=0.3,0.1

Type RM Length L Ch R = 1 ,5116    ,555,555,555
BEGIN DESCRIPTION:
A19205
END DESCRIPTION:
XS GIS Cut Line= 3
      2275269.03     13778273.04      2274232.61     13778871.97
      2272519.57     13779803.99
#Sta/Elev= 30
  4417.5  606.91    4501  607.54  4510.1  608.81  4531.6  606.85  4547.4  603.55
  4574.7   594.1    4612  589.17  4670.9  577.17  4722.4   573.5  4810.1  558.56
  4875.2  554.99  4983.4  553.21  4999.6  553.31  5008.2  549.14  5013.7   541.9
  5014.2   541.4  5031.8   541.9  5051.3  551.09  5067.1  554.23  5108.5  554.73
  5224.2   556.2  5461.2  557.65  5547.7  558.64    5800   557.9  5819.4  557.88
    5914  558.33  6105.4  559.53    6181   561.1  6376.9  560.38  7564.7  565.74
#Mann= 15 ,-1 , 0
  4417.5    .035       0    4501     .12       0  4875.2     .07       0
  4983.4     .12       0  5013.7     .05       0  5031.8     .12       0
  5108.5     .07       0  5224.2     .05       0  5461.2    .035       0
  5547.7     .05       0    5800    .035       0  5819.4     .05       0
    5914    .035       0  6105.4    .063       0  6376.9     .05       0
Bank Sta=5013.7,5031.8
XS Rating Curve= 0 ,0
Exp/Cntr=0.3,0.1

Type RM Length L Ch R = 1 ,4561    ,557,557,557
BEGIN DESCRIPTION:
A19204
END DESCRIPTION:
XS GIS Cut Line= 3
      2274987.81     13777871.97      2274248.24     13778226.14
      2272774.63     13778830.16
#Sta/Elev= 30
  4431.5  611.22  4501.5  611.23  4525.1  605.67  4541.7  600.36  4586.7   589.6
  4609.3  585.59  4645.3  580.75  4705.5  576.27  4745.1  570.59  4808.8   558.6
    4847  554.91  4959.5  551.26  4978.4  548.89  5000.1  542.63    5002  539.99
  5002.5  539.49  5020.4  539.99  5028.4  548.19  5044.4  553.02  5168.9  554.65
  5315.2  556.12  5741.5  559.62  5820.8  559.21  6007.5  559.66  6124.6  560.88
  6211.2  562.47    6294  561.57  6324.9  562.78  6522.2  563.53  6844.1  565.25
#Mann= 13 ,-1 , 0
  4431.5     .07       0  4525.1     .12       0  4541.7     .07       0
  4808.8     .12       0  4978.4      .1       0    5002     .05       0
  5020.4      .1       0  5168.9     .07       0  5315.2     .05       0
  5820.8    .035       0  6007.5     .05       0  6124.6    .035       0
  6522.2     .05       0
Bank Sta=5002,5020.4
XS Rating Curve= 0 ,0
Exp/Cntr=0.3,0.1

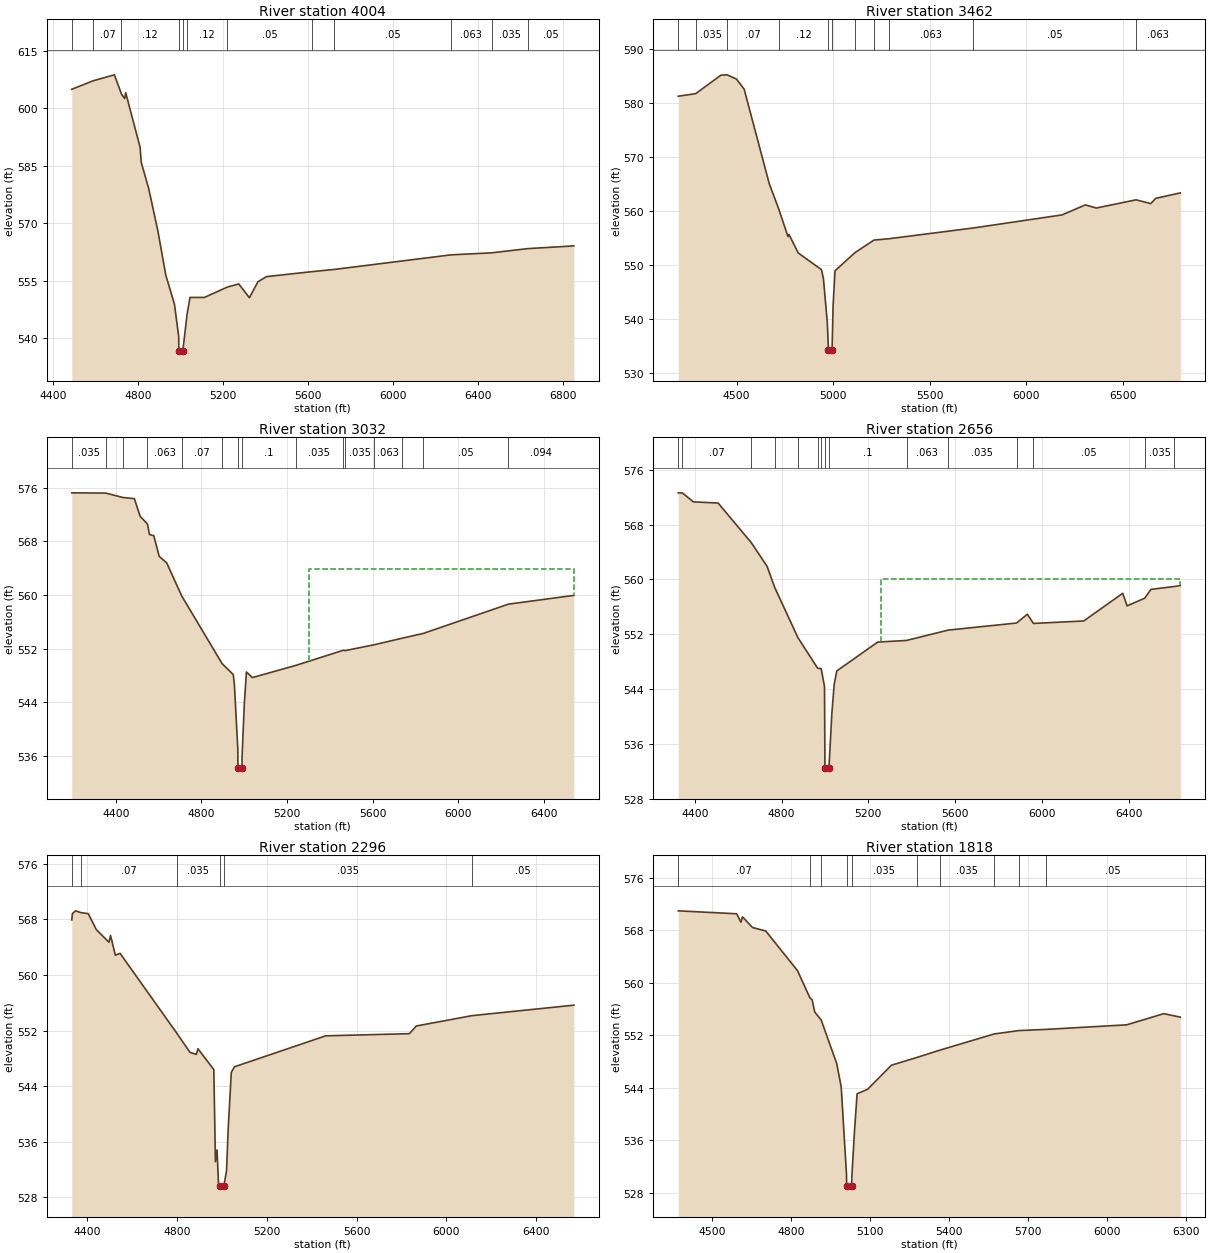
Type RM Length L Ch R = 1 ,4004    ,542,542,542
BEGIN DESCRIPTION:
A19203
END DESCRIPTION:
XS GIS Cut Line= 3
      2274933.86     13777536.73      2273797.68     13777688.22
      2272650.68      13778095.8
#Sta/Elev= 30
  4486.7  604.94  4587.6  607.17  4687.3  608.72  4720.7   603.7  4735.6  602.53
  4740.6  604.06  4808.4  589.78  4813.8  585.85  4848.7  579.06    4892  567.98
  4929.4  556.41  4970.1  548.82    4990  540.39  4990.8  536.55  4991.3  536.05
  5009.3  536.55  5029.3   546.1  5043.3  550.59    5111  550.59  5219.4   553.3
  5272.8  554.11  5322.9  550.52  5363.3   554.7  5403.6  556.03  5618.4  557.33
  5723.2  557.91    6272  561.71  6462.6  562.24    6634  563.34  6850.2  564.05
#Mann= 12 ,-1 , 0
  4486.7    .045       0  4587.6     .07       0  4720.7     .12       0
  4990.8     .05       0  5009.3     .12       0  5029.3     .12       0
  5219.4     .05       0  5618.4     .07       0  5723.2     .05       0
    6272    .063       0  6462.6    .035       0    6634     .05       0
Bank Sta=4990.8,5009.3
XS Rating Curve= 0 ,0
Exp/Cntr=0.3,0.1

Type RM Length L Ch R = 1 ,3462    ,430,430,430
BEGIN DESCRIPTION:
A19202
END DESCRIPTION:
XS GIS Cut Line= 3
      2275135.87      13777093.8      2273959.99      13777147.9
      2272614.62     13777609.58
#Sta/Elev= 30
  4197.4  581.26    4288  581.74  4418.5  585.16  4450.3  585.22  4498.6  584.44
  4538.6  582.57  4668.8  565.06    4717  560.47  4765.7  555.28  4770.7  555.68
  4818.9  552.25  4939.1  549.16  4949.1   547.5  4969.1  539.46  4975.3  534.22
  4975.8  533.72  4993.8  534.22  4999.1  542.43  5009.1  548.95  5111.9   552.3
  5210.6  554.64  5289.1  554.89  5725.8  556.88  6185.3   559.3  6305.1  561.15
  6362.3  560.57    6568  562.09  6643.7  561.39  6669.6  562.36  6796.9  563.37
#Mann= 11 ,-1 , 0
  4197.4    .045       0    4288    .035       0  4450.3     .07       0
    4717     .12       0  4975.3     .05       0  4993.8     .12       0
  5111.9      .1       0  5210.6    .035       0  5289.1    .063       0
  5725.8     .05       0    6568    .063       0
Bank Sta=4975.3,4993.8
XS Rating Curve= 0 ,0
Exp/Cntr=0.3,0.1

Type RM Length L Ch R = 1 ,3032    ,376,376,376
BEGIN DESCRIPTION:
A19201
END DESCRIPTION:
XS GIS Cut Line= 3
       2275175.5     13776806.69      2274140.33     13776687.66
      2272845.44     13776835.54
#Sta/Elev= 30
  4194.1  575.22  4352.9  575.18  4432.8  574.53  4486.5  574.35  4513.5  571.72
  4547.7  570.58    4557  569.01  4577.1  568.84  4602.5  565.76  4637.5  564.78
  4708.1  559.83  4896.3  549.77  4948.7  548.13  4953.8  546.61  4969.7  537.11
  4970.4  534.25  4970.9  533.75    4989  534.25  4989.8  536.08  4999.9  543.65
  5009.9  548.52  5037.8  547.69  5239.3  549.49  5462.6  551.76  5471.2  551.71
  5605.6  552.57  5736.6  553.55  5836.1  554.27  6233.9  558.63  6539.4  559.94
#Mann= 15 ,-1 , 0
  4194.1    .035       0  4352.9     .07       0  4432.8    .035       0
  4547.7    .063       0  4708.1     .07       0  4896.3      .1       0
  4970.4     .05       0    4989      .1       0  5239.3    .035       0
  5462.6    .063       0  5471.2    .035       0  5605.6    .063       0
  5736.6    .035       0  5836.1     .05       0  6233.9    .094       0
#XS Ineff= 2 , 0
       0                    5300       0  563.88
Permanent Ineff=
       F       F
Bank Sta=4970.4,4989
XS Rating Curve= 0 ,0
Exp/Cntr=0.3,0.1

Type RM Length L Ch R = 1 ,2656    ,360,360,360
BEGIN DESCRIPTION:
A19200
END DESCRIPTION:
XS GIS Cut Line= 3
      2275135.87     13776698.49        2274382.       13776345.
      2272899.73       13776345.
#Sta/Elev= 30
  4323.4  572.63  4342.7  572.61  4393.3  571.31  4507.4  571.14  4660.7  565.34
    4733  561.91    4768  558.85  4875.3   551.5  4966.2  547.05  4982.5  546.99
  4997.8  544.36  4999.8  532.54  5000.3  532.04  5018.4  532.54  5031.6  540.39
  5042.3  544.65  5054.4  546.65    5243  550.86    5376   551.1  5568.6  552.61
  5883.1  553.64    5933  554.92  5961.3  553.58    6193  553.94    6373  557.98
    6393  556.14    6474  557.26    6503  558.55  6611.5  558.97  6638.3  559.11
#Mann= 15 ,-1 , 0
  4323.4    .035       0  4342.7     .07       0  4660.7    .063       0
    4768    .035       0  4875.3    .063       0  4966.2    .035       0
  4982.5      .1       0  4999.8     .05       0  5018.4      .1       0
    5376    .063       0  5568.6    .035       0  5883.1     .07       0
  5961.3     .05       0    6474    .035       0  6611.5    .063       0
#XS Ineff= 2 , 0
       0                    5260       0     560
Permanent Ineff=
       F       F
Bank Sta=4999.8,5018.4
XS Rating Curve= 0 ,0
Exp/Cntr=0.3,0.1

Type RM Length L Ch R = 1 ,2296    ,478,478,478
BEGIN DESCRIPTION:
A19199
END DESCRIPTION:
XS GIS Cut Line= 3
      2275161.07     13776583.04      2274594.81     13776020.38
      2273168.27     13775854.67
#Sta/Elev= 30
  4332.6  567.92  4335.5  568.83  4349.7  569.23    4373  568.97  4406.2  568.82
  4441.6  566.54  4498.1  564.71  4505.2  565.69  4526.4  562.85  4547.6  563.11
    4799  551.68  4858.8  548.87  4887.1  548.58  4894.1  549.39  4964.8   546.4
  4971.9  533.15    4979  534.84  4986.1  529.73  4990.9   529.7  4991.4   529.2
  5009.6   529.7  5021.4  531.83  5028.5   537.7  5042.6  545.99  5056.8   546.8
  5462.9  551.25  5835.4  551.56  5865.6  552.66  6113.4  554.15    6567  555.66
#Mann= 6 ,-1 , 0
  4332.6    .035       0    4373     .07       0    4799    .035       0
  4990.9    .035       0  5009.6    .035       0  6113.4     .05       0
Bank Sta=4990.9,5009.6
XS Rating Curve= 0 ,0
Exp/Cntr=0.3,0.1

Type RM Length L Ch R = 1 ,1818    ,372,372,372
BEGIN DESCRIPTION:
A19198
END DESCRIPTION:
XS GIS Cut Line= 3
      2275399.16     13775951.85      2274980.75     13775731.82
       2273552.4     13775598.37
#Sta/Elev= 30
  4370.9  570.95  4592.8   570.5  4609.2  569.22  4614.9  570.03  4653.3   568.4
  4703.3  567.88    4824  561.83    4871   557.7  4879.5  557.38  4889.6  555.51
  4913.9  554.31  4972.8  547.69    4990  544.11  5010.1  530.76  5010.7  529.02
  5011.2  528.52  5029.6  529.02  5030.2  530.25  5040.2  537.19  5050.3  543.05
  5090.5  543.75  5180.8  547.41  5278.8  548.61  5364.2   549.7  5571.3  552.18
  5664.5  552.69  5767.4  552.87  6074.7  553.57  6215.3  555.27  6278.2  554.74
#Mann= 10 ,-1 , 0
  4370.9     .07       0    4871      .1       0  4913.9    .035       0
  5010.7    .035       0  5029.6    .035       0  5278.8    .063       0
  5364.2    .035       0  5571.3    .063       0  5664.5    .035       0
  5767.4     .05       0
Bank Sta=5010.7,5029.6
XS Rating Curve= 0 ,0
Exp/Cntr=0.3,0.1

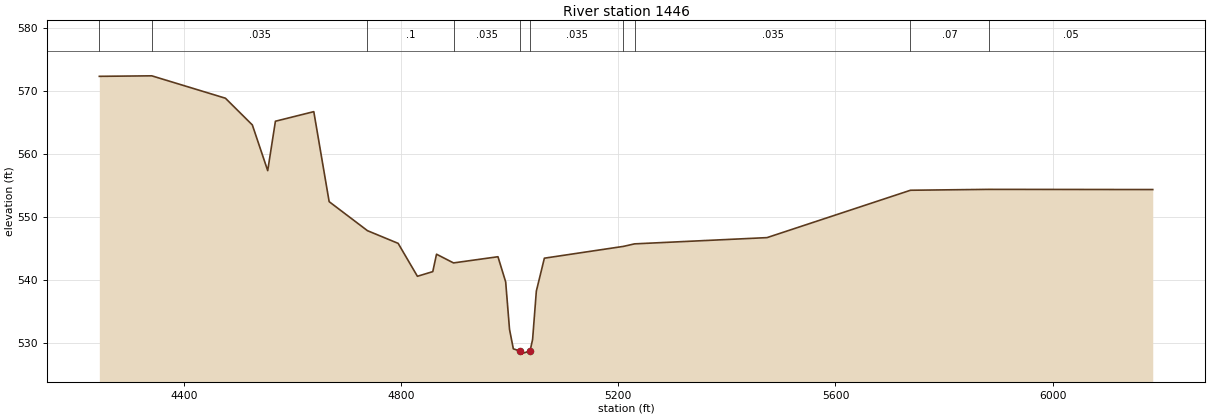
Type RM Length L Ch R = 1 ,1446    ,0,0,0
BEGIN DESCRIPTION:
A19197
END DESCRIPTION:
XS GIS Cut Line= 3
        2275410.     13775908.59      2274843.68     13775327.85
      2273714.72     13775291.78
#Sta/Elev= 30
  4243.8  572.28  4340.4  572.36  4476.1  568.81  4525.7  564.57    4554  557.33
  4568.2  565.16  4638.9  566.68  4667.2  552.41  4737.8  547.81  4794.3   545.8
  4829.8  540.58  4858.1  541.32    4865  544.08  4896.3   542.7  4978.2  543.68
  4992.4  539.69  4999.5  532.16  5006.5  529.08  5018.4  528.74  5018.9  528.24
  5037.3  528.74    5042  530.56  5048.9  538.23  5063.7  543.45  5209.3  545.32
  5229.9  545.72  5473.9  546.71  5738.2  554.22  5882.8  554.36  6184.5  554.33
#Mann= 10 ,-1 , 0
  4243.8     .07       0  4340.4    .035       0  4737.8      .1       0
  4896.3    .035       0  5018.4    .035       0  5037.3    .035       0
  5209.3      .1       0  5229.9    .035       0  5738.2     .07       0
  5882.8     .05       0
Bank Sta=5018.4,5037.3
XS Rating Curve= 0 ,0
Exp/Cntr=0.3,0.1

Chan Stop Cuts=-1
Use User Specified Reach Order=0
Composite Channel Slope=5