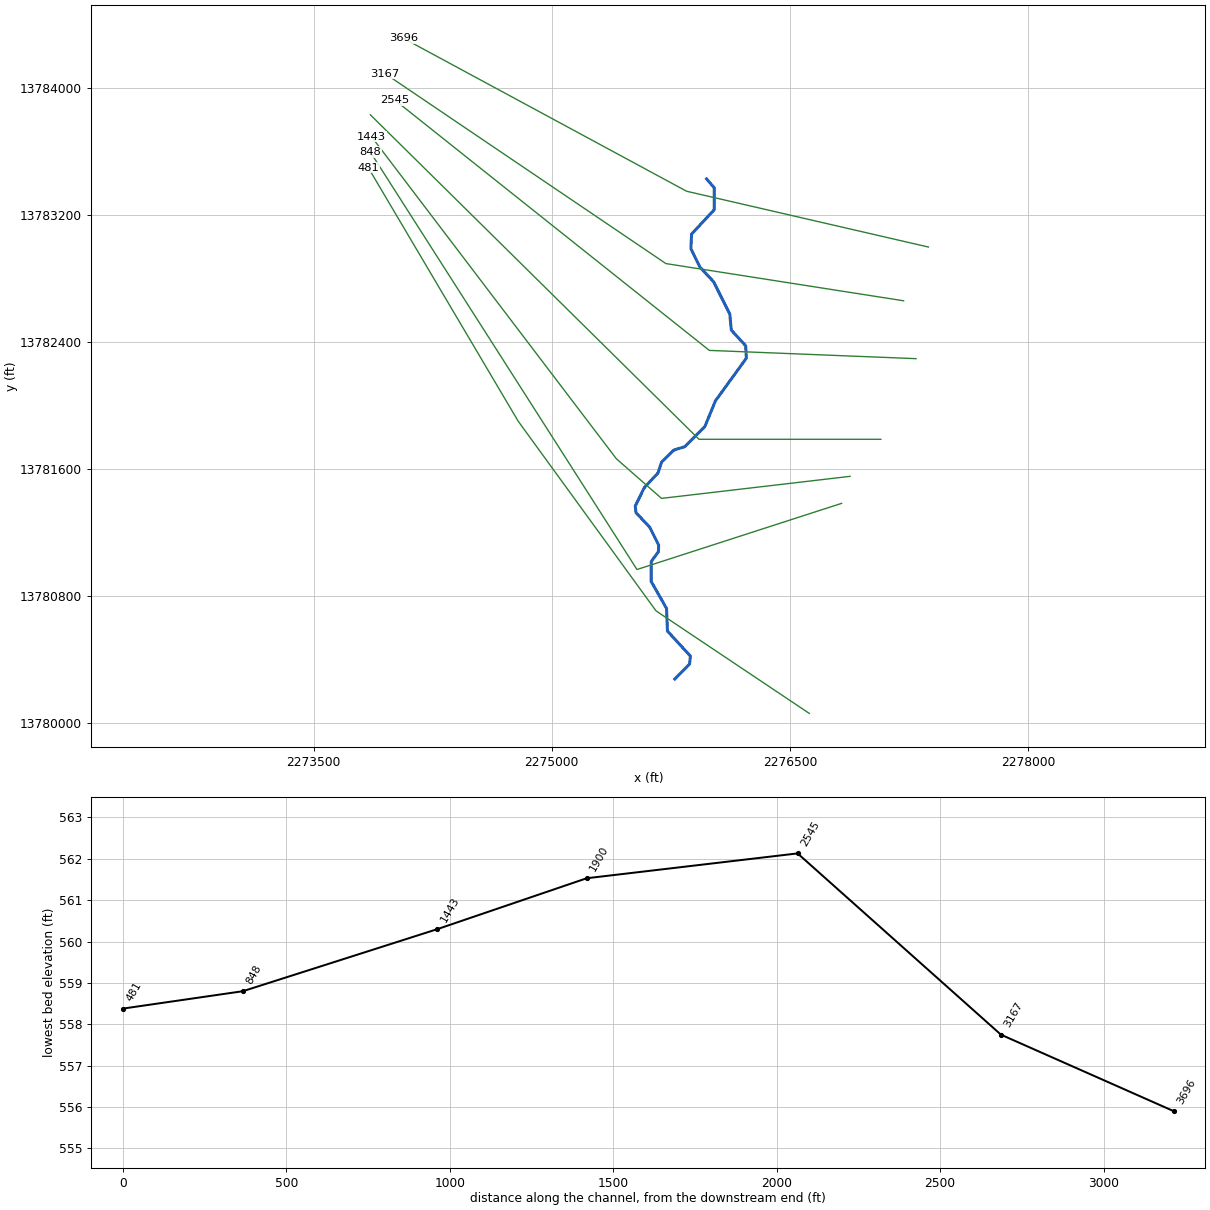
--- GUADALUPE TRIBUTARY 21.prj (project) ---

Proj Title=GUADALUPE TRIBUTARY 21 Base Level Engineering
Current Plan=p01
Default Exp/Contr=0.3,0.1
English Units
Geom File=g01
Flow File=f01
Plan File=p01
BEGIN DESCRIPTION:
GUADALUPE TRIBUTARY 21
END DESCRIPTION:

--- GUADALUPE TRIBUTARY 21.p01 (plan) ---

Plan Title=Multiple Run
Short Identifier=Multiple
Geom File=g01
Flow File=f01
Subcritical Flow
K Sum by GR= 0
Std Step Tol= 0.01
Critical Tol= 0.01
Num of Std Step Trials= 20
Max Error Tol= 0.3
Flow Tol Ratio= 0.001
Split Flow NTrial= 30
Split Flow Tol= 0.02
Split Flow Ratio= 0.02
Log Output Level= 0
Friction Slope Method= 1
Unsteady Friction Slope Method= 2
Unsteady Bridges Friction Slope Method= 1
Parabolic Critical Depth
Global Vel Dist=  1 , 1 , 1
Global Log Level= 0
CheckData=True
Encroach Param= -1, 0, 0, 0
BEGIN DESCRIPTION:
Multiple Run
END DESCRIPTION:

--- GUADALUPE TRIBUTARY 21.f01 (steady flow) ---

Flow Title=Multiple
Number of Profiles=7
Profile Names=10-year,25-year,50-year,1pct_min,100-year,1pct_plu,500-year
River Rch & RM= GUADALUPE TRIBUT,Reach-1,3696
     872    1422    1923    1257    2509    5006    4225
River Rch & RM= GUADALUPE TRIBUT,Reach-1,2545
    1304    2174    2985    1979    3948    7877    6840
River Rch & RM= GUADALUPE TRIBUT,Reach-1,848
    1503    2522    3477    2312    4614    9206    8049
Boundary for River Rch & Prof#=GUADALUPE TRIBUT,Reach-1,1
Up Type=0
Dn Type=3
Dn Slope=0.005
Boundary for River Rch & Prof#=GUADALUPE TRIBUT,Reach-1,2
Up Type=0
Dn Type=3
Dn Slope=0.005
Boundary for River Rch & Prof#=GUADALUPE TRIBUT,Reach-1,3
Up Type=0
Dn Type=3
Dn Slope=0.005
Boundary for River Rch & Prof#=GUADALUPE TRIBUT,Reach-1,4
Up Type=0
Dn Type=3
Dn Slope=0.005
Boundary for River Rch & Prof#=GUADALUPE TRIBUT,Reach-1,5
Up Type=0
Dn Type=3
Dn Slope=0.005
Boundary for River Rch & Prof#=GUADALUPE TRIBUT,Reach-1,6
Up Type=0
Dn Type=3
Dn Slope=0.005
Boundary for River Rch & Prof#=GUADALUPE TRIBUT,Reach-1,7
Up Type=0
Dn Type=3
Dn Slope=0.005

--- GUADALUPE TRIBUTARY 21.g01 (geometry) ---

Geom Title=Existing Conditions

River Reach=GUADALUPE TRIBUT,Reach-1
Reach XY= 30
      2275975.00     13783425.00      2276023.12     13783369.21
      2276022.96     13783230.85      2275880.40     13783077.43
      2275876.08     13782985.55      2275933.16     13782868.95
      2276019.15     13782777.29      2276121.17     13782573.41
      2276130.54     13782472.58      2276221.53     13782373.50
      2276225.21     13782295.06      2276030.85     13782027.29
      2275964.24     13781865.32      2275838.21     13781738.63
      2275768.93     13781716.85      2275691.64     13781641.71
      2275669.13     13781572.72      2275583.15     13781481.05
      2275525.70     13781364.30      2275530.10     13781322.71
      2275616.84     13781231.05      2275673.20     13781118.89
      2275671.63     13781076.74      2275626.23     13781014.50
      2275625.49     13780890.22      2275722.75     13780719.07
      2275728.54     13780576.47      2275873.43     13780418.96
      2275867.64     13780368.93      2275775.00     13780275.00

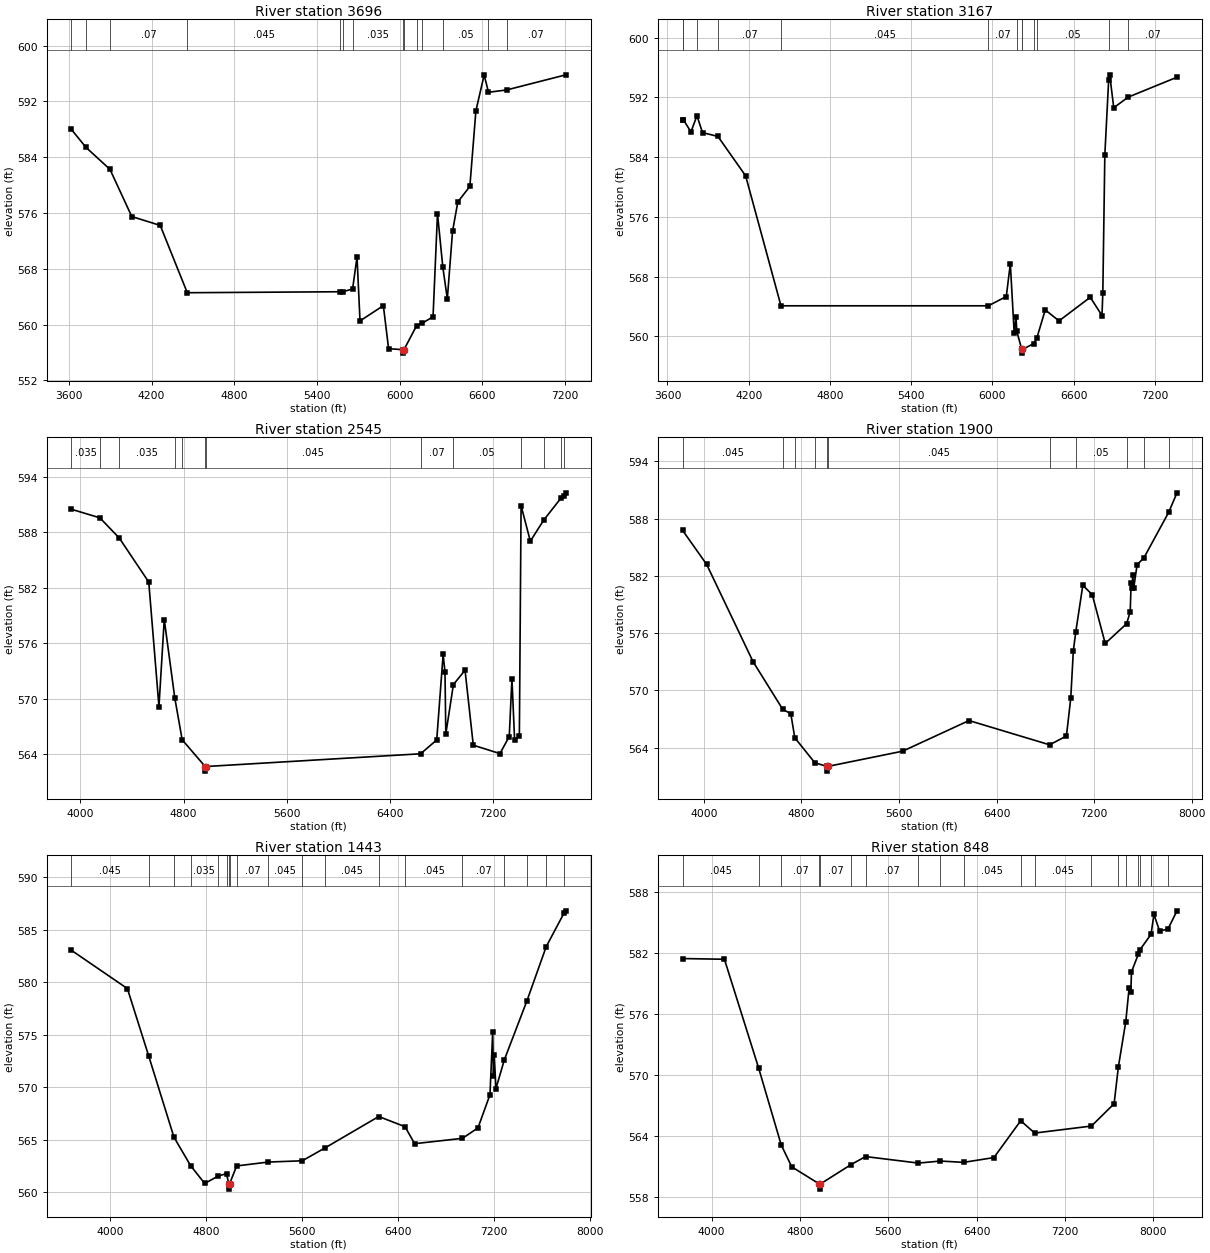
Type RM Length L Ch R = 1,3696,529,529,529
BEGIN DESCRIPTION:
9054
END DESCRIPTION:
XS GIS Cut Line= 3
      2277372.41     13782995.83      2275848.96     13783347.40
      2274065.93     13784310.49
#Sta/Elev= 30
  3617.6  587.97  3724.0  585.39  3897.6  582.25  4056.2  575.48  4262.7  574.21
  4459.0  564.56  5566.6  564.70  5586.7  564.69  5659.4  565.09  5691.5  569.69
  5713.3  560.52  5882.8  562.71  5920.8  556.53  6027.9  556.40  6028.2  555.90
  6032.7  556.40  6124.4  559.84  6161.9  560.15  6243.5  561.12  6275.9  575.91
  6314.7  568.20  6347.2  563.67  6385.3  573.39  6423.4  577.57  6510.9  579.81
  6554.7  590.64  6614.7  595.79  6646.1  593.30  6777.6  593.63  7207.6  595.80
#Mann=14,-1,0
  3617.6   0.035       0  3724.0   0.045       0  3897.6    0.07       0
  4459.0   0.045       0  5566.6   0.035       0  5586.7    0.07       0
  5659.4   0.035       0  6027.9   0.045       0  6032.7   0.035       0
  6124.4    0.07       0  6161.9   0.035       0  6314.7    0.05       0
  6646.1   0.035       0  6777.6    0.07       0
Bank Sta=6027.9,6032.7
Exp/Cntr=0.3,0.1

Type RM Length L Ch R = 1,3167,622,622,622
BEGIN DESCRIPTION:
9053
END DESCRIPTION:
XS GIS Cut Line= 3
      2277216.10     13782657.30      2275718.75     13782891.67
      2273948.94     13784088.89
#Sta/Elev= 30
  3711.8  588.97  3718.0  589.01  3773.6  587.39  3818.2  589.55  3859.1  587.29
  3972.9  586.78  4177.7  581.50  4438.7  564.09  5970.3  564.09  6103.1  565.33
  6133.0  569.73  6161.5  560.45  6175.0  562.56  6180.8  560.66  6217.5  558.25
  6217.8  557.75  6222.3  558.25  6305.5  559.02  6328.6  559.76  6390.9  563.54
  6492.6  562.07  6723.3  565.23  6810.1  562.79  6816.2  565.82  6831.1  584.32
  6859.3  594.30  6867.1  595.03  6897.0  590.62  7003.1  592.04  7364.1  594.71
#Mann=13,-1,0
  3711.8    0.07       0  3718.0   0.045       0  3818.2   0.035       0
  3972.9    0.07       0  4438.7   0.045       0  5970.3    0.07       0
  6180.8    0.05       0  6217.5   0.045       0  6222.3    0.05       0
  6305.5    0.07       0  6328.6    0.05       0  6859.3   0.035       0
  7003.1    0.07       0
Bank Sta=6217.5,6222.3
Exp/Cntr=0.3,0.1

Type RM Length L Ch R = 1,2545,645,645,645
BEGIN DESCRIPTION:
9052
END DESCRIPTION:
XS GIS Cut Line= 3
      2277294.25     13782292.71      2275992.19     13782344.79
      2274013.26     13783920.13
#Sta/Elev= 30
  3930.7  590.51  4151.5  589.58  4302.0  587.39  4530.4  582.62  4609.5  569.13
  4650.5  578.56  4732.1  570.07  4789.4  565.53  4967.5  562.63  4968.0  562.13
  4974.0  562.63  6637.8  564.01  6762.6  565.51  6812.2  574.78  6826.6  572.89
  6833.0  566.15  6891.8  571.51  6982.0  573.07  7046.0  564.94  7252.6  564.03
  7324.7  565.88  7345.6  572.15  7366.4  565.45  7403.1  565.95  7416.5  590.90
  7488.1  587.05  7591.2  589.32  7725.7  591.72  7746.2  591.96  7763.2  592.29
#Mann=13,-1,0
  3930.7   0.035       0  4151.5   0.045       0  4302.0   0.035       0
  4732.1    0.07       0  4789.4   0.045       0  4967.5   0.045       0
  4974.0   0.045       0  6637.8    0.07       0  6891.8    0.05       0
  7416.5   0.035       0  7591.2    0.07       0  7725.7    0.05       0
  7746.2    0.07       0
Bank Sta=4967.5,4974
Exp/Cntr=0.3,0.1

Type RM Length L Ch R = 1,1900,457,457,457
BEGIN DESCRIPTION:
9051
END DESCRIPTION:
XS GIS Cut Line= 3
      2277072.89     13781784.90      2275927.08     13781784.90
      2273856.78     13783829.16
#Sta/Elev= 30
  3824.5  586.77  4022.4  583.19  4402.4  573.01  4646.4  568.00  4712.4  567.55
  4744.9  565.03  4910.5  562.39  5010.9  562.03  5011.4  561.53  5017.8  562.03
  5629.5  563.62  6174.0  566.83  6834.9  564.29  6973.0  565.21  7008.4  569.17
  7029.6  574.13  7049.2  576.09  7107.4  581.01  7185.1  580.02  7291.2  574.91
  7467.0  576.99  7496.3  578.25  7503.3  581.24  7510.4  580.77  7517.4  582.11
  7524.6  580.72  7552.8  583.17  7608.6  583.89  7811.7  588.66  7879.8  590.70
#Mann=11,-1,0
  3824.5   0.045       0  4646.4    0.07       0  4744.9   0.035       0
  4910.5   0.045       0  5010.9   0.045       0  5017.8   0.045       0
  6834.9    0.07       0  7049.2    0.05       0  7467.0   0.035       0
  7608.6    0.05       0  7811.7    0.07       0
Bank Sta=5010.9,5017.8
Exp/Cntr=0.3,0.1

Type RM Length L Ch R = 1,1443,595,595,595
BEGIN DESCRIPTION:
A19217
END DESCRIPTION:
XS GIS Cut Line= 4
      2276878.69     13781551.39      2275691.16     13781412.50
      2275406.43     13781662.50      2273864.89     13783690.12
#Sta/Elev= 30
  3677.6  583.06  4144.4  579.41  4321.5  573.01  4532.5  565.25  4671.3  562.54
  4788.8  560.84  4900.6  561.54  4970.9  561.78  4989.2  560.80  4989.7  560.30
  4996.1  560.80  5055.3  562.51  5318.6  562.88  5602.3  563.00  5795.3  564.25
  6239.8  567.22  6458.8  566.25  6538.9  564.63  6937.8  565.14  7067.1  566.14
  7166.9  569.30  7189.7  575.27  7196.0  571.09  7202.4  573.07  7216.8  569.88
  7286.6  572.62  7473.0  578.18  7635.9  583.41  7783.5  586.59  7799.2  586.82
#Mann=19,-1,0
  3677.6   0.045       0  4321.5   0.035       0  4532.5   0.045       0
  4671.3   0.035       0  4900.6    0.07       0  4970.9   0.045       0
  4989.2   0.045       0  4996.1   0.045       0  5055.3    0.07       0
  5318.6   0.045       0  5602.3    0.07       0  5795.3   0.045       0
  6239.8   0.035       0  6458.8   0.045       0  6937.8    0.07       0
  7286.6    0.05       0  7473.0   0.035       0  7635.9    0.05       0
  7783.5    0.07       0
Bank Sta=4989.2,4996.1
Exp/Cntr=0.3,0.1

Type RM Length L Ch R = 1,848,367,367,367
BEGIN DESCRIPTION:
9050
END DESCRIPTION:
XS GIS Cut Line= 3
      2276825.52     13781381.25      2275536.46     13780964.58
      2273856.78     13783594.77
#Sta/Elev= 30
  3737.9  581.46  4116.8  581.39  4426.0  570.72  4631.0  563.14  4726.3  560.99
  4977.1  559.30  4977.6  558.80  4984.1  559.30  5262.8  561.21  5393.9  562.00
  5872.8  561.36  6071.8  561.56  6282.2  561.43  6556.2  561.90  6798.8  565.52
  6925.2  564.31  7439.1  565.00  7644.1  567.19  7682.9  570.82  7749.5  575.24
  7780.3  578.59  7795.6  578.16  7801.5  580.15  7862.9  581.87  7874.8  582.27
  7978.7  583.85  8004.5  585.80  8056.1  584.17  8131.7  584.36  8213.4  586.15
#Mann=19,-1,0
  3737.9   0.045       0  4426.0   0.035       0  4631.0    0.07       0
  4977.1    0.05       0  4984.1    0.07       0  5262.8   0.035       0
  5393.9    0.07       0  5872.8   0.045       0  6071.8    0.07       0
  6282.2   0.045       0  6798.8   0.035       0  6925.2   0.045       0
  7439.1    0.07       0  7682.9    0.05       0  7749.5    0.07       0
  7862.9    0.05       0  7874.8    0.07       0  7978.7   0.035       0
  8131.7    0.05       0
Bank Sta=4977.1,4984.1
Exp/Cntr=0.3,0.1

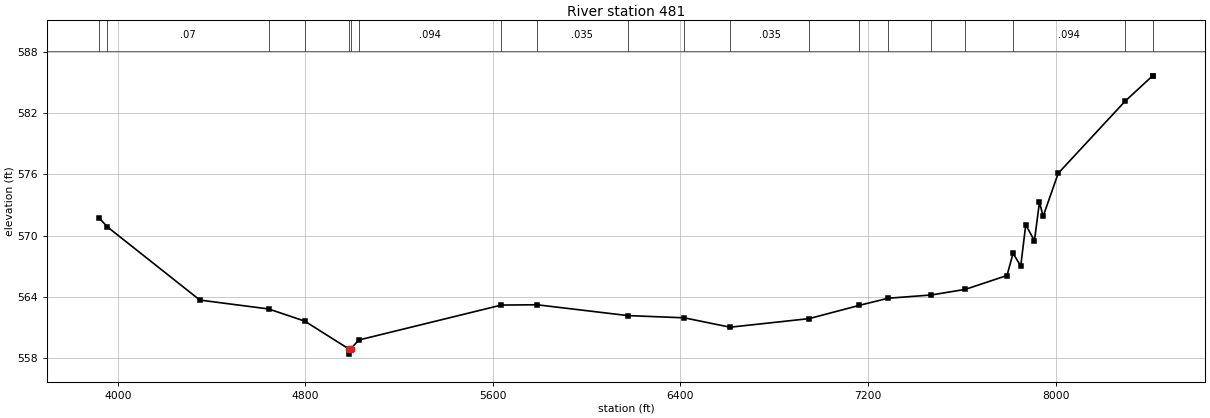
Type RM Length L Ch R = 1,481,0,0,0
BEGIN DESCRIPTION:
A19216
END DESCRIPTION:
XS GIS Cut Line= 4
      2276621.73     13780058.32      2275656.43     13780704.17
      2274788.38     13781898.61      2273843.96     13783495.79
#Sta/Elev= 30
  3921.2  571.72  3954.8  570.87  4350.1  563.68  4643.2  562.81  4797.0  561.62
  4986.1  558.88  4986.6  558.38  4993.2  558.88  5027.3  559.76  5636.0  563.19
  5788.2  563.22  6175.1  562.16  6416.5  561.94  6611.6  561.02  6948.7  561.86
  7162.6  563.16  7285.8  563.86  7470.1  564.18  7615.2  564.73  7793.0  566.09
  7818.9  568.27  7851.5  567.01  7873.0  571.06  7910.0  569.50  7931.5  573.28
  7947.1  571.89  8011.4  576.11  8297.2  583.19  8414.0  585.67  8414.7  585.67
#Mann=20,-1,0
  3921.2   0.045       0  3954.8    0.07       0  4643.2    0.07       0
  4797.0   0.045       0  4986.1   0.045       0  4993.2   0.045       0
  5027.3   0.094       0  5636.0    0.07       0  5788.2   0.035       0
  6175.1   0.045       0  6416.5   0.035       0  6611.6   0.035       0
  6948.7   0.045       0  7162.6   0.094       0  7285.8   0.063       0
  7470.1   0.045       0  7615.2   0.094       0  7818.9   0.094       0
  8297.2   0.035       0  8414.0    0.05       0
Bank Sta=4986.1,4993.2
Exp/Cntr=0.3,0.1

Chan Stop Cuts=-1