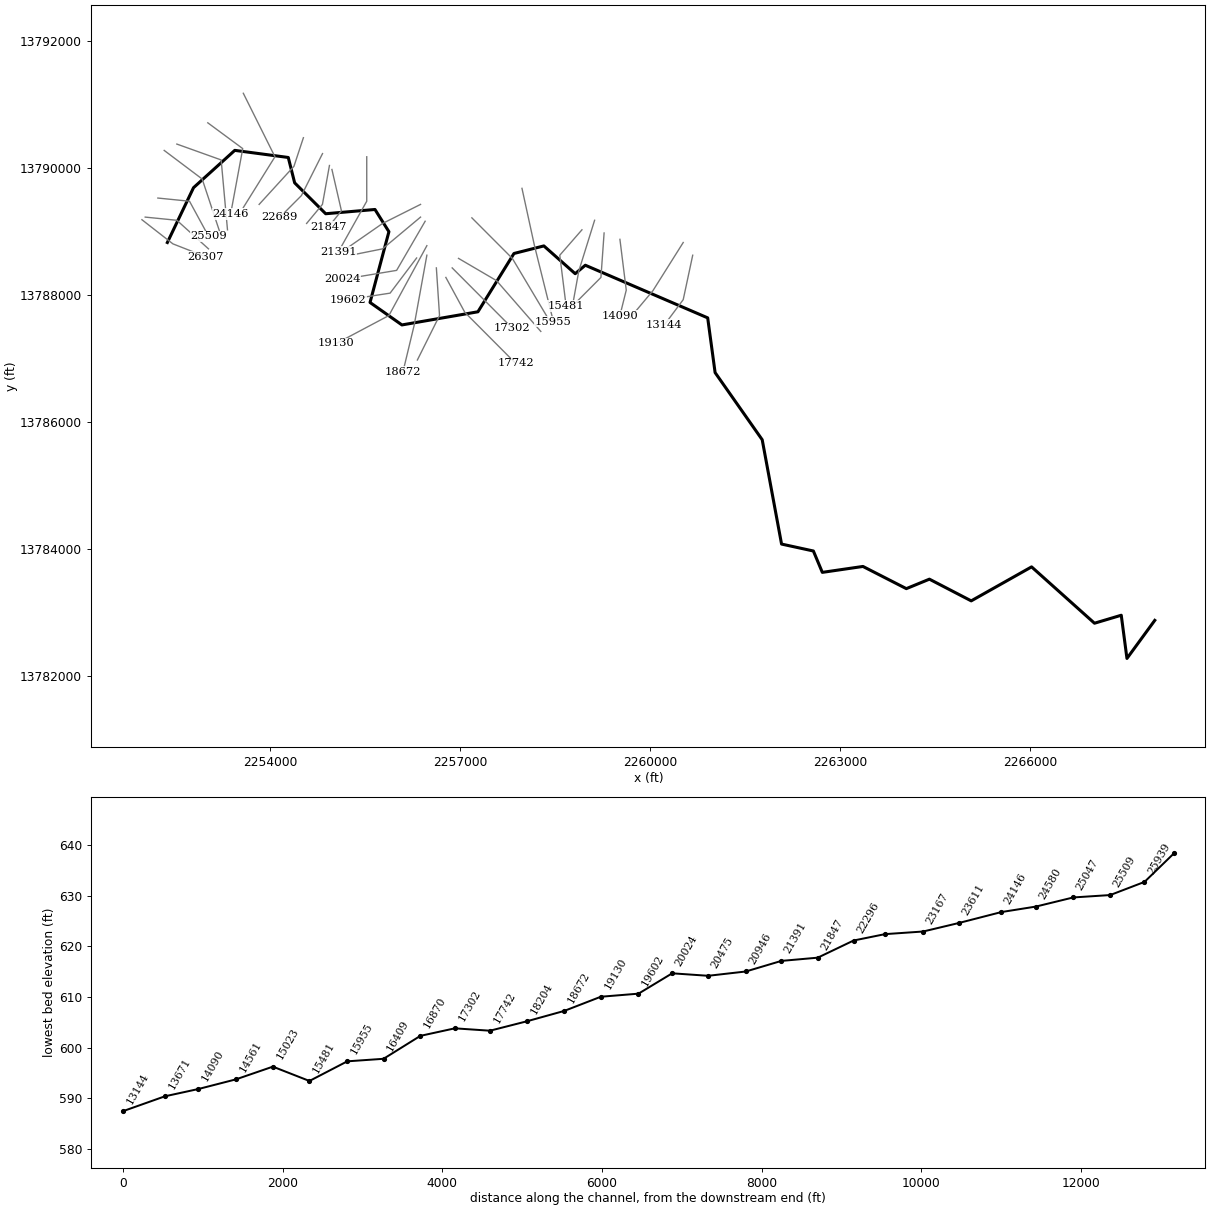
--- GUADALUPE TRIBUTARY 22.prj (project) ---

Proj Title=GUADALUPE TRIBUTARY 22 Base Level Engineering
Current Plan=p01
Default Exp/Contr=0.3,0.1
English Units
Geom File=g01
Flow File=f01
Plan File=p01
Y Axis Title=Elevation
X Axis Title(PF)=Main Channel Distance
X Axis Title(XS)=Station
BEGIN DESCRIPTION:
GUADALUPE TRIBUTARY 22
END DESCRIPTION:
DSS Export Rating Curves= 0
DSS Export Rating Curve Sorted= 0
DSS Export Volume Flow Curves= 0
DXF OffsetX= 0
DXF OffsetY= 0
DXF ScaleX= 1
DXF ScaleY= 10

--- GUADALUPE TRIBUTARY 22.p01 (plan) ---

Plan Title=Multiple Run
Short Identifier=Multiple
Geom File=g01
Flow File=f01
Subcritical Flow
K Sum by GR= 0
Std Step Tol= 0.01
Critical Tol= 0.01
Num of Std Step Trials= 20
Max Error Tol= 0.3
Flow Tol Ratio= 0.001
Split Flow NTrial= 30
Split Flow Tol= 0.02
Split Flow Ratio= 0.02
Log Output Level= 0
Friction Slope Method= 1
Unsteady Friction Slope Method= 2
Unsteady Bridges Friction Slope Method= 1
Parabolic Critical Depth
Global Vel Dist=  1 , 1 , 1
Global Log Level= 0
CheckData=True
Encroach Param= -1, 0, 0, 0
BEGIN DESCRIPTION:
Multiple Run
END DESCRIPTION:

--- GUADALUPE TRIBUTARY 22.f01 (steady flow) ---

Flow Title=Multiple
Number of Profiles=7
Profile Names=10-year,25-year,50-year,1pct_min,100-year,1pct_plu,500-year
River Rch & RM= GUADALUPE TRIBUT,Reach-1,26307
     873    1433    1948    1281    2556    5101    4356
River Rch & RM= GUADALUPE TRIBUT,Reach-1,24580
    1081    1782    2429    1599    3190    6366    5450
River Rch & RM= GUADALUPE TRIBUT,Reach-1,18672
    1439    2406    3309    2195    4380    8739    7603
River Rch & RM= GUADALUPE TRIBUT,Reach-1,15481
    1723    2903    4012    2674    5335   10645    9347
River Rch & RM= GUADALUPE TRIBUT,Reach-1,8801
    1870    3149    4350    2896    5779   11531   10105
Boundary for River Rch & Prof#=GUADALUPE TRIBUT,Reach-1,1
Up Type=0
Dn Type=3
Dn Slope=0.005
Boundary for River Rch & Prof#=GUADALUPE TRIBUT,Reach-1,2
Up Type=0
Dn Type=3
Dn Slope=0.005
Boundary for River Rch & Prof#=GUADALUPE TRIBUT,Reach-1,3
Up Type=0
Dn Type=3
Dn Slope=0.005
Boundary for River Rch & Prof#=GUADALUPE TRIBUT,Reach-1,4
Up Type=0
Dn Type=3
Dn Slope=0.005
Boundary for River Rch & Prof#=GUADALUPE TRIBUT,Reach-1,5
Up Type=0
Dn Type=3
Dn Slope=0.005
Boundary for River Rch & Prof#=GUADALUPE TRIBUT,Reach-1,6
Up Type=0
Dn Type=3
Dn Slope=0.005
Boundary for River Rch & Prof#=GUADALUPE TRIBUT,Reach-1,7
Up Type=0
Dn Type=3
Dn Slope=0.005

--- GUADALUPE TRIBUTARY 22.g01 (geometry) ---

Geom Title=Existing Conditions
Program Version=4.10

River Reach=GUADALUPE TRIBUT,Reach-1
Reach XY= 30
        2252375.       13788825.      2252788.54     13789688.38
      2253440.07     13790275.79      2254285.32     13790163.89
      2254386.11     13789764.68       2254876.4     13789278.06
      2255655.21     13789345.09      2255875.37      13788995.2
      2255577.04     13787880.85      2256080.86     13787527.06
      2257281.74     13787734.13      2257851.05     13788652.17
      2258323.48     13788771.26      2258818.33     13788333.95
      2258978.23     13788467.17      2260911.61     13787638.33
      2261028.75     13786776.55      2261772.94     13785719.15
      2262078.61     13784076.48       2262581.5     13783967.38
       2262722.7      13783630.8      2263364.52     13783724.07
      2264050.02     13783374.59       2264414.5      13783523.8
        2265075.     13783182.09      2266028.66     13783717.33
      2267022.69     13782830.08      2267445.48     13782955.74
      2267535.47     13782275.48        2267975.       13782875.

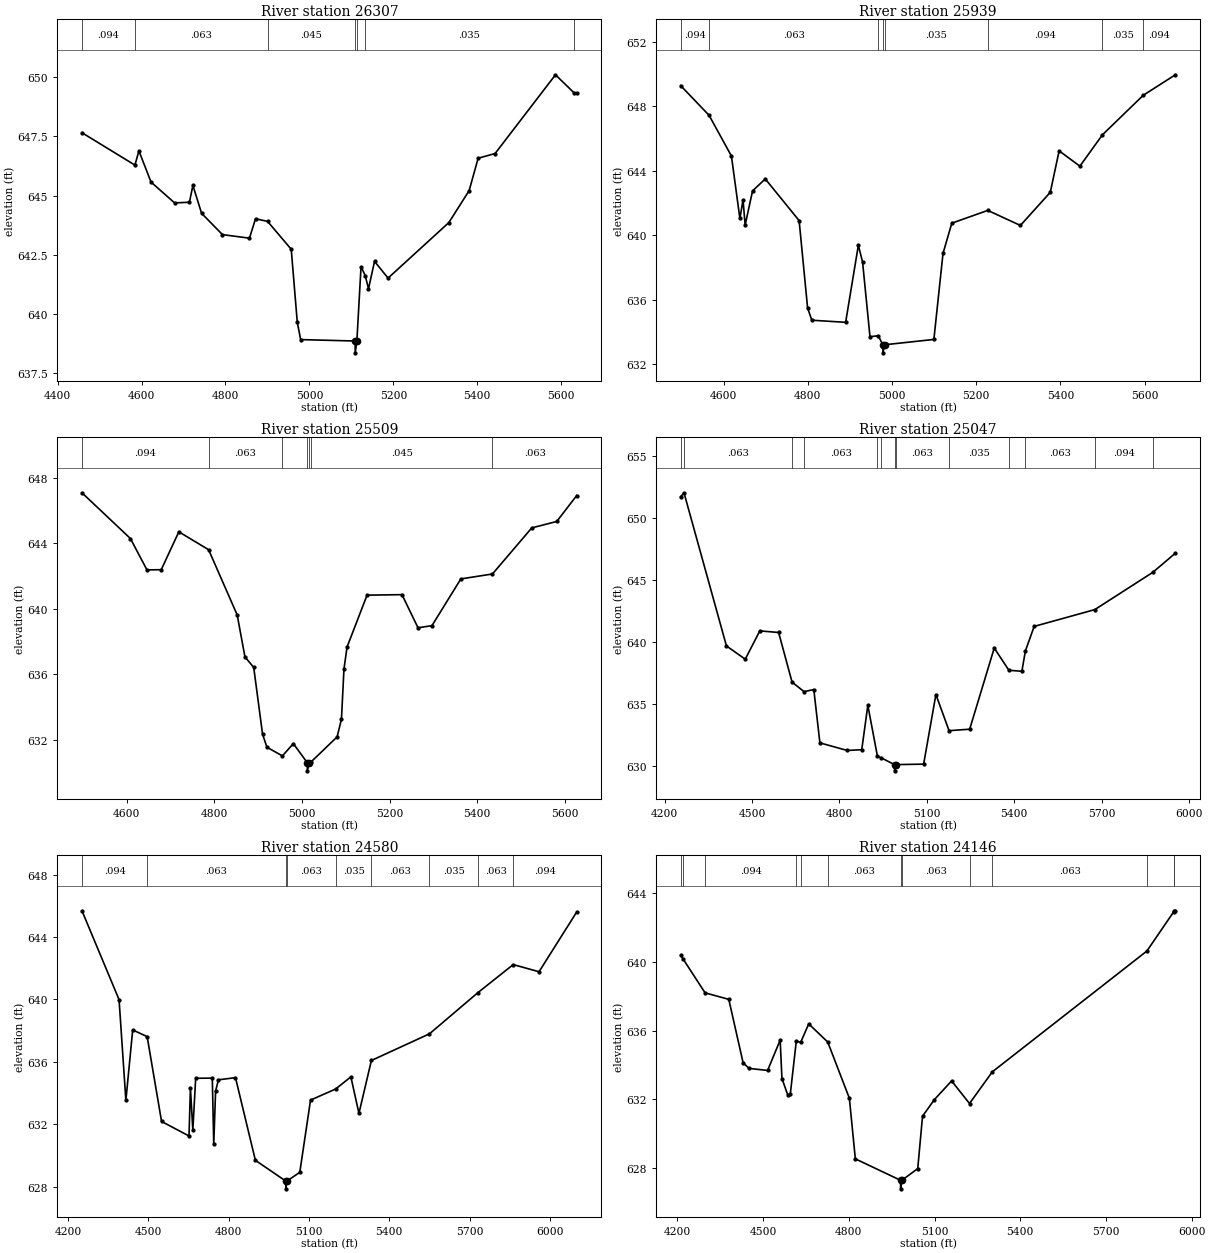
Type RM Length L Ch R = 1 ,26307   ,368,368,368
BEGIN DESCRIPTION:
A19241
END DESCRIPTION:
XS GIS Cut Line= 3
      2251973.37      13789183.7      2252462.96     13788803.48
      2252983.76     13788600.37
#Sta/Elev= 30
    4458  647.66  4584.2  646.29  4593.7  646.89  4622.7  645.57  4678.8  644.69
  4714.1  644.72  4722.3  645.43  4743.1  644.25  4792.8  643.35  4857.1   643.2
  4871.6  644.02  4900.3  643.91  4956.7  642.73  4971.1  639.64  4979.2  638.91
  5108.9  638.85  5109.2  638.35  5113.1  638.85    5123  641.99    5133  641.62
  5140.8  641.06  5155.2  642.22  5187.4  641.51  5332.3  643.86  5380.6  645.21
  5402.1  646.58  5442.5  646.78  5586.4  650.11  5629.8  649.36  5636.9  649.32
#Mann= 7 ,-1 , 0
    4458    .094       0  4584.2    .063       0  4900.3    .045       0
  5108.9    .045       0  5113.1    .045       0    5133    .035       0
  5629.8    .094       0
Bank Sta=5108.9,5113.1
XS Rating Curve= 0 ,0
Exp/Cntr=0.3,0.1

Type RM Length L Ch R = 1 ,25939   ,430,430,430
BEGIN DESCRIPTION:
GUADALUPE TRIBUTARY 22 55.0
END DESCRIPTION:
XS GIS Cut Line= 3
      2252025.03       13789225.        2252525.       13789175.
      2253024.97     13788725.03
#Sta/Elev= 30
  4497.9  649.27  4565.4  647.43  4618.5  644.91  4638.6  641.04  4646.1  642.19
  4651.1  640.63  4668.7  642.75  4698.9  643.49  4779.3  640.91  4799.4  635.51
  4809.4  634.74  4889.8  634.61    4920  639.38    4930  638.35  4947.6  633.72
  4967.3  633.78  4978.1  633.22  4978.4  632.72  4982.4  633.22  5099.4  633.55
  5121.1  638.88    5142  640.75  5227.4  641.54  5304.9  640.61  5375.9  642.66
  5396.9  645.23  5446.2  644.28  5499.7  646.22  5596.7  648.67    5673  649.94
#Mann= 8 ,-1 , 0
  4497.9    .094       0  4565.4    .063       0  4967.3    .035       0
  4978.1    .035       0  4982.4    .035       0  5227.4    .094       0
  5499.7    .035       0  5596.7    .094       0
Bank Sta=4978.1,4982.4
XS Rating Curve= 0 ,0
Exp/Cntr=0.3,0.1

Type RM Length L Ch R = 1 ,25509   ,462,462,462
BEGIN DESCRIPTION:
GUADALUPE TRIBUTARY 22 54.0
END DESCRIPTION:
XS GIS Cut Line= 3
      2252224.97       13789525.        2252725.       13789475.
      2253024.99     13788925.02
#Sta/Elev= 30
  4497.9  647.07  4608.5  644.28  4646.2  642.37  4678.8  642.38    4719  644.69
  4786.9   643.6  4852.2  639.62  4869.8  637.07  4889.9  636.42    4910  632.36
    4920  631.56  4955.3  631.03  4980.3  631.78    5012  630.62  5012.3  630.12
  5016.3  630.62  5019.8  630.64  5080.2  632.19  5090.1  633.27  5095.8  636.32
  5102.9  637.67  5148.5  640.83  5228.2  640.86  5264.8  638.84  5296.6  638.97
  5362.6  641.82  5434.7  642.12  5524.4  644.93  5581.4  645.32  5626.9   646.9
#Mann= 7 ,-1 , 0
  4497.9    .094       0  4786.9    .063       0  4955.3    .035       0
    5012    .035       0  5016.3    .035       0  5019.8    .045       0
  5434.7    .063       0
Bank Sta=5012,5016.3
XS Rating Curve= 0 ,0
Exp/Cntr=0.3,0.1

Type RM Length L Ch R = 1 ,25047   ,467,467,467
BEGIN DESCRIPTION:
GUADALUPE TRIBUTARY 22 53.0
END DESCRIPTION:
XS GIS Cut Line= 3
      2252325.03     13790274.97        2252925.       13789825.
      2253224.99     13788925.04
#Sta/Elev= 30
  4254.6   651.7  4266.1  652.02  4411.8   639.7  4476.4  638.63  4526.4  640.91
    4591  640.78  4637.1  636.79  4678.3  636.02  4711.8  636.19  4732.7   631.9
  4826.4  631.29  4876.4  631.35  4897.3  634.92  4930.1  630.84    4942  630.71
  4988.9  630.15  4989.2  629.65  4993.2  630.15  5088.9  630.19    5131  635.79
  5176.2  632.88    5247     633  5331.3  639.53  5381.6  637.74  5426.2  637.66
  5438.2  639.29  5468.4  641.27  5676.5  642.62  5875.8  645.62  5953.2  647.16
#Mann= 13 ,-1 , 0
  4254.6    .094       0  4266.1    .063       0  4637.1    .094       0
  4678.3    .063       0  4930.1    .094       0    4942    .063       0
  4988.9     .05       0  4993.2    .063       0  5176.2    .035       0
  5381.6    .045       0  5438.2    .063       0  5676.5    .094       0
  5875.8    .063       0
Bank Sta=4988.9,4993.2
XS Rating Curve= 0 ,0
Exp/Cntr=0.3,0.1

Type RM Length L Ch R = 1 ,24580   ,434,434,434
BEGIN DESCRIPTION:
GUADALUPE TRIBUTARY 22 52.0
END DESCRIPTION:
XS GIS Cut Line= 3
      2252525.02     13790374.99        2253225.       13790125.
        2253325.     13789025.02
#Sta/Elev= 30
  4252.3  645.68  4390.9  639.98  4416.3  633.52  4441.8  638.04  4495.8  637.61
  4549.6  632.17  4652.1  631.24  4657.4  634.31  4666.4  631.62    4677  634.94
  4739.1  634.95  4744.5   630.7  4751.4  634.12    4762  634.84  4825.7  634.98
    4900  629.68  5013.4  628.35  5013.7  627.85    5018  628.35  5065.9  628.91
    5106  633.54  5199.7  634.25  5256.7  635.03  5286.8  632.69  5333.3  636.08
  5550.3  637.79  5731.1  640.43  5863.1  642.23  5959.5  641.77  6100.1   645.6
#Mann= 9 ,-1 , 0
  4252.3    .094       0  4495.8    .063       0  5013.4     .05       0
    5018    .063       0  5199.7    .035       0  5333.3    .063       0
  5550.3    .035       0  5731.1    .063       0  5863.1    .094       0
Bank Sta=5013.4,5018
XS Rating Curve= 0 ,0
Exp/Cntr=0.3,0.1

Type RM Length L Ch R = 1 ,24146   ,535,535,535
BEGIN DESCRIPTION:
GUADALUPE TRIBUTARY 22 51.0
END DESCRIPTION:
XS GIS Cut Line= 3
      2253014.01     13790709.72      2253566.08     13790303.48
        2253375.     13789275.01
#Sta/Elev= 30
  4211.5  640.39  4219.9  640.18    4297   638.2    4380  637.82  4430.2  634.11
    4451  633.79  4515.8  633.67  4559.8  635.44    4566   633.2  4586.8  632.22
  4595.3  632.29  4616.3  635.39  4631.7  635.31  4659.7  636.39  4726.3  635.33
    4802  632.05  4822.9  628.51  4981.1  627.26  4981.5  626.76  4985.7  627.26
  5041.3  627.94  5058.1     631  5099.2  631.96  5159.8  633.06  5222.5  631.74
  5302.4  633.59  5843.3  640.64  5937.6  642.94  5939.9  642.98    5943  642.99
#Mann= 13 ,-1 , 0
  4211.5    .094       0  4219.9    .063       0    4297    .094       0
  4616.3    .035       0  4631.7    .094       0  4726.3    .063       0
  4981.1     .05       0  4985.7    .063       0  5222.5    .094       0
  5302.4    .063       0  5843.3    .035       0  5937.6    .063       0
  5939.9    .094       0
Bank Sta=4981.1,4985.7
XS Rating Curve= 0 ,0
Exp/Cntr=0.3,0.1

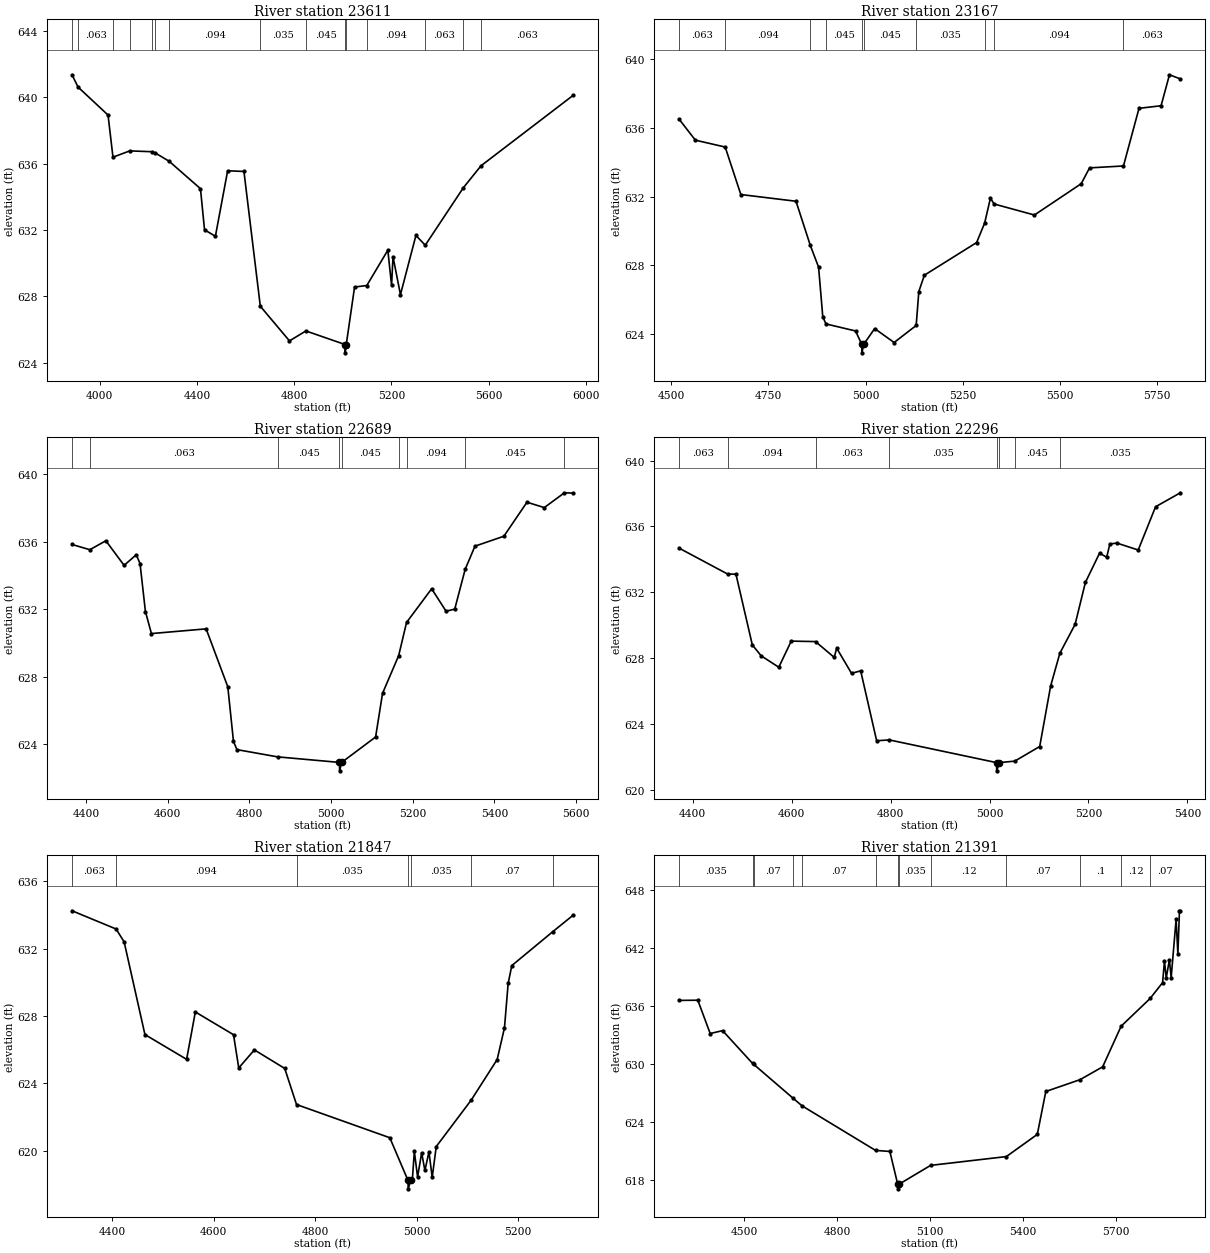
Type RM Length L Ch R = 1 ,23611   ,444,444,444
BEGIN DESCRIPTION:
GUADALUPE TRIBUTARY 22 50.0
END DESCRIPTION:
XS GIS Cut Line= 3
      2253575.01     13791174.98        2254075.       13790175.
      2253575.01     13789375.01
#Sta/Elev= 30
  3886.3  641.36    3911  640.62  4034.4  638.93  4054.7  636.39  4123.8  636.77
  4214.4  636.72    4228  636.65  4286.1  636.14  4414.6  634.49  4431.3  632.01
    4476  631.62  4526.4  635.57  4593.4  635.53  4660.8   627.4  4780.7  625.31
  4848.3  625.91  5009.7  625.09    5010  624.59  5014.3  625.09  5048.5  628.56
  5098.8  628.65  5185.3  630.78  5200.7  628.66  5206.6  630.39  5237.2   628.1
  5300.9  631.67  5339.2  631.08  5495.6  634.54  5568.5  635.87  5947.7  640.12
#Mann= 15 ,-1 , 0
  3886.3    .094       0    3911    .063       0  4054.7    .094       0
  4123.8    .063       0  4214.4    .094       0    4228    .063       0
  4286.1    .094       0  4660.8    .035       0  4848.3    .045       0
  5009.7    .045       0  5014.3    .045       0  5098.8    .094       0
  5339.2    .063       0  5495.6    .094       0  5568.5    .063       0
Bank Sta=5009.7,5014.3
XS Rating Curve= 0 ,0
Exp/Cntr=0.3,0.1

Type RM Length L Ch R = 1 ,23167   ,478,478,478
BEGIN DESCRIPTION:
GUADALUPE TRIBUTARY 22 49.0
END DESCRIPTION:
XS GIS Cut Line= 3
      2254524.41     13790475.35        2254375.       13790025.
      2253825.02     13789425.02
#Sta/Elev= 30
  4520.9  636.49  4562.4  635.28  4639.1  634.88  4679.3  632.12  4821.1  631.73
    4858  629.16  4879.2   627.9    4890  625.01  4898.2   624.6  4974.3  624.19
  4990.1  623.42  4990.5  622.92  4995.4  623.42  5023.4  624.33  5073.4  623.52
  5130.1  624.51  5136.9  626.48  5151.1  627.43  5285.5  629.33  5306.1  630.46
    5321  631.91  5330.4  631.57  5434.1  630.93  5554.4  632.75  5575.9  633.67
    5663  633.78    5703  637.13  5759.7  637.28  5781.3  639.08  5809.3  638.84
#Mann= 10 ,-1 , 0
  4520.9    .063       0  4639.1    .094       0    4858    .063       0
  4898.2    .045       0  4990.1    .045       0  4995.4    .045       0
  5130.1    .035       0  5306.1    .063       0  5330.4    .094       0
    5663    .063       0
Bank Sta=4990.1,4995.4
XS Rating Curve= 0 ,0
Exp/Cntr=0.3,0.1

Type RM Length L Ch R = 1 ,22689   ,393,393,393
BEGIN DESCRIPTION:
A19240
END DESCRIPTION:
XS GIS Cut Line= 3
      2254826.51     13790225.39      2254493.17      13789563.9
      2254149.68     13789220.41
#Sta/Elev= 30
  4366.1  635.84  4409.6  635.53  4448.9  636.06  4493.5   634.6  4523.3  635.23
  4532.5  634.71  4545.7  631.86  4560.4  630.55  4694.3  630.83  4747.3  627.39
  4761.2  624.15  4769.7  623.66  4869.1  623.23  5020.6   622.9    5021   622.4
  5025.9   622.9  5109.1  624.41    5126     627  5165.5  629.24  5184.8  631.21
  5246.2  633.21  5281.5  631.88  5302.7     632  5328.2  634.36  5352.2  635.74
    5423  636.33  5479.5  638.35  5521.9  638.03  5571.2  638.91  5592.6  638.89
#Mann= 9 ,-1 , 0
  4366.1    .094       0  4409.6    .063       0  4869.1    .045       0
  5020.6    .045       0  5025.9    .045       0  5165.5    .063       0
  5184.8    .094       0  5328.2    .045       0  5571.2    .035       0
Bank Sta=5020.6,5025.9
XS Rating Curve= 0 ,0
Exp/Cntr=0.3,0.1

Type RM Length L Ch R = 1 ,22296   ,449,449,449
BEGIN DESCRIPTION:
GUADALUPE TRIBUTARY 22 48.0
END DESCRIPTION:
XS GIS Cut Line= 3
      2254935.88     13790037.87        2254825.       13789425.
      2254575.02     13789125.02
#Sta/Elev= 30
  4372.6  634.68  4470.3  633.11  4487.3   633.1  4520.4   628.8  4538.1  628.14
  4573.9  627.44  4599.1  629.03  4648.2     629    4686  628.04    4691   628.6
    4721  627.07  4739.5  627.22  4771.8  622.97  4797.5  623.02  5014.2  621.64
  5014.6  621.14  5019.6  621.64    5051  621.73  5101.5  622.62  5123.6   626.3
  5142.2  628.29  5173.1  630.05  5193.9   632.6  5222.6  634.38  5236.9  634.13
  5243.4  634.94  5257.7  634.99  5300.7  634.57  5335.8   637.2  5385.9  638.05
#Mann= 8 ,-1 , 0
  4372.6    .063       0  4470.3    .094       0  4648.2    .063       0
  4797.5    .035       0  5014.2    .035       0  5019.6    .035       0
    5051    .045       0  5142.2    .035       0
Bank Sta=5014.2,5019.6
XS Rating Curve= 0 ,0
Exp/Cntr=0.3,0.1

Type RM Length L Ch R = 1 ,21847   ,456,456,456
BEGIN DESCRIPTION:
GUADALUPE TRIBUTARY 22 47.0
END DESCRIPTION:
XS GIS Cut Line= 3
      2254975.01     13789974.97        2255125.       13789325.
        2254925.       13789075.
#Sta/Elev= 30
  4321.1  634.24  4407.8  633.16  4423.7   632.4  4464.7   626.9  4546.8  625.43
    4564  628.24  4639.2  626.89  4649.5  624.92  4680.3  625.99  4740.1  624.89
  4763.3  622.75  4947.1  620.78  4982.9  618.25  4983.3  617.75  4988.3  618.25
  4991.4  618.25  4995.4  619.97  5001.8  618.45  5009.8  619.89  5016.2  618.84
  5024.2  619.94  5030.6  618.43  5038.6  620.26  5107.6  623.02  5158.6  625.42
    5173  627.31  5180.2  629.93  5187.4  630.99  5267.7  632.99  5308.3  633.98
#Mann= 7 ,-1 , 0
  4321.1    .063       0  4407.8    .094       0  4763.3    .035       0
  4982.9    .035       0  4988.3    .035       0  5107.6     .07       0
  5267.7      .1       0
Bank Sta=4982.9,4988.3
XS Rating Curve= 0 ,0
Exp/Cntr=0.3,0.1

Type RM Length L Ch R = 1 ,21391   ,445,445,445
BEGIN DESCRIPTION:
GUADALUPE TRIBUTARY 22 46.0
END DESCRIPTION:
XS GIS Cut Line= 3
        2255525.       13790175.        2255525.       13789475.
      2255074.99     13788674.98
#Sta/Elev= 30
  4290.7  636.62  4350.7  636.64  4390.7  633.19  4430.7  633.49  4527.4   630.1
  4530.8  630.01  4656.5  626.54    4687  625.71  4924.5  621.09  4970.7  620.98
  4995.9  617.61  4996.4  617.11  5001.4  617.61  5102.4  619.54  5346.8  620.45
  5446.8  622.75  5474.2  627.19  5584.4  628.41  5657.7  629.74  5717.4  633.95
    5811  636.82  5851.2  638.46  5857.3  640.68    5863  638.94  5873.2  640.83
  5878.9  638.97  5894.9  645.02  5900.6  641.42  5905.7   645.9  5908.6   645.9
#Mann= 13 ,-1 , 0
  4290.7    .035       0  4527.4    .063       0  4530.8     .07       0
  4656.5    .035       0    4687     .07       0  4924.5    .035       0
  4995.9    .035       0  5001.4    .035       0  5102.4     .12       0
  5346.8     .07       0  5584.4      .1       0  5717.4     .12       0
    5811     .07       0
Bank Sta=4995.9,5001.4
XS Rating Curve= 0 ,0
Exp/Cntr=0.3,0.1

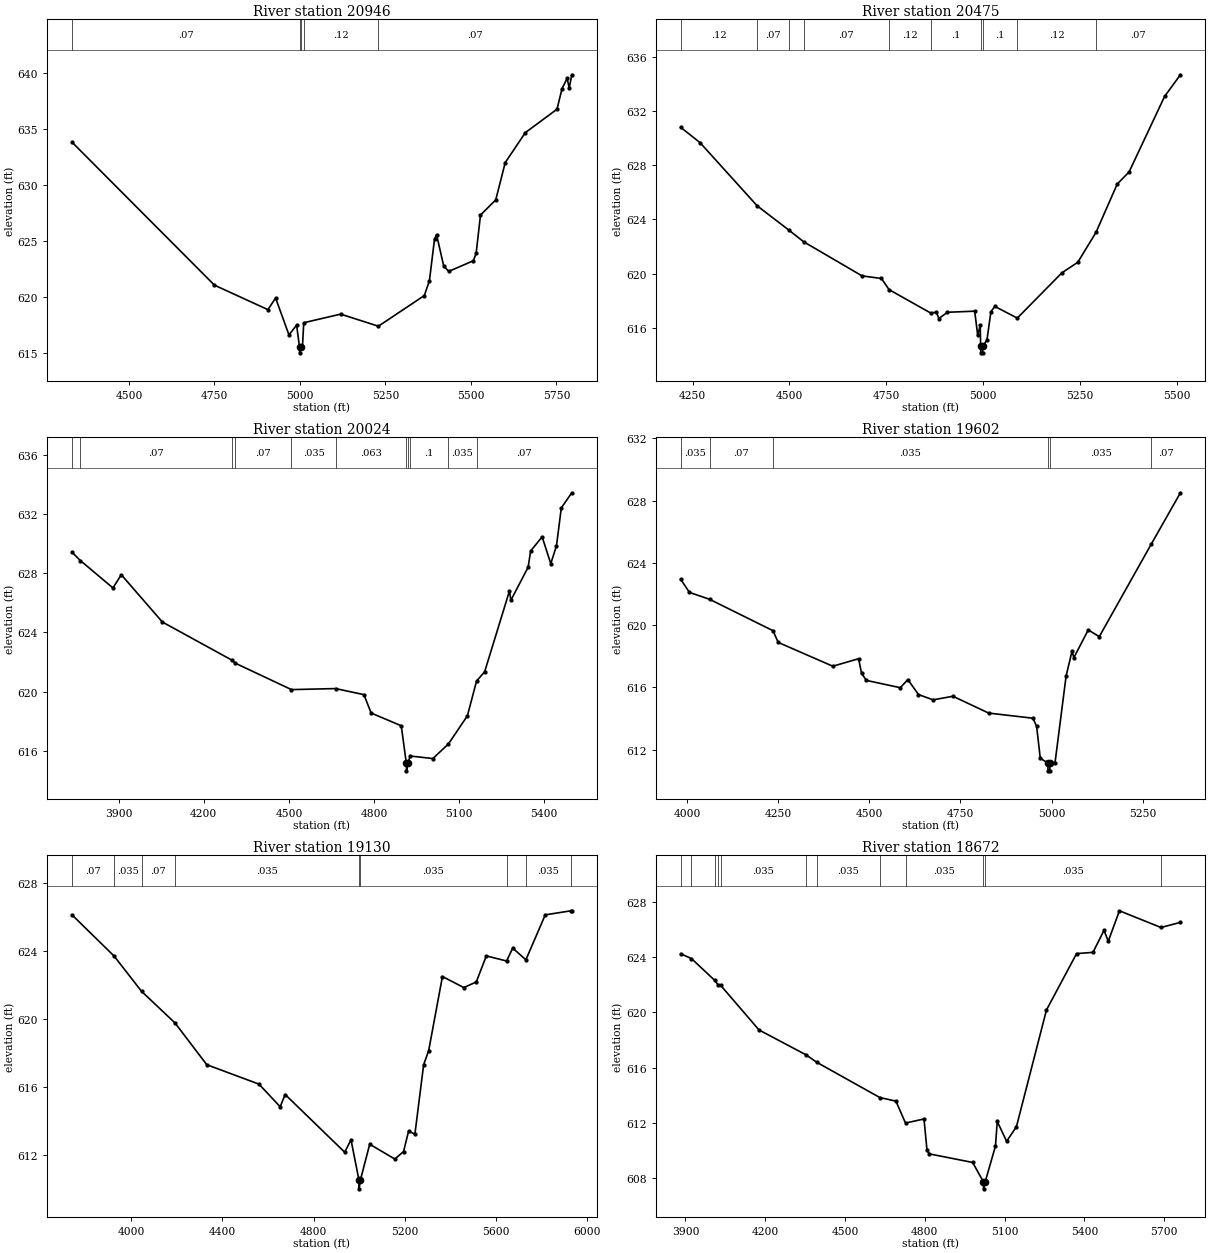
Type RM Length L Ch R = 1 ,20946   ,471,471,471
BEGIN DESCRIPTION:
GUADALUPE TRIBUTARY 22 45.0
END DESCRIPTION:
XS GIS Cut Line= 3
      2256375.03     13789425.01        2255775.       13789125.
      2255125.02     13788675.01
#Sta/Elev= 30
  4333.5  633.85    4750  621.07  4906.5  618.88  4928.9  619.92    4968  616.62
  4990.4   617.5  4998.8  615.52  4999.2  615.02  5004.4  615.52  5007.4  615.52
  5011.2  617.71  5119.2  618.48  5229.5   617.4  5363.8  620.14  5378.7  621.47
  5393.6  625.19  5399.6  625.58  5420.6  622.76  5435.4   622.3  5507.1  623.25
  5515.2   623.9    5528  627.33  5572.6  628.69  5600.3  632.02  5659.1   634.7
  5751.7  636.79  5766.5  638.64  5781.4  639.55  5787.5  638.68  5794.9  639.87
#Mann= 5 ,-1 , 0
  4333.5     .07       0  4998.8     .05       0  5004.4     .07       0
  5011.2     .12       0  5229.5     .07       0
Bank Sta=4998.8,5004.4
XS Rating Curve= 0 ,0
Exp/Cntr=0.3,0.1

Type RM Length L Ch R = 1 ,20475   ,451,451,451
BEGIN DESCRIPTION:
GUADALUPE TRIBUTARY 22 44.0
END DESCRIPTION:
XS GIS Cut Line= 3
      2256374.97     13789224.97        2255775.       13788725.
      2255274.99       13788625.
#Sta/Elev= 30
    4219  630.79  4269.1  629.66  4416.8     625  4498.8  623.21  4536.5  622.36
  4687.6  619.84  4737.7  619.65  4757.3  618.83  4864.5  617.11  4879.6  617.16
  4886.1   616.7  4908.2  617.16  4978.5  617.24  4986.3  615.47  4992.8   616.2
  4993.9  614.67  4994.3  614.17  4999.1  614.17  4999.6  614.67  5010.2  615.12
  5020.4   617.2  5030.6  617.59  5088.6  616.73  5203.9  620.07  5244.7  620.84
  5291.9  623.05  5346.7  626.61  5377.3   627.5  5469.1  633.07  5509.9  634.66
#Mann= 10 ,-1 , 0
    4219     .12       0  4416.8     .07       0  4498.8     .12       0
  4536.5     .07       0  4757.3     .12       0  4864.5      .1       0
  4993.9     .05       0  4999.6      .1       0  5088.6     .12       0
  5291.9     .07       0
Bank Sta=4993.9,4999.6
XS Rating Curve= 0 ,0
Exp/Cntr=0.3,0.1

Type RM Length L Ch R = 1 ,20024   ,422,422,422
BEGIN DESCRIPTION:
A19239
END DESCRIPTION:
XS GIS Cut Line= 3
      2256447.91     13789159.84      2255997.21      13788386.2
      2255141.87     13788244.23
#Sta/Elev= 30
  3735.1  629.41  3764.5  628.85  3879.6     627  3909.1  627.89  4053.9   624.7
  4299.8  622.12  4311.3  621.92  4509.1  620.14    4665  620.21  4764.5   619.8
  4790.1  618.56  4896.3   617.7  4914.2  615.16  4914.7  614.66  4919.9  615.16
  4927.4  615.66  5007.8  615.49  5062.4  616.47  5129.4  618.37  5161.8  620.72
  5190.2  621.34  5277.7  626.79  5282.8  626.17  5343.7   628.4  5352.4  629.49
    5393  630.45  5423.4  628.64  5443.6  629.84  5460.6   632.4  5497.5  633.42
#Mann= 11 ,-1 , 0
  3735.1    .035       0  3764.5     .07       0  4299.8    .035       0
  4311.3     .07       0  4509.1    .035       0    4665    .063       0
  4914.2     .05       0  4919.9    .063       0  4927.4      .1       0
  5062.4    .035       0  5161.8     .07       0
Bank Sta=4914.2,4919.9
XS Rating Curve= 0 ,0
Exp/Cntr=0.3,0.1

Type RM Length L Ch R = 1 ,19602   ,472,472,472
BEGIN DESCRIPTION:
GUADALUPE TRIBUTARY 22 43.0
END DESCRIPTION:
XS GIS Cut Line= 3
      2256313.06     13788581.38      2255894.29     13788027.75
        2255225.       13787925.
#Sta/Elev= 30
  3982.3  622.95  4006.5   622.1  4061.6  621.66  4235.8  619.64    4250  618.89
  4399.8  617.36  4470.6  617.84  4478.8   616.9  4491.8  616.45    4585  615.98
  4605.8   616.5  4634.9  615.54  4675.1   615.2  4729.5  615.43  4827.5  614.35
  4948.9  614.02    4959   613.5  4969.1  611.45  4989.9  611.14  4990.4  610.64
  4995.2  610.64  4995.7  611.14  5009.6  611.17    5040  616.74  5056.1  618.32
  5061.2  617.91  5100.7  619.69    5131  619.26  5273.5   625.2  5353.6   628.5
#Mann= 6 ,-1 , 0
  3982.3    .035       0  4061.6     .07       0  4235.8    .035       0
  4989.9    .035       0  4995.7    .035       0  5273.5     .07       0
Bank Sta=4989.9,4995.7
XS Rating Curve= 0 ,0
Exp/Cntr=0.3,0.1

Type RM Length L Ch R = 1 ,19130   ,458,458,458
BEGIN DESCRIPTION:
GUADALUPE TRIBUTARY 22 42.0
END DESCRIPTION:
XS GIS Cut Line= 3
      2256474.98     13788774.97        2255875.       13787675.
      2255046.08     13787236.33
#Sta/Elev= 30
  3740.8  626.12  3924.9  623.71  4045.8  621.63  4192.6  619.77  4331.7  617.32
  4560.4  616.18  4653.5  614.85  4675.3  615.57  4936.3  612.18  4963.9  612.91
    4999  610.53  4999.5  610.03  5004.8  610.53  5045.9  612.65    5156  611.78
  5194.3  612.22  5216.3  613.42    5244  613.24  5282.3  617.32  5304.3  618.14
  5364.7   622.5  5458.4  621.85    5513  622.18  5557.1  623.71    5646  623.41
  5672.7  624.17  5730.4  623.48  5815.4  626.12  5928.3  626.36  5931.6  626.34
#Mann= 9 ,-1 , 0
  3740.8     .07       0  3924.9    .035       0  4045.8     .07       0
  4192.6    .035       0    4999    .035       0  5004.8    .035       0
    5646     .07       0  5730.4    .035       0  5928.3     .07       0
Bank Sta=4999,5004.8
XS Rating Curve= 0 ,0
Exp/Cntr=0.3,0.1

Type RM Length L Ch R = 1 ,18672   ,468,468,468
BEGIN DESCRIPTION:
GUADALUPE TRIBUTARY 22 41.0
END DESCRIPTION:
XS GIS Cut Line= 3
      2256475.01     13788625.03        2256275.       13787525.
      2256096.57     13786785.59
#Sta/Elev= 30
  3881.9  624.25  3922.6   623.9  4010.2  622.32  4022.6     622  4032.5  621.96
  4176.7  618.73  4353.4  616.93  4393.7  616.39  4630.6  613.84  4691.2  613.58
  4727.2  611.99  4796.7  612.29  4808.1  610.01    4817  609.76  4979.6  609.14
  5020.2  607.73  5020.7  607.23  5026.7  607.73  5065.4  610.33    5072  612.11
  5107.3  610.67    5144  611.72  5257.1  620.18  5370.3  624.26    5432  624.35
  5473.2  625.94  5489.4  625.16  5531.3  627.36  5687.5  626.15  5760.6  626.52
#Mann= 12 ,-1 , 0
  3881.9    .035       0  3922.6     .07       0  4010.2    .035       0
  4022.6     .07       0  4032.5    .035       0  4353.4    .063       0
  4393.7    .035       0  4630.6    .063       0  4727.2    .035       0
  5020.2    .035       0  5026.7    .035       0  5687.5     .05       0
Bank Sta=5020.2,5026.7
XS Rating Curve= 0 ,0
Exp/Cntr=0.3,0.1

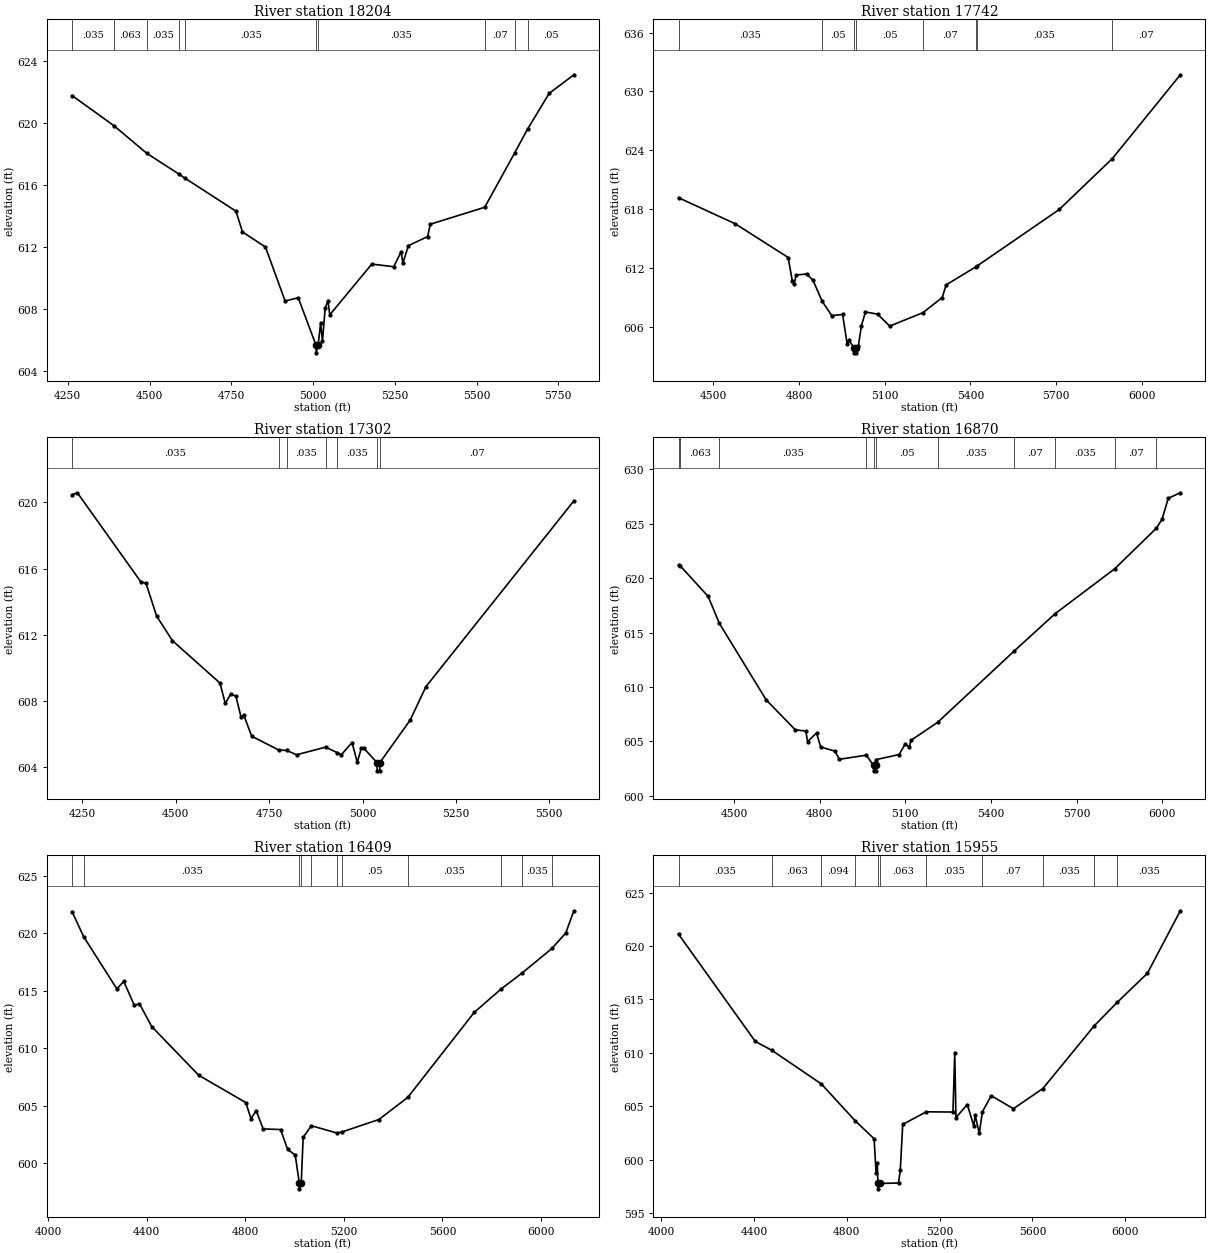
Type RM Length L Ch R = 1 ,18204   ,462,462,462
BEGIN DESCRIPTION:
GUADALUPE TRIBUTARY 22 40.0
END DESCRIPTION:
XS GIS Cut Line= 3
        2256625.     13788424.97        2256675.       13787675.
      2256324.98     13786974.97
#Sta/Elev= 30
  4263.1  621.76  4390.4  619.83  4492.1  618.03  4590.6  616.69  4609.4  616.42
  4764.2  614.31  4784.2  612.97  4854.4     612  4914.5  608.52  4954.6  608.73
  5008.9  605.68  5009.4  605.18  5015.5  605.68  5023.1  607.09  5028.7  605.93
  5037.1  608.08  5045.5  608.53  5051.1  607.63  5179.6   610.9  5246.7  610.73
  5269.1  611.69  5274.7  610.97  5291.5  612.09  5350.1  612.67  5358.5  613.47
  5524.8  614.56  5616.8  618.08  5655.9   619.6  5721.9   621.9  5797.4   623.1
#Mann= 10 ,-1 , 0
  4263.1    .035       0  4390.4    .063       0  4492.1    .035       0
  4590.6    .063       0  4609.4    .035       0  5008.9    .035       0
  5015.5    .035       0  5524.8     .07       0  5616.8    .035       0
  5655.9     .05       0
Bank Sta=5008.9,5015.5
XS Rating Curve= 0 ,0
Exp/Cntr=0.3,0.1

Type RM Length L Ch R = 1 ,17742   ,440,440,440
BEGIN DESCRIPTION:
GUADALUPE TRIBUTARY 22 39.0
END DESCRIPTION:
XS GIS Cut Line= 3
      2256774.98     13788275.04        2257075.       13787725.
      2257874.99     13786925.01
#Sta/Elev= 30
  4377.6  619.15  4576.5  616.49  4761.6  613.05  4776.3  610.64  4783.4  610.36
  4789.1  611.26  4827.1  611.37  4848.9  610.71  4880.7  608.59  4914.4  607.12
  4952.4  607.24  4968.5  604.19  4974.2  604.62  4992.4  603.82  4992.9  603.32
  4999.3  603.32  4999.8  603.82  5007.7  604.04  5018.3   606.1  5032.4  607.49
  5074.9  607.27  5117.3  606.05  5233.9  607.42  5301.1  608.96  5315.3  610.26
  5419.9  612.11  5421.8  612.15  5711.3  617.95  5897.4  623.15  6135.5   631.7
#Mann= 8 ,-1 , 0
  4377.6    .035       0  4880.7     .05       0  4992.4     .05       0
  4999.8     .05       0  5233.9     .07       0  5419.9     .05       0
  5421.8    .035       0  5897.4     .07       0
Bank Sta=4992.4,4999.8
XS Rating Curve= 0 ,0
Exp/Cntr=0.3,0.1

Type RM Length L Ch R = 1 ,17302   ,432,432,432
BEGIN DESCRIPTION:
GUADALUPE TRIBUTARY 22 38.0
END DESCRIPTION:
XS GIS Cut Line= 3
      2256874.98     13788425.02        2257425.       13787875.
      2257824.97     13787475.03
#Sta/Elev= 30
  4222.1  620.46  4236.3  620.58    4406  615.21  4420.1  615.11  4448.4  613.14
  4490.8  611.65  4618.1  609.09  4632.3  607.86  4646.4  608.41  4660.5  608.31
  4674.7  607.02  4681.8  607.16    4703  605.88  4775.1  605.05  4796.7  605.02
  4823.2  604.76  4900.9  605.22  4931.9  604.89  4943.4  604.77  4971.7   605.5
  4985.8   604.3  4996.4  605.15  5003.5  605.15  5038.5  604.29    5039  603.79
  5045.8  603.79  5046.3  604.29  5127.2  606.85  5169.7  608.88  5565.6  620.09
#Mann= 7 ,-1 , 0
  4222.1    .035       0  4775.1     .05       0  4796.7    .035       0
  4900.9     .05       0  4931.9    .035       0  5038.5    .035       0
  5046.3     .07       0
Bank Sta=5038.5,5046.3
XS Rating Curve= 0 ,0
Exp/Cntr=0.3,0.1

Type RM Length L Ch R = 1 ,16870   ,461,461,461
BEGIN DESCRIPTION:
GUADALUPE TRIBUTARY 22 37.0
END DESCRIPTION:
XS GIS Cut Line= 3
      2256975.01     13788574.99        2257575.       13788225.
      2258274.98     13787425.02
#Sta/Elev= 30
  4305.5  621.22  4311.1  621.14  4409.3  618.32  4448.2  615.86  4612.7  608.81
  4714.4  606.07  4751.6  605.95  4757.4  604.98  4788.8  605.78  4803.3  604.49
  4853.3  604.11    4869  603.36  4963.3  603.74  4988.4   602.8  4988.9   602.3
  4995.7   602.3  4996.2   602.8  4997.2  603.33  5078.4   603.8  5099.3  604.77
  5113.5  604.49  5120.2  605.11  5212.8  606.75  5481.4  613.31  5625.3  616.75
  5833.4  620.86  5979.3  624.59  5999.1  625.41  6020.9  627.34  6063.1  627.84
#Mann= 11 ,-1 , 0
  4305.5    .035       0  4311.1    .063       0  4448.2    .035       0
  4963.3     .05       0  4988.4     .05       0  4996.2     .05       0
  5212.8    .035       0  5481.4     .07       0  5625.3    .035       0
  5833.4     .07       0  5979.3    .035       0
Bank Sta=4988.4,4996.2
XS Rating Curve= 0 ,0
Exp/Cntr=0.3,0.1

Type RM Length L Ch R = 1 ,16409   ,454,454,454
BEGIN DESCRIPTION:
GUADALUPE TRIBUTARY 22 36.0
END DESCRIPTION:
XS GIS Cut Line= 3
      2257186.09     13789213.11        2257825.       13788575.
      2258406.92     13787601.91
#Sta/Elev= 30
  4096.8  621.88  4144.3  619.69  4278.5  615.17  4306.8  615.81  4349.3  613.74
  4370.5  613.87    4420  611.89  4610.9  607.65  4801.8  605.28    4823  603.88
  4844.2  604.57  4872.5  602.98  4943.2  602.93  4971.5  601.21  5002.7   600.7
  5019.1  598.27  5019.6  597.77    5027  598.27  5034.8  602.25  5068.1  603.26
  5171.2  602.63  5191.1  602.71  5342.1   603.8  5459.2  605.72  5729.2  613.12
  5837.4  615.14  5924.9  616.57  6044.5  618.68  6100.8  620.03  6133.6  621.96
#Mann= 11 ,-1 , 0
  4096.8     .07       0  4144.3    .035       0  5019.1    .035       0
    5027    .035       0  5068.1     .05       0  5171.2    .035       0
  5191.1     .05       0  5459.2    .035       0  5837.4     .07       0
  5924.9    .035       0  6044.5     .07       0
Bank Sta=5019.1,5027
XS Rating Curve= 0 ,0
Exp/Cntr=0.3,0.1

Type RM Length L Ch R = 1 ,15955   ,474,474,474
BEGIN DESCRIPTION:
GUADALUPE TRIBUTARY 22 35.0
END DESCRIPTION:
XS GIS Cut Line= 3
      2257977.53     13789677.98        2258175.       13788775.
      2258475.01     13787574.96
#Sta/Elev= 30
  4075.7  621.11  4406.3  611.07  4478.2  610.23  4690.9  607.09  4837.8  603.61
  4918.1  601.96  4926.5  598.77  4931.6  599.72  4934.5  597.77    4935  597.27
  4942.7  597.77  5023.2  597.82  5030.9  599.04  5041.3   603.3  5142.4  604.48
  5257.7  604.46  5265.4  610.03  5270.6  603.94  5319.6  605.16  5347.9  603.13
  5353.1  604.19  5371.1  602.46  5384.4  604.48  5422.6  605.99    5518  604.77
    5645  606.66  5866.9  612.55  5965.4  614.73  6095.2  617.45    6237   623.3
#Mann= 11 ,-1 , 0
  4075.7    .035       0  4478.2    .063       0  4690.9    .094       0
  4837.8    .063       0  4934.5     .05       0  4942.7    .063       0
  5142.4    .035       0  5384.4     .07       0    5645    .035       0
  5866.9     .07       0  5965.4    .035       0
Bank Sta=4934.5,4942.7
XS Rating Curve= 0 ,0
Exp/Cntr=0.3,0.1

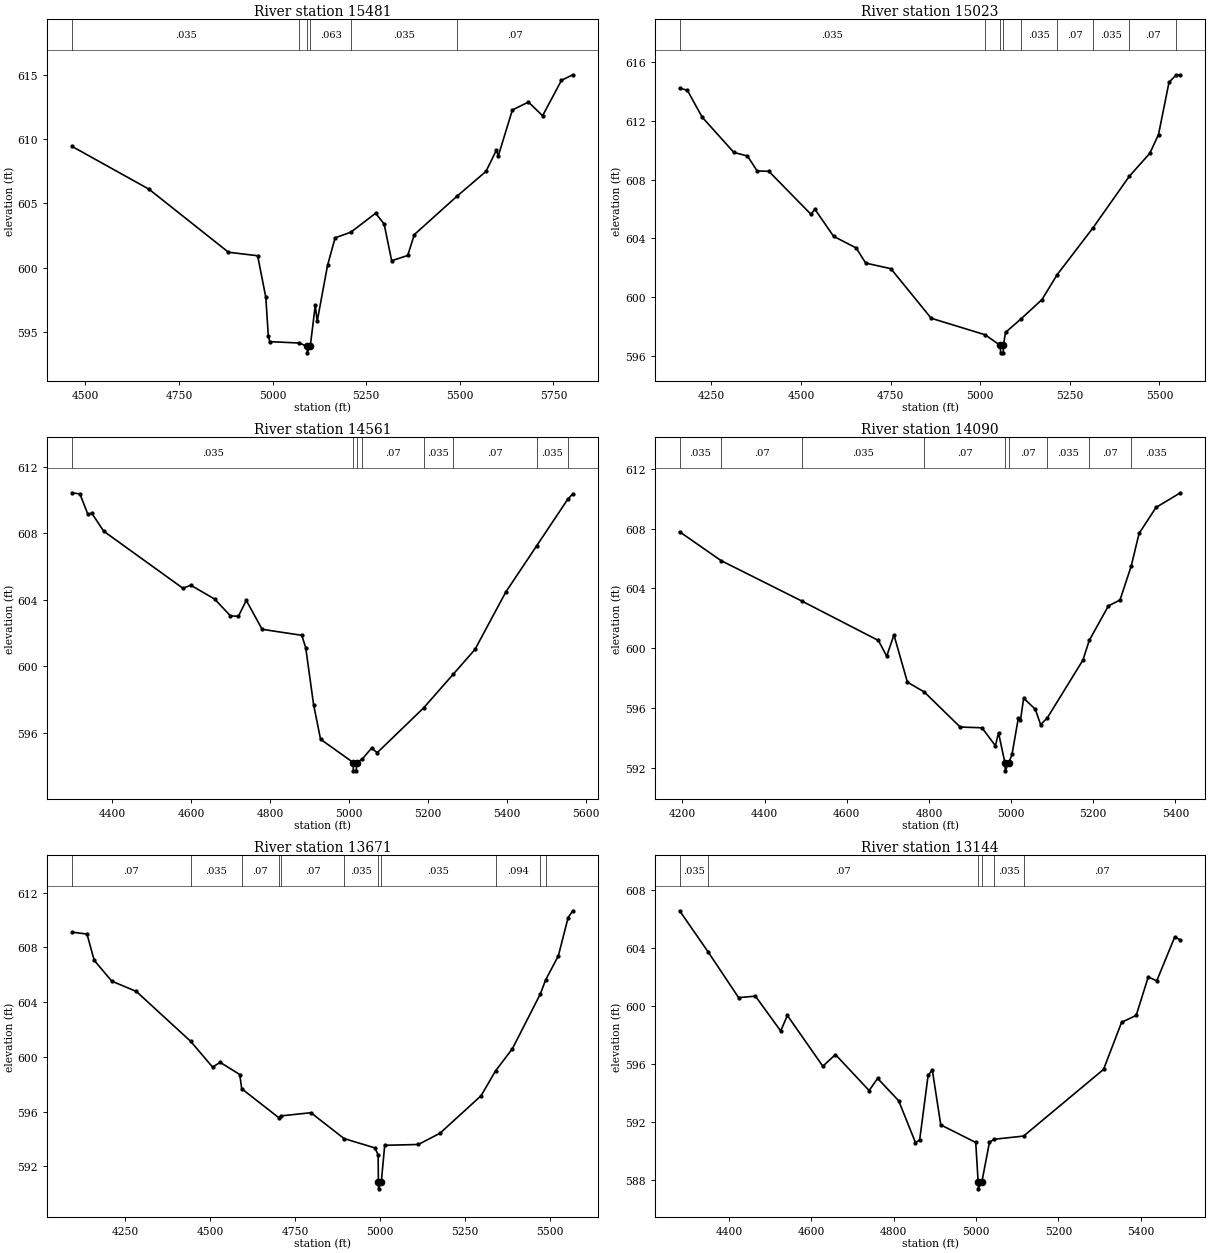
Type RM Length L Ch R = 1 ,15481   ,458,458,458
BEGIN DESCRIPTION:
GUADALUPE TRIBUTARY 22 34.0
END DESCRIPTION:
XS GIS Cut Line= 3
      2258924.97     13789024.96        2258575.       13788625.
        2258675.     13787824.98
#Sta/Elev= 30
  4464.1  609.42  4669.5   606.1  4882.1   601.2    4960  600.93  4981.8   597.7
  4988.4  594.73  4992.2  594.26  5071.6  594.15  5092.2  593.89  5092.7  593.39
  5100.5  593.89    5114  597.09    5119  595.83  5146.7  600.18  5166.9  602.32
  5209.1  602.76  5275.2  604.23  5297.9  603.39    5318  600.54  5360.9  600.95
  5378.5  602.57  5492.1  605.54    5570  607.48  5597.7  609.12  5602.7  608.67
  5640.5  612.25  5683.4  612.86  5721.2   611.8  5771.6  614.55  5801.8  614.98
#Mann= 6 ,-1 , 0
  4464.1    .035       0  5071.6    .063       0  5092.2    .035       0
  5100.5    .063       0  5209.1    .035       0  5492.1     .07       0
Bank Sta=5092.2,5100.5
XS Rating Curve= 0 ,0
Exp/Cntr=0.3,0.1

Type RM Length L Ch R = 1 ,15023   ,462,462,462
BEGIN DESCRIPTION:
GUADALUPE TRIBUTARY 22 33.0
END DESCRIPTION:
XS GIS Cut Line= 3
      2259125.01     13789175.05        2258875.       13788375.
        2258775.     13787825.02
#Sta/Elev= 30
  4161.2  614.21  4182.7  614.07  4224.1  612.24  4312.6  609.84  4350.4   609.6
  4377.6  608.58  4410.1  608.56  4527.9  605.63  4538.4  605.99  4590.8  604.14
  4653.7  603.35  4680.4  602.32  4750.6  601.94  4863.2  598.57  5013.3  597.45
  5056.2  596.72  5056.7  596.22    5064  596.22  5064.5  596.72  5070.5  597.61
  5113.9  598.53  5172.2  599.84  5214.5  601.53    5315  604.73  5415.6  608.21
  5473.3  609.79  5497.4  611.06  5526.7  614.61    5546  615.09  5558.4  615.12
#Mann= 9 ,-1 , 0
  4161.2    .035       0  5013.3     .07       0  5056.2    .035       0
  5064.5     .07       0  5113.9    .035       0  5214.5     .07       0
    5315    .035       0  5415.6     .07       0    5546    .035       0
Bank Sta=5056.2,5064.5
XS Rating Curve= 0 ,0
Exp/Cntr=0.3,0.1

Type RM Length L Ch R = 1 ,14561   ,471,471,471
BEGIN DESCRIPTION:
GUADALUPE TRIBUTARY 22 32.0
END DESCRIPTION:
XS GIS Cut Line= 3
        2259275.     13788974.99        2259225.       13788275.
      2258824.97     13787874.97
#Sta/Elev= 30
  4298.2  610.43  4318.2  610.36  4338.3  609.14  4348.3   609.2  4378.4  608.12
  4578.9  604.69  4598.9  604.87  4659.1  604.04  4699.2  603.03  4719.3     603
  4739.3  603.96  4779.4  602.22  4879.7  601.86  4889.7  601.12  4909.7  597.69
  4927.3  595.61  5009.9  594.21  5010.4  593.71  5017.8  593.71  5018.3  594.21
  5032.2   594.4  5056.5  595.08  5070.7   594.8  5188.4   597.5  5262.8  599.51
  5318.2  601.01  5395.9  604.45  5474.3  607.24  5552.7  610.03  5565.7  610.37
#Mann= 8 ,-1 , 0
  4298.2    .035       0  5009.9    .035       0  5018.3    .035       0
  5032.2     .07       0  5188.4    .035       0  5262.8     .07       0
  5474.3    .035       0  5552.7     .07       0
Bank Sta=5009.9,5018.3
XS Rating Curve= 0 ,0
Exp/Cntr=0.3,0.1

Type RM Length L Ch R = 1 ,14090   ,419,419,419
BEGIN DESCRIPTION:
GUADALUPE TRIBUTARY 22 31.0
END DESCRIPTION:
XS GIS Cut Line= 3
        2259525.     13788874.97        2259625.       13788075.
        2259525.     13787675.01
#Sta/Elev= 30
  4193.4  607.79  4294.4  605.86    4492  603.14  4677.1  600.52  4697.3  599.47
  4714.9  600.89  4747.7  597.73  4788.5  597.08  4876.1  594.73  4929.1  594.68
  4961.8  593.48  4969.4  594.34  4985.2   592.3  4985.7   591.8  4993.8   592.3
  5002.2   592.9  5017.6  595.33  5022.8  595.18  5030.5  596.66  5058.9  595.92
  5071.8  594.89  5087.8  595.33  5174.8  599.21  5190.1  600.52  5236.7  602.83
    5265  603.23  5292.3   605.5  5311.4  607.68  5352.6  609.42  5411.9   610.4
#Mann= 9 ,-1 , 0
  4193.4    .035       0  4294.4     .07       0    4492    .035       0
  4788.5     .07       0  4985.2     .05       0  4993.8     .07       0
  5087.8    .035       0  5190.1     .07       0  5292.3    .035       0
Bank Sta=4985.2,4993.8
XS Rating Curve= 0 ,0
Exp/Cntr=0.3,0.1

Type RM Length L Ch R = 1 ,13671   ,527,527,527
BEGIN DESCRIPTION:
GUADALUPE TRIBUTARY 22 30.0
END DESCRIPTION:
XS GIS Cut Line= 3
      2260524.99     13788824.98      2260046.56     13788066.79
      2259674.99     13787624.99
#Sta/Elev= 30
  4093.7  609.11  4137.8  608.97    4159  607.05  4210.7  605.53  4282.9  604.78
  4443.1  601.13  4507.5  599.25  4529.7   599.6  4587.3  598.71  4593.2  597.67
  4702.1  595.56  4709.3  595.69  4796.8  595.92  4894.5  594.03  4985.1  593.35
  4994.7  592.84  4995.4  590.86  4995.9  590.36    5004  590.86    5014  593.54
  5112.9   593.6  5176.7  594.42  5297.6  597.16  5340.1  598.97  5389.9   600.6
    5472  604.59  5487.5  605.61  5525.2  607.39  5553.8  610.17  5567.5  610.67
#Mann= 11 ,-1 , 0
  4093.7     .07       0  4443.1    .035       0  4593.2     .07       0
  4702.1    .035       0  4709.3     .07       0  4894.5    .035       0
  4995.4    .035       0    5004    .035       0  5340.1    .094       0
    5472    .035       0  5487.5    .094       0
Bank Sta=4995.4,5004
XS Rating Curve= 0 ,0
Exp/Cntr=0.3,0.1

Type RM Length L Ch R = 1 ,13144   ,443,443,443
BEGIN DESCRIPTION:
GUADALUPE TRIBUTARY 22 29.0
END DESCRIPTION:
XS GIS Cut Line= 3
        2260675.     13788624.99        2260525.       13787925.
      2260224.99     13787524.98
#Sta/Elev= 30
  4280.1  606.59  4350.1  603.72  4423.3   600.6  4464.2   600.7  4525.5   598.3
  4541.7  599.37  4627.8  595.87  4658.5  596.67  4740.3  594.19  4760.8  595.03
  4811.9  593.49  4852.8   590.6    4863  590.79  4883.5  595.25  4893.7   595.6
  4914.2  591.82  4999.1  590.61  5004.9  587.91  5005.4  587.41  5014.1  587.91
  5032.4  590.62    5044  590.83  5115.3  591.05  5309.5  595.65  5353.3   598.9
  5388.7  599.37  5417.9  602.02  5438.7  601.76  5482.4  604.79    5496  604.57
#Mann= 6 ,-1 , 0
  4280.1    .035       0  4350.1     .07       0  5004.9     .05       0
  5014.1     .07       0    5044    .035       0  5115.3     .07       0
Bank Sta=5004.9,5014.1
XS Rating Curve= 0 ,0
Exp/Cntr=0.3,0.1