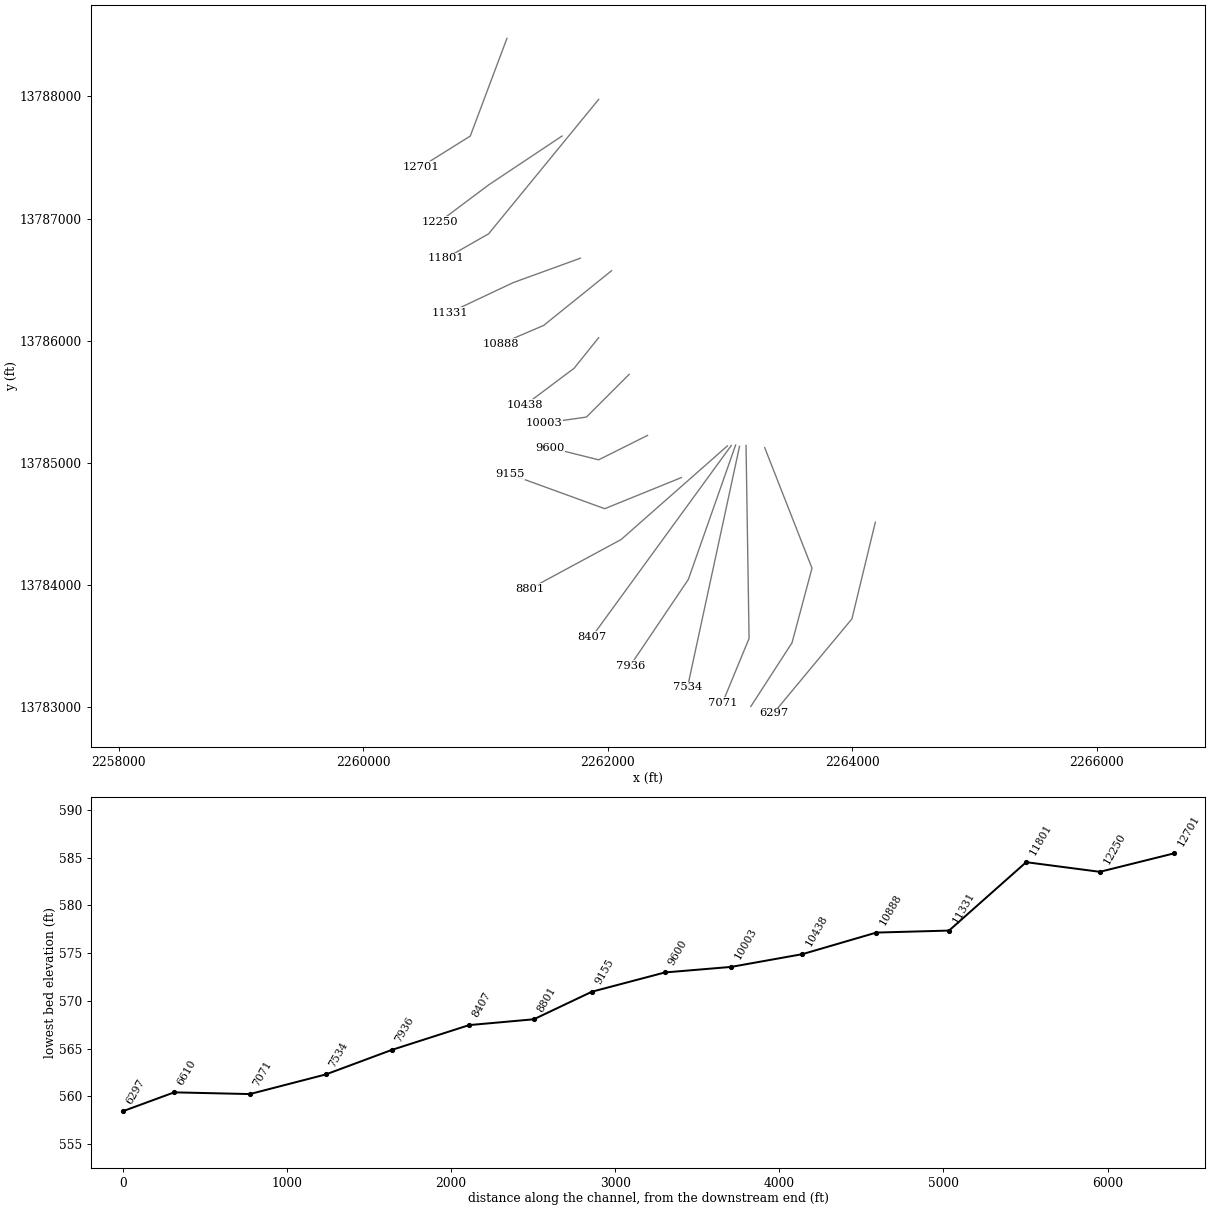
HEC-RAS study GUADALUPE TRIBUTARY 22.prj: GUADALUPE TRIBUTARY 22 Base Level Engineering

--- GUADALUPE TRIBUTARY 22.g01 (geometry) --- (continued)

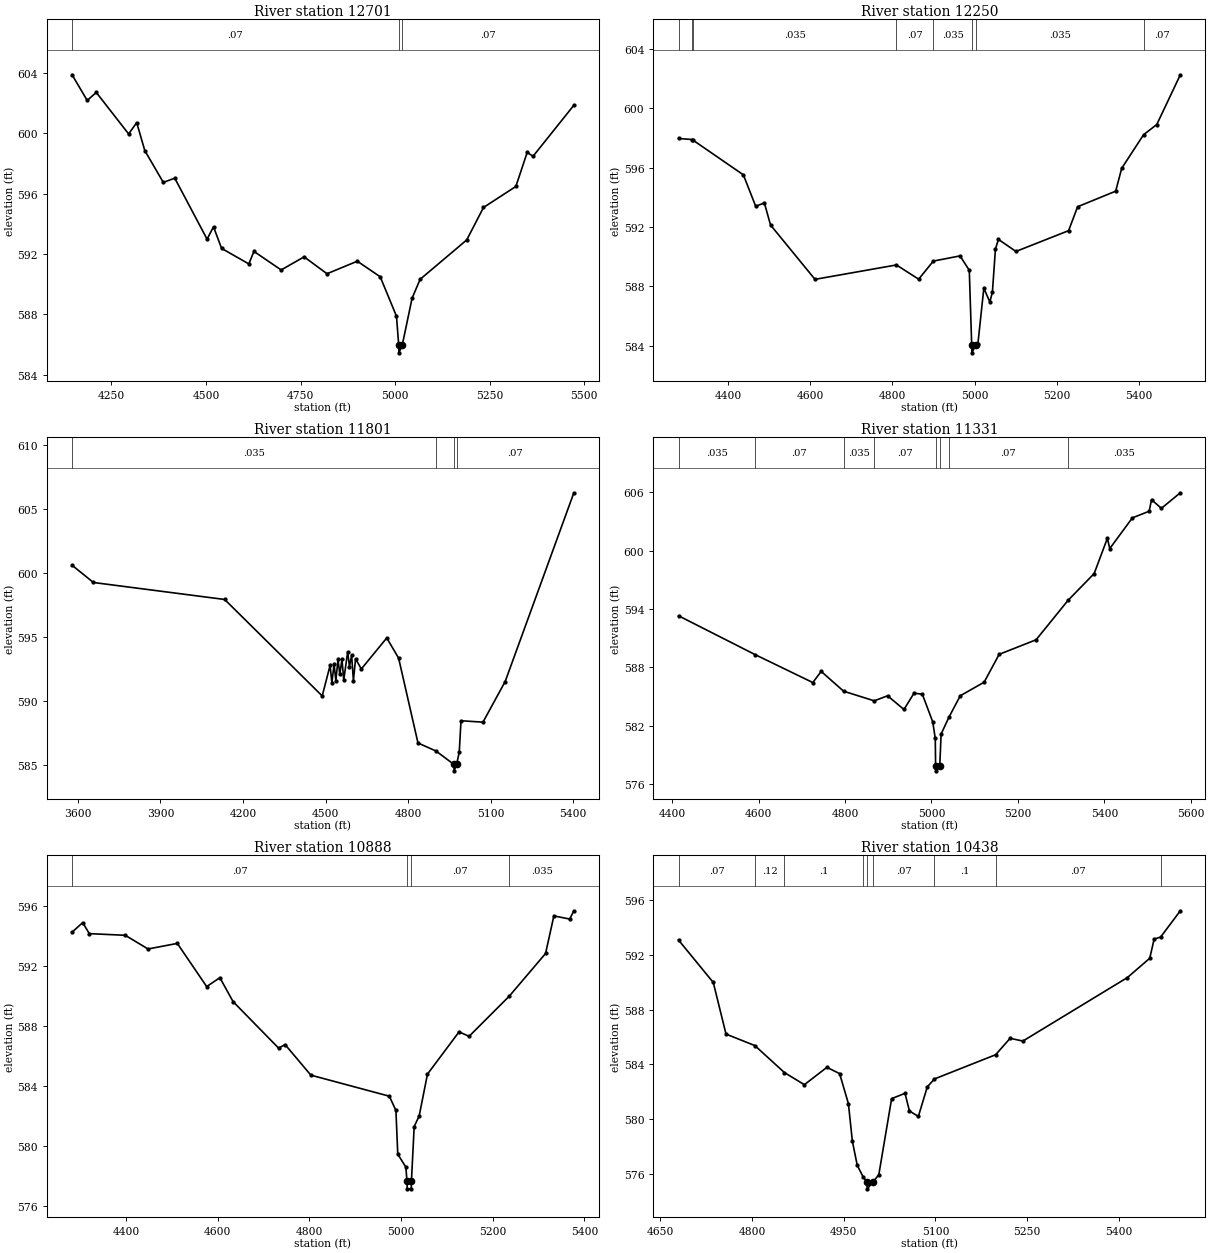
Type RM Length L Ch R = 1 ,12701   ,451,451,451
BEGIN DESCRIPTION:
GUADALUPE TRIBUTARY 22 28.0
END DESCRIPTION:
XS GIS Cut Line= 3
      2261174.98     13788474.96        2260875.       13787675.
      2260474.96     13787424.98
#Sta/Elev= 30
  4146.2  603.88  4186.2  602.18  4210.2  602.71  4295.7  599.96    4317  600.71
  4338.4  598.86  4387.3  596.75  4417.6  597.03    4503  592.99    4520  593.81
  4541.3  592.38  4613.4  591.35  4626.8  592.18  4698.8  590.95  4759.4  591.82
  4819.9   590.7    4900  591.53  4960.5   590.5  5003.5  587.89  5009.5  585.96
    5010  585.46  5018.7  585.96  5044.8  589.08    5066  590.33  5189.2  592.94
  5233.5  595.09    5319  596.48    5349  598.74  5364.4  598.48  5472.3  601.86
#Mann= 3 ,-1 , 0
  4146.2     .07       0  5009.5     .05       0  5018.7     .07       0
Bank Sta=5009.5,5018.7
XS Rating Curve= 0 ,0
Exp/Cntr=0.3,0.1

Type RM Length L Ch R = 1 ,12250   ,449,449,449
BEGIN DESCRIPTION:
GUADALUPE TRIBUTARY 22 27.0
END DESCRIPTION:
XS GIS Cut Line= 3
      2261625.04     13787675.03        2261025.       13787275.
      2260624.97     13786974.98
#Sta/Elev= 30
  4279.3  597.97  4312.1   597.9  4314.3  597.86  4437.1  595.52  4467.1   593.4
  4488.2  593.63  4503.2  592.14  4611.4  588.48  4809.6  589.45  4863.7  588.49
  4899.4  589.71  4964.4  590.06  4986.9  589.09  4992.8  584.03  4993.3  583.53
  5002.2  584.03  5007.8  584.12  5022.3  587.89  5036.9  586.95  5043.2  587.63
  5050.5  590.51  5057.8  591.17  5100.5  590.36  5228.6  591.76  5250.5  593.37
  5343.2  594.42  5357.8  595.96    5411  598.22  5443.2  598.91  5500.5  602.26
#Mann= 8 ,-1 , 0
  4279.3    .035       0  4312.1     .07       0  4314.3    .035       0
  4809.6     .07       0  4899.4    .035       0  4992.8    .035       0
  5002.2    .035       0    5411     .07       0
Bank Sta=4992.8,5002.2
XS Rating Curve= 0 ,0
Exp/Cntr=0.3,0.1

Type RM Length L Ch R = 1 ,11801   ,470,470,470
BEGIN DESCRIPTION:
GUADALUPE TRIBUTARY 22 26.0
END DESCRIPTION:
XS GIS Cut Line= 3
      2261924.97     13787974.97        2261025.       13786875.
      2260675.03     13786675.02
#Sta/Elev= 30
  3578.6  600.63  3656.1  599.28  4133.4  597.95    4488   590.4  4516.7  592.79
  4523.2  591.42  4531.1   592.9  4537.6   591.6  4545.5  593.27  4551.9  592.09
  4559.8  593.26  4566.3  591.65  4580.6  593.85  4587.1   592.7    4595  593.58
  4601.4  591.59  4609.3  593.31  4630.2  592.51  4722.7  594.94  4765.8  593.36
  4836.2  586.72  4901.8  586.09    4967  585.04  4967.5  584.54  4976.6  585.04
  4986.2     586  4992.6  588.46  5072.5  588.35  5153.2  591.53  5402.9   606.3
#Mann= 4 ,-1 , 0
  3578.6    .035       0  4901.8     .07       0    4967     .05       0
  4976.6     .07       0
Bank Sta=4967,4976.6
XS Rating Curve= 0 ,0
Exp/Cntr=0.3,0.1

Type RM Length L Ch R = 1 ,11331   ,443,443,443
BEGIN DESCRIPTION:
GUADALUPE TRIBUTARY 22 25.0
END DESCRIPTION:
XS GIS Cut Line= 3
      2261774.99       13786675.        2261225.       13786475.
      2260704.77     13786229.22
#Sta/Elev= 30
    4415  593.32  4591.9  589.33  4725.6  586.45  4744.9   587.6  4796.8  585.56
  4867.7  584.57  4898.5  585.09  4936.4  583.68  4959.7  585.36  4978.9  585.25
    5003   582.4  5008.8   580.7  5009.6  577.87  5010.1  577.37  5019.2  577.87
  5022.3  581.15  5040.1  582.86  5066.6  585.09  5121.9  586.49  5156.5  589.35
    5242  590.85  5315.8   594.9  5376.3  597.66  5406.9  601.29  5412.4  600.23
  5464.7  603.39  5503.5  604.07    5509  605.26  5531.8  604.37  5575.6  605.97
#Mann= 8 ,-1 , 0
    4415    .035       0  4591.9     .07       0  4796.8    .035       0
  4867.7     .07       0  5009.6     .05       0  5019.2     .07       0
  5040.1     .07       0  5315.8    .035       0
Bank Sta=5009.6,5019.2
XS Rating Curve= 0 ,0
Exp/Cntr=0.3,0.1

Type RM Length L Ch R = 1 ,10888   ,450,450,450
BEGIN DESCRIPTION:
GUADALUPE TRIBUTARY 22 24.0
END DESCRIPTION:
XS GIS Cut Line= 3
      2262030.41     13786572.68        2261475.       13786125.
      2261124.96     13785974.98
#Sta/Elev= 30
  4282.7  594.23  4305.9  594.86  4320.3  594.13  4398.7  594.02  4448.3  593.11
  4512.2  593.48  4576.2  590.61    4605   591.2  4633.8  589.61    4733  586.52
  4747.3  586.75  4803.4  584.72  4974.5  583.32  4988.9  582.37  4992.9  579.47
  5010.6   578.6    5013  577.66  5013.5  577.16  5022.2  577.16  5022.7  577.66
  5028.7   581.3  5039.6  582.01  5057.7  584.79  5126.6   587.6  5148.4   587.3
  5236.3  589.98  5315.2  592.81  5333.3  595.31  5367.8   595.1  5376.9  595.65
#Mann= 4 ,-1 , 0
  4282.7     .07       0    5013     .05       0  5022.7     .07       0
  5236.3    .035       0
Bank Sta=5013,5022.7
XS Rating Curve= 0 ,0
Exp/Cntr=0.3,0.1

Type RM Length L Ch R = 1 ,10438   ,435,435,435
BEGIN DESCRIPTION:
GUADALUPE TRIBUTARY 22 23.0
END DESCRIPTION:
XS GIS Cut Line= 3
        2261925.       13786025.        2261725.       13785775.
      2261324.96     13785474.97
#Sta/Elev= 30
  4680.1  593.08  4736.9  589.98  4757.7  586.21  4804.8  585.37  4853.1   583.4
  4885.8  582.51  4922.6  583.78  4943.4  583.32  4957.8  581.12  4964.2  578.39
  4972.2  576.62  4982.2  575.74    4988   575.4  4988.5   574.9  4998.1   575.4
  5007.5  575.94  5028.4  581.49  5050.3  581.88  5057.5  580.59  5072.1  580.19
  5086.7  582.35  5098.4  582.93  5198.4   584.7  5222.1   585.9    5243   585.7
  5413.8  590.34  5450.3  591.75  5457.5  593.15  5468.1   593.3  5500.3  595.22
#Mann= 9 ,-1 , 0
  4680.1     .07       0  4804.8     .12       0  4853.1      .1       0
  4982.2     .07       0    4988     .05       0  4998.1     .07       0
  5098.4      .1       0  5198.4     .07       0  5468.1    .035       0
Bank Sta=4988,4998.1
XS Rating Curve= 0 ,0
Exp/Cntr=0.3,0.1

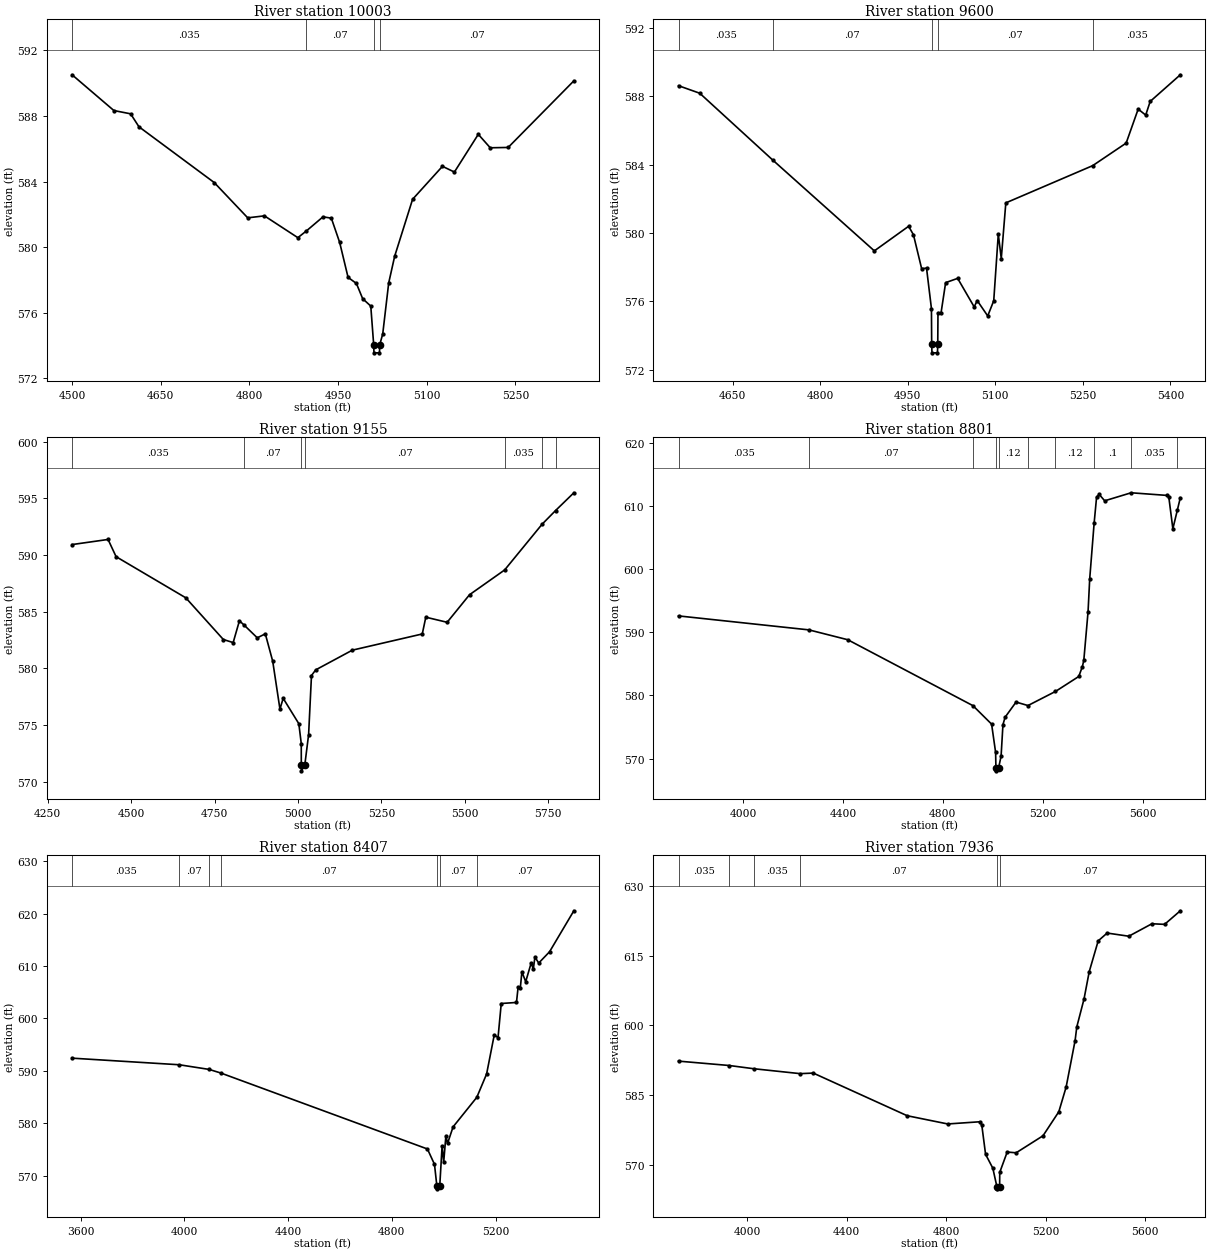
Type RM Length L Ch R = 1 ,10003   ,403,403,403
BEGIN DESCRIPTION:
GUADALUPE TRIBUTARY 22 22.0
END DESCRIPTION:
XS GIS Cut Line= 3
      2262174.99     13785724.99        2261825.       13785375.
      2261475.01       13785325.
#Sta/Elev= 30
  4500.3  590.51    4571  588.33  4599.3  588.13  4613.4  587.34  4740.7  583.94
  4797.3  581.79  4825.6  581.91  4882.1  580.58  4896.5  580.99  4924.6  581.85
  4938.7  581.77  4952.8  580.29    4967  578.16  4981.1  577.79  4991.7  576.86
  5005.4  576.41  5010.3  574.06  5010.8  573.56  5020.1  573.56  5020.6  574.06
  5025.6  574.71  5035.7  577.82  5045.8  579.45  5076.1  582.92  5126.6  584.93
  5146.8  584.58  5187.2  586.88  5207.4  586.06  5237.7  586.08  5348.8  590.14
#Mann= 4 ,-1 , 0
  4500.3    .035       0  4896.5     .07       0  5010.3     .05       0
  5020.6     .07       0
Bank Sta=5010.3,5020.6
XS Rating Curve= 0 ,0
Exp/Cntr=0.3,0.1

Type RM Length L Ch R = 1 ,9600    ,445,445,445
BEGIN DESCRIPTION:
GUADALUPE TRIBUTARY 22 21.0
END DESCRIPTION:
XS GIS Cut Line= 3
      2262324.96     13785224.98        2261925.       13785025.
      2261524.98       13785125.
#Sta/Elev= 30
  4557.4  588.62  4593.7  588.18    4719  584.26  4892.8  578.95  4951.5  580.39
  4959.8  579.89  4973.8  577.91  4982.2  577.94  4990.6  575.57    4991  573.48
  4991.5  572.98  5000.9  572.98  5001.4  573.48  5001.8  575.33  5007.1  575.33
  5014.9  577.09  5035.5  577.34  5063.8  575.67    5069  576.04    5087  575.14
  5097.3  576.03  5105.1  579.93  5110.2   578.5    5118  581.76  5266.8  583.94
  5324.1  585.26  5344.7  587.25  5357.6   586.9  5365.3   587.7  5416.9  589.26
#Mann= 5 ,-1 , 0
  4557.4    .035       0    4719     .07       0    4991     .05       0
  5001.4     .07       0  5266.8    .035       0
Bank Sta=4991,5001.4
XS Rating Curve= 0 ,0
Exp/Cntr=0.3,0.1

Type RM Length L Ch R = 1 ,9155    ,354,354,354
BEGIN DESCRIPTION:
GUADALUPE TRIBUTARY 22 20.0
END DESCRIPTION:
XS GIS Cut Line= 3
      2262601.82     13784879.84        2261975.       13784625.
      2261198.24     13784907.56
#Sta/Elev= 30
  4323.2  590.93    4431  591.38  4455.1  589.86  4663.9  586.23  4776.4  582.55
  4805.8  582.28  4824.5   584.2  4837.3  583.86    4878   582.7  4902.1  583.05
  4924.3  580.63  4945.9  576.41  4955.6  577.36  5002.5  575.12  5009.8  573.36
  5009.9  571.46  5010.4  570.96  5020.3  571.46  5031.8  574.16  5040.4  579.37
    5053  579.87  5162.8  581.61  5372.3  583.04  5382.9  584.52  5446.8  584.07
  5513.8   586.5  5619.1  588.69  5731.4  592.73  5771.5  593.93  5826.4   595.5
#Mann= 7 ,-1 , 0
  4323.2    .035       0  4837.3     .07       0  5009.9     .05       0
  5020.3     .07       0  5619.1    .035       0  5731.4    .063       0
  5771.5    .035       0
Bank Sta=5009.9,5020.3
XS Rating Curve= 0 ,0
Exp/Cntr=0.3,0.1

Type RM Length L Ch R = 1 ,8801    ,394,394,394
BEGIN DESCRIPTION:
A19238
END DESCRIPTION:
XS GIS Cut Line= 3
      2262978.01     13785138.92       2262108.5     13784372.33
      2261359.86     13783967.86
#Sta/Elev= 30
  3741.3  592.58  4263.7  590.37  4419.3  588.81  4920.7  578.38  4995.4  575.46
  5011.5  570.98  5012.7  568.57  5013.2  568.07  5023.6  568.57  5033.4   570.4
  5040.9  575.39  5049.6  576.56  5093.4  578.95  5141.1   578.4  5251.3  580.63
  5344.6     583  5359.1  584.57  5364.8  585.57  5381.8  593.25  5388.4  598.45
  5406.1  607.25    5416  611.39  5426.5   611.8  5448.4  610.79  5554.3  612.06
  5699.6  611.64  5705.3  611.37  5721.5  606.37  5739.1  609.26  5751.4  611.28
#Mann= 10 ,-1 , 0
  3741.3    .035       0  4263.7     .07       0  4920.7     .12       0
  5012.7     .05       0  5023.6     .12       0  5141.1      .1       0
  5251.3     .12       0  5406.1      .1       0  5554.3    .035       0
  5739.1    .063       0
Bank Sta=5012.7,5023.6
XS Rating Curve= 0 ,0
Exp/Cntr=0.3,0.1

Type RM Length L Ch R = 1 ,8407    ,471,471,471
BEGIN DESCRIPTION:
A19237
END DESCRIPTION:
XS GIS Cut Line= 2
      2263009.95     13785142.48      2261871.67     13783578.68
#Sta/Elev= 30
  3567.4  592.42  3980.5  591.16  4095.8  590.27  4140.9  589.58  4937.2  575.07
  4964.4  572.14  4973.6  567.96  4974.1  567.46  4984.6  567.96  4993.8  575.68
  4999.9  572.57  5008.4  577.62  5014.6  576.12  5036.1   579.3  5127.5  584.94
  5165.3   589.4  5194.7  596.85  5209.3  596.34  5221.7  602.86  5280.4  603.06
  5286.6  605.92  5295.1  605.78  5301.3   608.9    5316  607.03  5336.9  610.57
  5345.3  609.43  5351.5  611.73  5366.2  610.59  5407.9  612.74  5501.6  620.57
#Mann= 7 ,-1 , 0
  3567.4    .035       0  3980.5     .07       0  4095.8    .035       0
  4140.9     .07       0  4973.6     .05       0  4984.6     .07       0
  5127.5     .07       0
Bank Sta=4973.6,4984.6
XS Rating Curve= 0 ,0
Exp/Cntr=0.3,0.1

Type RM Length L Ch R = 1 ,7936    ,402,402,402
BEGIN DESCRIPTION:
A19236
END DESCRIPTION:
XS GIS Cut Line= 3
      2263045.41     13785145.99      2262658.59     13784045.83
      2262183.14     13783339.77
#Sta/Elev= 30
  3723.5  592.32  3927.4  591.38  4025.4  590.69  4212.6  589.63  4265.2  589.75
  4642.8  580.58  4805.8  578.81  4936.9  579.29  4942.9   578.5  4957.9  572.29
  4987.1  569.29  5003.3  565.36  5003.8  564.86  5014.4  565.36  5014.9   568.4
  5044.8  572.77  5080.8  572.61  5188.8  576.27  5252.4  581.44  5281.8  586.75
  5317.8  596.73  5324.7  599.69  5353.7  605.68  5374.7  611.57  5410.7  618.18
  5446.7  619.86  5533.7  619.18  5626.7  621.86  5677.6  621.73  5740.9  624.65
#Mann= 6 ,-1 , 0
  3723.5    .035       0  3927.4     .07       0  4025.4    .035       0
  4212.6     .07       0  5003.3     .05       0  5014.4     .07       0
Bank Sta=5003.3,5014.4
XS Rating Curve= 0 ,0
Exp/Cntr=0.3,0.1

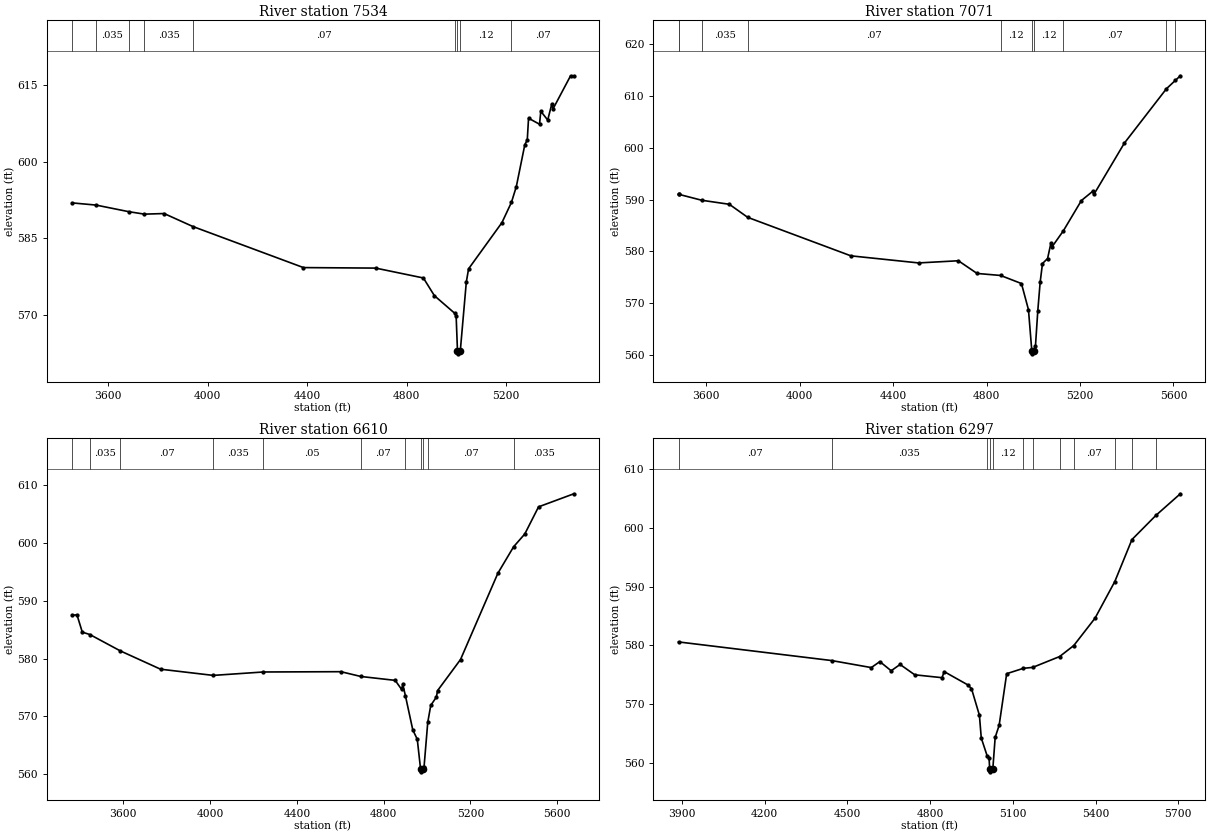
Type RM Length L Ch R = 1 ,7534    ,463,463,463
BEGIN DESCRIPTION:
A19235
END DESCRIPTION:
XS GIS Cut Line= 2
      2263077.35     13785135.31      2262651.49     13783162.14
#Sta/Elev= 30
  3454.6  591.92  3551.1  591.49  3682.1   590.2  3745.6  589.71  3824.8  589.83
  3940.7  587.28  4385.4  579.22  4675.9  579.12  4867.9  577.18  4912.1  573.71
  4994.9  570.21  4999.7  569.64  5005.1  562.79  5005.6  562.29  5016.2  562.79
  5040.6  576.39  5049.7  578.98  5183.8  588.04    5222  592.01  5241.7  595.11
  5275.9  603.34  5285.8  604.27  5290.9  608.54  5335.1  607.36  5340.2  609.91
    5368  608.18  5384.4  611.33  5389.5  610.38    5460  616.87  5473.2  616.75
#Mann= 9 ,-1 , 0
  3454.6     .07       0  3551.1    .035       0  3682.1     .07       0
  3745.6    .035       0  3940.7     .07       0  4994.9     .12       0
  5005.1     .05       0  5016.2     .12       0    5222     .07       0
Bank Sta=5005.1,5016.2
XS Rating Curve= 0 ,0
Exp/Cntr=0.3,0.1

Type RM Length L Ch R = 1 ,7071    ,461,461,461
BEGIN DESCRIPTION:
A19234
END DESCRIPTION:
XS GIS Cut Line= 3
       2263130.6     13785142.41      2263155.44     13783563.17
      2262938.97     13783037.97
#Sta/Elev= 30
    3482  591.04  3482.8  591.03  3581.2  589.88  3699.4   589.1    3778  586.58
  4219.5  579.15  4509.5  577.78  4679.6   578.2  4759.6  575.75  4860.3  575.36
  4949.6   573.8  4979.6  568.75    4994  560.73  4994.5  560.23  5005.1  560.73
  5009.6  561.79  5019.6  568.58  5029.6  574.05  5039.6  577.67  5061.4  578.63
  5075.7  581.61  5081.1  580.93  5128.8  583.97  5206.2  589.83  5254.1  591.59
  5259.5     591    5390  600.91  5570.1  611.41  5608.1  613.01  5629.5  613.91
#Mann= 10 ,-1 , 0
    3482    .035       0  3482.8     .07       0  3581.2    .035       0
    3778     .07       0  4860.3     .12       0    4994     .05       0
  5005.1     .12       0  5128.8     .07       0  5570.1    .035       0
  5608.1     .07       0
Bank Sta=4994,5005.1
XS Rating Curve= 0 ,0
Exp/Cntr=0.3,0.1

Type RM Length L Ch R = 1 ,6610    ,313,313,313
BEGIN DESCRIPTION:
A19233
END DESCRIPTION:
XS GIS Cut Line= 4
      2263283.18     13785124.76      2263670.04      13784138.1
      2263506.78     13783527.68       2263169.8     13783006.25
#Sta/Elev= 30
  3363.9  587.48  3386.5  587.57    3411  584.57  3445.7  584.16  3586.7  581.32
  3771.8  578.16  4014.4  577.09  4245.3  577.68  4602.9  577.73    4695   576.9
    4853  576.23  4882.4  574.67  4887.9  575.55  4900.4  573.52  4934.1  567.66
  4954.8  566.04  4969.9  560.91  4970.4  560.41  4981.1  560.91  4985.9  561.22
  5003.1  568.98  5016.9   571.9    5043  573.35  5048.1  574.45    5154  579.83
  5326.3  594.76  5398.8  599.34  5450.3  601.55  5513.7  606.24  5676.4   608.5
#Mann= 11 ,-1 , 0
  3363.9     .07       0  3445.7    .035       0  3586.7     .07       0
  4014.4    .035       0  4245.3     .05       0    4695     .07       0
  4900.4     .12       0  4969.9     .05       0  4981.1     .12       0
  5003.1     .07       0  5398.8    .035       0
Bank Sta=4969.9,4981.1
XS Rating Curve= 0 ,0
Exp/Cntr=0.3,0.1

Type RM Length L Ch R = 1 ,6297    ,309,309,309
BEGIN DESCRIPTION:
A19232
END DESCRIPTION:
XS GIS Cut Line= 4
      2264188.18     13784514.28      2263996.54     13783722.88
      2263716.17     13783385.73      2263354.53     13782949.63
#Sta/Elev= 30
  3888.2  580.56  4443.2  577.39  4587.1  576.19    4618  577.21  4659.1  575.65
  4691.5  576.72  4744.6  574.96  4843.5  574.47  4851.4   575.5    4936  573.27
  4950.3  572.62    4979  568.08  4985.8  564.19  5007.5   561.1  5014.1  560.82
  5016.2  558.93  5016.7  558.43  5027.7  558.93  5036.2   564.3  5050.6  566.36
  5077.9  575.15  5138.8  576.07  5172.1  576.22  5269.9  578.07  5321.1  579.94
  5398.3  584.61    5470  590.85  5532.1     598    5619  602.12  5707.5   605.8
#Mann= 12 ,-1 , 0
  3888.2     .07       0  4443.2    .035       0  5007.5     .12       0
  5016.2    .035       0  5027.7     .12       0  5138.8     .12       0
  5172.1    .035       0  5269.9     .12       0  5321.1     .07       0
    5470    .035       0  5532.1     .07       0    5619    .035       0
Bank Sta=5016.2,5027.7
XS Rating Curve= 0 ,0
Exp/Cntr=0.3,0.1