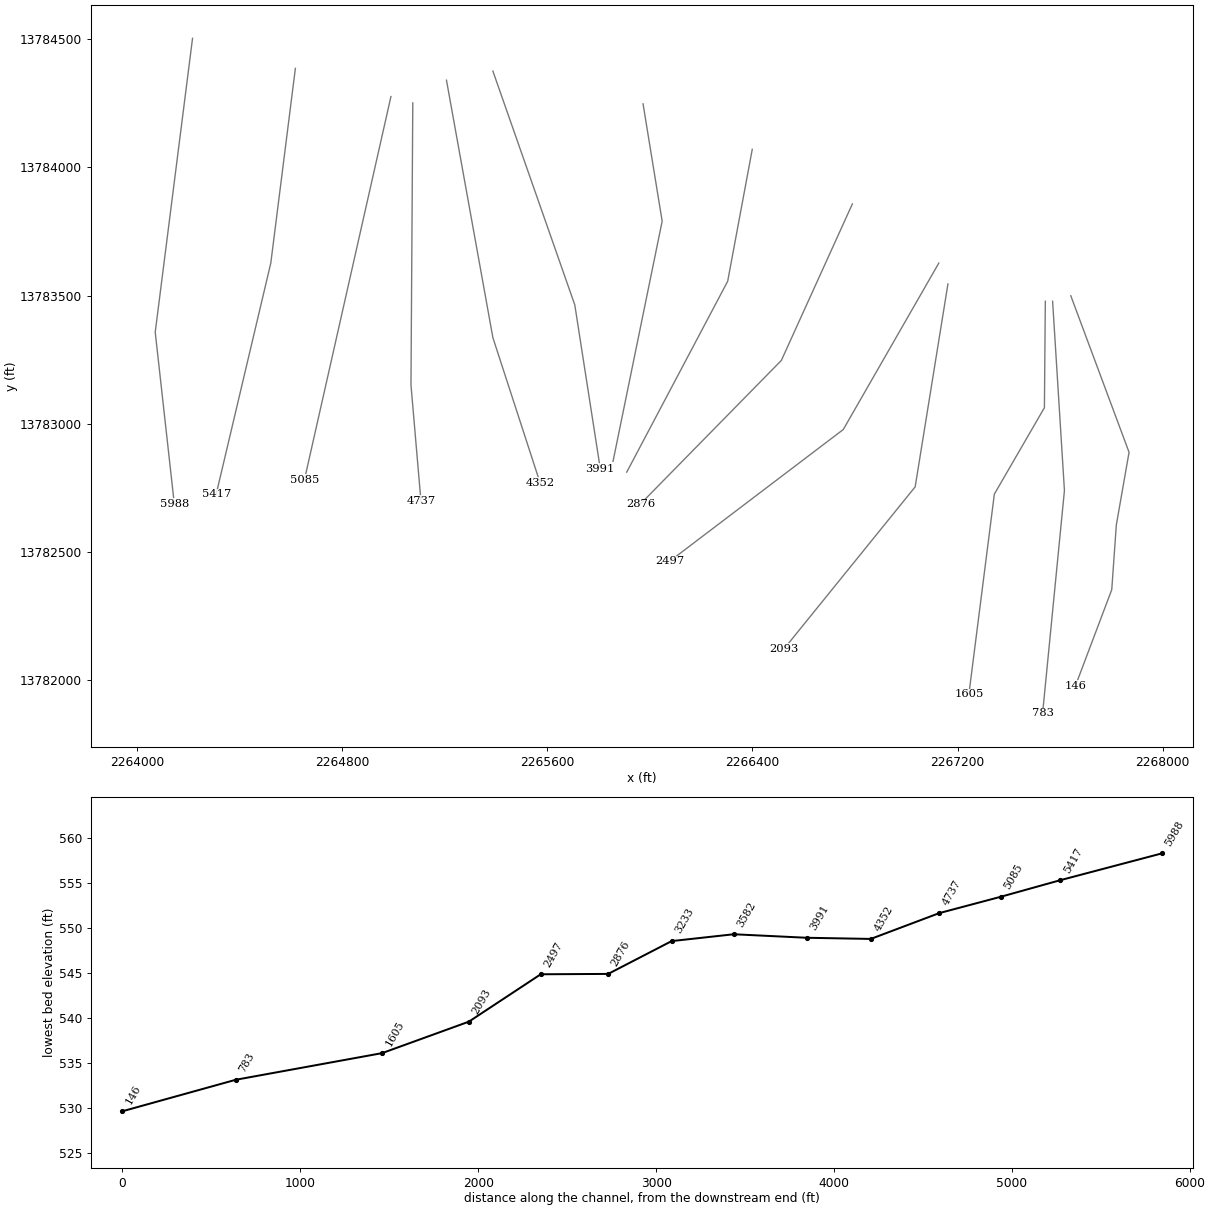
HEC-RAS study GUADALUPE TRIBUTARY 22.prj: GUADALUPE TRIBUTARY 22 Base Level Engineering

--- GUADALUPE TRIBUTARY 22.g01 (geometry) --- (continued)

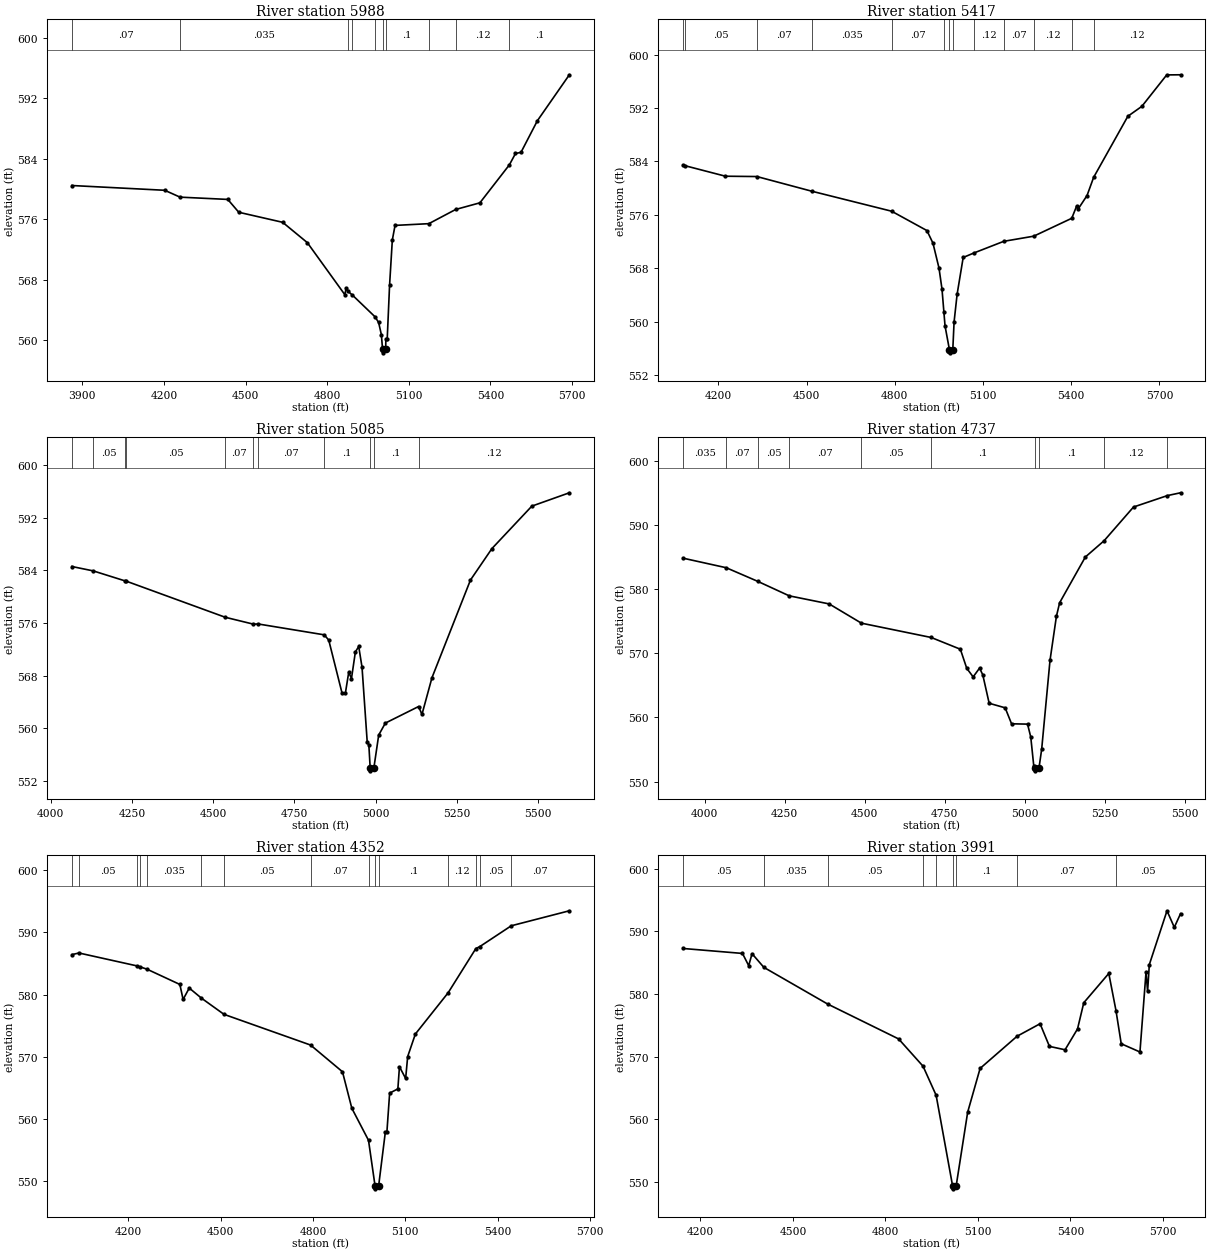
Type RM Length L Ch R = 1 ,5988    ,571,571,571
BEGIN DESCRIPTION:
A19231
END DESCRIPTION:
XS GIS Cut Line= 3
      2264216.57     13784503.63      2264071.07     13783357.34
      2264145.41     13782688.25
#Sta/Elev= 30
  3861.5  580.47  4202.8  579.84  4259.2  578.93  4434.7  578.63    4475  576.93
  4636.3   575.6    4727  572.91  4864.9  566.02  4869.9  566.89  4876.4  566.47
  4892.9  565.96  4975.9  563.09  4989.1  562.34  4999.2  560.73  5003.5  558.82
    5004  558.32  5015.1  558.82  5015.7  560.16  5020.7  560.16  5029.4   567.3
  5039.5  573.26  5049.5  575.19  5173.7  575.42  5272.4   577.3  5361.4  578.18
  5469.8  583.21  5492.2  584.71  5512.4  584.86  5572.7  589.05  5690.2  595.13
#Mann= 10 ,-1 , 0
  3861.5     .07       0  4259.2    .035       0  4876.4      .1       0
  4892.9     .12       0  4975.9      .1       0  5003.5     .05       0
  5015.1      .1       0  5173.7      .1       0  5272.4     .12       0
  5469.8      .1       0
Bank Sta=5003.5,5015.1
XS Rating Curve= 0 ,0
Exp/Cntr=0.3,0.1

Type RM Length L Ch R = 1 ,5417    ,332,332,332
BEGIN DESCRIPTION:
A19230
END DESCRIPTION:
XS GIS Cut Line= 3
       2264617.6     13784386.53      2264521.78     13783627.06
      2264308.85     13782725.66
#Sta/Elev= 30
  4079.9  583.43  4085.2  583.38  4224.1  581.79    4331  581.74  4517.1  579.55
  4789.1  576.55  4909.2  573.65  4929.7  571.77  4950.3  568.03  4960.5  564.87
  4966.8  561.51  4970.8  559.37  4985.6  555.84  4986.1  555.34  4997.2  555.84
  5001.6  559.99  5011.9  564.12  5032.5  569.62  5068.7  570.29  5170.5  572.04
  5272.4  572.81  5401.7  575.49  5418.2  577.31  5423.3  576.87  5453.7   578.9
  5476.1  581.62  5592.5  590.77    5640  592.25  5724.6  596.96  5771.6  596.98
#Mann= 13 ,-1 , 0
  4079.9    .035       0  4085.2     .05       0    4331     .07       0
  4517.1    .035       0  4789.1     .07       0  4966.8      .1       0
  4985.6     .05       0  4997.2      .1       0  5068.7     .12       0
  5170.5     .07       0  5272.4     .12       0  5401.7      .1       0
  5476.1     .12       0
Bank Sta=4985.6,4997.2
XS Rating Curve= 0 ,0
Exp/Cntr=0.3,0.1

Type RM Length L Ch R = 1 ,5085    ,348,348,348
BEGIN DESCRIPTION:
A19229
END DESCRIPTION:
XS GIS Cut Line= 2
      2264990.24     13784276.51      2264653.09     13782782.38
#Sta/Elev= 30
  4064.9  584.58  4130.8  583.91  4228.8  582.39  4232.4  582.35  4537.2  576.86
  4624.1  575.81  4638.7  575.84  4841.9  574.19  4855.8  573.39  4896.8  565.32
  4907.1  565.34  4917.3  568.49  4925.8  567.55  4937.8  571.59  4948.1  572.42
  4958.3  569.26  4974.2  557.93  4979.3  557.44  4983.3  554.01  4983.8  553.51
  4994.9  554.01  5009.6  558.95  5030.1  560.77  5132.4  563.29  5142.8  562.09
  5173.6  567.67  5292.1  582.52  5358.1   587.3  5481.1  593.76  5596.6  595.79
#Mann= 11 ,-1 , 0
  4064.9    .035       0  4130.8     .05       0  4228.8     .07       0
  4232.4     .05       0  4537.2     .07       0  4624.1     .05       0
  4638.7     .07       0  4841.9      .1       0  4983.3     .05       0
  4994.9      .1       0  5132.4     .12       0
Bank Sta=4983.3,4994.9
XS Rating Curve= 0 ,0
Exp/Cntr=0.3,0.1

Type RM Length L Ch R = 1 ,4737    ,385,385,385
BEGIN DESCRIPTION:
A19228
END DESCRIPTION:
XS GIS Cut Line= 3
      2265075.42     13784251.68      2265068.32      13783151.5
      2265107.24     13782698.57
#Sta/Elev= 30
  3932.2  584.82  4067.2  583.33  4165.6  581.21  4264.1  578.95  4388.9  577.69
  4489.7  574.69  4707.8  572.46  4798.9  570.63  4818.9  567.65  4838.9  566.32
  4858.9  567.69  4868.9  566.65  4888.9  562.21  4938.9   561.5  4958.9  559.01
  5008.9  558.96  5018.9  556.95  5028.2  552.49  5033.1  552.18  5033.6  551.68
  5044.8  552.18    5053  555.04  5079.1  568.91  5099.1  575.77  5109.2  577.88
  5189.5     585  5248.2  587.54    5340  592.79  5445.8  594.57    5487  595.01
#Mann= 10 ,-1 , 0
  3932.2    .035       0  4067.2     .07       0  4165.6     .05       0
  4264.1     .07       0  4489.7     .05       0  4707.8      .1       0
  5033.1     .05       0  5044.8      .1       0  5248.2     .12       0
  5445.8     .05       0
Bank Sta=5033.1,5044.8
XS Rating Curve= 0 ,0
Exp/Cntr=0.3,0.1

Type RM Length L Ch R = 1 ,4352    ,361,361,361
BEGIN DESCRIPTION:
A19227
END DESCRIPTION:
XS GIS Cut Line= 3
      2265206.72     13784340.43      2265387.73     13783336.04
      2265571.98     13782769.09
#Sta/Elev= 30
  4016.5  586.42  4039.7  586.68    4229   584.6  4238.6  584.45  4261.2  584.07
  4367.5  581.63    4378  579.22    4398  581.05  4437.6  579.43  4510.9  576.83
  4792.2   571.9  4895.9  567.61  4926.3  561.75  4980.5  556.61  5001.7  549.31
  5002.2  548.81  5013.5  549.31  5035.1  557.88  5040.2  557.88  5049.2  564.18
  5075.9  564.86  5081.1  568.42  5101.2  566.53  5107.8  570.05  5132.8  573.67
  5239.4   580.3  5329.4   587.4  5341.9   587.7  5444.4  591.05  5633.2  593.46
#Mann= 15 ,-1 , 0
  4016.5    .035       0  4039.7     .05       0    4229    .035       0
  4238.6     .05       0  4261.2    .035       0  4437.6     .07       0
  4510.9     .05       0  4792.2     .07       0  4980.5      .1       0
  5001.7     .05       0  5013.5      .1       0  5239.4     .12       0
  5329.4     .07       0  5341.9     .05       0  5444.4     .07       0
Bank Sta=5001.7,5013.5
XS Rating Curve= 0 ,0
Exp/Cntr=0.3,0.1

Type RM Length L Ch R = 1 ,3991    ,409,409,409
BEGIN DESCRIPTION:
A19226
END DESCRIPTION:
XS GIS Cut Line= 3
      2265387.72     13784375.91      2265707.13      13783463.8
       2265806.5       13782825.
#Sta/Elev= 30
  4143.9  587.26  4336.6  586.47  4356.8  584.52  4367.6  586.43  4405.9  584.25
  4612.4  578.41  4842.8  572.84    4922  568.49  4964.4  563.86  5017.7  549.44
  5018.2  548.94  5029.5  549.44  5066.7  561.17    5107  568.14  5226.9  573.27
  5301.4  575.26  5331.8  571.65  5382.4  571.11  5422.8  574.43  5443.1  578.61
  5524.2  583.28  5547.5  577.36  5564.5  572.07  5625.2  570.76  5644.9   583.5
    5650  580.43  5655.6  584.69  5712.9  593.27  5736.6  590.63  5756.8  592.81
#Mann= 9 ,-1 , 0
  4143.9     .05       0  4405.9    .035       0  4612.4     .05       0
    4922     .12       0  4964.4      .1       0  5017.7     .05       0
  5029.5      .1       0  5226.9     .07       0  5547.5     .05       0
Bank Sta=5017.7,5029.5
XS Rating Curve= 0 ,0
Exp/Cntr=0.3,0.1

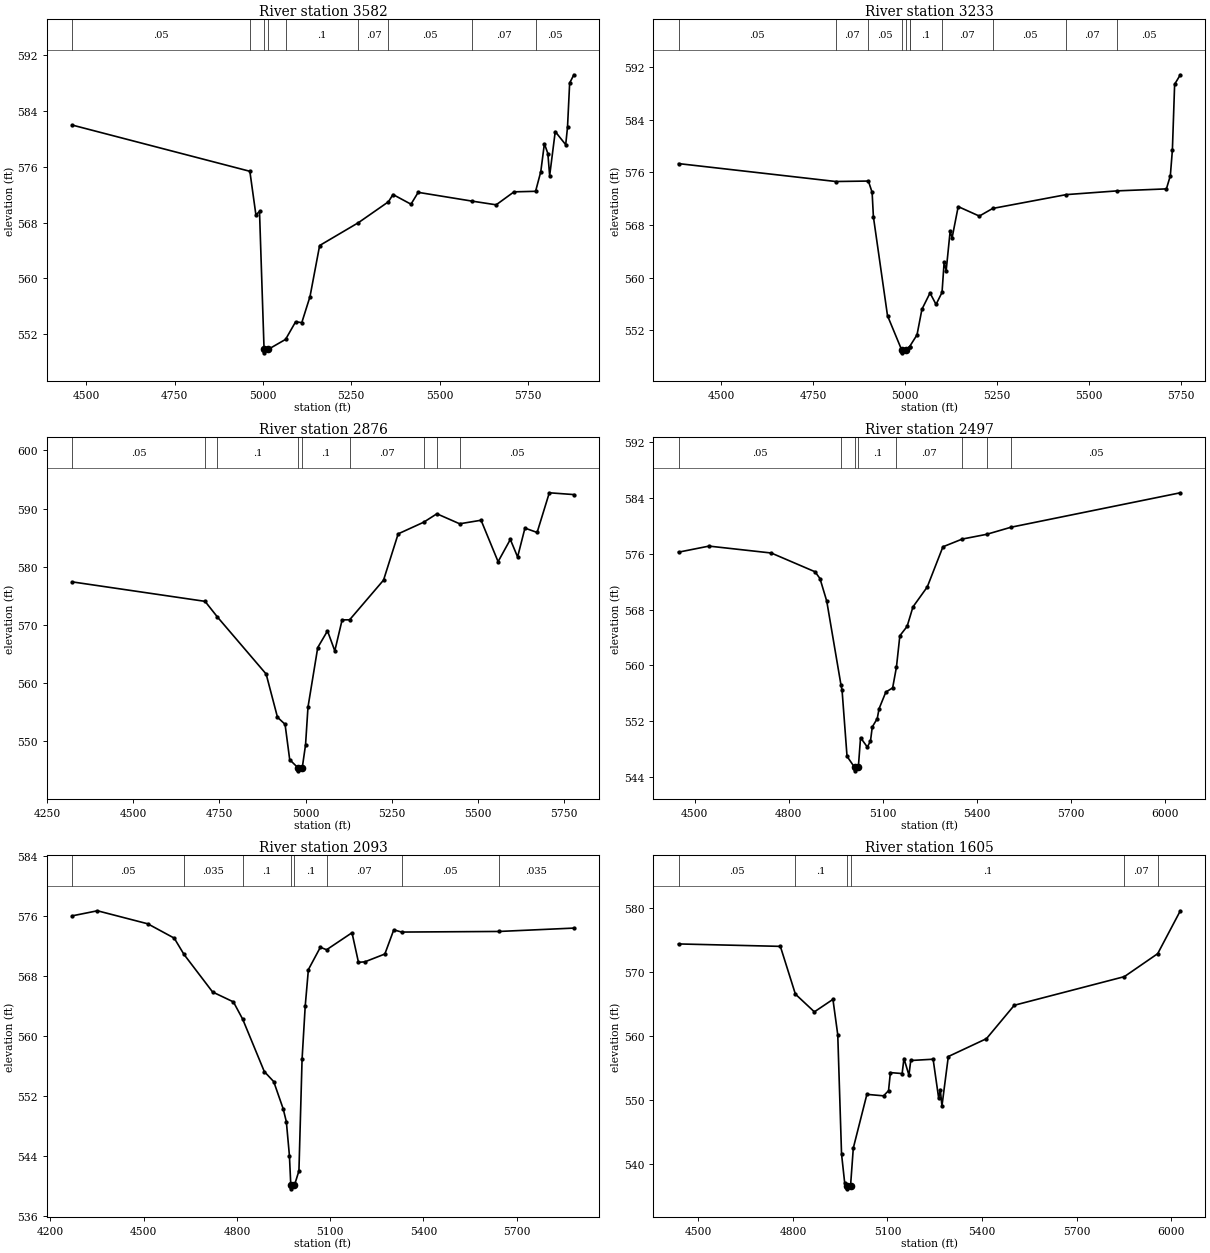
Type RM Length L Ch R = 1 ,3582    ,349,349,349
BEGIN DESCRIPTION:
A19225
END DESCRIPTION:
XS GIS Cut Line= 3
       2265973.3     13784248.11      2266047.83     13783790.31
      2265856.18     13782853.34
#Sta/Elev= 30
    4460  582.02  4963.2  575.38  4980.3  569.13  4990.5  569.62  5003.4  549.83
  5003.9  549.33  5015.2  549.83  5064.3  551.26  5092.6  553.78  5110.2  553.67
  5133.4   557.4  5160.7  564.73  5270.5  568.01  5355.5  571.01  5368.2  572.05
  5419.2  570.66  5439.6  572.36  5592.2   571.1  5660.3  570.57  5710.8  572.43
  5771.9  572.51  5786.6  575.33  5796.8  579.34  5806.6  577.93  5811.7  574.75
  5827.5  581.08  5857.1   579.2  5862.2  581.68  5868.3  588.05  5880.2  589.23
#Mann= 9 ,-1 , 0
    4460     .05       0  4963.2     .12       0  5003.4     .05       0
  5015.2     .12       0  5064.3      .1       0  5270.5     .07       0
  5355.5     .05       0  5592.2     .07       0  5771.9     .05       0
Bank Sta=5003.4,5015.2
XS Rating Curve= 0 ,0
Exp/Cntr=0.3,0.1

Type RM Length L Ch R = 1 ,3233    ,357,357,357
BEGIN DESCRIPTION:
A19224
END DESCRIPTION:
XS GIS Cut Line= 3
      2266399.17     13784070.65      2266303.36     13783556.08
       2265909.7     13782811.33
#Sta/Elev= 30
  4383.7  577.31  4811.8  574.59  4900.4  574.66  4910.6  572.95  4914.1  569.23
  4952.5  554.21  4990.6  549.07  4991.1  548.57  5002.5  549.07  5012.6  549.52
  5012.8  549.53  5032.8   551.3  5046.2  555.19  5068.2  557.66  5084.6  555.92
  5100.9  557.75  5106.6  562.33  5112.2  561.07  5122.9  567.01  5128.3  566.04
  5144.9  570.78  5202.4  569.34  5238.8   570.5  5439.1   572.6  5578.2  573.17
  5711.6  573.47  5722.3  575.47  5727.9  579.37    5734  589.36  5749.5   590.8
#Mann= 11 ,-1 , 0
  4383.7     .05       0  4811.8     .07       0  4900.4     .05       0
  4990.6     .05       0  5002.5     .05       0  5012.6     .07       0
  5012.8      .1       0  5100.9     .07       0  5238.8     .05       0
  5439.1     .07       0  5578.2     .05       0
Bank Sta=4990.6,5002.5
XS Rating Curve= 0 ,0
Exp/Cntr=0.3,0.1

Type RM Length L Ch R = 1 ,2876    ,379,379,379
BEGIN DESCRIPTION:
A19223
END DESCRIPTION:
XS GIS Cut Line= 3
      2266789.55      13783857.7      2266512.74     13783247.32
      2265962.67      13782686.6
#Sta/Elev= 30
  4322.4   577.4  4708.2  574.05  4744.2  571.35  4885.4  561.56  4918.3  554.13
  4940.3  552.92  4953.8  546.83  4978.2  545.42  4978.7  544.92  4990.1  545.42
  4999.7  549.38  5006.8  555.87  5035.1  566.11  5063.4  568.97  5084.6  565.54
  5105.8  570.86  5127.6  570.88    5226   577.7  5268.4  585.65  5342.4  587.65
  5380.7   589.1  5446.8  587.38  5508.9  587.99  5558.3  580.87  5593.8  584.69
  5614.9  581.68  5636.2  586.64  5671.5  585.89  5706.9  592.71  5778.1   592.4
#Mann= 9 ,-1 , 0
  4322.4     .05       0  4708.2     .07       0  4744.2      .1       0
  4978.2     .05       0  4990.1      .1       0  5127.6     .07       0
  5342.4      .1       0  5380.7     .07       0  5446.8     .05       0
Bank Sta=4978.2,4990.1
XS Rating Curve= 0 ,0
Exp/Cntr=0.3,0.1

Type RM Length L Ch R = 1 ,2497    ,404,404,404
BEGIN DESCRIPTION:
A19222
END DESCRIPTION:
XS GIS Cut Line= 3
      2267126.71     13783627.04      2266754.07      13782977.6
      2266076.23     13782463.01
#Sta/Elev= 30
  4448.3  576.25  4545.4  577.12  4743.9  576.13  4883.4  573.44  4899.2  572.47
  4920.8  569.23  4966.2   557.2  4969.7  556.42  4985.5  546.96  5009.6  545.38
  5010.1  544.88  5021.5  545.38  5028.6  549.64  5050.2  548.29  5060.3  549.16
    5066  551.18  5081.8  552.37  5087.6  553.79  5109.2  556.18  5130.9  556.78
    5143  559.75  5153.9  564.26    5177   565.6  5195.7   568.4  5241.3  571.26
  5291.2  577.02  5352.8  578.13  5430.6  578.81  5508.5  579.83  6048.1  584.77
#Mann= 8 ,-1 , 0
  4448.3     .05       0  4966.2      .1       0  5009.6     .05       0
  5021.5      .1       0    5143     .07       0  5352.8     .05       0
  5430.6     .07       0  5508.5     .05       0
Bank Sta=5009.6,5021.5
XS Rating Curve= 0 ,0
Exp/Cntr=0.3,0.1

Type RM Length L Ch R = 1 ,2093    ,488,488,488
BEGIN DESCRIPTION:
A19221
END DESCRIPTION:
XS GIS Cut Line= 3
       2267162.2     13783545.45      2267034.44     13782754.01
      2266523.41     13782122.33
#Sta/Elev= 30
  4269.8  576.04  4351.4  576.72  4513.4  574.98  4598.4  573.07  4629.8   570.9
  4721.9  565.88  4788.8  564.56  4818.7  562.25  4888.2  555.26  4918.5  553.92
  4948.9  550.29  4959.1  548.57    4969  544.04  4973.4  540.11  4973.9  539.61
  4985.3  540.11  4999.6  542.01  5009.7  556.91  5019.8     564    5030  568.87
  5068.5  571.85  5088.6  571.52  5170.3  573.79  5191.1  569.84  5211.9  569.91
    5276  570.95  5304.7  574.18  5329.9  573.88  5643.1  573.96    5884  574.41
#Mann= 8 ,-1 , 0
  4269.8     .05       0  4629.8    .035       0  4818.7      .1       0
  4973.4     .05       0  4985.3      .1       0  5088.6     .07       0
  5329.9     .05       0  5643.1    .035       0
Bank Sta=4973.4,4985.3
XS Rating Curve= 0 ,0
Exp/Cntr=0.3,0.1

Type RM Length L Ch R = 1 ,1605    ,822,822,822
BEGIN DESCRIPTION:
A19220
END DESCRIPTION:
XS GIS Cut Line= 4
      2267541.94     13783477.95      2267538.39     13783062.77
       2267343.2     13782725.62      2267243.83     13781944.89
#Sta/Elev= 30
  4437.2  574.37  4760.2  573.99  4807.9  566.53  4868.1  563.76    4927  565.71
  4942.3  560.18  4954.3  541.56  4964.3  537.02  4970.9  536.61  4971.4  536.11
  4982.9  536.61  4991.6  542.48  5034.7  550.87  5087.7  550.64  5103.4  551.45
  5109.2  554.27  5146.5  554.12  5152.3  556.47  5168.1  553.87  5173.8  556.16
  5244.8  556.36  5262.5  550.25  5267.5  551.62  5272.8  549.05    5293  556.78
    5414  559.57  5502.3  564.79  5851.4  569.26  5957.2  572.85    6029  579.55
#Mann= 6 ,-1 , 0
  4437.2     .05       0  4807.9      .1       0  4970.9     .05       0
  4982.9      .1       0  5851.4     .07       0  5957.2    .035       0
Bank Sta=4970.9,4982.9
XS Rating Curve= 0 ,0
Exp/Cntr=0.3,0.1

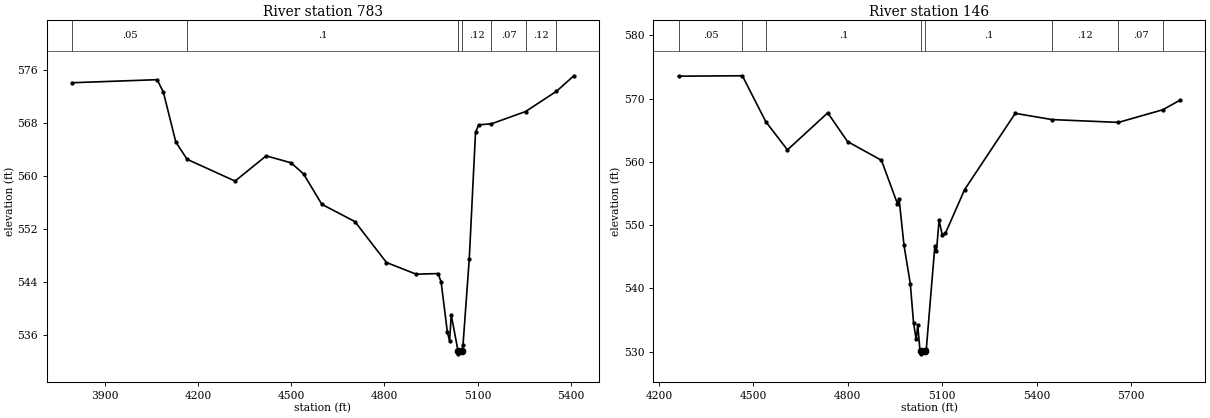
Type RM Length L Ch R = 1 ,783     ,637,637,637
BEGIN DESCRIPTION:
A19219
END DESCRIPTION:
XS GIS Cut Line= 3
      2267570.33     13783477.97      2267616.47     13782739.82
      2267531.29     13781870.28
#Sta/Elev= 30
  3795.7  574.09  4069.2  574.55  4089.2  572.67  4129.3  565.13  4165.5  562.53
  4319.7  559.24  4419.9  563.05    4500  561.99  4540.2  560.31  4598.5  555.74
  4705.1  553.12  4806.6  546.94  4901.9  545.18  4972.2  545.27  4982.2  544.02
  5002.3  536.42  5009.6  535.08  5014.7  539.02  5035.9  533.77  5036.5  533.65
    5037  533.15  5048.6  533.65  5052.6  534.49  5072.7  547.46  5092.8  566.58
  5102.8  567.73  5144.2  567.89  5253.7  569.74  5352.9  572.79    5409  575.14
#Mann= 8 ,-1 , 0
  3795.7     .05       0  4165.5      .1       0  5035.9     .12       0
  5036.5     .05       0  5048.6     .12       0  5144.2     .07       0
  5253.7     .12       0  5352.9    .035       0
Bank Sta=5036.5,5048.6
XS Rating Curve= 0 ,0
Exp/Cntr=0.3,0.1

Type RM Length L Ch R = 1 ,146     ,0,0,0
BEGIN DESCRIPTION:
A19218
END DESCRIPTION:
XS GIS Cut Line= 5
      2267641.31     13783499.28      2267868.44     13782888.87
      2267818.76     13782604.96      2267801.01     13782352.98
      2267659.06      13781976.8
#Sta/Elev= 30
  4262.5  573.56  4465.3  573.62  4539.5  566.38  4608.5   561.9  4736.5  567.76
  4799.4  563.22  4907.3  560.25    4958  553.38  4963.1  554.21  4978.6  546.89
  4998.9  540.71  5009.1  534.54  5017.5  531.94  5022.6  534.14  5029.4  530.26
  5033.5  530.15    5034  529.65  5045.6  530.15  5049.7  530.41  5076.9  546.75
    5082  545.94  5090.3  550.77  5100.5  548.41  5110.6  548.73  5171.5  555.63
  5332.3  567.68  5449.5  566.69  5660.2  566.25  5801.2  568.25  5856.7  569.79
#Mann= 8 ,-1 , 0
  4262.5     .05       0  4465.3     .07       0  4539.5      .1       0
  5033.5     .05       0  5045.6      .1       0  5449.5     .12       0
  5660.2     .07       0  5801.2     .12       0
Bank Sta=5033.5,5045.6
XS Rating Curve= 0 ,0
Exp/Cntr=0.3,0.1

Chan Stop Cuts=-1
Use User Specified Reach Order=0
Composite Channel Slope=5