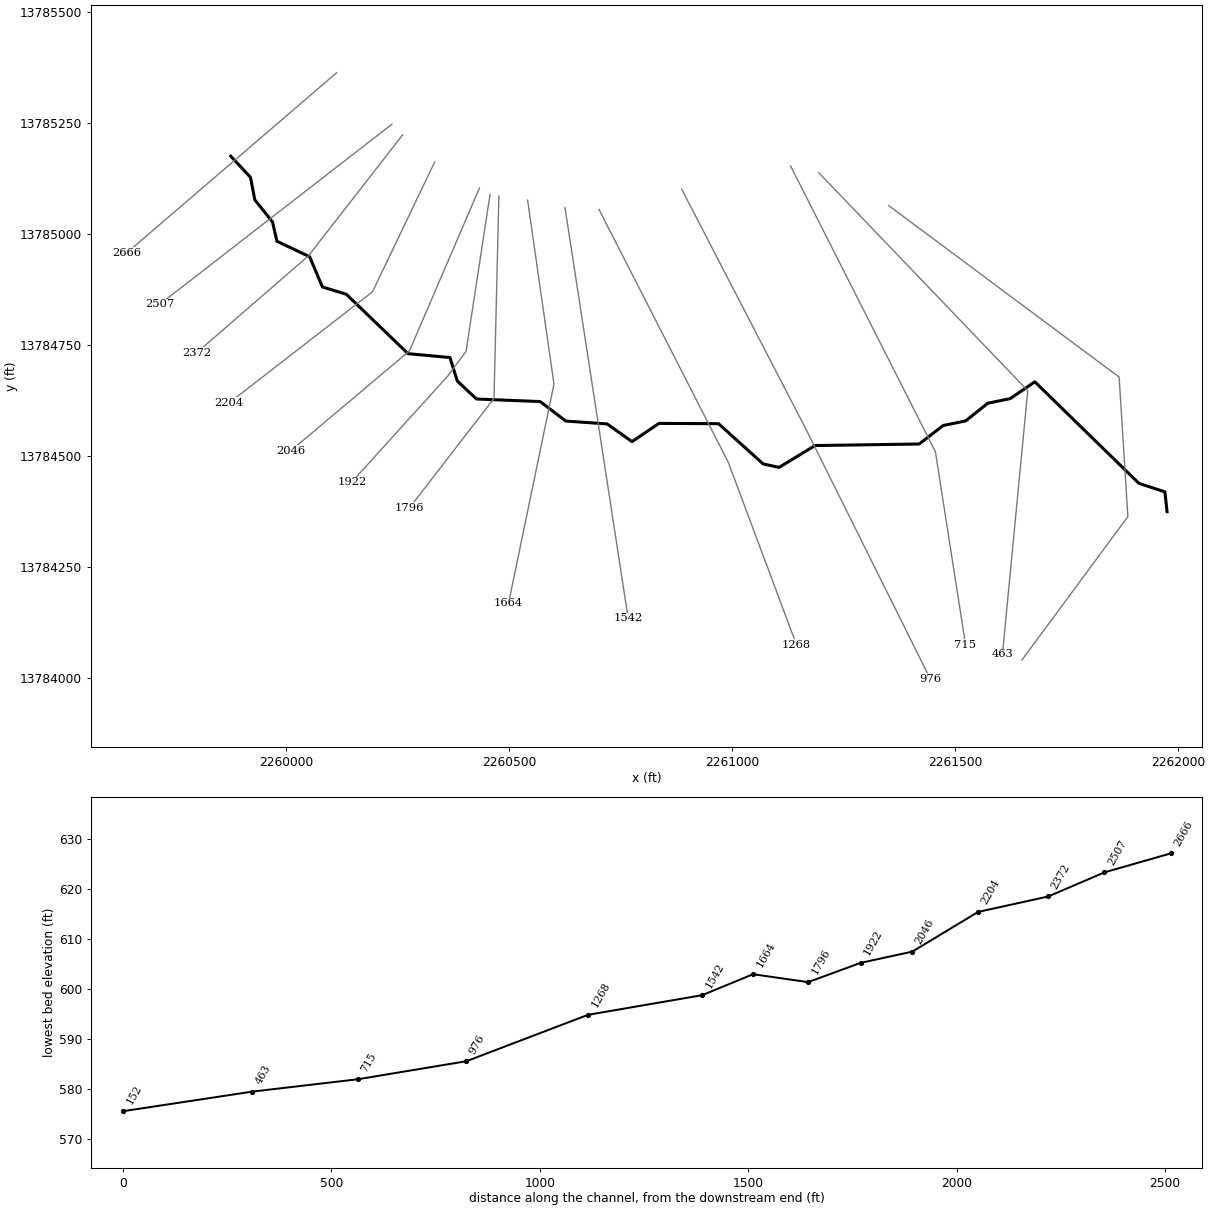
--- GUADALUPE TRIBUTARY 23 2.prj (project) ---

Proj Title=GUADALUPE TRIBUTARY 23 2 Base Level Engineering
Current Plan=p01
Default Exp/Contr=0.3,0.1
English Units
Geom File=g01
Flow File=f01
Plan File=p01
BEGIN DESCRIPTION:
GUADALUPE TRIBUTARY 23 2
END DESCRIPTION:

--- GUADALUPE TRIBUTARY 23 2.p01 (plan) ---

Plan Title=Multiple Run
Short Identifier=Multiple
Geom File=g01
Flow File=f01
Subcritical Flow
K Sum by GR= 0
Std Step Tol= 0.01
Critical Tol= 0.01
Num of Std Step Trials= 20
Max Error Tol= 0.3
Flow Tol Ratio= 0.001
Split Flow NTrial= 30
Split Flow Tol= 0.02
Split Flow Ratio= 0.02
Log Output Level= 0
Friction Slope Method= 1
Unsteady Friction Slope Method= 2
Unsteady Bridges Friction Slope Method= 1
Parabolic Critical Depth
Global Vel Dist=  1 , 1 , 1
Global Log Level= 0
CheckData=True
Encroach Param= -1, 0, 0, 0
BEGIN DESCRIPTION:
Multiple Run
END DESCRIPTION:

--- GUADALUPE TRIBUTARY 23 2.f01 (steady flow) ---

Flow Title=Multiple
Number of Profiles=7
Profile Names=10-year,25-year,50-year,1pct_min,100-year,1pct_plu,500-year
River Rch & RM= GUADALUPE TRIBUT,Reach-1,2666
     311     483     634     405     809    1614    1297
Boundary for River Rch & Prof#=GUADALUPE TRIBUT,Reach-1,1
Up Type=0
Dn Type=3
Dn Slope=0.005
Boundary for River Rch & Prof#=GUADALUPE TRIBUT,Reach-1,2
Up Type=0
Dn Type=3
Dn Slope=0.005
Boundary for River Rch & Prof#=GUADALUPE TRIBUT,Reach-1,3
Up Type=0
Dn Type=3
Dn Slope=0.005
Boundary for River Rch & Prof#=GUADALUPE TRIBUT,Reach-1,4
Up Type=0
Dn Type=3
Dn Slope=0.005
Boundary for River Rch & Prof#=GUADALUPE TRIBUT,Reach-1,5
Up Type=0
Dn Type=3
Dn Slope=0.005
Boundary for River Rch & Prof#=GUADALUPE TRIBUT,Reach-1,6
Up Type=0
Dn Type=3
Dn Slope=0.005
Boundary for River Rch & Prof#=GUADALUPE TRIBUT,Reach-1,7
Up Type=0
Dn Type=3
Dn Slope=0.005

--- GUADALUPE TRIBUTARY 23 2.g01 (geometry) ---

Geom Title=Existing Conditions

River Reach=GUADALUPE TRIBUT,Reach-1
Reach XY= 30
      2259875.00     13785175.00      2259919.32     13785127.36
      2259929.03     13785076.64      2259968.77     13785026.86
      2259978.53     13784983.49      2260051.96     13784948.65
      2260080.63     13784880.65      2260134.42     13784864.11
      2260272.63     13784730.55      2260366.65     13784721.81
      2260383.17     13784668.97      2260426.27     13784628.49
      2260569.06     13784622.73      2260626.60     13784578.85
      2260719.11     13784572.45      2260775.00     13784532.56
      2260835.44     13784573.63      2260969.14     13784572.94
      2261068.95     13784482.50      2261104.79     13784474.64
      2261185.50     13784523.76      2261419.07     13784527.24
      2261472.82     13784568.88      2261523.28     13784579.16
      2261572.81     13784618.95      2261623.37     13784629.44
      2261678.41     13784667.23      2261911.92     13784438.60
      2261970.08     13784419.67      2261975.00     13784375.00

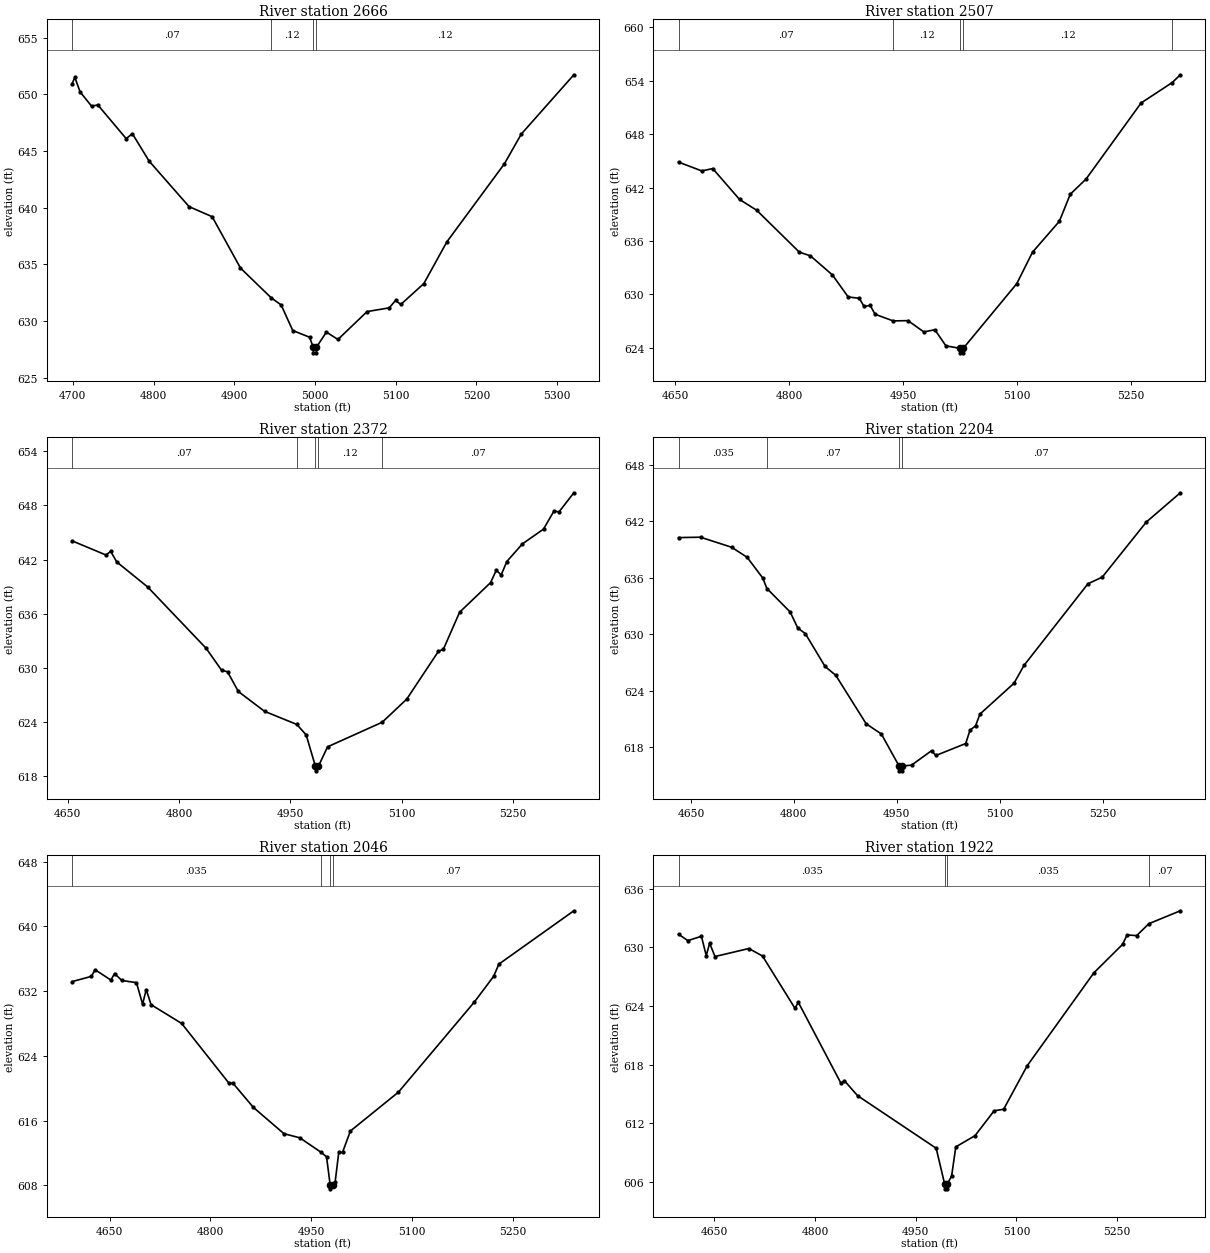
Type RM Length L Ch R = 1,2666,159,159,159
BEGIN DESCRIPTION:
GUADALUPE TRIBUTARY 23 210469
END DESCRIPTION:
XS GIS Cut Line= 2
      2260112.28     13785362.45      2259641.33     13784956.91
#Sta/Elev= 30
  4699.1  650.94  4702.5  651.50  4709.1  650.21  4723.3  648.96  4731.0  649.07
  4766.1  646.10  4773.8  646.53  4794.6  644.11  4844.0  640.10  4872.6  639.21
  4907.7  634.68  4945.5  632.07  4958.1  631.42  4972.4  629.17  4993.2  628.58
  4997.8  627.70  4998.1  627.20  5001.6  627.20  5001.8  627.70  5014.1  629.03
  5028.4  628.38  5064.5  630.84  5092.0  631.17  5099.7  631.82  5106.3  631.47
  5134.8  633.31  5163.3  636.99  5234.6  643.88  5255.5  646.50  5320.6  651.73
#Mann=4,-1,0
  4699.1    0.07       0  4945.5    0.12       0  4997.8    0.05       0
  5001.8    0.12       0
Bank Sta=4997.8,5001.8
Exp/Cntr=0.3,0.1

Type RM Length L Ch R = 1,2507,135,135,135
BEGIN DESCRIPTION:
GUADALUPE TRIBUTARY 23 210468
END DESCRIPTION:
XS GIS Cut Line= 2
      2260236.54     13785246.87      2259715.45     13784841.33
#Sta/Elev= 30
  4654.2  644.86  4684.7  643.87  4699.2  644.13  4734.5  640.66  4757.1  639.44
  4813.2  634.73  4827.7  634.32  4856.7  632.17  4877.5  629.69  4892.0  629.55
  4898.3  628.63  4906.4  628.74  4912.8  627.75  4936.7  627.00  4956.2  627.03
  4977.0  625.76  4991.5  626.01  5006.0  624.20  5024.8  623.91  5025.0  623.41
  5028.5  623.41  5028.8  623.91  5099.2  631.18  5120.0  634.73  5155.3  638.20
  5169.7  641.25  5190.5  642.96  5262.9  651.51  5303.9  653.81  5314.5  654.68
#Mann=5,-1,0
  4654.2    0.07       0  4936.7    0.12       0  5024.8    0.05       0
  5028.8    0.12       0  5303.9    0.07       0
Bank Sta=5024.8,5028.8
Exp/Cntr=0.3,0.1

Type RM Length L Ch R = 1,2372,168,168,168
BEGIN DESCRIPTION:
GUADALUPE TRIBUTARY 23 210467
END DESCRIPTION:
XS GIS Cut Line= 3
      2260260.53     13785222.89      2260049.04     13784950.35
      2259799.17     13784733.07
#Sta/Elev= 30
  4655.9  644.08  4701.6  642.51  4707.9  642.92  4716.1  641.74  4757.7  638.97
  4836.5  632.17  4857.3  629.74  4865.4  629.56  4879.9  627.38  4915.2  625.18
  4958.6  623.73  4971.3  622.57  4983.8  619.08  4984.1  618.58  4987.8  619.08
  5000.1  621.24  5073.8  623.97  5106.8  626.53  5149.6  631.84  5156.2  632.06
  5178.1  636.17  5219.8  639.45  5227.4  640.81  5234.1  640.31  5241.7  641.79
  5262.6  643.74  5291.1  645.38  5305.3  647.40  5311.9  647.28  5332.0  649.41
#Mann=5,-1,0
  4655.9    0.07       0  4958.6    0.12       0  4983.8    0.05       0
  4987.8    0.12       0  5073.8    0.07       0
Bank Sta=4983.8,4987.8
Exp/Cntr=0.3,0.1

Type RM Length L Ch R = 1,2204,158,158,158
BEGIN DESCRIPTION:
GUADALUPE TRIBUTARY 23 210466
END DESCRIPTION:
XS GIS Cut Line= 3
      2260332.47     13785161.81      2260192.95     13784869.67
      2259870.96     13784619.49
#Sta/Elev= 30
  4631.9  640.28  4664.0  640.32  4709.4  639.25  4732.0  638.18  4754.7  635.98
  4760.7  634.87  4794.6  632.38  4805.7  630.68  4816.8  630.07  4845.5  626.59
  4861.1  625.65  4905.4  620.50  4927.6  619.41  4953.5  616.00  4953.7  615.50
  4957.2  615.50  4957.5  616.00  4971.7  616.11  5000.7  617.64  5007.0  617.13
  5050.5  618.40  5056.8  619.81  5064.9  620.28  5071.3  621.53  5121.0  624.81
  5135.5  626.70  5228.7  635.37  5249.6  636.08  5313.8  641.93  5363.4  645.04
#Mann=4,-1,0
  4631.9   0.035       0  4760.7    0.07       0  4953.5    0.05       0
  4957.5    0.07       0
Bank Sta=4953.5,4957.5
Exp/Cntr=0.3,0.1

Type RM Length L Ch R = 1,2046,124,124,124
BEGIN DESCRIPTION:
GUADALUPE TRIBUTARY 23 210465
END DESCRIPTION:
XS GIS Cut Line= 3
      2260432.81     13785103.02      2260275.80     13784736.67
      2260009.88     13784512.16
#Sta/Elev= 30
  4594.2  633.18  4623.0  633.83  4628.4  634.65  4652.0  633.37  4657.4  634.18
  4668.2  633.32  4690.0  633.05  4699.1  630.40  4704.6  632.19  4711.7  630.33
  4757.2  628.01  4827.9  620.59  4833.3  620.64  4864.0  617.62  4909.5  614.37
  4933.1  613.86  4964.3  612.09  4972.8  611.52  4978.2  608.05  4978.4  607.55
  4982.2  608.05  4985.6  608.38  4991.0  612.06  4996.6  612.06  5008.3  614.70
  5079.8  619.51  5192.9  630.67  5221.5  633.84  5229.2  635.34  5340.8  641.94
#Mann=4,-1,0
  4594.2   0.035       0  4964.3    0.07       0  4978.2    0.05       0
  4982.2    0.07       0
Bank Sta=4978.2,4982.2
Exp/Cntr=0.3,0.1

Type RM Length L Ch R = 1,1922,126,126,126
BEGIN DESCRIPTION:
A19253
END DESCRIPTION:
XS GIS Cut Line= 4
      2260456.54     13785088.67      2260402.76     13784735.56
      2260361.53     13784679.99      2260146.42     13784441.57
#Sta/Elev= 30
  4596.6  631.34  4610.4  630.69  4630.7  631.13  4637.9  629.15  4642.9  630.42
  4650.9  629.06  4701.4  629.88  4721.7  629.11  4770.0  623.77  4775.1  624.37
  4838.7  616.08  4843.7  616.36  4863.3  614.83  4980.4  609.45  4993.0  605.80
  4993.3  605.30  4996.8  605.30  4997.0  605.80  5003.4  606.61  5009.6  609.59
  5038.3  610.74  5066.7  613.28  5080.9  613.44  5116.0  617.89  5215.4  627.40
  5258.0  630.30  5264.8  631.27  5279.0  631.20  5297.3  632.42  5344.1  633.74
#Mann=4,-1,0
  4596.6   0.035       0  4993.0   0.035       0  4997.0   0.035       0
  5297.3    0.07       0
Bank Sta=4993,4997
Exp/Cntr=0.3,0.1

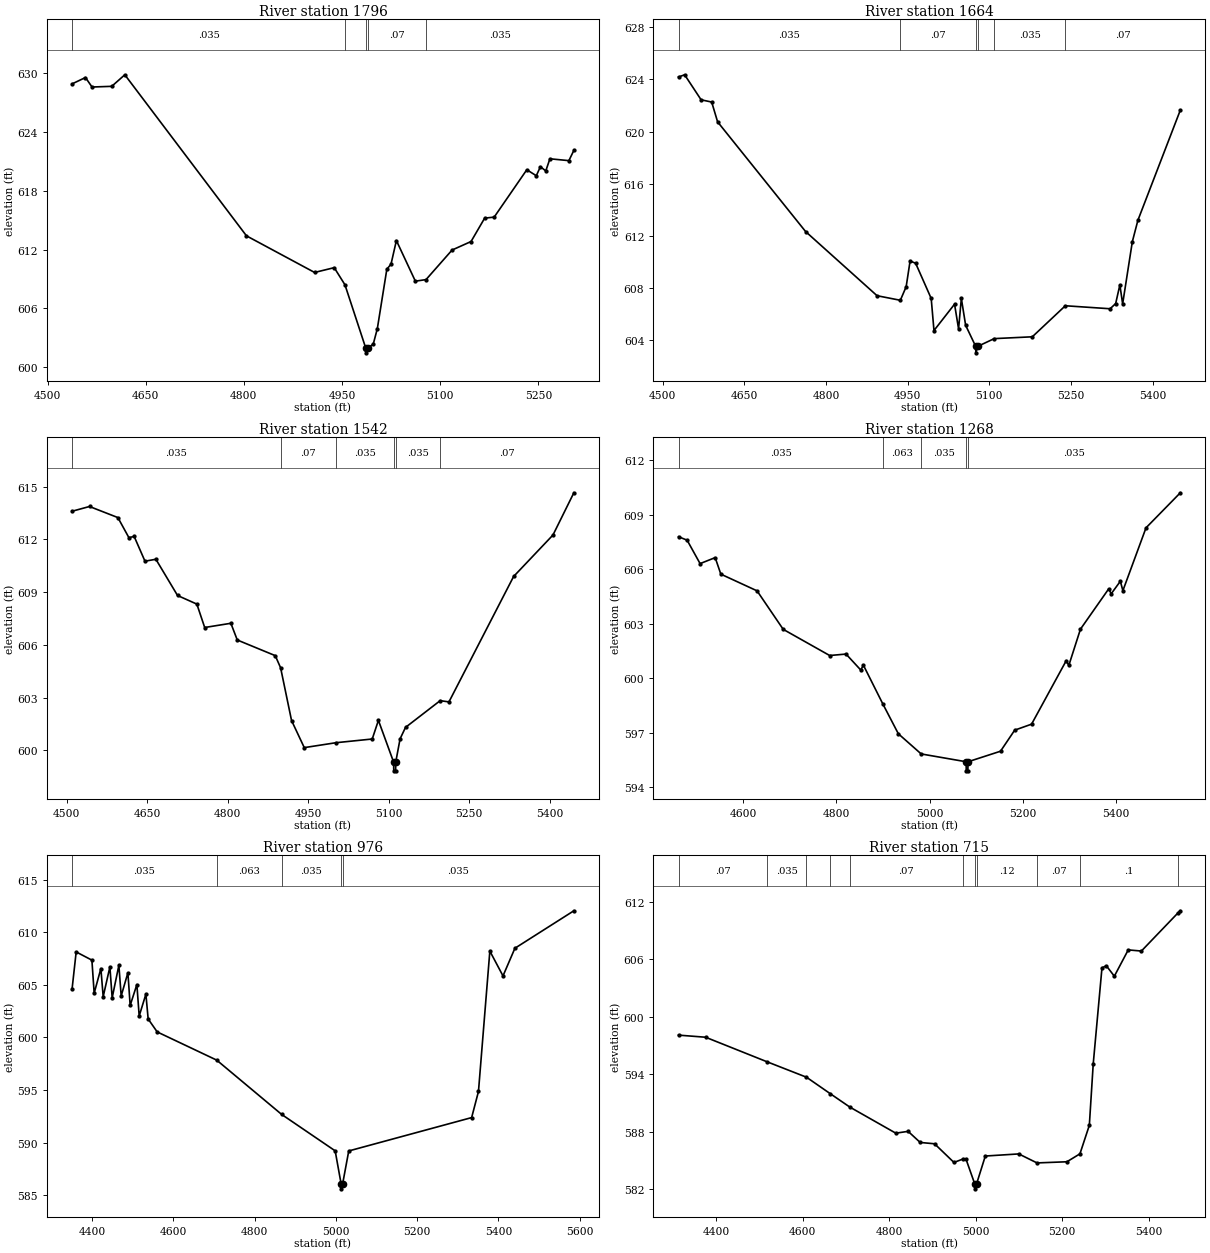
Type RM Length L Ch R = 1,1796,132,132,132
BEGIN DESCRIPTION:
GUADALUPE TRIBUTARY 23 210464
END DESCRIPTION:
XS GIS Cut Line= 3
      2260476.40     13785085.53      2260465.49     13784629.83
      2260275.79     13784383.43
#Sta/Elev= 30
  4537.5  628.92  4558.0  629.57  4568.0  628.60  4598.1  628.67  4618.1  629.85
  4804.0  613.40  4908.1  609.66  4938.1  610.15  4954.5  608.40  4986.2  601.95
  4986.4  601.45  4990.2  601.95  4997.8  602.35  5004.0  603.93  5018.5  609.99
  5024.9  610.51  5033.1  612.92  5062.1  608.77  5078.4  608.93  5118.2  611.95
  5147.2  612.82  5168.0  615.21  5182.5  615.31  5232.4  620.15  5246.9  619.54
  5253.2  620.46  5261.4  620.03  5267.7  621.27  5296.7  621.08  5304.3  622.13
#Mann=5,-1,0
  4537.5   0.035       0  4954.5    0.07       0  4986.2    0.05       0
  4990.2    0.07       0  5078.4   0.035       0
Bank Sta=4986.2,4990.2
Exp/Cntr=0.3,0.1

Type RM Length L Ch R = 1,1664,122,122,122
BEGIN DESCRIPTION:
A19252
END DESCRIPTION:
XS GIS Cut Line= 3
      2260540.80     13785076.12      2260599.95     13784662.07
      2260498.05     13784168.64
#Sta/Elev= 30
  4528.8  624.18  4540.0  624.35  4570.3  622.43  4589.7  622.26  4600.6  620.74
  4762.3  612.33  4893.6  607.41  4936.4  607.06  4947.1  608.10  4954.3  610.07
  4964.5  609.90  4993.1  607.20  4998.2  604.74  5036.0  606.76  5043.4  604.87
  5048.5  607.20  5056.4  605.14  5074.8  603.53  5075.1  603.03  5078.8  603.53
  5108.9  604.12  5178.9  604.26  5239.6  606.64  5321.9  606.41  5332.1  606.81
  5339.8  608.24  5344.9  606.78  5362.7  611.55  5372.9  613.19  5450.9  621.64
#Mann=6,-1,0
  4528.8   0.035       0  4936.4    0.07       0  5074.8    0.05       0
  5078.8    0.07       0  5108.9   0.035       0  5239.6    0.07       0
Bank Sta=5074.8,5078.8
Exp/Cntr=0.3,0.1

Type RM Length L Ch R = 1,1542,274,274,274
BEGIN DESCRIPTION:
GUADALUPE TRIBUTARY 23 210463
END DESCRIPTION:
XS GIS Cut Line= 2
      2260624.66     13785059.37      2260766.39     13784134.87
#Sta/Elev= 30
  4509.9  613.60  4542.4  613.87  4595.3  613.24  4615.8  612.10  4625.6  612.17
  4645.8  610.76  4666.1  610.87  4706.5  608.81  4742.5  608.32  4757.1  606.99
  4805.9  607.23  4817.8  606.28  4888.6  605.39  4898.6  604.70  4919.0  601.70
  4942.7  600.16  5002.0  600.44  5069.4  600.65  5080.9  601.71  5109.2  599.34
  5109.5  598.84  5113.0  598.84  5113.2  599.34  5121.3  600.66  5131.4  601.31
  5196.0  602.83  5212.4  602.76  5332.9  609.89  5406.3  612.25  5445.2  614.65
#Mann=6,-1,0
  4509.9   0.035       0  4898.6    0.07       0  5002.0   0.035       0
  5109.2    0.05       0  5113.2   0.035       0  5196.0    0.07       0
Bank Sta=5109.2,5113.2
Exp/Cntr=0.3,0.1

Type RM Length L Ch R = 1,1268,292,292,292
BEGIN DESCRIPTION:
GUADALUPE TRIBUTARY 23 210462
END DESCRIPTION:
XS GIS Cut Line= 3
      2260700.96     13785055.04      2260990.97     13784485.93
      2261143.58     13784076.06
#Sta/Elev= 30
  4461.7  607.80  4480.1  607.61  4507.9  606.32  4540.3  606.65  4552.4  605.74
  4630.1  604.82  4686.2  602.70  4785.8  601.26  4820.9  601.34  4852.5  600.46
  4858.1  600.73  4899.7  598.60  4933.1  596.95  4982.1  595.84  5078.5  595.41
  5078.7  594.91  5082.2  594.91  5082.5  595.41  5152.2  595.99  5182.6  597.15
  5218.8  597.48  5293.2  600.98  5298.6  600.71  5323.6  602.71  5384.2  604.93
  5389.6  604.66  5409.2  605.35  5414.6  604.83  5464.2  608.29  5537.8  610.22
#Mann=5,-1,0
  4461.7   0.035       0  4899.7   0.063       0  4982.1   0.035       0
  5078.5   0.035       0  5082.5   0.035       0
Bank Sta=5078.5,5082.5
Exp/Cntr=0.3,0.1

Type RM Length L Ch R = 1,976,261,261,261
BEGIN DESCRIPTION:
GUADALUPE TRIBUTARY 23 210461
END DESCRIPTION:
XS GIS Cut Line= 3
      2260886.31     13785100.78      2261165.40     13784560.06
      2261443.88     13783998.74
#Sta/Elev= 30
  4350.5  604.60  4360.6  608.13  4399.3  607.35  4404.9  604.21  4421.4  606.55
  4427.1  603.88  4443.6  606.71  4449.2  603.77  4465.7  606.86  4471.4  603.95
  4487.9  606.15  4493.5  603.05  4510.0  605.03  4515.7  602.04  4532.2  604.12
  4537.8  601.76  4560.0  600.53  4706.5  597.85  4866.4  592.69  4998.1  589.23
  5012.6  586.12  5012.9  585.62  5016.6  586.12  5031.5  589.22  5334.0  592.39
  5350.8  594.87  5378.8  608.21  5411.2  605.85  5440.5  608.48  5585.6  612.04
#Mann=5,-1,0
  4350.5   0.035       0  4706.5   0.063       0  4866.4   0.035       0
  5012.6   0.035       0  5016.6   0.035       0
Bank Sta=5012.6,5016.6
Exp/Cntr=0.3,0.1

Type RM Length L Ch R = 1,715,252,252,252
BEGIN DESCRIPTION:
GUADALUPE TRIBUTARY 23 210460
END DESCRIPTION:
XS GIS Cut Line= 3
      2261130.50     13785153.14      2261455.39     13784509.91
      2261522.97     13784076.06
#Sta/Elev= 30
  4313.5  598.08  4376.0  597.86  4517.7  595.30  4609.2  593.68  4664.1  591.96
  4709.3  590.56  4815.6  587.83  4844.1  588.02  4872.0  586.86  4905.2  586.72
  4950.0  584.77  4969.9  585.11  4977.9  585.11  4998.2  582.51  4998.5  582.01
  5002.2  582.51  5022.5  585.44  5099.8  585.66  5142.0  584.72  5211.1  584.84
  5241.2  585.67  5262.9  588.65  5271.9  595.07  5292.1  605.11  5302.2  605.33
  5320.7  604.24  5352.8  606.99  5383.2  606.87  5466.8  610.81  5473.2  611.08
#Mann=11,-1,0
  4313.5    0.07       0  4517.7   0.035       0  4609.2   0.063       0
  4664.1   0.035       0  4709.3    0.07       0  4969.9    0.12       0
  4998.2    0.05       0  5002.2    0.12       0  5142.0    0.07       0
  5241.2     0.1       0  5466.8   0.035       0
Bank Sta=4998.2,5002.2
Exp/Cntr=0.3,0.1

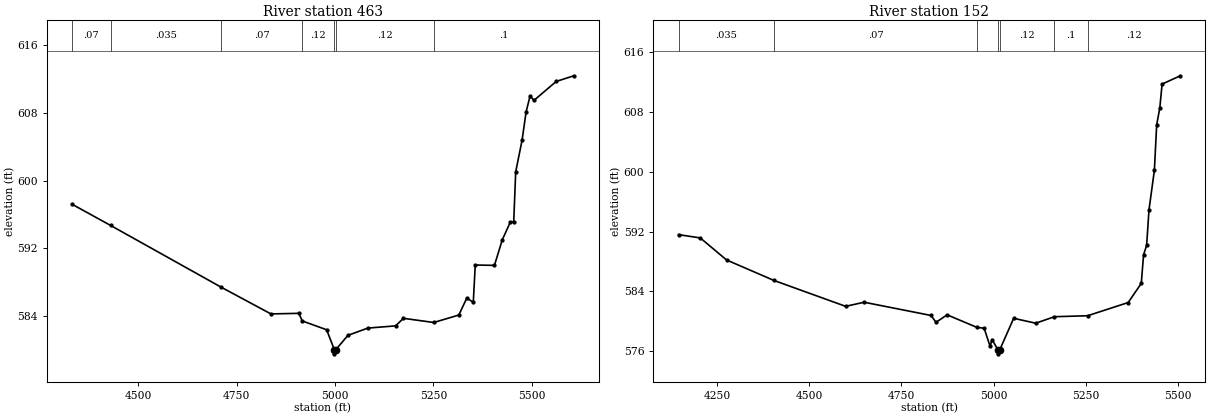
Type RM Length L Ch R = 1,463,311,311,311
BEGIN DESCRIPTION:
GUADALUPE TRIBUTARY 23 210459
END DESCRIPTION:
XS GIS Cut Line= 3
      2261193.73     13785137.87      2261662.52     13784647.28
      2261605.83     13784054.24
#Sta/Elev= 30
  4332.4  597.20  4430.3  594.70  4711.2  587.41  4837.4  584.26  4908.2  584.33
  4917.0  583.43  4978.9  582.39  4998.3  580.05  4998.5  579.55  5002.3  580.05
  5032.9  581.73  5083.6  582.59  5153.9  582.85  5174.0  583.74  5251.0  583.25
  5314.6  584.13  5334.7  586.12  5351.3  585.64  5356.3  590.03  5405.0  589.99
  5425.1  593.02  5445.2  595.08  5454.0  595.16  5459.0  601.02  5475.3  604.79
  5485.4  608.09  5495.4  609.96  5505.5  609.46  5561.8  611.69  5606.7  612.36
#Mann=7,-1,0
  4332.4    0.07       0  4430.3   0.035       0  4711.2    0.07       0
  4917.0    0.12       0  4998.3    0.05       0  5002.3    0.12       0
  5251.0     0.1       0
Bank Sta=4998.3,5002.3
Exp/Cntr=0.3,0.1

Type RM Length L Ch R = 1,152,0,0,0
BEGIN DESCRIPTION:
GUADALUPE TRIBUTARY 23 210458
END DESCRIPTION:
XS GIS Cut Line= 4
      2261350.76     13785063.71      2261867.48     13784677.80
      2261887.10     13784363.83      2261649.72     13784041.51
#Sta/Elev= 30
  4146.0  591.58  4204.9  591.14  4276.1  588.19  4404.8  585.44  4598.9  581.98
  4648.9  582.53  4830.1  580.76  4843.8  579.84  4873.9  580.84  4955.3  579.15
  4974.1  579.06  4990.4  576.61  4995.4  577.53  5012.2  576.12  5012.4  575.62
  5016.2  576.12  5054.2  580.38  5113.9  579.72  5164.7  580.59  5254.5  580.72
  5364.5  582.49  5400.0  585.05  5406.2  588.88  5414.5  590.15  5420.9  594.90
  5435.5  600.20  5441.7  606.27  5450.2  608.55  5456.4  611.74  5505.8  612.85
#Mann=7,-1,0
  4146.0   0.035       0  4404.8    0.07       0  4955.3    0.12       0
  5012.2    0.05       0  5016.2    0.12       0  5164.7     0.1       0
  5254.5    0.12       0
Bank Sta=5012.2,5016.2
Exp/Cntr=0.3,0.1

Chan Stop Cuts=-1