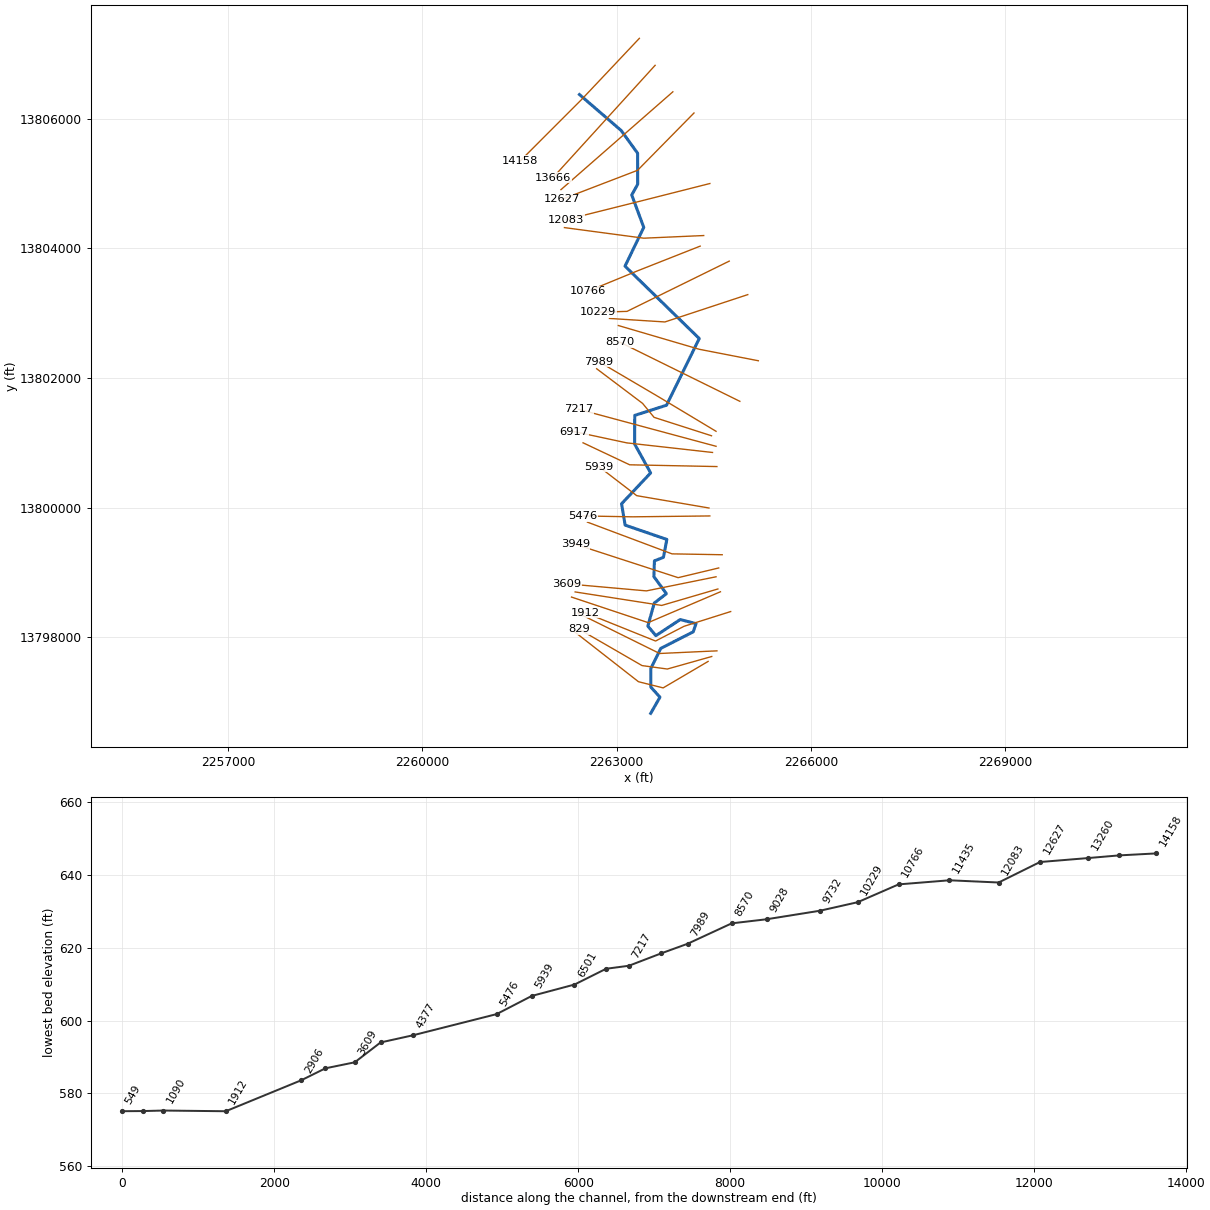
--- GUADALUPE TRIBUTARY 29 2.prj (project) ---

Proj Title=GUADALUPE TRIBUTARY 29 2 Base Level Engineering
Current Plan=p01
Default Exp/Contr=0.3,0.1
English Units
Geom File=g01
Flow File=f01
Plan File=p01
BEGIN DESCRIPTION:
GUADALUPE TRIBUTARY 29 2
END DESCRIPTION:

--- GUADALUPE TRIBUTARY 29 2.p01 (plan) ---

Plan Title=Multiple Run
Short Identifier=Multiple
Geom File=g01
Flow File=f01
Subcritical Flow
K Sum by GR= 0
Std Step Tol= 0.01
Critical Tol= 0.01
Num of Std Step Trials= 20
Max Error Tol= 0.3
Flow Tol Ratio= 0.001
Split Flow NTrial= 30
Split Flow Tol= 0.02
Split Flow Ratio= 0.02
Log Output Level= 0
Friction Slope Method= 1
Unsteady Friction Slope Method= 2
Unsteady Bridges Friction Slope Method= 1
Parabolic Critical Depth
Global Vel Dist=  1 , 1 , 1
Global Log Level= 0
CheckData=True
Encroach Param= -1, 0, 0, 0
BEGIN DESCRIPTION:
Multiple Run
END DESCRIPTION:

--- GUADALUPE TRIBUTARY 29 2.f01 (steady flow) ---

Flow Title=Multiple
Number of Profiles=7
Profile Names=10-year,25-year,50-year,1pct_min,100-year,1pct_plu,500-year
River Rch & RM= GUADALUPE TRIBUT,Reach-1,14158
     589     928    1225     781    1559    3110    2500
River Rch & RM= GUADALUPE TRIBUT,Reach-1,12627
     919    1489    2003    1301    2596    5179    4318
River Rch & RM= GUADALUPE TRIBUT,Reach-1,5476
    1336    2218    3036    2005    4000    7981    6878
Boundary for River Rch & Prof#=GUADALUPE TRIBUT,Reach-1,1
Up Type=0
Dn Type=3
Dn Slope=0.005
Boundary for River Rch & Prof#=GUADALUPE TRIBUT,Reach-1,2
Up Type=0
Dn Type=3
Dn Slope=0.005
Boundary for River Rch & Prof#=GUADALUPE TRIBUT,Reach-1,3
Up Type=0
Dn Type=3
Dn Slope=0.005
Boundary for River Rch & Prof#=GUADALUPE TRIBUT,Reach-1,4
Up Type=0
Dn Type=3
Dn Slope=0.005
Boundary for River Rch & Prof#=GUADALUPE TRIBUT,Reach-1,5
Up Type=0
Dn Type=3
Dn Slope=0.005
Boundary for River Rch & Prof#=GUADALUPE TRIBUT,Reach-1,6
Up Type=0
Dn Type=3
Dn Slope=0.005
Boundary for River Rch & Prof#=GUADALUPE TRIBUT,Reach-1,7
Up Type=0
Dn Type=3
Dn Slope=0.005

--- GUADALUPE TRIBUTARY 29 2.g01 (geometry) ---

Geom Title=Existing Conditions

River Reach=GUADALUPE TRIBUT,Reach-1
Reach XY= 30
      2262425.00     13806375.00      2263069.74     13805819.53
      2263322.94     13805469.15      2263324.49     13804990.21
      2263232.53     13804825.01      2263417.89     13804325.01
      2263128.46     13803726.50      2264274.63     13802609.73
      2263769.44     13801580.62      2263278.54     13801423.56
      2263277.26     13800980.94      2263524.06     13800535.49
      2263075.51     13800059.79      2263130.44     13799730.25
      2263774.34     13799509.17      2263721.62     13799233.15
      2263582.68     13799178.70      2263574.22     13798935.05
      2263767.42     13798671.66      2263580.42     13798527.67
      2263480.47     13798172.55      2263604.58     13798024.42
      2263980.85     13798272.94      2264224.83     13798209.92
      2264181.39     13798083.01      2263680.36     13797827.70
      2263526.05     13797514.57      2263527.06     13797230.85
      2263667.72     13797075.09      2263525.00     13796825.00

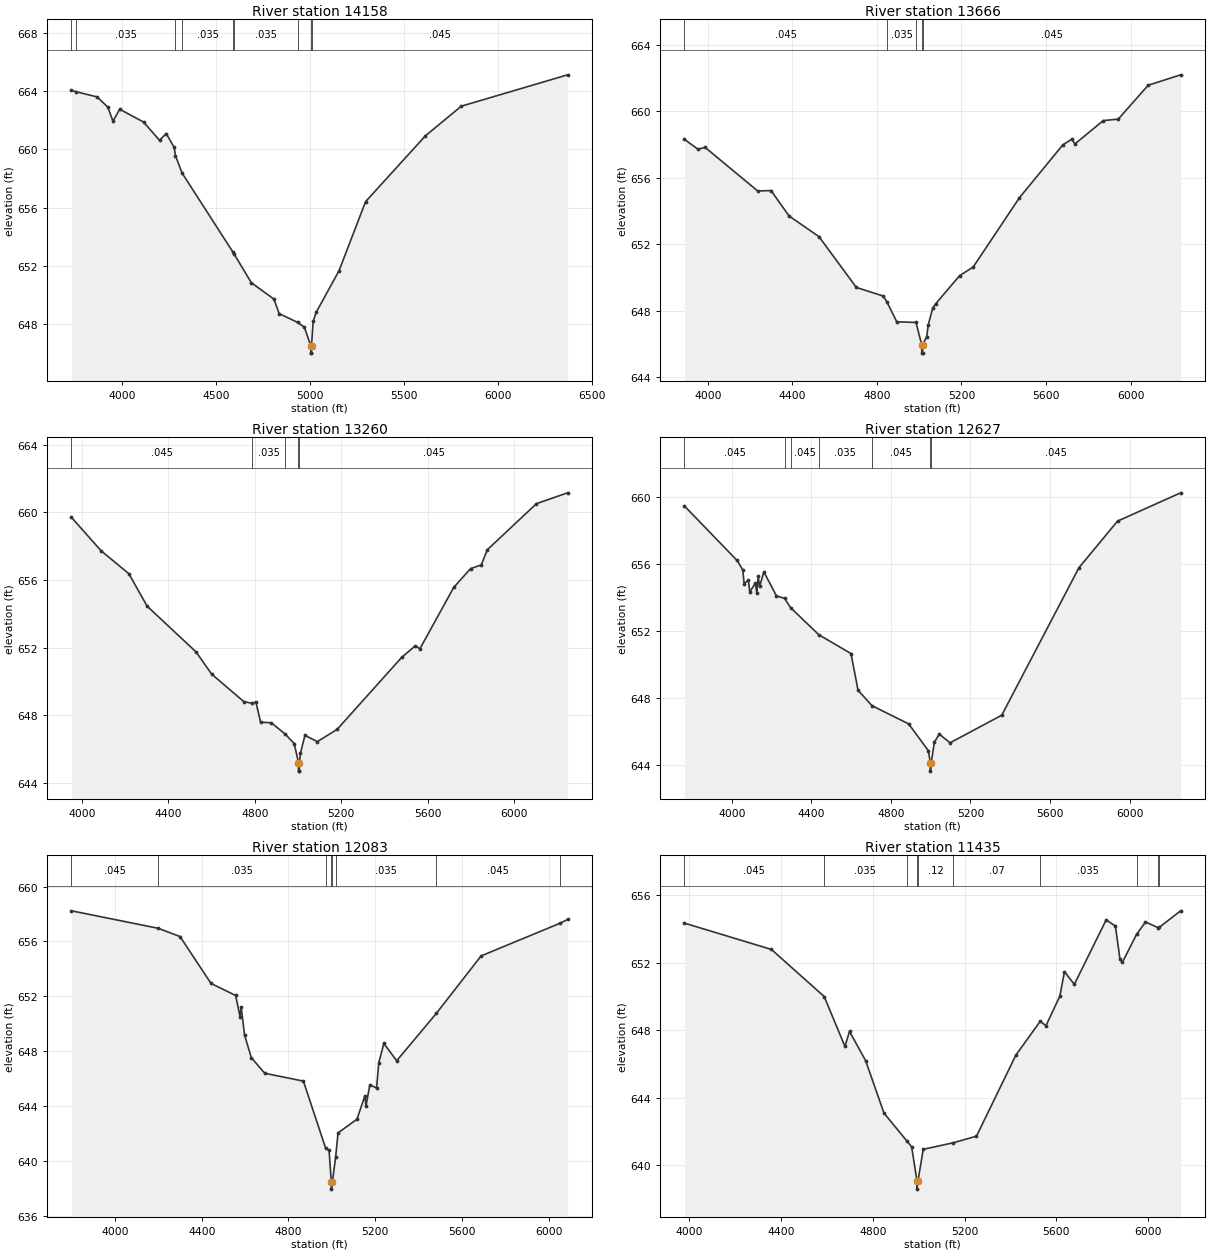
Type RM Length L Ch R = 1,14158,492,492,492
BEGIN DESCRIPTION:
GUADALUPE TRIBUTARY 29 210491
END DESCRIPTION:
XS GIS Cut Line= 3
      2263350.03     13807242.39      2262464.58     13806304.86
      2261509.89     13805350.17
#Sta/Elev= 30
  3731.7  664.08  3758.3  663.97  3867.7  663.62  3924.3  662.93  3952.6  661.95
  3988.2  662.77  4115.3  661.89  4200.2  660.63  4235.8  661.10  4278.3  660.14
  4285.2  659.57  4320.1  658.38  4590.7  652.94  4597.2  652.80  4688.5  650.83
  4808.7  649.70  4837.0  648.70  4934.4  648.10  4971.3  647.76  5004.9  646.48
  5005.2  645.98  5008.7  645.98  5008.9  646.48  5017.7  648.18  5035.0  648.82
  5155.2  651.65  5296.6  656.41  5614.8  660.94  5805.8  662.98  6371.4  665.14
#Mann=9,-1,0
  3731.7   0.045       0  3758.3   0.035       0  4285.2   0.045       0
  4320.1   0.035       0  4590.7   0.045       0  4597.2   0.035       0
  4934.4   0.045       0  5004.9   0.045       0  5008.9   0.045       0
Bank Sta=5004.9,5008.9
Exp/Cntr=0.3,0.1

Type RM Length L Ch R = 1,13666,406,406,406
BEGIN DESCRIPTION:
GUADALUPE TRIBUTARY 29 210490
END DESCRIPTION:
XS GIS Cut Line= 2
      2263593.09     13806825.73      2262013.39     13805089.80
#Sta/Elev= 30
  3889.7  658.32  3952.6  657.73  3987.8  657.83  4235.7  655.21  4299.3  655.23
  4384.4  653.70  4526.2  652.45  4702.7  649.39  4830.4  648.87  4848.4  648.49
  4893.9  647.32  4984.9  647.28  5012.1  645.93  5012.3  645.43  5015.9  645.43
  5016.2  645.93  5035.8  646.43  5042.5  647.11  5064.1  648.15  5078.3  648.41
  5191.2  650.10  5255.4  650.62  5474.3  654.80  5679.7  657.99  5722.3  658.33
  5736.5  658.04  5870.9  659.45  5941.9  659.54  6083.1  661.58  6236.8  662.21
#Mann=5,-1,0
  3889.7   0.045       0  4848.4   0.035       0  4984.9   0.045       0
  5012.1   0.045       0  5016.2   0.045       0
Bank Sta=5012.1,5016.2
Exp/Cntr=0.3,0.1

Type RM Length L Ch R = 1,13260,633,633,633
BEGIN DESCRIPTION:
GUADALUPE TRIBUTARY 29 210489
END DESCRIPTION:
XS GIS Cut Line= 2
      2263867.09     13806417.06      2262139.46     13804907.09
#Sta/Elev= 30
  3952.6  659.70  4089.9  657.72  4218.0  656.37  4302.5  654.45  4529.3  651.74
  4600.5  650.44  4749.6  648.81  4787.6  648.71  4805.6  648.78  4827.4  647.59
  4876.7  647.56  4942.0  646.88  4983.1  646.32  5002.4  645.20  5002.7  644.70
  5006.4  644.70  5006.7  645.20  5011.5  645.75  5032.4  646.82  5089.4  646.44
  5181.4  647.17  5479.5  651.42  5543.1  652.11  5564.0  651.93  5720.6  655.56
  5798.4  656.67  5847.8  656.89  5876.2  657.79  6103.1  660.51  6247.1  661.15
#Mann=5,-1,0
  3952.6   0.045       0  4787.6   0.035       0  4942.0   0.045       0
  5002.4   0.045       0  5006.7   0.045       0
Bank Sta=5002.4,5006.7
Exp/Cntr=0.3,0.1

Type RM Length L Ch R = 1,12627,544,544,544
BEGIN DESCRIPTION:
GUADALUPE TRIBUTARY 29 210488
END DESCRIPTION:
XS GIS Cut Line= 3
      2264193.67     13806090.49      2263322.78     13805205.99
      2262152.56     13804756.95
#Sta/Elev= 30
  3761.9  659.44  4026.5  656.19  4054.7  655.63  4061.9  654.81  4083.0  655.01
  4090.2  654.31  4118.4  654.84  4125.5  654.23  4132.6  655.24  4139.6  654.64
  4160.9  655.51  4224.5  654.07  4264.8  653.93  4295.7  653.37  4436.8  651.76
  4599.2  650.63  4634.6  648.44  4704.5  647.52  4889.2  646.43  4988.2  644.83
  4998.1  644.11  4998.4  643.61  5002.6  644.11  5018.4  645.34  5043.1  645.82
  5097.2  645.30  5357.2  646.95  5745.4  655.76  5939.5  658.54  6256.6  660.23
#Mann=7,-1,0
  3761.9   0.045       0  4264.8   0.035       0  4295.7   0.045       0
  4436.8   0.035       0  4704.5   0.045       0  4998.1   0.045       0
  5002.6   0.045       0
Bank Sta=4998.1,5002.6
Exp/Cntr=0.3,0.1

Type RM Length L Ch R = 1,12083,648,648,648
BEGIN DESCRIPTION:
GUADALUPE TRIBUTARY 29 210487
END DESCRIPTION:
XS GIS Cut Line= 3
      2264438.63     13805001.88      2263363.61     13804729.73
      2262220.62     13804443.98
#Sta/Elev= 30
  3799.6  658.23  4199.5  656.96  4299.9  656.36  4442.9  652.95  4556.4  652.07
  4576.7  650.53  4581.8  651.23  4597.6  649.19  4628.6  647.55  4690.5  646.41
  4868.8  645.84  4971.3  640.96  4987.1  640.80  4997.5  638.48  4997.9  637.98
  5002.2  638.48  5017.3  640.30  5028.4  642.07  5116.0  643.07  5152.1  644.77
  5157.2  644.01  5175.1  645.58  5206.0  645.33  5216.3  647.18  5239.7  648.58
  5298.8  647.32  5481.7  650.77  5688.1  654.95  6049.6  657.31  6086.7  657.60
#Mann=8,-1,0
  3799.6   0.045       0  4199.5   0.035       0  4971.3    0.07       0
  4997.5    0.05       0  5002.2    0.07       0  5017.3   0.035       0
  5481.7   0.045       0  6049.6   0.035       0
Bank Sta=4997.5,5002.2
Exp/Cntr=0.3,0.1

Type RM Length L Ch R = 1,11435,669,669,669
BEGIN DESCRIPTION:
GUADALUPE TRIBUTARY 29 210486
END DESCRIPTION:
XS GIS Cut Line= 3
      2264343.39     13804199.04      2263418.04     13804158.21
      2262193.33     13804321.51
#Sta/Elev= 30
  3979.6  654.36  4358.4  652.80  4588.3  650.01  4678.7  647.05  4698.7  647.94
  4768.8  646.21  4848.8  643.10  4947.5  641.46  4969.4  641.10  4992.5  639.09
  4992.8  638.59  4997.2  639.09  5019.9  640.95  5151.2  641.34  5251.9  641.73
  5423.4  646.53  5529.6  648.54  5554.6  648.28  5615.1  650.03  5635.3  651.48
  5678.3  650.73  5816.9  654.55  5857.2  654.19  5877.4  652.21  5887.5  652.03
  5949.3  653.69  5988.4  654.43  6041.7  654.10  6049.1  654.12  6141.4  655.09
#Mann=10,-1,0
  3979.6   0.045       0  4588.3   0.035       0  4947.5    0.12       0
  4992.5    0.05       0  4997.2    0.12       0  5151.2    0.07       0
  5529.6   0.035       0  5949.3   0.045       0  6041.7   0.035       0
  6049.1   0.045       0
Bank Sta=4992.5,4997.2
Exp/Cntr=0.3,0.1

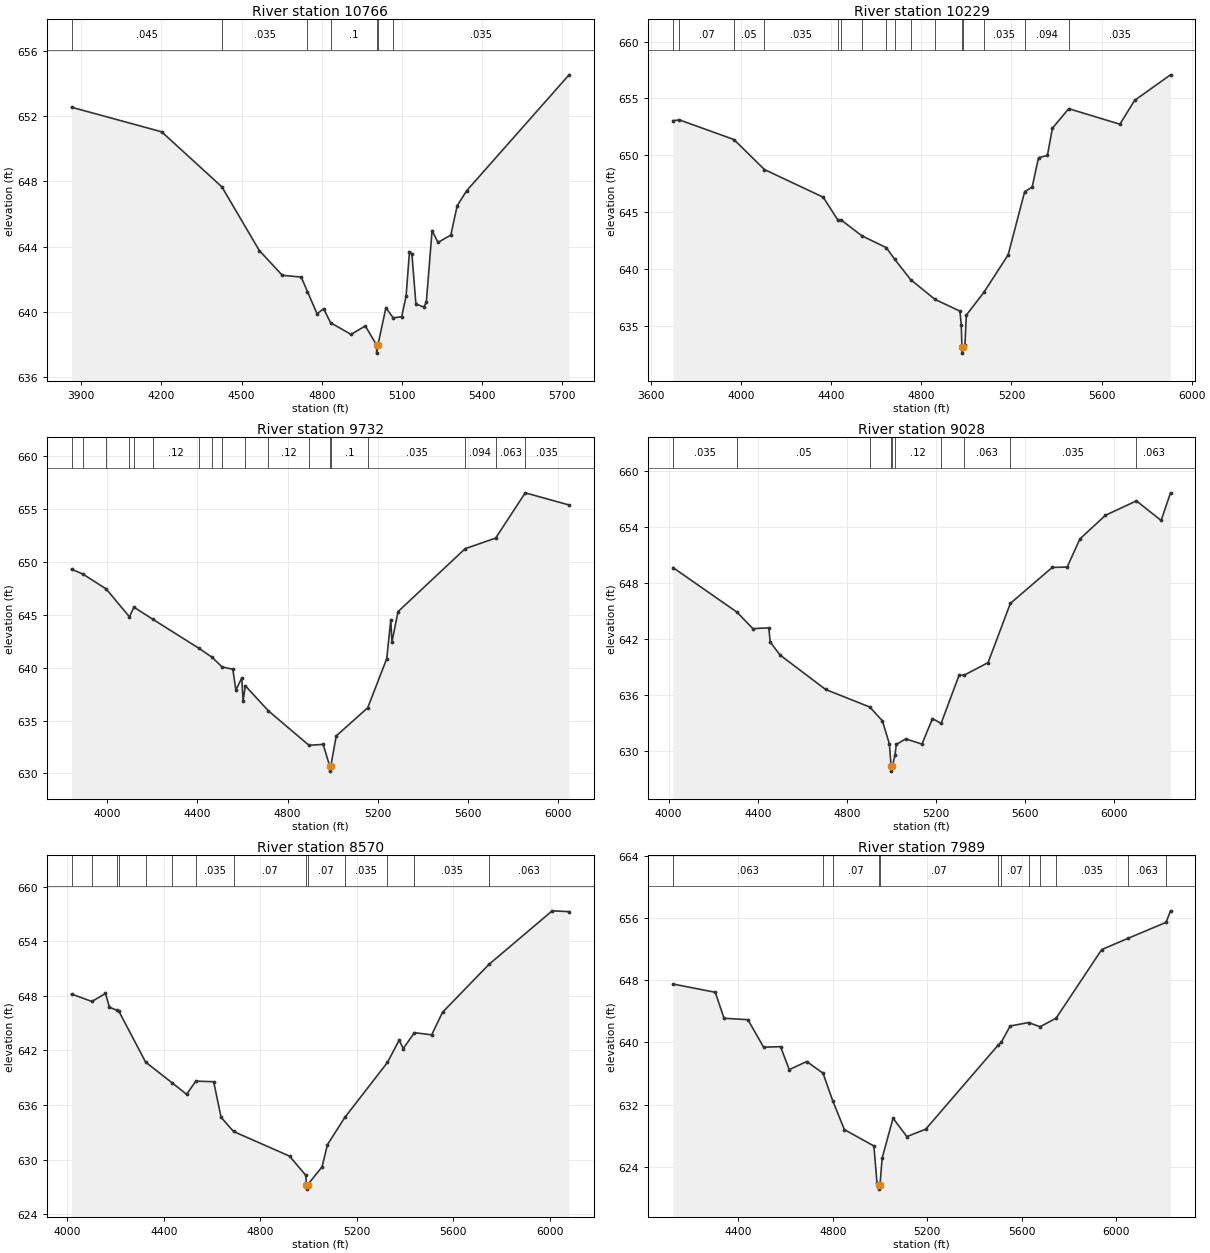
Type RM Length L Ch R = 1,10766,537,537,537
BEGIN DESCRIPTION:
GUADALUPE TRIBUTARY 29 210485
END DESCRIPTION:
XS GIS Cut Line= 3
      2264288.89     13804035.73      2263322.78     13803654.73
      2262560.77     13803341.76
#Sta/Elev= 30
  3863.5  652.56  4200.9  651.05  4426.3  647.67  4566.4  643.76  4652.4  642.24
  4723.2  642.13  4746.6  641.24  4782.7  639.87  4807.1  640.19  4832.9  639.33
  4909.8  638.61  4963.1  639.13  5005.2  637.96  5005.6  637.46  5010.3  637.96
  5040.2  640.25  5067.2  639.63  5099.2  639.69  5115.8  640.97  5128.5  643.70
  5137.5  643.56  5152.5  640.48  5181.9  640.29  5191.5  640.58  5213.1  644.99
  5235.2  644.26  5283.2  644.71  5307.2  646.52  5342.9  647.44  5725.8  654.55
#Mann=7,-1,0
  3863.5   0.045       0  4426.3   0.035       0  4746.6    0.07       0
  4832.9     0.1       0  5005.2    0.05       0  5010.3     0.1       0
  5067.2   0.035       0
Bank Sta=5005.2,5010.3
Exp/Cntr=0.3,0.1

Type RM Length L Ch R = 1,10229,497,497,497
BEGIN DESCRIPTION:
GUADALUPE TRIBUTARY 29 210484
END DESCRIPTION:
XS GIS Cut Line= 3
      2264737.93     13803804.40      2263159.49     13803028.79
      2262710.41     13803015.18
#Sta/Elev= 30
  3698.1  653.04  3726.7  653.11  3968.8  651.38  4103.9  648.74  4365.0  646.30
  4428.4  644.33  4444.1  644.30  4536.6  642.90  4644.8  641.86  4681.6  640.85
  4752.9  639.04  4861.1  637.30  4971.6  636.27  4977.5  635.08  4980.5  633.07
  4980.9  632.57  4985.7  633.07  4993.8  633.31  5000.0  635.92  5077.4  637.91
  5185.4  641.22  5258.9  646.79  5292.2  647.20  5320.3  649.78  5359.7  649.98
  5382.1  652.38  5454.4  654.10  5681.4  652.73  5746.7  654.83  5906.1  657.08
#Mann=16,-1,0
  3698.1    0.05       0  3726.7    0.07       0  3968.8    0.05       0
  4103.9   0.035       0  4428.4    0.07       0  4444.1    0.05       0
  4536.6   0.035       0  4644.8    0.07       0  4681.6   0.035       0
  4752.9    0.07       0  4861.1     0.1       0  4980.5    0.05       0
  4985.7     0.1       0  5077.4   0.035       0  5258.9   0.094       0
  5454.4   0.035       0
Bank Sta=4980.5,4985.7
Exp/Cntr=0.3,0.1

Type RM Length L Ch R = 1,9732,704,704,704
BEGIN DESCRIPTION:
GUADALUPE TRIBUTARY 29 210483
END DESCRIPTION:
XS GIS Cut Line= 3
      2265023.70     13803287.32      2263744.62     13802865.50
      2262888.68     13802919.84
#Sta/Elev= 30
  3842.5  649.31  3893.5  648.84  3996.2  647.44  4099.0  644.81  4118.9  645.72
  4201.7  644.59  4407.1  641.83  4464.2  641.00  4509.8  640.07  4557.2  639.85
  4570.6  637.89  4597.1  639.04  4602.4  636.83  4612.5  638.29  4715.2  635.91
  4894.8  632.66  4957.3  632.75  4986.2  630.72  4986.6  630.22  4991.5  630.72
  5015.3  633.55  5154.9  636.21  5239.1  640.85  5257.2  644.55  5262.2  642.41
  5289.2  645.30  5586.6  651.25  5721.7  652.25  5852.9  656.53  6047.0  655.38
#Mann=18,-1,0
  3842.5    0.07       0  3893.5    0.05       0  3996.2    0.07       0
  4099.0    0.05       0  4118.9    0.07       0  4201.7    0.12       0
  4407.1    0.07       0  4464.2   0.035       0  4509.8    0.07       0
  4612.5   0.035       0  4715.2    0.12       0  4894.8     0.1       0
  4986.2    0.05       0  4991.5     0.1       0  5154.9   0.035       0
  5586.6   0.094       0  5721.7   0.063       0  5852.9   0.035       0
Bank Sta=4986.2,4991.5
Exp/Cntr=0.3,0.1

Type RM Length L Ch R = 1,9028,458,458,458
BEGIN DESCRIPTION:
GUADALUPE TRIBUTARY 29 210482
END DESCRIPTION:
XS GIS Cut Line= 3
      2265186.98     13802266.78      2264275.31     13802443.67
      2263025.20     13802810.55
#Sta/Elev= 30
  4019.8  649.63  4307.0  644.86  4378.3  643.10  4449.6  643.19  4455.7  641.67
  4500.6  640.27  4704.3  636.60  4902.7  634.72  4959.2  633.24  4990.5  630.77
  4998.2  628.37  4998.6  627.87  5003.7  628.37  5015.2  629.55  5021.7  630.72
  5063.4  631.32  5136.4  630.76  5183.7  633.49  5222.3  632.97  5303.1  638.13
  5325.9  638.13  5433.0  639.47  5533.0  645.80  5721.0  649.65  5787.7  649.68
  5845.1  652.70  5959.7  655.22  6098.3  656.76  6209.2  654.67  6251.3  657.62
#Mann=10,-1,0
  4019.8   0.035       0  4307.0    0.05       0  4902.7     0.1       0
  4998.2    0.05       0  5003.7     0.1       0  5015.2    0.12       0
  5222.3   0.035       0  5325.9   0.063       0  5533.0   0.035       0
  6098.3   0.063       0
Bank Sta=4998.2,5003.7
Exp/Cntr=0.3,0.1

Type RM Length L Ch R = 1,8570,581,581,581
BEGIN DESCRIPTION:
GUADALUPE TRIBUTARY 29 210481
END DESCRIPTION:
XS GIS Cut Line= 2
      2264901.28     13801640.81      2263050.67     13802552.51
#Sta/Elev= 30
  4017.5  648.21  4101.8  647.39  4158.3  648.27  4174.5  646.76  4205.1  646.43
  4213.3  646.34  4324.7  640.72  4436.1  638.41  4494.6  637.18  4532.9  638.63
  4606.9  638.56  4637.6  634.65  4689.2  633.09  4921.3  630.38  4988.7  628.28
  4991.5  627.25  4992.0  626.75  4997.1  627.25  5056.1  629.19  5078.6  631.64
  5150.5  634.63  5327.6  640.69  5376.1  643.14  5393.0  642.21  5439.1  643.96
  5510.9  643.72  5555.8  646.20  5748.0  651.46  6010.6  657.36  6080.5  657.27
#Mann=14,-1,0
  4017.5   0.035       0  4101.8   0.063       0  4205.1   0.035       0
  4213.3   0.063       0  4324.7   0.094       0  4436.1   0.063       0
  4532.9   0.035       0  4689.2    0.07       0  4991.5    0.05       0
  4997.1    0.07       0  5150.5   0.035       0  5327.6   0.063       0
  5439.1   0.035       0  5748.0   0.063       0
Bank Sta=4991.5,4997.1
Exp/Cntr=0.3,0.1

Type RM Length L Ch R = 1,7989,348,348,348
BEGIN DESCRIPTION:
GUADALUPE TRIBUTARY 29 210480
END DESCRIPTION:
XS GIS Cut Line= 3
      2264533.88     13801178.15      2263649.37     13801708.86
      2262724.09     13802253.14
#Sta/Elev= 30
  4124.0  647.49  4303.0  646.43  4339.9  643.09  4441.0  642.91  4507.5  639.37
  4579.0  639.44  4615.9  636.49  4689.8  637.53  4758.8  636.04  4799.4  632.52
  4849.2  628.78  4974.0  626.68  4987.2  621.93  4994.0  621.63  4994.5  621.13
  4999.7  621.63  5009.0  625.13  5055.2  630.25  5113.5  627.88  5193.4  628.84
  5500.0  639.65  5512.3  639.98  5550.7  642.10  5628.6  642.54  5677.2  642.00
  5744.9  643.10  5937.9  651.92  6050.5  653.38  6210.2  655.42  6229.0  656.90
#Mann=12,-1,0
  4124.0   0.063       0  4758.8   0.035       0  4799.4    0.07       0
  4994.0    0.05       0  4999.7    0.07       0  5500.0   0.035       0
  5512.3    0.07       0  5628.6   0.035       0  5677.2    0.07       0
  5744.9   0.035       0  6050.5   0.063       0  6210.2   0.035       0
Bank Sta=4994,4999.7
Exp/Cntr=0.3,0.1

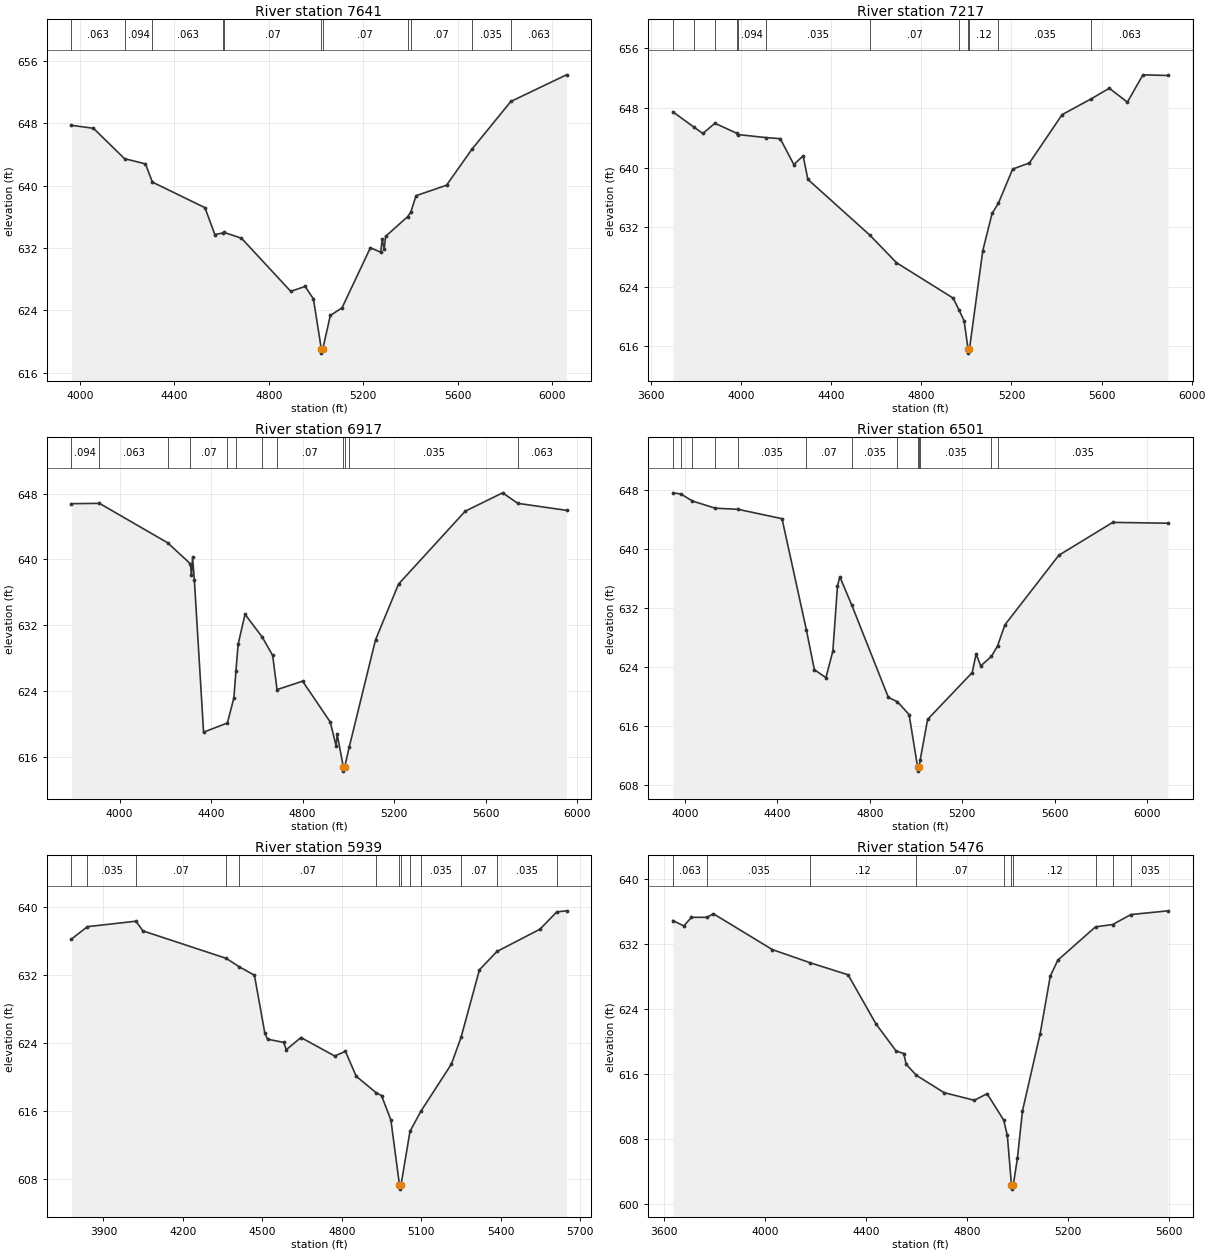
Type RM Length L Ch R = 1,7641,424,424,424
BEGIN DESCRIPTION:
A19322
END DESCRIPTION:
XS GIS Cut Line= 4
      2264463.86     13801109.19      2263577.21     13801393.37
      2263399.12     13801609.35      2262690.58     13802143.60
#Sta/Elev= 30
  3963.4  647.73  4056.7  647.35  4188.5  643.45  4277.2  642.78  4306.5  640.44
  4529.3  637.16  4571.3  633.71  4605.5  633.91  4609.4  633.99  4684.2  633.24
  4893.0  626.42  4953.9  627.05  4989.1  625.45  5022.8  618.99  5023.2  618.49
  5028.5  618.99  5060.8  623.33  5110.3  624.30  5230.6  632.02  5274.3  631.44
  5280.6  633.10  5288.9  631.82  5295.2  633.48  5388.8  636.02  5401.5  636.56
  5424.2  638.70  5553.3  640.04  5660.7  644.65  5825.7  650.79  6061.8  654.21
#Mann=11,-1,0
  3963.4   0.063       0  4188.5   0.094       0  4306.5   0.063       0
  4605.5   0.035       0  4609.4    0.07       0  5022.8    0.05       0
  5028.5    0.07       0  5388.8   0.035       0  5401.5    0.07       0
  5660.7   0.035       0  5825.7   0.063       0
Bank Sta=5022.8,5028.5
Exp/Cntr=0.3,0.1

Type RM Length L Ch R = 1,7217,300,300,300
BEGIN DESCRIPTION:
GUADALUPE TRIBUTARY 29 210479
END DESCRIPTION:
XS GIS Cut Line= 2
      2264533.84     13800946.84      2262411.12     13801518.34
#Sta/Elev= 30
  3696.3  647.49  3791.1  645.40  3829.7  644.58  3883.1  645.95  3980.5  644.60
  3985.9  644.43  4108.0  644.03  4173.3  643.88  4233.6  640.40  4275.0  641.58
  4295.7  638.42  4570.6  630.94  4689.3  627.23  4941.2  622.47  4967.8  620.83
  4989.6  619.44  5007.4  615.59  5007.9  615.09  5013.2  615.59  5072.5  628.84
  5113.9  633.85  5141.5  635.19  5205.2  639.80  5279.6  640.62  5424.6  647.10
  5554.7  649.24  5634.3  650.65  5714.5  648.78  5783.7  652.45  5894.6  652.36
#Mann=12,-1,0
  3696.3   0.094       0  3791.1   0.063       0  3883.1   0.094       0
  3980.5   0.063       0  3985.9   0.094       0  4108.0   0.035       0
  4570.6    0.07       0  4967.8    0.12       0  5007.4    0.05       0
  5013.2    0.12       0  5141.5   0.035       0  5554.7   0.063       0
Bank Sta=5007.4,5013.2
Exp/Cntr=0.3,0.1

Type RM Length L Ch R = 1,6917,416,416,416
BEGIN DESCRIPTION:
A19321
END DESCRIPTION:
XS GIS Cut Line= 3
      2264479.07     13800851.51      2263156.61     13800999.30
      2262341.93     13801173.60
#Sta/Elev= 30
  3789.6  646.78  3912.1  646.82  4210.4  642.02  4309.9  639.46  4314.1  638.05
  4319.1  640.25  4327.0  637.47  4367.2  619.00  4471.3  620.11  4499.7  623.18
  4508.7  626.45  4518.2  629.69  4548.4  633.33  4624.0  630.54  4669.1  628.33
  4688.3  624.17  4799.9  625.20  4920.7  620.24  4946.2  617.36  4951.2  618.73
  4978.1  614.76  4978.6  614.26  4983.9  614.76  5003.4  617.14  5118.6  630.22
  5219.2  637.00  5510.8  645.87  5674.2  648.10  5740.6  646.82  5953.4  645.97
#Mann=12,-1,0
  3789.6   0.094       0  3912.1   0.063       0  4210.4   0.035       0
  4309.9    0.07       0  4471.3   0.035       0  4508.7    0.07       0
  4624.0   0.035       0  4688.3    0.07       0  4978.1    0.05       0
  4983.9    0.07       0  5003.4   0.035       0  5740.6   0.063       0
Bank Sta=4978.1,4983.9
Exp/Cntr=0.3,0.1

Type RM Length L Ch R = 1,6501,562,562,562
BEGIN DESCRIPTION:
GUADALUPE TRIBUTARY 29 210478
END DESCRIPTION:
XS GIS Cut Line= 3
      2264547.47     13800633.87      2263200.32     13800661.08
      2262480.87     13801000.44
#Sta/Elev= 30
  3947.9  647.58  3983.1  647.42  4032.7  646.47  4131.3  645.50  4229.9  645.35
  4420.5  644.08  4525.6  629.08  4560.5  623.65  4610.5  622.57  4640.5  626.16
  4660.5  634.95  4670.5  636.23  4722.8  632.36  4880.6  619.91  4919.9  619.31
  4970.6  617.57  5007.6  610.42  5008.1  609.92  5013.5  610.42  5018.5  611.43
  5050.6  616.92  5243.7  623.26  5260.6  625.77  5280.6  624.16  5327.0  625.45
  5353.3  626.86  5385.3  629.72  5618.6  639.13  5851.9  643.58  6090.8  643.47
#Mann=13,-1,0
  3947.9   0.045       0  3983.1   0.094       0  4032.7   0.063       0
  4131.3   0.045       0  4229.9   0.035       0  4525.6    0.07       0
  4722.8   0.035       0  4919.9    0.07       0  5007.6    0.05       0
  5013.5    0.07       0  5018.5   0.035       0  5327.0    0.07       0
  5353.3   0.035       0
Bank Sta=5007.6,5013.5
Exp/Cntr=0.3,0.1

Type RM Length L Ch R = 1,5939,463,463,463
BEGIN DESCRIPTION:
GUADALUPE TRIBUTARY 29 210477
END DESCRIPTION:
XS GIS Cut Line= 3
      2264425.03     13799994.31      2263309.18     13800184.82
      2262724.03     13800633.88
#Sta/Elev= 30
  3779.0  636.18  3839.6  637.64  4022.5  638.28  4049.2  637.14  4363.9  633.91
  4413.6  632.91  4470.2  631.93  4509.5  625.09  4519.6  624.42  4580.3  624.03
  4590.6  623.18  4645.6  624.61  4773.2  622.44  4813.8  622.98  4854.4  620.06
  4930.5  618.10  4950.1  617.79  4985.4  614.91  5017.8  607.29  5018.3  606.79
  5023.7  607.29  5057.5  613.58  5098.8  615.95  5213.8  621.48  5250.3  624.62
  5319.8  632.57  5385.9  634.72  5548.3  637.34  5612.1  639.38  5648.6  639.50
#Mann=13,-1,0
  3779.0   0.063       0  3839.6   0.035       0  4022.5    0.07       0
  4363.9   0.035       0  4413.6    0.07       0  4930.5    0.12       0
  5017.8    0.05       0  5023.7    0.12       0  5057.5    0.07       0
  5098.8   0.035       0  5250.3    0.07       0  5385.9   0.035       0
  5612.1    0.07       0
Bank Sta=5017.8,5023.7
Exp/Cntr=0.3,0.1

Type RM Length L Ch R = 1,5476,1099,1099,1099
BEGIN DESCRIPTION:
GUADALUPE TRIBUTARY 29 210476
END DESCRIPTION:
XS GIS Cut Line= 3
      2264438.57     13799871.85      2263241.14     13799858.24
      2262479.57     13799871.84
#Sta/Elev= 30
  3635.9  634.86  3679.5  634.20  3709.5  635.26  3771.4  635.26  3796.4  635.70
  4029.5  631.29  4179.9  629.66  4329.5  628.18  4439.5  622.15  4519.5  618.80
  4549.5  618.49  4559.5  617.16  4599.9  615.80  4709.5  613.67  4829.0  612.73
  4879.6  613.54  4945.2  610.29  4959.6  608.40  4976.0  602.29  4976.5  601.79
  4983.1  602.29  4999.6  605.61  5019.6  611.44  5089.6  620.95  5129.6  628.03
  5159.6  629.99  5308.6  634.09  5376.2  634.37  5448.5  635.60  5595.1  636.06
#Mann=10,-1,0
  3635.9   0.063       0  3771.4   0.035       0  4179.9    0.12       0
  4599.9    0.07       0  4945.2    0.12       0  4976.0    0.05       0
  4983.1    0.12       0  5308.6   0.035       0  5376.2    0.12       0
  5448.5   0.035       0
Bank Sta=4976,4983.1
Exp/Cntr=0.3,0.1

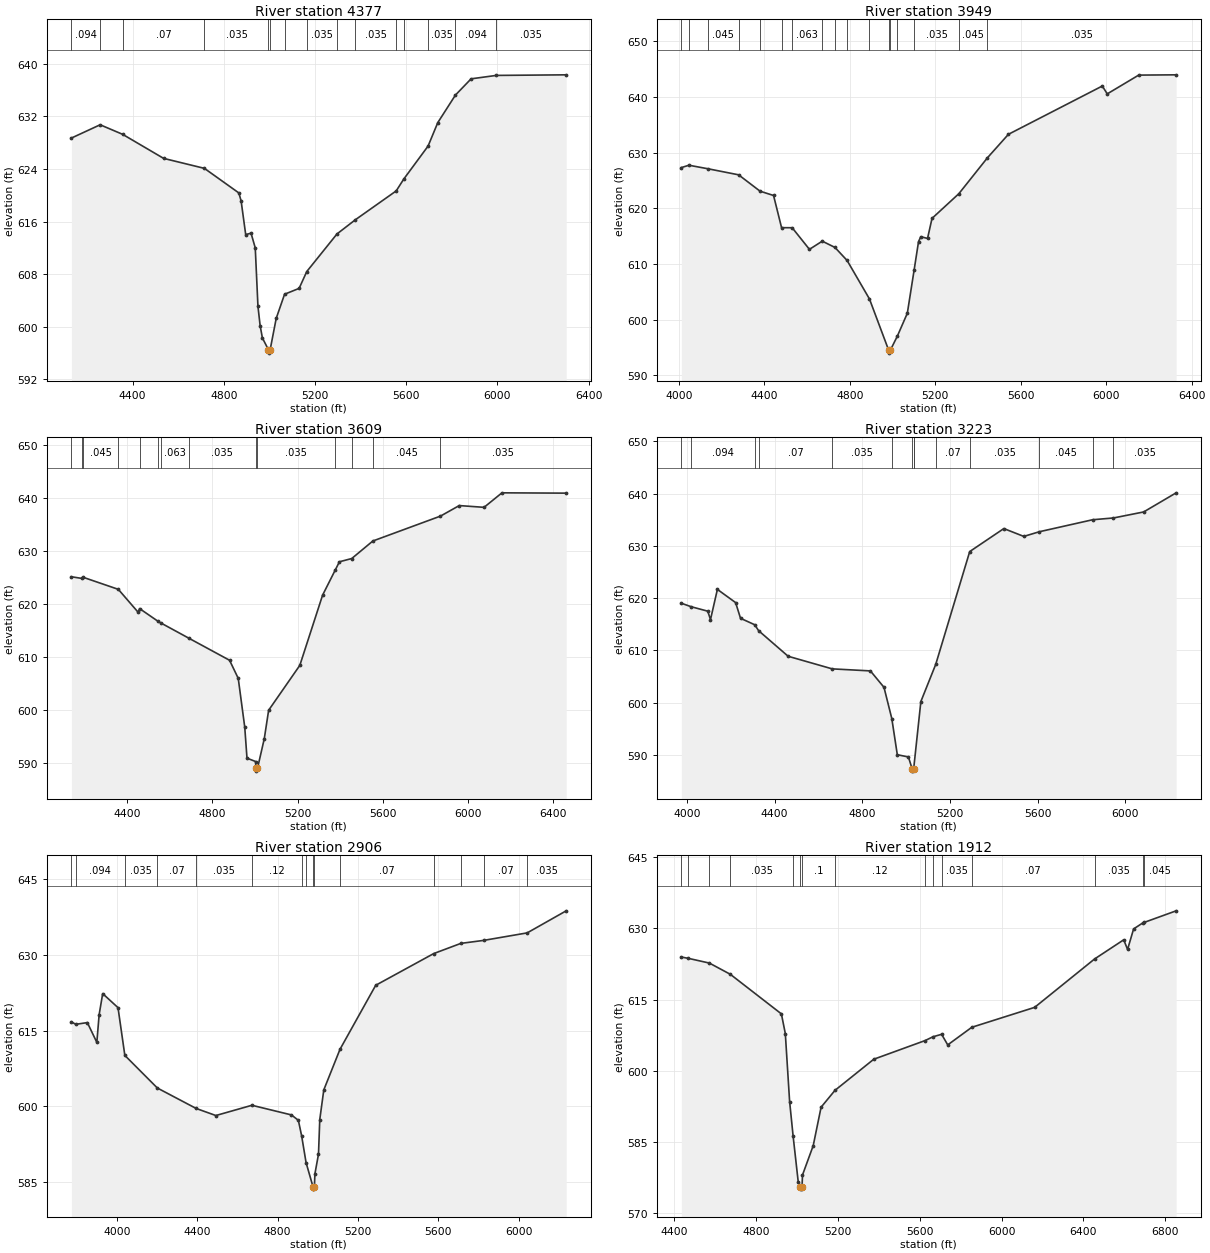
Type RM Length L Ch R = 1,4377,428,428,428
BEGIN DESCRIPTION:
GUADALUPE TRIBUTARY 29 210475
END DESCRIPTION:
XS GIS Cut Line= 3
      2264629.09     13799273.12      2263853.48     13799286.72
      2262548.54     13799776.07
#Sta/Elev= 30
  4132.0  628.70  4258.0  630.72  4356.5  629.27  4536.2  625.61  4715.1  624.09
  4866.2  620.35  4876.2  619.12  4896.2  614.01  4919.6  614.23  4938.1  611.99
  4949.9  603.10  4959.5  600.15  4969.4  598.29  4996.1  596.48  4996.6  595.98
  5003.3  596.48  5030.0  601.27  5066.6  604.94  5130.4  605.83  5163.9  608.39
  5296.4  614.11  5376.6  616.26  5556.1  620.66  5589.4  622.47  5695.8  627.48
  5738.4  631.05  5815.8  635.24  5884.4  637.71  5994.7  638.23  6301.4  638.32
#Mann=15,-1,0
  4132.0   0.094       0  4258.0   0.063       0  4356.5    0.07       0
  4715.1   0.035       0  4996.1   0.035       0  5003.3   0.035       0
  5066.6    0.12       0  5163.9   0.035       0  5296.4     0.1       0
  5376.6   0.035       0  5556.1    0.12       0  5589.4     0.1       0
  5695.8   0.035       0  5815.8   0.094       0  5994.7   0.035       0
Bank Sta=4996.1,5003.3
Exp/Cntr=0.3,0.1

Type RM Length L Ch R = 1,3949,340,340,340
BEGIN DESCRIPTION:
GUADALUPE TRIBUTARY 29 210474
END DESCRIPTION:
XS GIS Cut Line= 3
      2264574.68     13799069.00      2263948.73     13798919.32
      2262358.31     13799435.87
#Sta/Elev= 30
  4011.7  627.31  4047.2  627.73  4137.1  627.09  4279.6  626.01  4380.1  623.07
  4443.2  622.30  4480.7  616.52  4530.4  616.51  4611.1  612.63  4671.2  614.10
  4730.7  612.97  4787.5  610.63  4892.0  603.73  4982.2  594.50  4982.7  594.00
  4989.5  594.50  5022.6  597.05  5069.3  601.16  5101.2  608.94  5121.8  614.03
  5132.4  614.90  5163.9  614.59  5184.9  618.19  5310.7  622.63  5444.3  629.07
  5542.4  633.28  5981.8  641.95  6005.0  640.54  6152.2  643.91  6327.5  643.96
#Mann=17,-1,0
  4011.7   0.063       0  4047.2   0.035       0  4137.1   0.045       0
  4279.6    0.07       0  4380.1   0.035       0  4480.7   0.094       0
  4530.4   0.063       0  4671.2   0.035       0  4730.7   0.094       0
  4787.5   0.063       0  4892.0   0.035       0  4982.2   0.035       0
  4989.5   0.035       0  5022.6   0.063       0  5101.2   0.035       0
  5310.7   0.045       0  5444.3   0.035       0
Bank Sta=4982.2,4989.5
Exp/Cntr=0.3,0.1

Type RM Length L Ch R = 1,3609,386,386,386
BEGIN DESCRIPTION:
GUADALUPE TRIBUTARY 29 210473
END DESCRIPTION:
XS GIS Cut Line= 3
      2264533.81     13798932.92      2263458.86     13798715.21
      2262234.16     13798824.07
#Sta/Elev= 30
  4136.7  625.13  4185.4  624.82  4192.7  625.02  4357.3  622.76  4450.2  618.46
  4457.2  619.14  4545.2  616.71  4558.3  616.41  4688.6  613.57  4880.3  609.41
  4921.1  606.00  4951.7  596.81  4962.2  590.98  5002.7  590.35  5004.2  589.04
  5004.7  588.54  5011.5  589.04  5043.6  594.66  5064.0  600.00  5210.6  608.45
  5317.7  621.67  5377.2  626.40  5396.8  627.95  5454.7  628.56  5553.9  631.86
  5872.0  636.55  5960.2  638.53  6076.9  638.20  6161.0  640.93  6463.0  640.87
#Mann=14,-1,0
  4136.7   0.045       0  4185.4   0.035       0  4192.7   0.045       0
  4357.3   0.035       0  4457.2   0.094       0  4545.2   0.035       0
  4558.3   0.063       0  4688.6   0.035       0  5004.2   0.035       0
  5011.5   0.035       0  5377.2    0.07       0  5454.7   0.035       0
  5553.9   0.045       0  5872.0   0.035       0
Bank Sta=5004.2,5011.5
Exp/Cntr=0.3,0.1

Type RM Length L Ch R = 1,3223,317,317,317
BEGIN DESCRIPTION:
A19320
END DESCRIPTION:
XS GIS Cut Line= 3
      2264562.42     13798744.74      2263694.67     13798490.86
      2262358.52     13798699.04
#Sta/Elev= 30
  3975.2  619.02  4020.2  618.35  4095.6  617.50  4108.0  615.88  4139.5  621.67
  4222.6  619.14  4245.0  616.14  4309.9  614.90  4327.4  613.77  4462.2  608.87
  4663.1  606.46  4837.3  606.07  4899.2  602.93  4934.9  596.94  4960.0  590.03
  5010.6  589.60  5027.2  587.39  5027.7  586.89  5034.5  587.39  5035.1  587.52
  5067.4  600.21  5135.2  607.32  5290.2  628.91  5445.8  633.31  5536.8  631.81
  5608.3  632.71  5850.9  635.00  5945.8  635.34  6083.4  636.49  6231.6  640.15
#Mann=14,-1,0
  3975.2   0.045       0  4020.2   0.094       0  4309.9   0.035       0
  4327.4    0.07       0  4663.1   0.035       0  4934.9    0.07       0
  5027.2    0.05       0  5034.5    0.07       0  5035.1    0.12       0
  5135.2    0.07       0  5290.2   0.035       0  5608.3   0.045       0
  5850.9    0.07       0  5945.8   0.035       0
Bank Sta=5027.2,5034.5
Exp/Cntr=0.3,0.1

Type RM Length L Ch R = 1,2906,994,994,994
BEGIN DESCRIPTION:
GUADALUPE TRIBUTARY 29 210472
END DESCRIPTION:
XS GIS Cut Line= 3
      2264601.88     13798701.59      2263486.08     13798225.34
      2262302.21     13798619.96
#Sta/Elev= 30
  3774.6  616.74  3796.4  616.26  3853.9  616.60  3901.1  612.68  3912.6  618.18
  3930.2  622.34  4006.4  619.56  4040.4  610.10  4202.1  603.64  4395.1  599.59
  4493.1  598.19  4672.5  600.22  4869.0  598.31  4903.5  597.24  4919.8  594.16
  4941.9  588.85  4976.1  584.11  4976.6  583.61  4983.4  584.11  4985.7  586.62
  5003.6  590.52  5010.0  597.40  5030.0  603.27  5110.7  611.32  5288.2  623.99
  5576.6  630.27  5711.7  632.29  5824.6  632.88  6041.7  634.37  6235.7  638.74
#Mann=15,-1,0
  3774.6   0.045       0  3796.4   0.094       0  4040.4   0.035       0
  4202.1    0.07       0  4395.1   0.035       0  4672.5    0.12       0
  4919.8    0.07       0  4941.9   0.035       0  4976.1   0.035       0
  4983.4   0.035       0  5110.7    0.07       0  5576.6   0.035       0
  5711.7   0.045       0  5824.6    0.07       0  6041.7   0.035       0
Bank Sta=4976.1,4983.4
Exp/Cntr=0.3,0.1

Type RM Length L Ch R = 1,1912,822,822,822
BEGIN DESCRIPTION:
A19318
END DESCRIPTION:
XS GIS Cut Line= 4
      2264759.44     13798396.13      2264039.49     13798168.78
      2263599.95     13797941.43      2262516.23     13798377.19
#Sta/Elev= 30
  4434.9  623.96  4469.3  623.68  4571.7  622.69  4674.0  620.33  4923.7  611.99
  4942.9  607.85  4963.9  593.54  4981.0  586.26  5005.8  576.68  5016.7  575.59
  5017.2  575.09  5024.6  575.59  5026.8  578.06  5079.2  584.24  5117.7  592.34
  5185.6  595.89  5375.1  602.44  5625.9  606.37  5664.5  607.17  5706.7  607.69
  5736.6  605.46  5854.2  609.17  6161.2  613.36  6454.1  623.55  6596.6  627.59
  6615.4  625.56  6644.9  629.88  6689.3  631.13  6697.7  631.27  6852.8  633.69
#Mann=15,-1,0
  4434.9    0.07       0  4469.3     0.1       0  4571.7   0.063       0
  4674.0   0.035       0  4981.0     0.1       0  5016.7    0.05       0
  5024.6     0.1       0  5185.6    0.12       0  5625.9   0.035       0
  5664.5    0.12       0  5706.7   0.035       0  5854.2    0.07       0
  6454.1   0.035       0  6689.3    0.07       0  6697.7   0.045       0
Bank Sta=5016.7,5024.6
Exp/Cntr=0.3,0.1

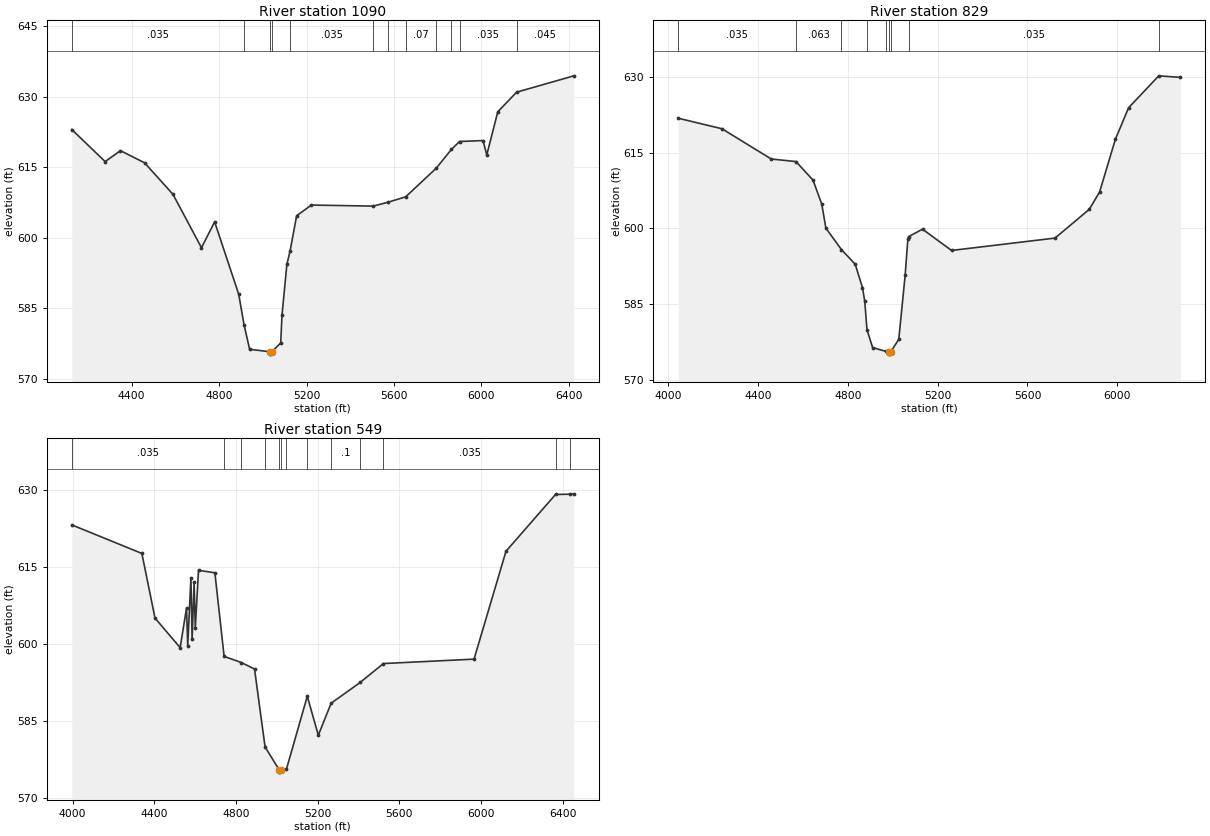
Type RM Length L Ch R = 1,1090,261,261,261
BEGIN DESCRIPTION:
GUADALUPE TRIBUTARY 29 210471
END DESCRIPTION:
XS GIS Cut Line= 3
      2264547.45     13797789.90      2263662.97     13797749.07
      2262398.69     13798374.42
#Sta/Elev= 30
  4126.6  623.06  4279.2  616.24  4349.3  618.56  4459.4  615.98  4589.5  609.27
  4719.7  597.91  4779.9  603.42  4889.9  588.04  4914.4  581.52  4939.9  576.31
  5033.2  575.78  5033.7  575.28  5041.1  575.78  5082.0  577.65  5087.9  583.54
  5110.2  594.35  5124.6  597.15  5154.9  604.71  5222.2  606.99  5505.1  606.77
  5570.7  607.56  5653.4  608.74  5793.7  614.85  5862.8  618.84  5900.1  620.51
  6007.4  620.71  6024.3  617.66  6074.7  626.83  6160.8  631.00  6422.5  634.48
#Mann=12,-1,0
  4126.6   0.035       0  4914.4     0.1       0  5033.2    0.05       0
  5041.1     0.1       0  5124.6   0.035       0  5505.1    0.07       0
  5570.7   0.035       0  5653.4    0.07       0  5793.7   0.035       0
  5862.8    0.07       0  5900.1   0.035       0  6160.8   0.045       0
Bank Sta=5033.2,5041.1
Exp/Cntr=0.3,0.1

Type RM Length L Ch R = 1,829,280,280,280
BEGIN DESCRIPTION:
A19319
END DESCRIPTION:
XS GIS Cut Line= 4
      2264467.63     13797702.70      2263781.83     13797509.46
      2263391.54     13797562.51      2262413.94     13798127.09
#Sta/Elev= 30
  4045.2  621.81  4239.8  619.73  4459.5  613.74  4569.3  613.24  4645.2  609.57
  4684.4  604.79  4702.5  600.07  4772.0  595.81  4833.1  592.93  4865.5  588.28
  4875.6  585.61  4885.5  579.97  4910.6  576.44  4971.6  575.66  4984.1  575.64
  4984.6  575.14  4992.1  575.64  5027.0  578.06  5055.5  590.74  5067.4  597.84
  5071.4  598.40  5132.9  599.86  5261.9  595.65  5722.8  598.10  5875.1  603.78
  5921.0  607.20  5991.4  617.64  6050.2  623.88  6184.6  630.20  6280.5  629.89
#Mann=9,-1,0
  4045.2   0.035       0  4569.3   0.063       0  4772.0     0.1       0
  4885.5    0.12       0  4971.6     0.1       0  4984.1    0.05       0
  4992.1     0.1       0  5071.4   0.035       0  6184.6   0.045       0
Bank Sta=4984.1,4992.1
Exp/Cntr=0.3,0.1

Type RM Length L Ch R = 1,549,0,0,0
BEGIN DESCRIPTION:
GUADALUPE TRIBUTARY 29 210470
END DESCRIPTION:
XS GIS Cut Line= 4
      2264411.41     13797626.62      2263717.40     13797218.38
      2263336.39     13797313.63      2262343.05     13798089.26
#Sta/Elev= 30
  3996.0  623.26  4339.2  617.70  4403.6  605.10  4526.6  599.35  4557.9  607.05
  4563.7  599.70  4579.4  612.95  4585.2  600.97  4595.0  612.14  4600.8  603.20
  4616.5  614.40  4696.6  613.94  4741.9  597.64  4826.1  596.45  4890.8  595.19
  4942.4  580.01  5010.5  575.60  5011.0  575.10  5018.5  575.60  5046.8  575.64
  5149.1  589.88  5203.1  582.29  5265.8  588.52  5407.8  592.56  5521.7  596.25
  5965.6  597.11  6121.9  618.12  6364.4  629.18  6434.4  629.24  6454.2  629.31
#Mann=13,-1,0
  3996.0   0.035       0  4741.9   0.063       0  4826.1   0.035       0
  4942.4   0.033       0  5010.5   0.033       0  5018.5   0.033       0
  5046.8    0.12       0  5149.1    0.07       0  5265.8     0.1       0
  5407.8    0.07       0  5521.7   0.035       0  6364.4   0.045       0
  6434.4   0.035       0
Bank Sta=5010.5,5018.5
Exp/Cntr=0.3,0.1

Chan Stop Cuts=-1