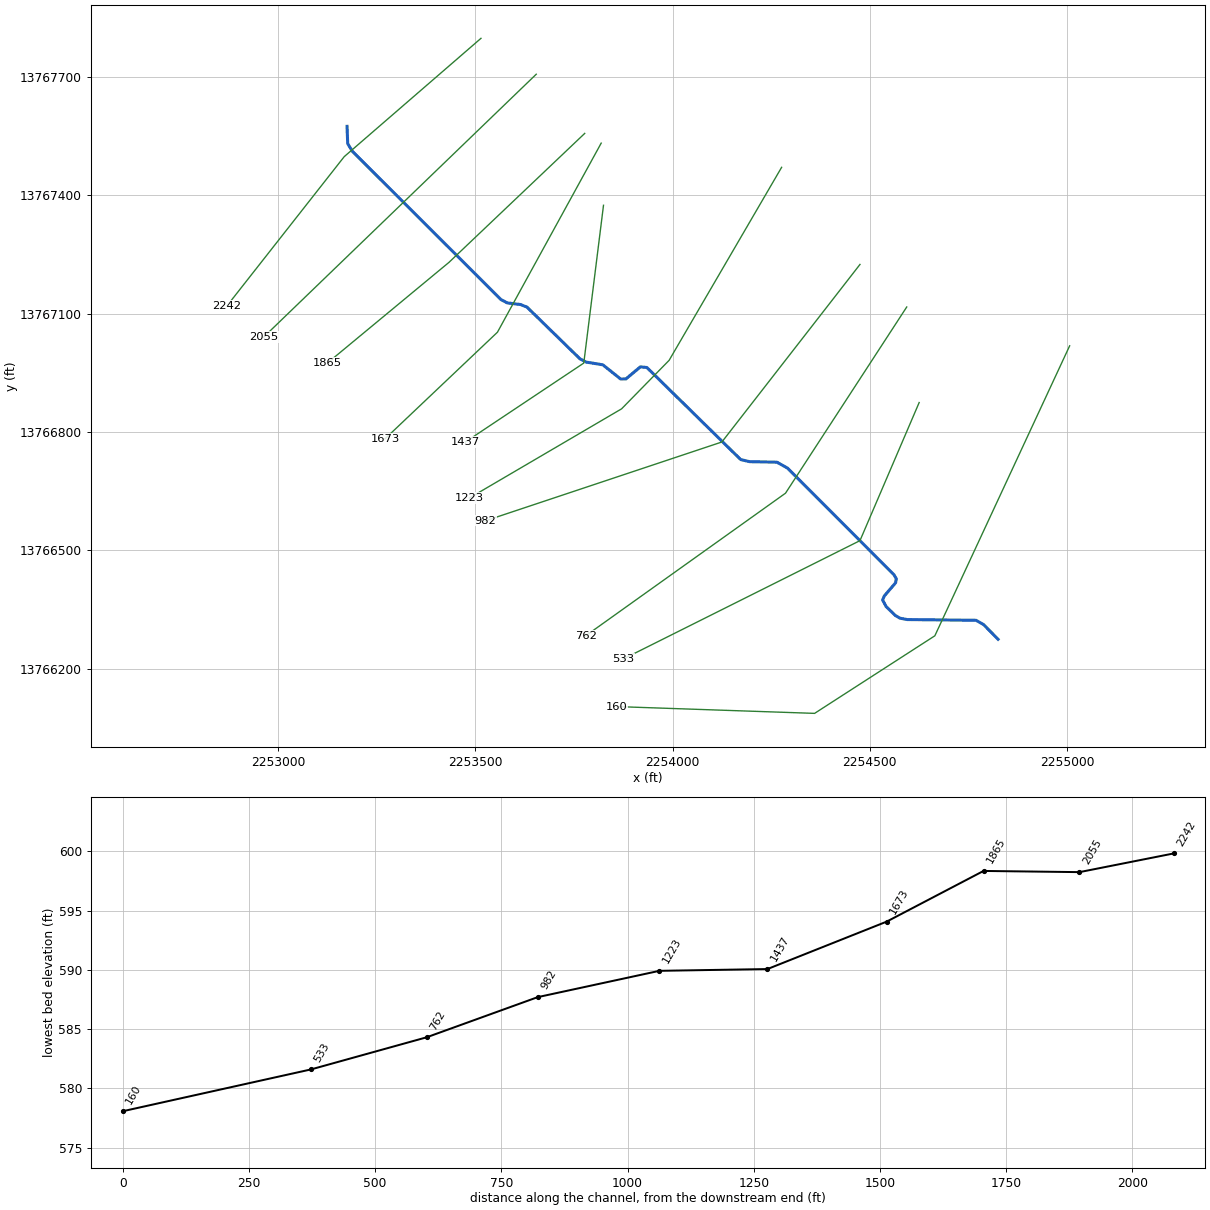
--- GUADALUPE TRIBUTARY 2A 2.prj (project) ---

Proj Title=GUADALUPE TRIBUTARY 2A 2 Base Level Engineering
Current Plan=p01
Default Exp/Contr=0.3,0.1
English Units
Geom File=g01
Flow File=f01
Plan File=p01
BEGIN DESCRIPTION:
GUADALUPE TRIBUTARY 2A 2
END DESCRIPTION:

--- GUADALUPE TRIBUTARY 2A 2.p01 (plan) ---

Plan Title=Multiple Run
Short Identifier=Multiple
Geom File=g01
Flow File=f01
Subcritical Flow
K Sum by GR= 0
Std Step Tol= 0.01
Critical Tol= 0.01
Num of Std Step Trials= 20
Max Error Tol= 0.3
Flow Tol Ratio= 0.001
Split Flow NTrial= 30
Split Flow Tol= 0.02
Split Flow Ratio= 0.02
Log Output Level= 0
Friction Slope Method= 1
Unsteady Friction Slope Method= 2
Unsteady Bridges Friction Slope Method= 1
Parabolic Critical Depth
Global Vel Dist=  1 , 1 , 1
Global Log Level= 0
CheckData=True
Encroach Param= -1, 0, 0, 0
BEGIN DESCRIPTION:
Multiple Run
END DESCRIPTION:

--- GUADALUPE TRIBUTARY 2A 2.f01 (steady flow) ---

Flow Title=Multiple
Number of Profiles=7
Profile Names=10-year,25-year,50-year,1pct_min,100-year,1pct_plu,500-year
River Rch & RM= GUADALUPE TRIBUT,Reach-1,2242
     225     340     438     274     547    1092     843
Boundary for River Rch & Prof#=GUADALUPE TRIBUT,Reach-1,1
Up Type=0
Dn Type=3
Dn Slope=0.005
Boundary for River Rch & Prof#=GUADALUPE TRIBUT,Reach-1,2
Up Type=0
Dn Type=3
Dn Slope=0.005
Boundary for River Rch & Prof#=GUADALUPE TRIBUT,Reach-1,3
Up Type=0
Dn Type=3
Dn Slope=0.005
Boundary for River Rch & Prof#=GUADALUPE TRIBUT,Reach-1,4
Up Type=0
Dn Type=3
Dn Slope=0.005
Boundary for River Rch & Prof#=GUADALUPE TRIBUT,Reach-1,5
Up Type=0
Dn Type=3
Dn Slope=0.005
Boundary for River Rch & Prof#=GUADALUPE TRIBUT,Reach-1,6
Up Type=0
Dn Type=3
Dn Slope=0.005
Boundary for River Rch & Prof#=GUADALUPE TRIBUT,Reach-1,7
Up Type=0
Dn Type=3
Dn Slope=0.005

--- GUADALUPE TRIBUTARY 2A 2.g01 (geometry) ---

Geom Title=Existing Conditions

River Reach=GUADALUPE TRIBUT,Reach-1
Reach XY= 30
      2253175.00     13767575.00      2253176.68     13767531.14
      2253188.47     13767511.73      2253565.32     13767135.78
      2253581.05     13767127.53      2253614.36     13767123.45
      2253631.05     13767116.84      2253765.32     13766985.75
      2253781.05     13766977.46      2253823.35     13766970.56
      2253868.45     13766934.59      2253881.73     13766934.77
      2253918.34     13766965.40      2253935.00     13766963.76
      2254172.57     13766730.52      2254195.06     13766725.13
      2254264.52     13766723.83      2254291.75     13766708.54
      2254561.35     13766438.33      2254566.99     13766428.32
      2254565.38     13766418.31      2254536.65     13766384.85
      2254532.46     13766374.75      2254541.20     13766357.87
      2254564.49     13766335.48      2254576.00     13766328.54
      2254594.76     13766324.96      2254769.22     13766323.11
      2254788.50     13766312.08      2254825.00     13766275.00

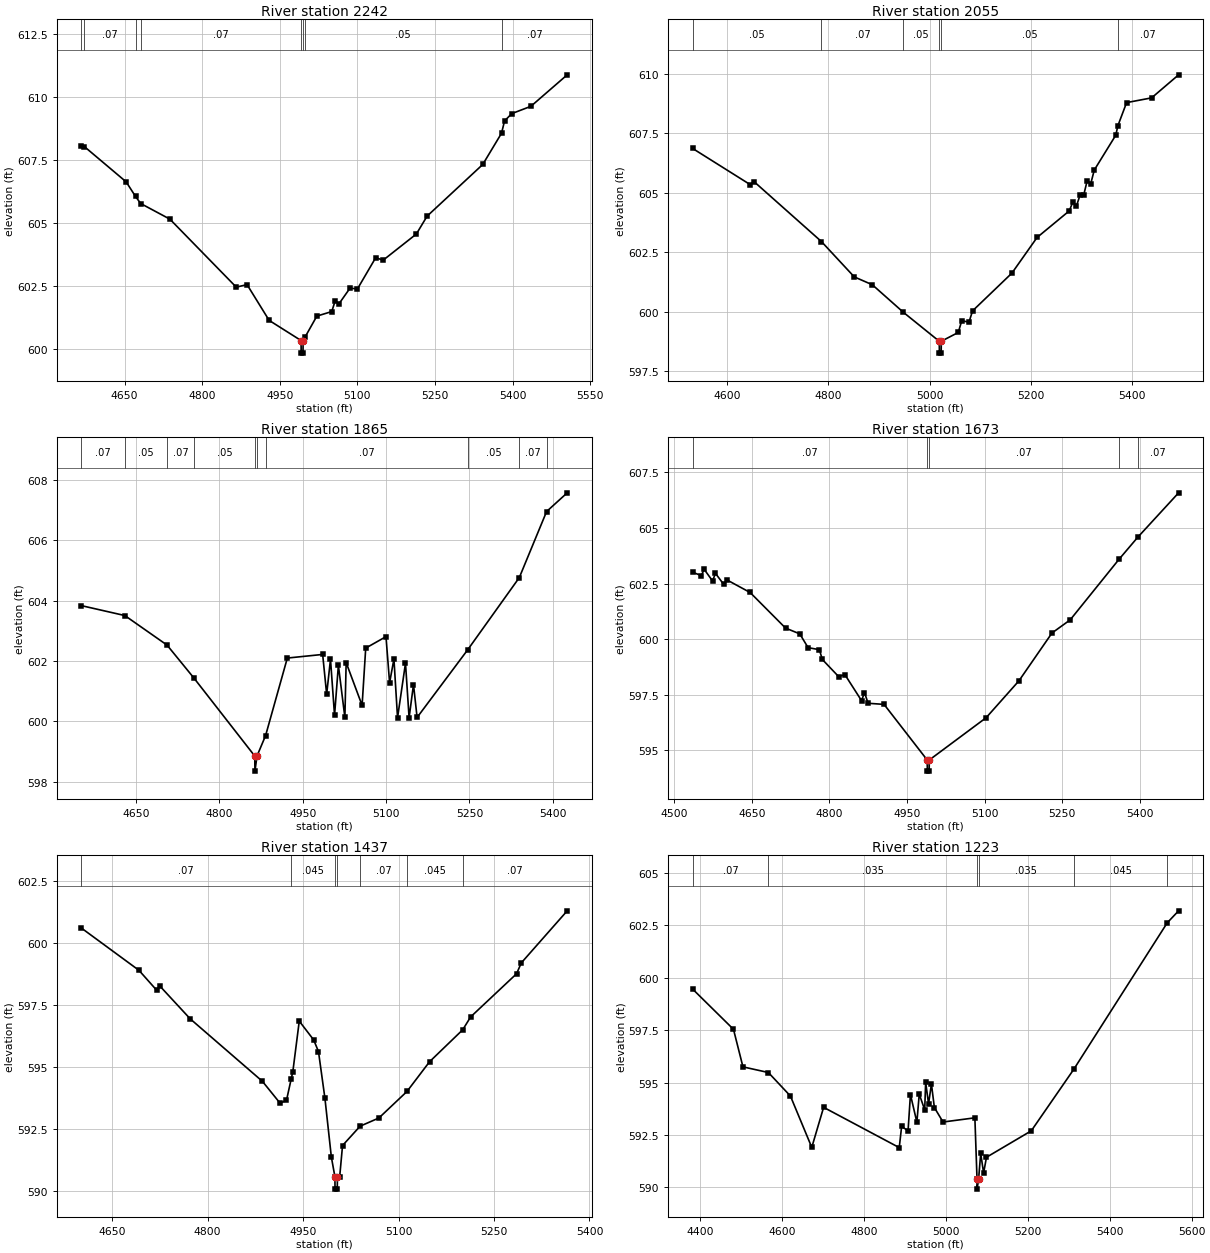
Type RM Length L Ch R = 1,2242,187,187,187
BEGIN DESCRIPTION:
A19331
END DESCRIPTION:
XS GIS Cut Line= 3
      2253514.42     13767798.04      2253167.80     13767498.13
      2252870.54     13767119.80
#Sta/Elev= 30
  4566.2  608.04  4572.3  608.03  4653.1  606.63  4671.2  606.05  4681.2  605.77
  4737.6  605.15  4865.9  602.45  4886.8  602.55  4929.5  601.13  4991.2  600.33
  4991.4  599.83  4994.9  599.83  4995.2  600.33  4999.0  600.47  5021.7  601.30
  5050.5  601.48  5056.9  601.89  5064.9  601.80  5085.8  602.41  5100.2  602.38
  5135.5  603.62  5149.9  603.52  5214.1  604.56  5234.9  605.27  5342.4  607.32
  5378.7  608.56  5384.6  609.05  5398.5  609.34  5435.5  609.63  5505.7  610.88
#Mann=8,-1,0
  4566.2    0.05       0  4572.3    0.07       0  4671.2    0.05       0
  4681.2    0.07       0  4991.2    0.05       0  4995.2    0.07       0
  4999.0    0.05       0  5378.7    0.07       0
Bank Sta=4991.2,4995.2
Exp/Cntr=0.3,0.1

Type RM Length L Ch R = 1,2055,190,190,190
BEGIN DESCRIPTION:
A19332
END DESCRIPTION:
XS GIS Cut Line= 2
      2253654.51     13767707.07      2252963.79     13767040.94
#Sta/Elev= 30
  4532.1  606.87  4646.3  605.34  4653.5  605.47  4786.4  602.95  4851.3  601.46
  4886.9  601.13  4948.2  599.97  5019.1  598.75  5019.4  598.25  5022.9  598.25
  5023.1  598.75  5056.6  599.12  5063.6  599.62  5077.7  599.55  5084.9  600.03
  5162.6  601.62  5212.2  603.12  5275.8  604.24  5282.8  604.61  5290.0  604.45
  5296.9  604.89  5304.1  604.89  5311.1  605.50  5318.3  605.39  5325.2  605.96
  5367.7  607.43  5371.7  607.82  5389.0  608.80  5438.4  609.00  5491.7  609.97
#Mann=6,-1,0
  4532.1    0.05       0  4786.4    0.07       0  4948.2    0.05       0
  5019.1    0.05       0  5023.1    0.05       0  5371.7    0.07       0
Bank Sta=5019.1,5023.1
Exp/Cntr=0.3,0.1

Type RM Length L Ch R = 1,1865,192,192,192
BEGIN DESCRIPTION:
GUADALUPE TRIBUTARY 2A 2 4.0
END DESCRIPTION:
XS GIS Cut Line= 3
      2253777.38     13767557.10      2253433.27     13767230.20
      2253125.03     13766975.02
#Sta/Elev= 30
  4551.2  603.84  4629.7  603.51  4705.7  602.53  4754.4  601.43  4863.6  598.85
  4863.9  598.35  4867.6  598.85  4883.1  599.53  4922.2  602.10  4985.8  602.22
  4993.0  600.90  4999.9  602.06  5007.2  600.20  5014.1  601.86  5025.8  600.13
  5028.1  601.95  5056.8  600.53  5063.3  602.43  5099.8  602.81  5106.3  601.28
  5114.1  602.07  5120.6  600.12  5134.9  601.93  5141.4  600.12  5149.3  601.22
  5155.8  600.13  5247.1  602.38  5339.8  604.77  5388.9  606.96  5426.0  607.58
#Mann=10,-1,0
  4551.2    0.07       0  4629.7    0.05       0  4705.7    0.07       0
  4754.4    0.05       0  4863.6    0.05       0  4867.6    0.05       0
  4883.1    0.07       0  5247.1    0.05       0  5339.8    0.07       0
  5388.9   0.045       0
Bank Sta=4863.6,4867.6
Exp/Cntr=0.3,0.1

Type RM Length L Ch R = 1,1673,236,236,236
BEGIN DESCRIPTION:
A19330
END DESCRIPTION:
XS GIS Cut Line= 3
      2253819.17     13767532.52      2253556.18     13767053.22
      2253271.01     13766782.81
#Sta/Elev= 30
  4535.6  603.01  4552.3  602.86  4558.0  603.14  4574.1  602.62  4579.8  602.96
  4595.9  602.46  4601.6  602.67  4646.8  602.10  4715.3  600.50  4742.8  600.24
  4758.9  599.62  4780.7  599.53  4786.4  599.09  4817.9  598.32  4830.0  598.41
  4862.2  597.24  4867.9  597.60  4875.0  597.12  4905.8  597.07  4989.2  594.57
  4989.5  594.07  4993.0  594.07  4993.2  594.57  5103.1  596.47  5166.6  598.13
  5230.5  600.28  5265.7  600.87  5360.0  603.59  5396.2  604.58  5475.3  606.58
#Mann=5,-1,0
  4535.6    0.07       0  4989.2    0.05       0  4993.2    0.07       0
  5360.0   0.045       0  5396.2    0.07       0
Bank Sta=4989.2,4993.2
Exp/Cntr=0.3,0.1

Type RM Length L Ch R = 1,1437,214,214,214
BEGIN DESCRIPTION:
GUADALUPE TRIBUTARY 2A 2 3.0
END DESCRIPTION:
XS GIS Cut Line= 3
      2253825.00     13767374.96      2253775.00     13766975.00
      2253475.02     13766775.02
#Sta/Elev= 30
  4601.4  600.61  4692.1  598.90  4719.8  598.10  4724.8  598.27  4772.7  596.94
  4886.1  594.42  4913.8  593.54  4923.9  593.65  4931.2  594.50  4933.9  594.81
  4944.0  596.85  4966.7  596.09  4974.2  595.62  4984.3  593.74  4994.4  591.37
  5000.0  590.57  5000.2  590.07  5003.7  590.07  5004.0  590.57  5007.5  590.57
  5012.0  591.83  5039.6  592.61  5069.1  592.94  5113.2  594.01  5148.7  595.21
  5200.8  596.50  5213.3  597.02  5285.4  598.76  5292.9  599.20  5365.0  601.30
#Mann=7,-1,0
  4601.4    0.07       0  4931.2   0.045       0  5000.0   0.045       0
  5004.0   0.045       0  5039.6    0.07       0  5113.2   0.045       0
  5200.8    0.07       0
Bank Sta=5000,5004
Exp/Cntr=0.3,0.1

Type RM Length L Ch R = 1,1223,241,241,241
BEGIN DESCRIPTION:
A19329
END DESCRIPTION:
XS GIS Cut Line= 4
      2254276.41     13767471.13      2253991.25     13766981.94
      2253870.81     13766859.03      2253484.90     13766632.89
#Sta/Elev= 30
  4382.6  599.46  4482.3  597.54  4505.4  595.75  4567.4  595.48  4621.2  594.36
  4673.3  591.91  4702.2  593.82  4886.7  591.90  4892.5  592.91  4908.2  592.70
  4914.0  594.43  4929.7  593.11  4935.5  594.45  4948.8  593.70  4951.1  595.02
  4958.2  593.99  4965.2  594.93  4972.4  593.81  4993.5  593.12  5071.2  593.32
  5076.4  590.42  5076.6  589.92  5080.4  590.42  5085.4  591.62  5092.5  590.69
  5099.5  591.44  5208.8  592.70  5312.7  595.64  5540.5  602.62  5568.2  603.19
#Mann=6,-1,0
  4382.6    0.07       0  4567.4   0.035       0  5076.4   0.035       0
  5080.4   0.035       0  5312.7   0.045       0  5540.5    0.07       0
Bank Sta=5076.4,5080.4
Exp/Cntr=0.3,0.1

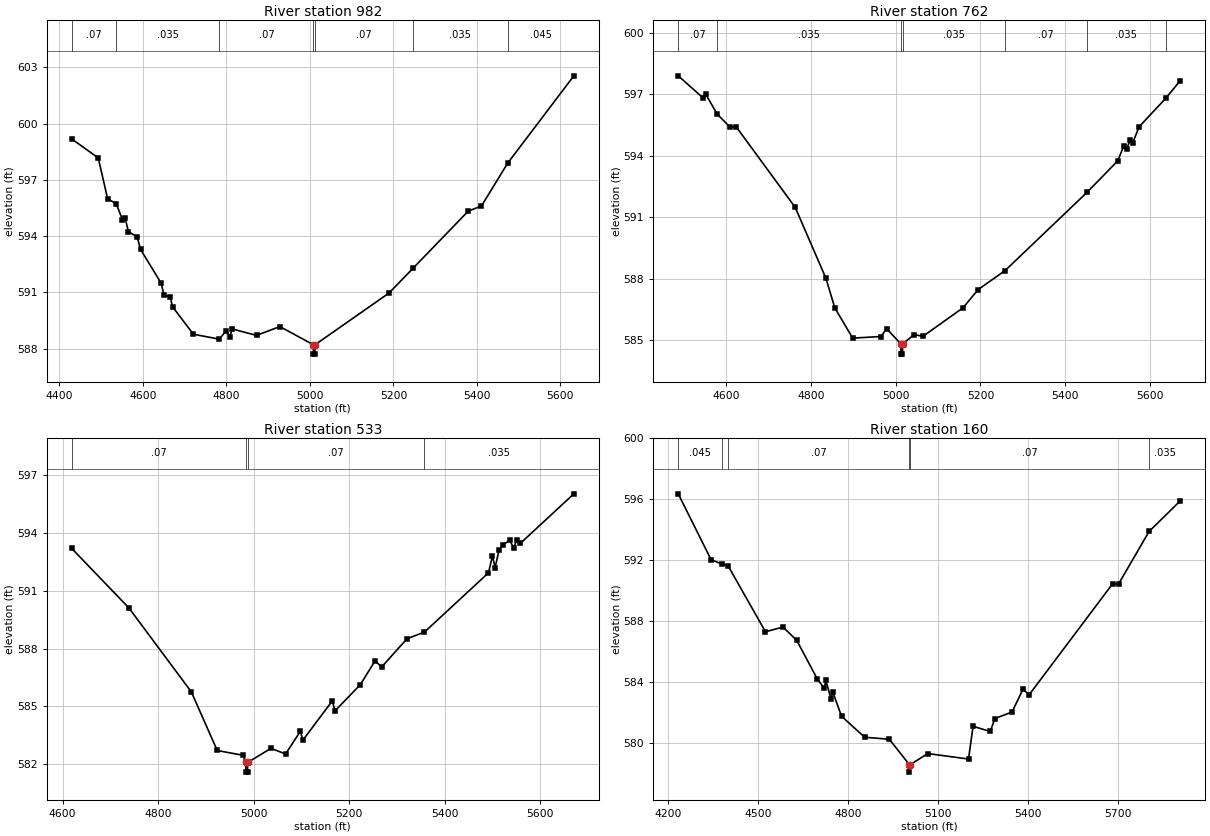
Type RM Length L Ch R = 1,982,220,220,220
BEGIN DESCRIPTION:
GUADALUPE TRIBUTARY 2A 2 2.0
END DESCRIPTION:
XS GIS Cut Line= 3
      2254475.02     13767225.03      2254125.00     13766775.00
      2253524.98     13766574.99
#Sta/Elev= 30
  4429.6  599.18  4493.0  598.17  4515.6  595.98  4536.0  595.73  4550.9  594.88
  4557.2  594.98  4565.4  594.23  4586.2  593.96  4594.3  593.29  4644.1  591.47
  4650.4  590.84  4664.9  590.77  4671.2  590.22  4721.0  588.76  4782.9  588.50
  4799.7  588.95  4807.9  588.62  4814.2  589.04  4872.1  588.70  4928.2  589.17
  5008.3  588.20  5008.5  587.70  5012.0  587.70  5012.3  588.20  5189.5  590.96
  5247.0  592.28  5379.2  595.33  5410.8  595.60  5473.7  597.89  5632.2  602.55
#Mann=7,-1,0
  4429.6    0.07       0  4536.0   0.035       0  4782.9    0.07       0
  5008.3    0.05       0  5012.3    0.07       0  5247.0   0.035       0
  5473.7   0.045       0
Bank Sta=5008.3,5012.3
Exp/Cntr=0.3,0.1

Type RM Length L Ch R = 1,762,229,229,229
BEGIN DESCRIPTION:
A19333
END DESCRIPTION:
XS GIS Cut Line= 3
      2254593.48     13767117.13      2254286.22     13766645.18
      2253779.96     13766283.91
#Sta/Elev= 30
  4486.8  597.89  4545.6  596.81  4551.6  597.00  4578.4  596.03  4608.9  595.39
  4624.0  595.39  4763.0  591.47  4835.4  588.01  4856.5  586.56  4898.7  585.09
  4965.2  585.17  4978.6  585.55  5012.4  584.81  5012.6  584.31  5016.1  584.31
  5016.4  584.81  5043.6  585.26  5064.4  585.18  5159.0  586.57  5194.7  587.46
  5258.5  588.39  5452.0  592.21  5524.1  593.74  5538.8  594.48  5545.0  594.32
  5553.6  594.75  5559.7  594.63  5574.5  595.40  5637.4  596.79  5671.9  597.66
#Mann=7,-1,0
  4486.8    0.07       0  4578.4   0.035       0  5012.4   0.035       0
  5016.4   0.035       0  5258.5    0.07       0  5452.0   0.035       0
  5637.4   0.045       0
Bank Sta=5012.4,5016.4
Exp/Cntr=0.3,0.1

Type RM Length L Ch R = 1,533,373,373,373
BEGIN DESCRIPTION:
GUADALUPE TRIBUTARY 2A 2 1.0
END DESCRIPTION:
XS GIS Cut Line= 3
      2254625.02     13766875.04      2254475.00     13766525.00
      2253875.04     13766225.02
#Sta/Elev= 30
  4619.2  593.18  4738.9  590.10  4869.5  585.76  4923.9  582.72  4978.3  582.47
  4983.5  582.10  4983.8  581.60  4987.3  581.60  4987.5  582.10  5036.4  582.83
  5067.1  582.54  5097.9  583.71  5103.4  583.26  5164.9  585.29  5170.5  584.77
  5223.6  586.13  5254.4  587.36  5268.4  587.05  5321.5  588.51  5357.9  588.85
  5492.0  591.92  5500.3  592.79  5505.9  592.19  5514.3  593.12  5522.7  593.38
  5536.7  593.60  5545.1  593.19  5550.7  593.63  5559.0  593.45  5670.8  596.01
#Mann=4,-1,0
  4619.2    0.07       0  4983.5    0.05       0  4987.5    0.07       0
  5357.9   0.035       0
Bank Sta=4983.5,4987.5
Exp/Cntr=0.3,0.1

Type RM Length L Ch R = 1,160,0,0,0
BEGIN DESCRIPTION:
A19328
END DESCRIPTION:
XS GIS Cut Line= 4
      2255006.45     13767018.83      2254664.76     13766283.84
      2254359.96     13766087.20      2253859.21     13766104.38
#Sta/Elev= 30
  4234.9  596.35  4344.5  592.02  4382.1  591.73  4400.6  591.64  4525.8  587.29
  4584.4  587.60  4630.2  586.72  4698.8  584.18  4721.7  583.58  4727.2  584.09
  4744.6  582.85  4750.1  583.34  4779.5  581.74  4856.7  580.36  4938.8  580.23
  5005.4  578.57  5005.7  578.07  5009.4  578.57  5067.0  579.29  5202.9  578.93
  5218.1  581.08  5275.5  580.74  5290.7  581.59  5348.1  582.02  5384.4  583.51
  5405.5  583.16  5683.3  590.44  5703.3  590.43  5805.1  593.88  5909.2  595.89
#Mann=6,-1,0
  4234.9   0.045       0  4382.1   0.035       0  4400.6    0.07       0
  5005.4    0.05       0  5009.4    0.07       0  5805.1   0.035       0
Bank Sta=5005.4,5009.4
Exp/Cntr=0.3,0.1

Chan Stop Cuts=-1