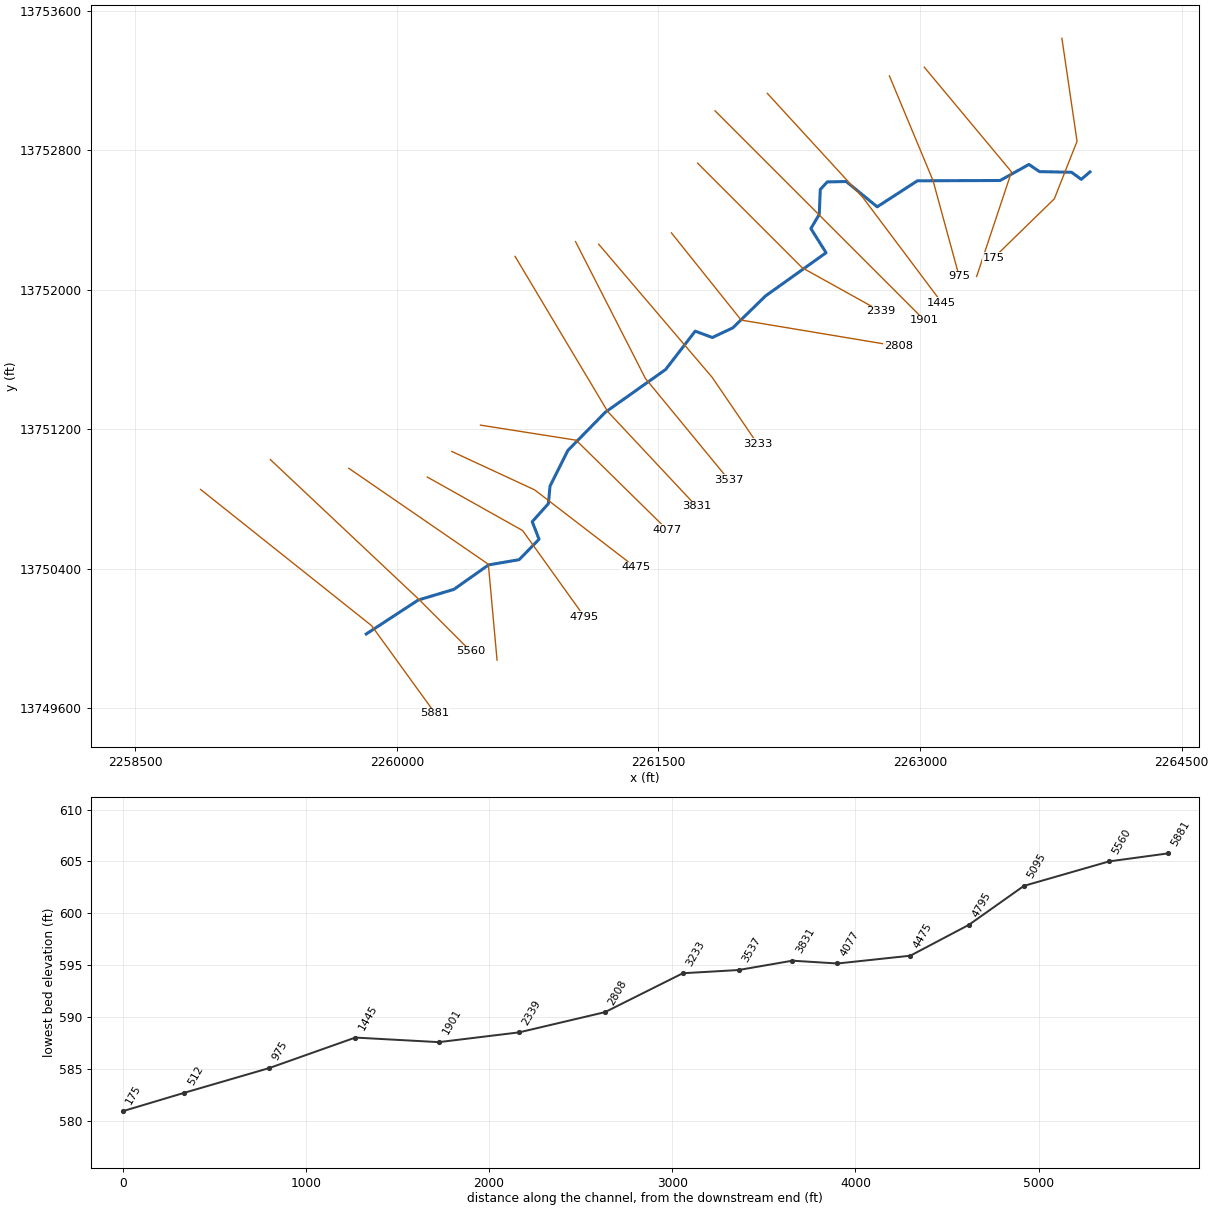
--- GUADALUPE TRIBUTARY 2A.prj (project) ---

Proj Title=GUADALUPE TRIBUTARY 2A Base Level Engineering
Current Plan=p01
Default Exp/Contr=0.3,0.1
English Units
Geom File=g01
Flow File=f01
Plan File=p01
BEGIN DESCRIPTION:
GUADALUPE TRIBUTARY 2A
END DESCRIPTION:

--- GUADALUPE TRIBUTARY 2A.p01 (plan) ---

Plan Title=Multiple Run
Short Identifier=Multiple
Geom File=g01
Flow File=f01
Subcritical Flow
K Sum by GR= 0
Std Step Tol= 0.01
Critical Tol= 0.01
Num of Std Step Trials= 20
Max Error Tol= 0.3
Flow Tol Ratio= 0.001
Split Flow NTrial= 30
Split Flow Tol= 0.02
Split Flow Ratio= 0.02
Log Output Level= 0
Friction Slope Method= 1
Unsteady Friction Slope Method= 2
Unsteady Bridges Friction Slope Method= 1
Parabolic Critical Depth
Global Vel Dist=  1 , 1 , 1
Global Log Level= 0
CheckData=True
Encroach Param= -1, 0, 0, 0
BEGIN DESCRIPTION:
Multiple Run
END DESCRIPTION:

--- GUADALUPE TRIBUTARY 2A.f01 (steady flow) ---

Flow Title=Multiple
Number of Profiles=7
Profile Names=10-year,25-year,50-year,1pct_min,100-year,1pct_plu,500-year
River Rch & RM= GUADALUPE TRIBUT,Reach-1,5881
     339     525     686     435     868    1731    1373
River Rch & RM= GUADALUPE TRIBUT,Reach-1,3831
     615     984    1314     849    1694    3380    2787
Boundary for River Rch & Prof#=GUADALUPE TRIBUT,Reach-1,1
Up Type=0
Dn Type=3
Dn Slope=0.005
Boundary for River Rch & Prof#=GUADALUPE TRIBUT,Reach-1,2
Up Type=0
Dn Type=3
Dn Slope=0.005
Boundary for River Rch & Prof#=GUADALUPE TRIBUT,Reach-1,3
Up Type=0
Dn Type=3
Dn Slope=0.005
Boundary for River Rch & Prof#=GUADALUPE TRIBUT,Reach-1,4
Up Type=0
Dn Type=3
Dn Slope=0.005
Boundary for River Rch & Prof#=GUADALUPE TRIBUT,Reach-1,5
Up Type=0
Dn Type=3
Dn Slope=0.005
Boundary for River Rch & Prof#=GUADALUPE TRIBUT,Reach-1,6
Up Type=0
Dn Type=3
Dn Slope=0.005
Boundary for River Rch & Prof#=GUADALUPE TRIBUT,Reach-1,7
Up Type=0
Dn Type=3
Dn Slope=0.005

--- GUADALUPE TRIBUTARY 2A.g01 (geometry) ---

Geom Title=Existing Conditions

River Reach=GUADALUPE TRIBUT,Reach-1
Reach XY= 30
      2259825.00     13750025.00      2260122.58     13750219.46
      2260327.29     13750280.84      2260526.56     13750421.24
      2260701.88     13750451.17      2260815.85     13750568.27
      2260776.67     13750668.95      2260869.46     13750772.58
      2260878.83     13750873.41      2260980.83     13751077.30
      2261195.39     13751296.22      2261541.67     13751541.65
      2261711.27     13751761.60      2261809.58     13751725.14
      2261927.30     13751780.83      2262115.32     13751964.22
      2262461.73     13752211.31      2262374.51     13752349.96
      2262422.70     13752430.93      2262428.44     13752573.78
      2262468.50     13752617.38      2262577.42     13752619.61
      2262754.84     13752474.53      2262985.50     13752623.80
      2263459.79     13752625.51      2263624.99     13752717.47
      2263685.44     13752676.38      2263869.16     13752672.64
      2263925.14     13752631.91      2263975.00     13752675.00

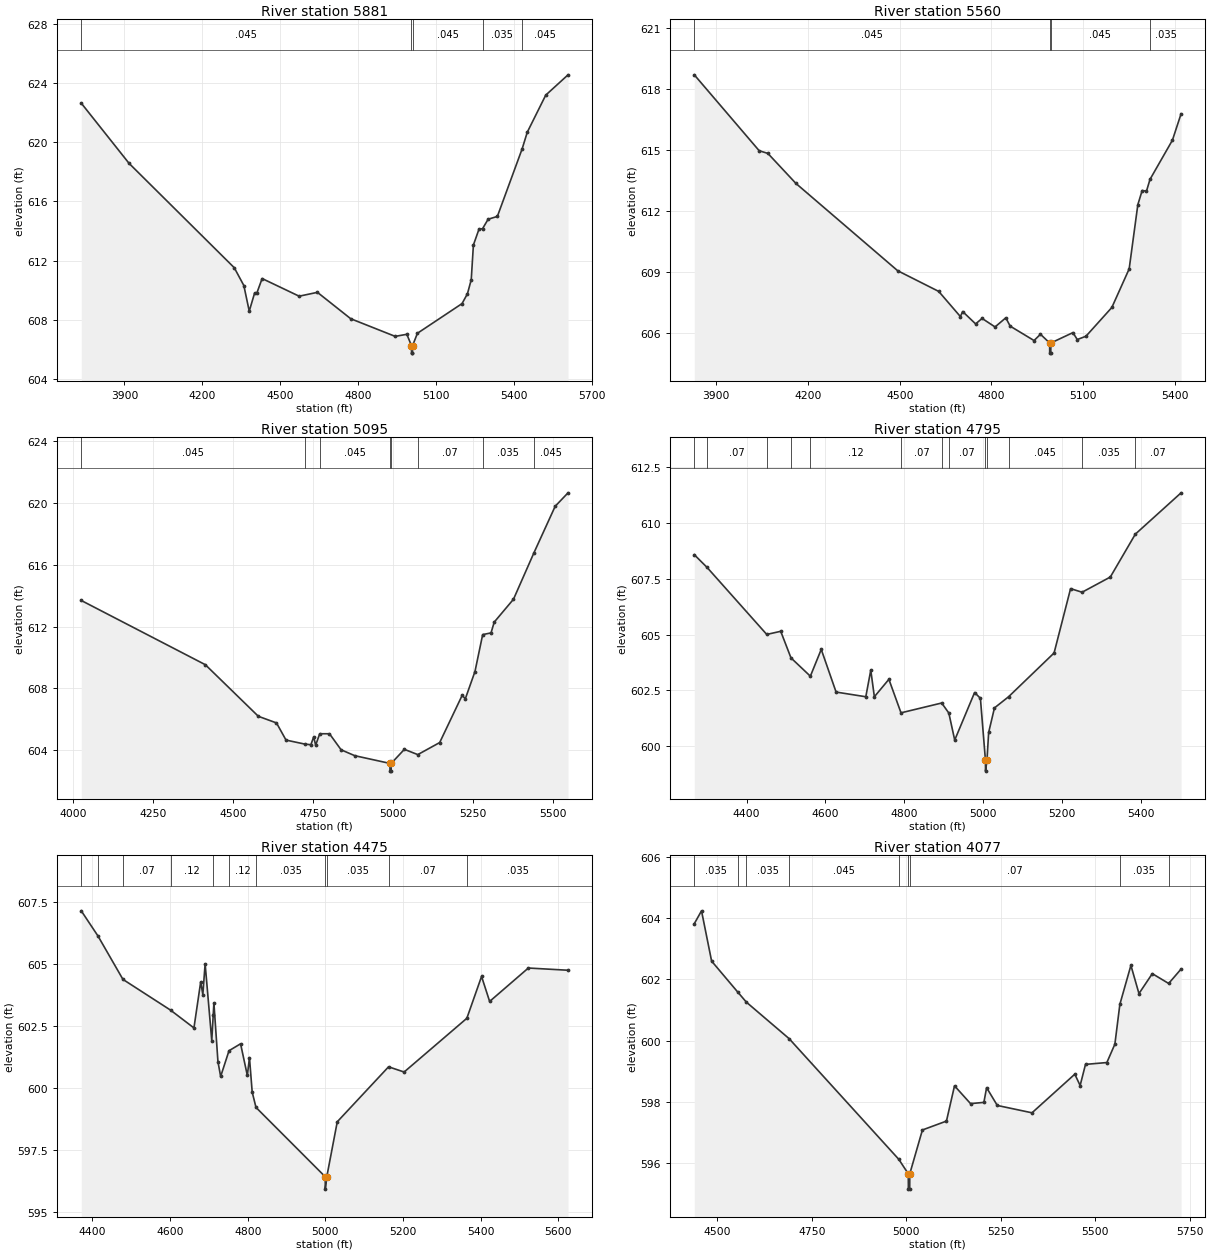
Type RM Length L Ch R = 1,5881,321,321,321
BEGIN DESCRIPTION:
A19325
END DESCRIPTION:
XS GIS Cut Line= 3
      2258874.86     13750853.84      2259855.73     13750072.62
      2260219.86     13749569.77
#Sta/Elev= 30
  3733.8  622.63  3917.9  618.57  4323.1  611.53  4360.0  610.33  4380.8  608.60
  4401.6  609.83  4409.6  609.80  4430.4  610.80  4573.0  609.61  4643.4  609.87
  4771.6  608.09  4942.9  606.90  4987.8  607.04  5005.7  606.27  5006.0  605.77
  5009.5  605.77  5009.7  606.27  5028.6  607.11  5200.3  609.11  5221.1  609.77
  5235.8  610.72  5244.1  613.06  5265.2  614.11  5279.6  614.17  5300.8  614.80
  5336.4  614.99  5432.1  619.56  5451.6  620.67  5522.7  623.17  5608.6  624.54
#Mann=5,-1,0
  3733.8   0.045       0  5005.7   0.045       0  5009.7   0.045       0
  5279.6   0.035       0  5432.1   0.045       0
Bank Sta=5005.7,5009.7
Exp/Cntr=0.3,0.1

Type RM Length L Ch R = 1,5560,465,465,465
BEGIN DESCRIPTION:
GUADALUPE TRIBUTARY 2A 11.0
END DESCRIPTION:
XS GIS Cut Line= 3
      2259275.03     13751024.98      2260125.00     13750225.00
      2260425.01     13749924.99
#Sta/Elev= 30
  3828.4  618.71  4040.6  614.97  4068.9  614.84  4160.7  613.36  4493.3  609.06
  4627.6  608.04  4698.4  606.80  4705.7  607.05  4748.2  606.44  4769.3  606.71
  4811.7  606.29  4846.9  606.74  4861.1  606.33  4939.2  605.62  4960.2  605.93
  4990.2  605.50  4990.4  605.00  4993.9  605.00  4994.2  605.50  5066.3  606.01
  5080.5  605.67  5108.8  605.83  5193.6  607.25  5250.2  609.15  5278.5  612.31
  5292.6  613.01  5306.8  612.98  5318.3  613.56  5391.6  615.49  5419.9  616.79
#Mann=4,-1,0
  3828.4   0.045       0  4990.2   0.045       0  4994.2   0.045       0
  5318.3   0.035       0
Bank Sta=4990.2,4994.2
Exp/Cntr=0.3,0.1

Type RM Length L Ch R = 1,5095,300,300,300
BEGIN DESCRIPTION:
GUADALUPE TRIBUTARY 2A 10.0
END DESCRIPTION:
XS GIS Cut Line= 3
      2259724.98     13750975.01      2260525.00     13750425.00
      2260575.00     13749875.01
#Sta/Elev= 30
  4024.8  613.69  4413.1  609.53  4578.9  606.19  4635.7  605.76  4665.5  604.65
  4724.4  604.39  4743.3  604.35  4752.1  604.86  4758.2  604.32  4770.9  605.06
  4801.5  605.06  4837.9  604.02  4880.6  603.64  4990.6  603.14  4990.9  602.64
  4994.4  602.64  4994.6  603.14  5035.8  604.05  5077.8  603.71  5146.3  604.49
  5216.5  607.54  5226.6  607.33  5256.7  609.09  5280.8  611.48  5306.9  611.59
  5317.0  612.29  5377.2  613.77  5441.5  616.79  5507.7  619.79  5547.9  620.66
#Mann=8,-1,0
  4024.8   0.045       0  4724.4    0.07       0  4770.9   0.045       0
  4990.6   0.045       0  4994.6   0.045       0  5077.8    0.07       0
  5280.8   0.035       0  5441.5   0.045       0
Bank Sta=4990.6,4994.6
Exp/Cntr=0.3,0.1

Type RM Length L Ch R = 1,4795,320,320,320
BEGIN DESCRIPTION:
GUADALUPE TRIBUTARY 2A 9.0
END DESCRIPTION:
XS GIS Cut Line= 3
      2260175.03     13750924.98      2260721.60     13750618.10
      2261075.01     13750124.99
#Sta/Elev= 30
  4267.7  608.58  4300.1  608.01  4451.3  605.01  4486.7  605.15  4512.7  603.96
  4561.8  603.14  4589.4  604.34  4627.0  602.43  4702.3  602.22  4714.9  603.41
  4724.0  602.22  4760.8  603.00  4791.5  601.50  4894.6  601.94  4912.7  601.49
  4927.6  600.28  4978.0  602.41  4992.7  602.15  5005.4  599.39  5005.7  598.89
  5009.4  599.39  5013.6  600.62  5028.3  601.72  5064.1  602.22  5179.4  604.18
  5221.2  607.06  5250.4  606.90  5321.9  607.58  5385.3  609.50  5501.2  611.35
#Mann=13,-1,0
  4267.7   0.035       0  4300.1    0.07       0  4451.3    0.12       0
  4512.7    0.07       0  4561.8    0.12       0  4791.5    0.07       0
  4894.6   0.045       0  4912.7    0.07       0  5005.4    0.05       0
  5009.4    0.07       0  5064.1   0.045       0  5250.4   0.035       0
  5385.3    0.07       0
Bank Sta=5005.4,5009.4
Exp/Cntr=0.3,0.1

Type RM Length L Ch R = 1,4475,398,398,398
BEGIN DESCRIPTION:
A19327
END DESCRIPTION:
XS GIS Cut Line= 3
      2260315.63     13751071.59      2260790.71     13750851.32
      2261369.44     13750406.48
#Sta/Elev= 30
  4371.2  607.15  4414.0  606.14  4478.6  604.38  4601.1  603.14  4661.4  602.42
  4678.8  604.28  4684.3  603.77  4690.2  605.01  4707.3  601.91  4711.1  602.96
  4712.8  603.43  4723.2  601.06  4730.2  600.46  4751.7  601.50  4781.5  601.78
  4798.9  600.50  4804.4  601.22  4811.4  599.83  4821.2  599.21  4999.5  596.41
  4999.7  595.91  5003.5  596.41  5030.5  598.63  5162.6  600.85  5202.7  600.64
  5364.2  602.81  5402.1  604.50  5422.9  603.49  5522.6  604.84  5624.8  604.75
#Mann=11,-1,0
  4371.2    0.07       0  4414.0    0.12       0  4478.6    0.07       0
  4601.1    0.12       0  4711.1    0.07       0  4751.7    0.12       0
  4821.2   0.035       0  4999.5   0.035       0  5003.5   0.035       0
  5162.6    0.07       0  5364.2   0.035       0
Bank Sta=4999.5,5003.5
Exp/Cntr=0.3,0.1

Type RM Length L Ch R = 1,4077,246,246,246
BEGIN DESCRIPTION:
GUADALUPE TRIBUTARY 2A 8.0
END DESCRIPTION:
XS GIS Cut Line= 3
      2260479.76     13751222.75      2261028.25     13751136.38
      2261550.40     13750622.85
#Sta/Elev= 30
  4439.2  603.82  4458.3  604.24  4485.0  602.60  4554.1  601.59  4577.0  601.26
  4690.0  600.07  4980.3  596.13  5005.2  595.66  5005.5  595.16  5009.0  595.16
  5009.2  595.66  5042.6  597.09  5106.2  597.38  5127.5  598.53  5169.9  597.95
  5205.2  597.99  5212.4  598.47  5240.7  597.89  5332.5  597.65  5445.7  598.91
  5459.8  598.54  5474.0  599.23  5530.5  599.29  5551.7  599.89  5564.9  601.19
  5594.1  602.46  5615.4  601.54  5650.7  602.19  5694.0  601.87  5726.8  602.34
#Mann=9,-1,0
  4439.2   0.035       0  4554.1    0.07       0  4577.0   0.035       0
  4690.0   0.045       0  4980.3    0.07       0  5005.2    0.05       0
  5009.2    0.07       0  5564.9   0.035       0  5694.0    0.07       0
Bank Sta=5005.2,5009.2
Exp/Cntr=0.3,0.1

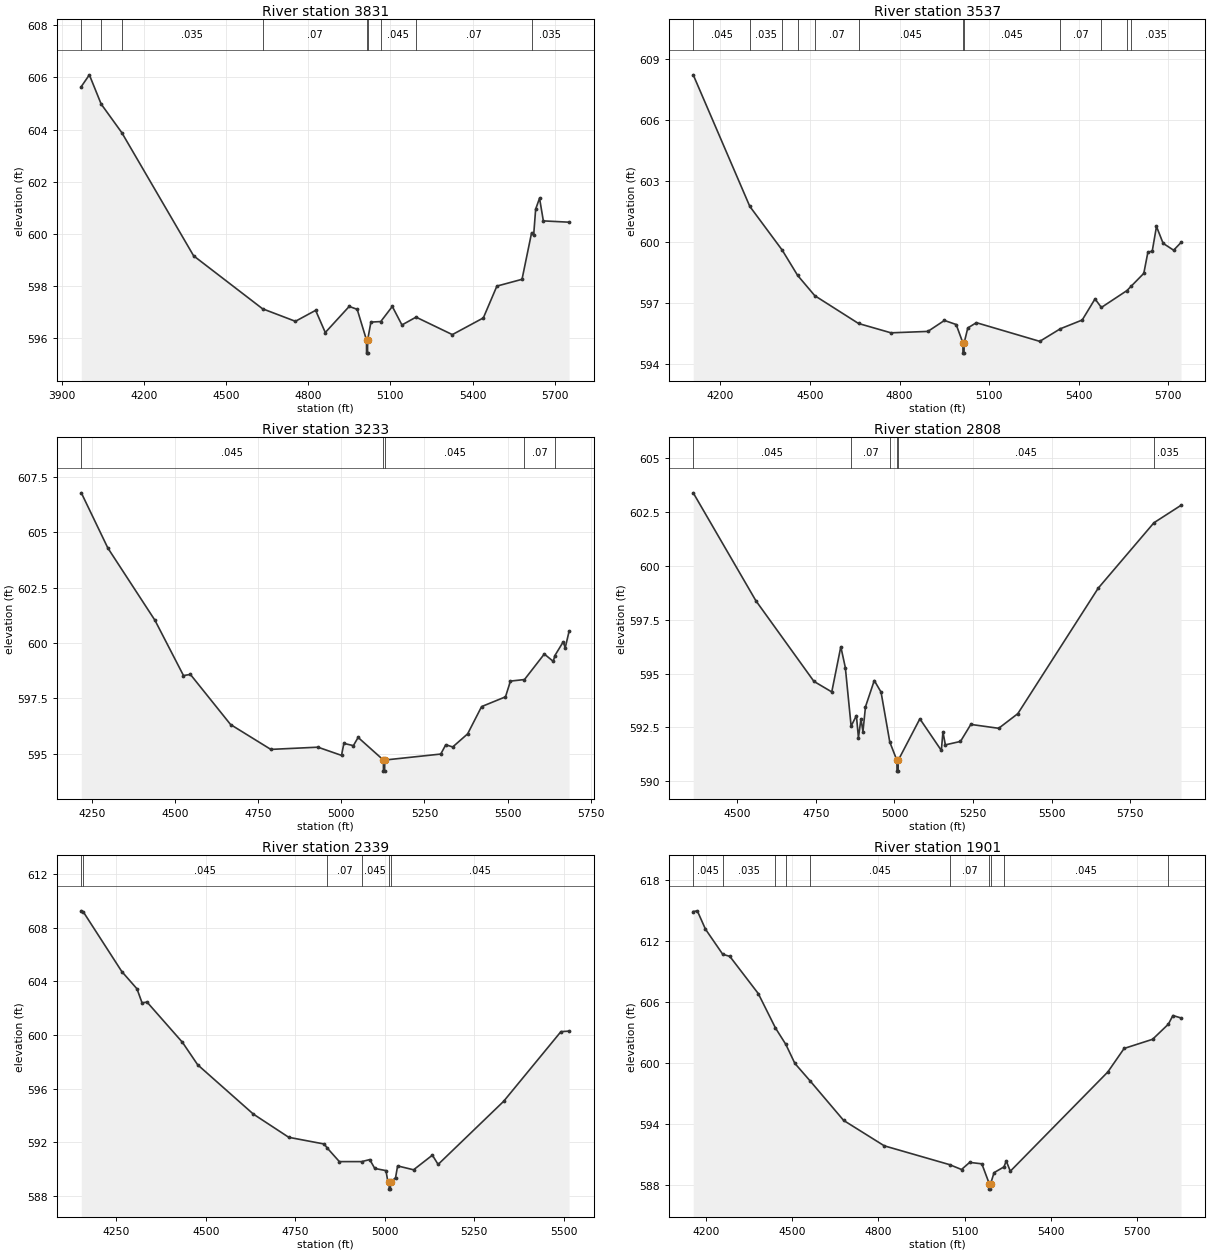
Type RM Length L Ch R = 1,3831,294,294,294
BEGIN DESCRIPTION:
A19326
END DESCRIPTION:
XS GIS Cut Line= 3
      2260678.41     13752190.20      2261209.65     13751300.50
      2261719.28     13750756.31
#Sta/Elev= 30
  3970.9  605.65  4000.3  606.10  4043.4  604.98  4119.0  603.88  4381.2  599.16
  4633.0  597.13  4752.9  596.65  4826.8  597.07  4862.1  596.22  4949.4  597.22
  4978.6  597.11  5012.7  595.93  5012.9  595.43  5016.4  595.43  5016.7  595.93
  5028.8  596.62  5064.7  596.64  5106.9  597.22  5142.1  596.51  5193.6  596.81
  5326.2  596.14  5439.4  596.78  5488.9  598.00  5580.7  598.26  5615.8  600.05
  5623.2  599.95  5630.5  600.95  5644.7  601.37  5658.6  600.50  5752.7  600.45
#Mann=9,-1,0
  3970.9   0.045       0  4043.4    0.07       0  4119.0   0.035       0
  4633.0    0.07       0  5012.7    0.05       0  5016.7    0.07       0
  5064.7   0.045       0  5193.6    0.07       0  5615.8   0.035       0
Bank Sta=5012.7,5016.7
Exp/Cntr=0.3,0.1

Type RM Length L Ch R = 1,3537,304,304,304
BEGIN DESCRIPTION:
GUADALUPE TRIBUTARY 2A 7.0
END DESCRIPTION:
XS GIS Cut Line= 3
      2261024.99     13752275.01      2261425.59     13751490.53
      2261903.99     13750908.70
#Sta/Elev= 30
  4108.8  608.24  4298.3  601.76  4407.1  599.60  4458.5  598.36  4516.0  597.36
  4662.6  595.99  4771.3  595.53  4894.9  595.60  4950.3  596.14  4989.6  595.94
  5012.3  595.03  5012.5  594.53  5016.0  594.53  5016.3  595.03  5028.6  595.77
  5057.3  596.03  5269.7  595.11  5338.6  595.73  5411.8  596.16  5454.8  597.20
  5476.1  596.78  5561.6  597.61  5575.5  597.82  5618.2  598.46  5632.0  599.51
  5646.4  599.55  5660.7  600.77  5682.9  599.94  5718.1  599.60  5742.9  599.98
#Mann=12,-1,0
  4108.8   0.045       0  4298.3   0.035       0  4407.1    0.07       0
  4458.5   0.035       0  4516.0    0.07       0  4662.6   0.045       0
  5012.3   0.045       0  5016.3   0.045       0  5338.6    0.07       0
  5476.1   0.045       0  5561.6    0.07       0  5575.5   0.035       0
Bank Sta=5012.3,5016.3
Exp/Cntr=0.3,0.1

Type RM Length L Ch R = 1,3233,425,425,425
BEGIN DESCRIPTION:
A19324
END DESCRIPTION:
XS GIS Cut Line= 3
      2261157.79     13752260.15      2261808.85     13751496.23
      2262069.27     13751114.29
#Sta/Elev= 30
  4218.9  606.77  4298.7  604.28  4440.3  601.02  4526.0  598.53  4546.8  598.58
  4667.6  596.32  4788.4  595.20  4930.0  595.30  5000.9  594.93  5008.0  595.47
  5036.6  595.37  5050.8  595.74  5126.8  594.72  5127.0  594.22  5130.5  594.22
  5130.8  594.72  5299.2  594.99  5314.2  595.41  5335.1  595.31  5379.9  595.90
  5421.9  597.13  5493.7  597.57  5508.6  598.28  5550.8  598.35  5610.3  599.50
  5637.3  599.17  5642.1  599.43  5667.2  600.05  5673.2  599.78  5684.9  600.53
#Mann=5,-1,0
  4218.9   0.045       0  5126.8   0.045       0  5130.8   0.045       0
  5550.8    0.07       0  5642.1   0.035       0
Bank Sta=5126.8,5130.8
Exp/Cntr=0.3,0.1

Type RM Length L Ch R = 1,2808,469,469,469
BEGIN DESCRIPTION:
GUADALUPE TRIBUTARY 2A 6.0
END DESCRIPTION:
XS GIS Cut Line= 3
      2261575.00     13752325.00      2261975.00     13751825.00
      2262874.98     13751675.00
#Sta/Elev= 30
  4359.4  603.40  4558.7  598.39  4743.6  594.64  4800.4  594.15  4829.2  596.25
  4843.6  595.28  4862.0  592.56  4878.8  593.05  4885.3  592.02  4893.3  592.90
  4899.7  592.31  4907.7  593.46  4935.7  594.68  4957.3  594.14  4985.1  591.82
  5007.8  590.97  5008.1  590.47  5011.6  590.47  5011.8  590.97  5080.8  592.90
  5149.2  591.43  5154.3  592.30  5161.9  591.69  5210.1  591.85  5243.0  592.64
  5331.7  592.46  5392.6  593.14  5648.5  598.97  5825.9  602.01  5912.1  602.82
#Mann=6,-1,0
  4359.4   0.045       0  4862.0    0.07       0  4985.1   0.045       0
  5007.8   0.045       0  5011.8   0.045       0  5825.9   0.035       0
Bank Sta=5007.8,5011.8
Exp/Cntr=0.3,0.1

Type RM Length L Ch R = 1,2339,438,438,438
BEGIN DESCRIPTION:
GUADALUPE TRIBUTARY 2A 5.0
END DESCRIPTION:
XS GIS Cut Line= 3
      2261725.01     13752724.99      2262325.00     13752125.00
      2262775.00     13751875.00
#Sta/Elev= 30
  4151.7  609.25  4157.6  609.16  4264.8  604.73  4307.3  603.44  4321.4  602.40
  4335.5  602.45  4434.5  599.45  4477.0  597.78  4632.5  594.11  4731.5  592.38
  4830.5  591.88  4839.1  591.58  4872.9  590.57  4935.3  590.57  4957.8  590.72
  4971.9  590.06  5003.1  589.90  5008.2  589.12  5011.9  589.02  5012.2  588.52
  5015.7  588.52  5015.9  589.02  5030.0  589.38  5035.7  590.25  5080.3  589.96
  5132.9  591.05  5148.9  590.36  5332.0  595.06  5492.1  600.25  5515.0  600.29
#Mann=6,-1,0
  4151.7   0.035       0  4157.6   0.045       0  4839.1    0.07       0
  4935.3   0.045       0  5011.9   0.045       0  5015.9   0.045       0
Bank Sta=5011.9,5015.9
Exp/Cntr=0.3,0.1

Type RM Length L Ch R = 1,1901,456,456,456
BEGIN DESCRIPTION:
GUADALUPE TRIBUTARY 2A 4.0
END DESCRIPTION:
XS GIS Cut Line= 3
      2261824.97     13753025.03      2262425.00     13752425.00
      2263025.00     13751825.00
#Sta/Elev= 30
  4156.0  614.89  4170.2  614.96  4198.5  613.16  4258.8  610.68  4283.3  610.48
  4382.3  606.82  4442.2  603.43  4478.2  601.82  4509.6  599.95  4563.2  598.21
  4679.3  594.34  4820.7  591.84  5047.8  589.99  5089.4  589.51  5117.7  590.21
  5160.1  590.07  5186.4  588.08  5186.7  587.58  5190.2  587.58  5190.4  588.08
  5202.6  589.20  5237.2  589.77  5245.0  590.36  5259.1  589.34  5598.5  599.11
  5655.1  601.42  5754.1  602.32  5809.1  603.81  5824.8  604.66  5853.1  604.42
#Mann=10,-1,0
  4156.0   0.045       0  4258.8   0.035       0  4442.2   0.045       0
  4478.2   0.035       0  4563.2   0.045       0  5047.8    0.07       0
  5186.4   0.045       0  5190.4    0.07       0  5237.2   0.045       0
  5809.1   0.035       0
Bank Sta=5186.4,5190.4
Exp/Cntr=0.3,0.1

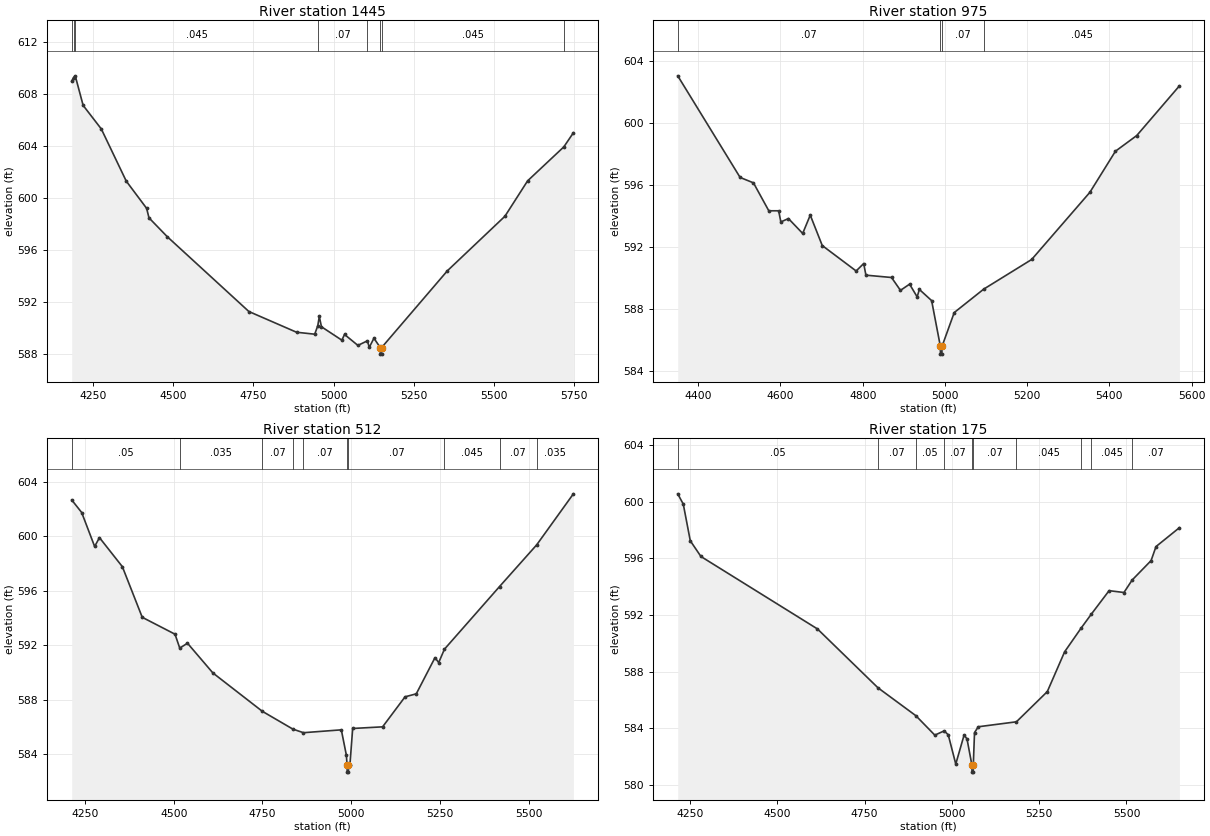
Type RM Length L Ch R = 1,1445,470,470,470
BEGIN DESCRIPTION:
GUADALUPE TRIBUTARY 2A 3.0
END DESCRIPTION:
XS GIS Cut Line= 3
      2262125.00     13753125.00      2262675.00     13752525.00
      2263124.97     13751925.04
#Sta/Elev= 30
  4183.9  608.98  4189.4  609.25  4194.8  609.38  4219.4  607.11  4276.1  605.30
  4353.8  601.30  4417.3  599.21  4424.7  598.48  4481.4  597.04  4736.1  591.29
  4884.7  589.70  4941.4  589.55  4951.0  590.21  4955.6  590.91  4962.4  590.12
  5026.0  589.09  5034.3  589.53  5076.0  588.69  5105.6  589.04  5111.4  588.54
  5126.0  589.24  5145.8  588.52  5146.1  588.02  5149.6  588.02  5149.8  588.52
  5355.1  594.42  5534.3  598.60  5605.1  601.32  5718.1  603.93  5747.8  605.01
#Mann=8,-1,0
  4183.9   0.045       0  4189.4   0.035       0  4194.8   0.045       0
  4951.0    0.07       0  5105.6   0.045       0  5145.8    0.05       0
  5149.8   0.045       0  5718.1   0.035       0
Bank Sta=5145.8,5149.8
Exp/Cntr=0.3,0.1

Type RM Length L Ch R = 1,975,463,463,463
BEGIN DESCRIPTION:
GUADALUPE TRIBUTARY 2A 2.0
END DESCRIPTION:
XS GIS Cut Line= 3
      2262825.00     13753224.99      2263075.00     13752625.00
      2263225.01     13752074.98
#Sta/Elev= 30
  4350.1  603.02  4501.8  596.47  4534.3  596.12  4571.6  594.32  4595.5  594.32
  4600.9  593.60  4619.3  593.82  4654.0  592.86  4672.4  594.04  4701.6  592.08
  4784.0  590.44  4802.4  590.92  4807.8  590.17  4870.1  590.02  4891.8  589.19
  4914.0  589.59  4932.4  588.77  4937.8  589.25  4967.6  588.53  4988.9  585.58
  4989.1  585.08  4992.6  585.08  4992.9  585.58  5022.6  587.76  5094.3  589.27
  5210.9  591.18  5352.5  595.51  5414.7  598.16  5466.5  599.17  5570.2  602.37
#Mann=4,-1,0
  4350.1    0.07       0  4988.9    0.05       0  4992.9    0.07       0
  5094.3   0.045       0
Bank Sta=4988.9,4992.9
Exp/Cntr=0.3,0.1

Type RM Length L Ch R = 1,512,337,337,337
BEGIN DESCRIPTION:
GUADALUPE TRIBUTARY 2A 1.0
END DESCRIPTION:
XS GIS Cut Line= 3
      2263024.97     13753275.03      2263525.00     13752675.00
      2263325.01     13752075.02
#Sta/Elev= 30
  4212.6  602.65  4240.6  601.73  4277.1  599.24  4290.7  599.89  4355.2  597.76
  4411.2  594.05  4503.6  592.81  4516.9  591.79  4538.7  592.15  4610.3  589.97
  4749.5  587.16  4835.9  585.85  4865.5  585.59  4972.2  585.80  4986.5  583.93
  4988.4  583.20  4988.7  582.70  4992.2  582.70  4992.4  583.20  4996.3  583.20
  5004.2  585.90  5088.5  586.02  5151.8  588.22  5183.4  588.44  5236.1  591.09
  5246.6  590.73  5262.7  591.71  5417.9  596.30  5522.7  599.36  5626.1  603.10
#Mann=10,-1,0
  4212.6    0.05       0  4516.9   0.035       0  4749.5    0.07       0
  4835.9   0.035       0  4865.5    0.07       0  4988.4    0.05       0
  4992.4    0.07       0  5262.7   0.045       0  5417.9    0.07       0
  5522.7   0.035       0
Bank Sta=4988.4,4992.4
Exp/Cntr=0.3,0.1

Type RM Length L Ch R = 1,175,0,0,0
BEGIN DESCRIPTION:
A19323
END DESCRIPTION:
XS GIS Cut Line= 4
      2263814.06     13753440.70      2263900.87     13752850.40
      2263770.66     13752520.54      2263423.46     13752182.02
#Sta/Elev= 30
  4215.2  600.55  4231.1  599.82  4251.1  597.24  4281.6  596.13  4615.2  591.02
  4788.4  586.87  4897.0  584.90  4951.2  583.53  4978.1  583.83  4989.7  583.55
  5011.2  581.49  5035.1  583.54  5043.4  583.26  5057.4  581.42  5057.7  580.92
  5061.2  580.92  5061.4  581.42  5064.9  583.71  5075.7  584.12  5184.9  584.47
  5273.3  586.60  5322.9  589.41  5370.4  591.09  5399.5  592.07  5450.2  593.72
  5492.7  593.59  5516.2  594.47  5570.4  595.84  5584.5  596.83  5651.4  598.16
#Mann=10,-1,0
  4215.2    0.05       0  4788.4    0.07       0  4897.0    0.05       0
  4978.1    0.07       0  5057.4    0.05       0  5061.4    0.07       0
  5184.9   0.045       0  5370.4    0.07       0  5399.5   0.045       0
  5516.2    0.07       0
Bank Sta=5057.4,5061.4
Exp/Cntr=0.3,0.1

Chan Stop Cuts=-1