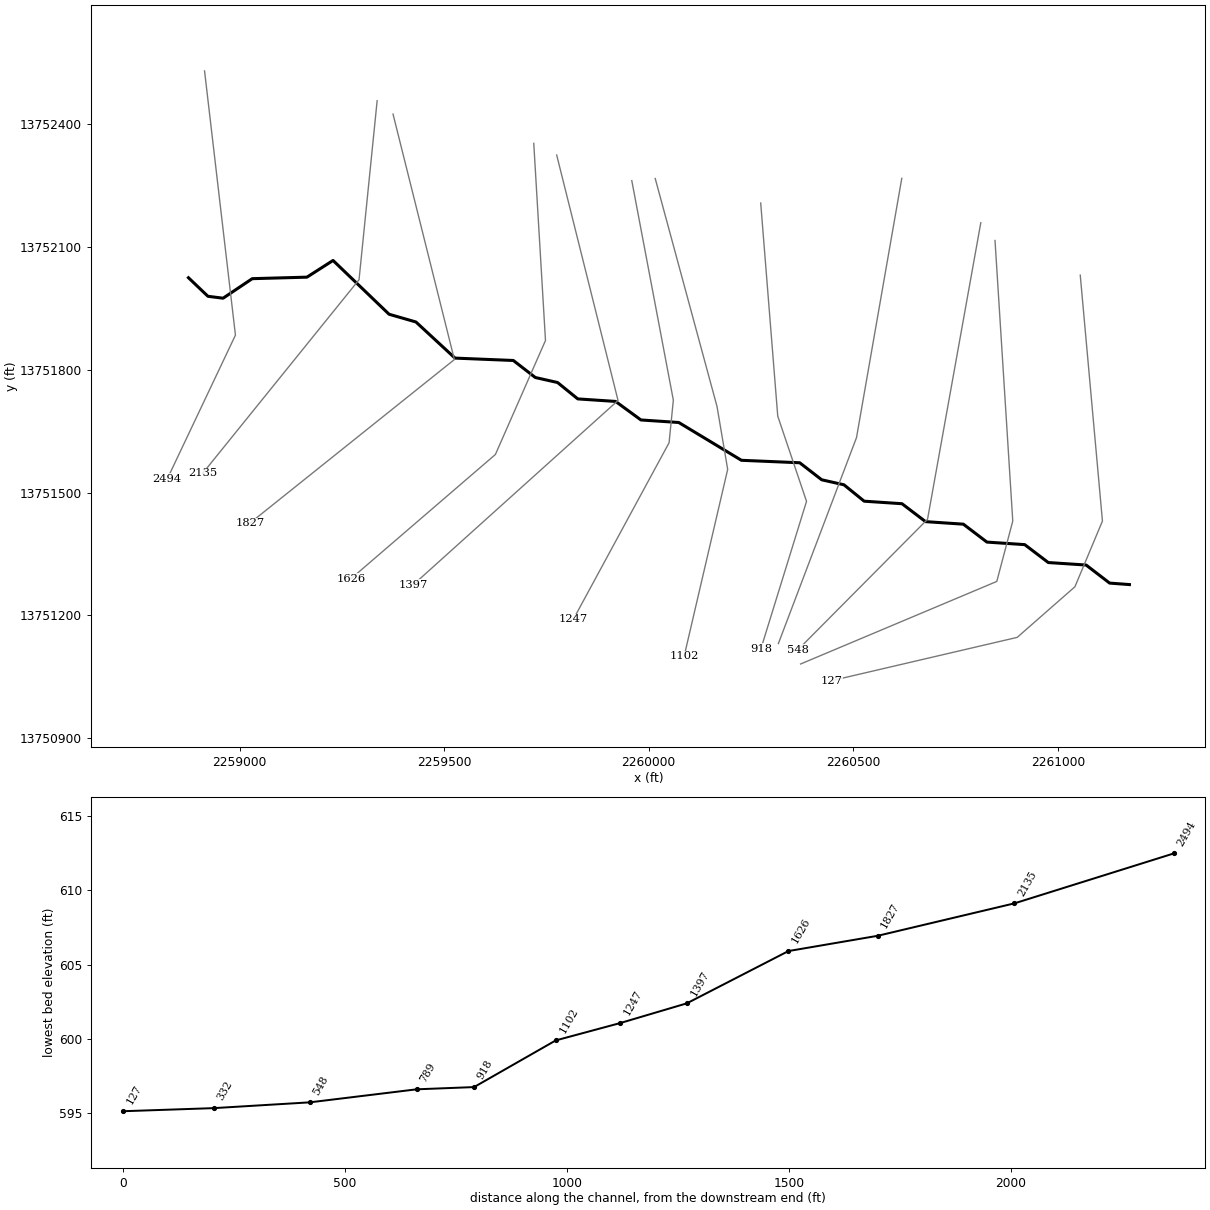
--- GUADALUPE TRIBUTARY 2C.prj (project) ---

Proj Title=GUADALUPE TRIBUTARY 2C Base Level Engineering
Current Plan=p01
Default Exp/Contr=0.3,0.1
English Units
Geom File=g01
Flow File=f01
Plan File=p01
BEGIN DESCRIPTION:
GUADALUPE TRIBUTARY 2C
END DESCRIPTION:

--- GUADALUPE TRIBUTARY 2C.p01 (plan) ---

Plan Title=Multiple Run
Short Identifier=Multiple
Geom File=g01
Flow File=f01
Subcritical Flow
K Sum by GR= 0
Std Step Tol= 0.01
Critical Tol= 0.01
Num of Std Step Trials= 20
Max Error Tol= 0.3
Flow Tol Ratio= 0.001
Split Flow NTrial= 30
Split Flow Tol= 0.02
Split Flow Ratio= 0.02
Log Output Level= 0
Friction Slope Method= 1
Unsteady Friction Slope Method= 2
Unsteady Bridges Friction Slope Method= 1
Parabolic Critical Depth
Global Vel Dist=  1 , 1 , 1
Global Log Level= 0
CheckData=True
Encroach Param= -1, 0, 0, 0
BEGIN DESCRIPTION:
Multiple Run
END DESCRIPTION:

--- GUADALUPE TRIBUTARY 2C.f01 (steady flow) ---

Flow Title=Multiple
Number of Profiles=7
Profile Names=10-year,25-year,50-year,1pct_min,100-year,1pct_plu,500-year
River Rch & RM= GUADALUPE TRIBUT,Reach-1,2494
     247     374     482     302     602    1201     925
Boundary for River Rch & Prof#=GUADALUPE TRIBUT,Reach-1,1
Up Type=0
Dn Type=3
Dn Slope=0.005
Boundary for River Rch & Prof#=GUADALUPE TRIBUT,Reach-1,2
Up Type=0
Dn Type=3
Dn Slope=0.005
Boundary for River Rch & Prof#=GUADALUPE TRIBUT,Reach-1,3
Up Type=0
Dn Type=3
Dn Slope=0.005
Boundary for River Rch & Prof#=GUADALUPE TRIBUT,Reach-1,4
Up Type=0
Dn Type=3
Dn Slope=0.005
Boundary for River Rch & Prof#=GUADALUPE TRIBUT,Reach-1,5
Up Type=0
Dn Type=3
Dn Slope=0.005
Boundary for River Rch & Prof#=GUADALUPE TRIBUT,Reach-1,6
Up Type=0
Dn Type=3
Dn Slope=0.005
Boundary for River Rch & Prof#=GUADALUPE TRIBUT,Reach-1,7
Up Type=0
Dn Type=3
Dn Slope=0.005

--- GUADALUPE TRIBUTARY 2C.g01 (geometry) ---

Geom Title=Existing Conditions

River Reach=GUADALUPE TRIBUT,Reach-1
Reach XY= 30
      2258875.00     13752025.00      2258922.63     13751979.61
      2258959.67     13751974.97      2259030.93     13752022.72
      2259164.56     13752026.40      2259228.42     13752067.21
      2259365.32     13751935.78      2259431.04     13751916.82
      2259526.47     13751828.55      2259669.07     13751822.75
      2259722.82     13751781.12      2259777.18     13751768.89
      2259826.58     13751728.83      2259919.03     13751722.65
      2259980.97     13751677.35      2260073.42     13751671.17
      2260226.56     13751578.76      2260369.07     13751572.75
      2260422.82     13751531.12      2260477.18     13751518.89
      2260526.58     13751478.83      2260619.03     13751472.65
      2260676.60     13751428.85      2260769.03     13751422.65
      2260826.60     13751378.85      2260919.03     13751372.65
      2260976.60     13751328.85      2261069.08     13751322.77
      2261126.51     13751278.64      2261175.00     13751275.00

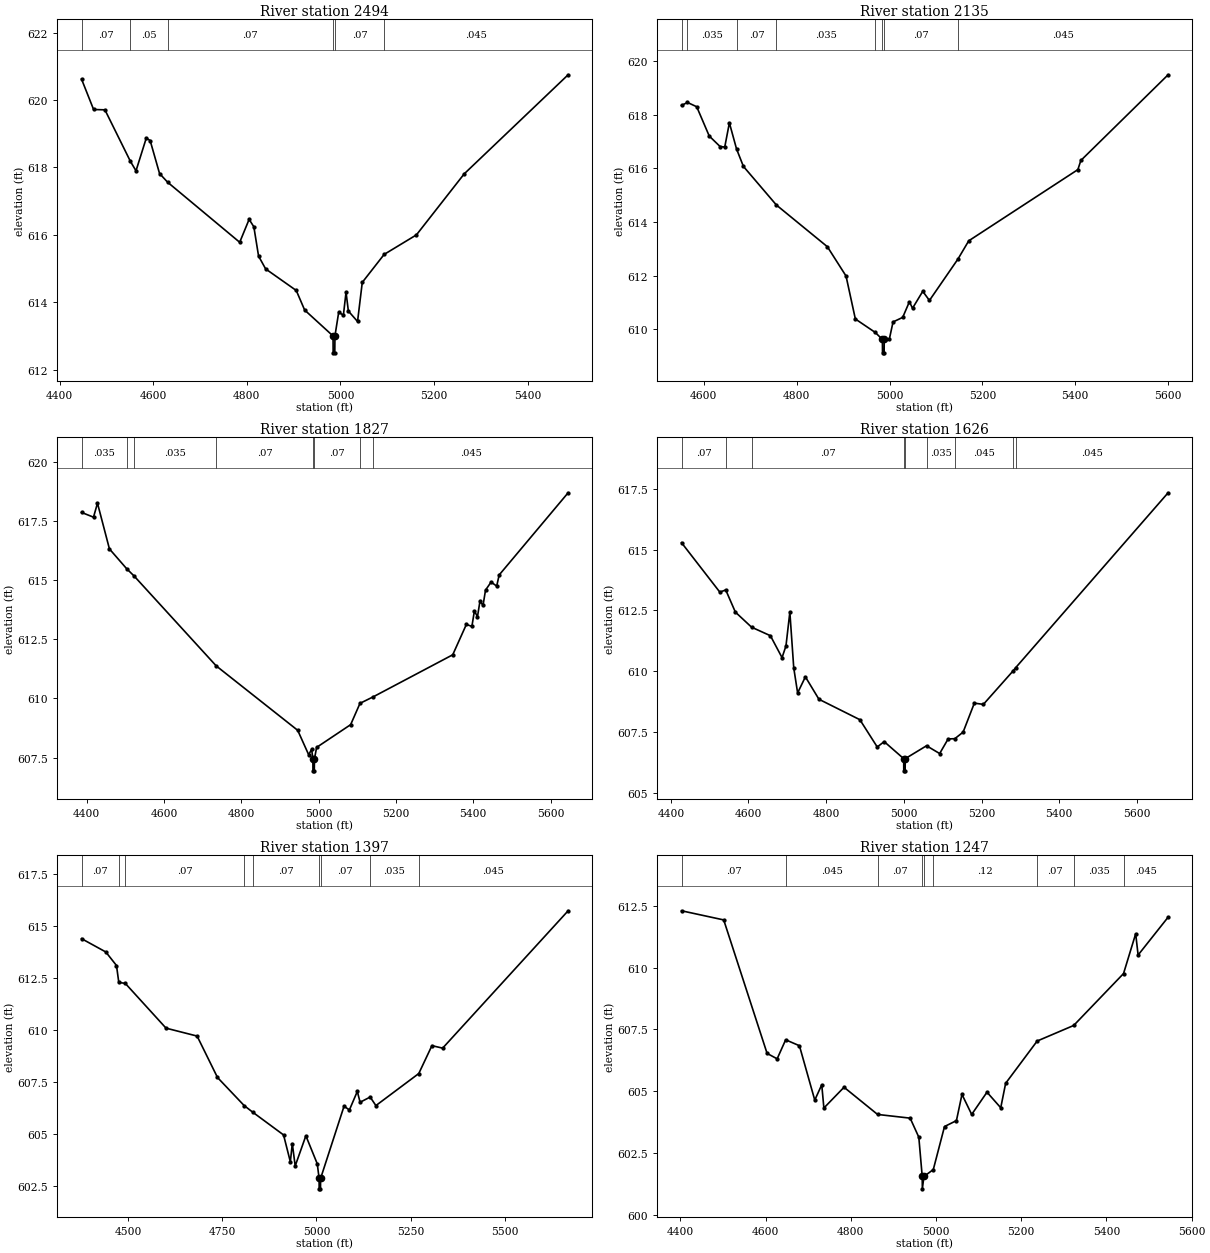
Type RM Length L Ch R = 1,2494,359,359,359
BEGIN DESCRIPTION:
A19340
END DESCRIPTION:
XS GIS Cut Line= 3
      2258914.32     13752530.51      2258989.84     13751884.68
      2258823.18     13751533.11
#Sta/Elev= 30
  4447.0  620.62  4472.7  619.72  4496.9  619.71  4551.4  618.18  4563.3  617.90
  4585.2  618.87  4593.5  618.80  4613.6  617.82  4631.0  617.56  4784.8  615.78
  4804.9  616.46  4815.0  616.24  4825.1  615.37  4840.2  614.99  4905.6  614.35
  4923.5  613.77  4984.2  613.00  4984.4  612.50  4987.9  612.50  4988.2  613.00
  4996.2  613.70  5006.3  613.62  5011.9  614.30  5016.9  613.74  5036.5  613.43
  5046.6  614.59  5093.3  615.42  5162.3  616.00  5264.3  617.81  5486.3  620.75
#Mann=6,-1,0
  4447.0    0.07       0  4551.4    0.05       0  4631.0    0.07       0
  4984.2    0.05       0  4988.2    0.07       0  5093.3   0.045       0
Bank Sta=4984.2,4988.2
Exp/Cntr=0.3,0.1

Type RM Length L Ch R = 1,2135,308,308,308
BEGIN DESCRIPTION:
GUADALUPE TRIBUTARY 2C 5.0
END DESCRIPTION:
XS GIS Cut Line= 3
      2259336.20     13752457.58      2259291.93     13752020.10
      2258909.53     13751546.66
#Sta/Elev= 30
  4551.9  618.34  4564.7  618.45  4584.6  618.29  4611.6  617.20  4634.9  616.81
  4645.0  616.79  4655.0  617.69  4670.4  616.72  4685.2  616.07  4756.4  614.63
  4866.1  613.08  4906.3  611.99  4926.4  610.39  4969.2  609.89  4984.6  609.63
  4984.9  609.13  4988.4  609.13  4988.6  609.63  4999.6  609.64  5007.6  610.28
  5028.4  610.45  5042.8  611.03  5049.6  610.79  5071.6  611.42  5086.0  611.08
  5147.4  612.62  5170.7  613.30  5405.8  615.95  5412.2  616.29  5600.2  619.48
#Mann=8,-1,0
  4551.9    0.07       0  4564.7   0.035       0  4670.4    0.07       0
  4756.4   0.035       0  4969.2    0.07       0  4984.6    0.05       0
  4988.6    0.07       0  5147.4   0.045       0
Bank Sta=4984.6,4988.6
Exp/Cntr=0.3,0.1

Type RM Length L Ch R = 1,1827,201,201,201
BEGIN DESCRIPTION:
GUADALUPE TRIBUTARY 2C 4.0
END DESCRIPTION:
XS GIS Cut Line= 3
      2259375.01     13752424.96      2259525.00     13751825.00
      2259025.03     13751425.03
#Sta/Elev= 30
  4386.6  617.85  4417.5  617.65  4427.8  618.24  4458.7  616.31  4503.5  615.47
  4522.3  615.17  4735.0  611.37  4945.8  608.65  4974.1  607.62  4981.8  607.85
  4985.0  607.44  4985.2  606.94  4988.7  606.94  4989.0  607.44  4994.7  607.93
  5082.7  608.89  5106.9  609.79  5141.7  610.07  5346.8  611.84  5382.0  613.12
  5396.4  613.04  5402.8  613.69  5410.8  613.45  5417.2  614.10  5425.2  613.93
  5431.6  614.57  5446.0  614.91  5460.5  614.74  5466.9  615.21  5645.3  618.68
#Mann=8,-1,0
  4386.6   0.035       0  4503.5    0.07       0  4522.3   0.035       0
  4735.0    0.07       0  4985.0    0.05       0  4989.0    0.07       0
  5106.9   0.035       0  5141.7   0.045       0
Bank Sta=4985,4989
Exp/Cntr=0.3,0.1

Type RM Length L Ch R = 1,1626,229,229,229
BEGIN DESCRIPTION:
A19339
END DESCRIPTION:
XS GIS Cut Line= 4
      2259719.01     13752353.39      2259747.66     13751871.66
      2259625.26     13751593.01      2259272.09     13751289.18
#Sta/Elev= 30
  4427.6  615.28  4526.2  613.25  4541.4  613.34  4566.2  612.43  4607.9  611.81
  4656.4  611.46  4686.4  610.56  4696.5  611.04  4706.5  612.43  4716.5  610.14
  4726.5  609.11  4746.5  609.77  4781.4  608.85  4886.8  608.01  4931.5  606.89
  4949.4  607.11  4999.6  606.41  4999.8  605.91  5003.3  605.91  5003.6  606.41
  5058.4  606.94  5092.2  606.62  5114.0  607.22  5131.2  607.23  5152.6  607.50
  5181.5  608.69  5204.8  608.64  5280.5  610.00  5287.6  610.14  5680.4  617.33
#Mann=9,-1,0
  4427.6    0.07       0  4541.4   0.035       0  4607.9    0.07       0
  4999.6    0.05       0  5003.6    0.07       0  5058.4   0.035       0
  5131.2   0.045       0  5280.5   0.035       0  5287.6   0.045       0
Bank Sta=4999.6,5003.6
Exp/Cntr=0.3,0.1

Type RM Length L Ch R = 1,1397,150,150,150
BEGIN DESCRIPTION:
GUADALUPE TRIBUTARY 2C 3.0
END DESCRIPTION:
XS GIS Cut Line= 3
      2259775.01     13752324.97      2259925.00     13751725.00
      2259425.01     13751275.01
#Sta/Elev= 30
  4376.8  614.40  4441.2  613.76  4469.5  613.11  4475.6  612.30  4492.9  612.25
  4601.0  610.10  4683.4  609.72  4737.5  607.73  4808.3  606.38  4830.5  606.07
  4912.8  604.97  4930.8  603.68  4936.0  604.55  4943.7  603.48  4972.0  604.93
  5002.3  603.58  5007.1  602.88  5007.3  602.38  5010.8  602.38  5011.1  602.88
  5073.3  606.35  5087.5  606.17  5108.5  607.06  5115.9  606.54  5142.6  606.79
  5157.8  606.38  5271.6  607.92  5306.5  609.26  5334.9  609.14  5667.9  615.74
#Mann=9,-1,0
  4376.8    0.07       0  4475.6   0.035       0  4492.9    0.07       0
  4808.3   0.045       0  4830.5    0.07       0  5007.1    0.05       0
  5011.1    0.07       0  5142.6   0.035       0  5271.6   0.045       0
Bank Sta=5007.1,5011.1
Exp/Cntr=0.3,0.1

Type RM Length L Ch R = 1,1247,145,145,145
BEGIN DESCRIPTION:
A19338
END DESCRIPTION:
XS GIS Cut Line= 4
      2259958.60     13752262.27      2260060.16     13751725.82
      2260049.74     13751621.66      2259815.56     13751189.72
#Sta/Elev= 30
  4402.7  612.30  4501.7  611.93  4603.5  606.53  4627.1  606.31  4647.1  607.08
  4679.4  606.84  4715.4  604.64  4731.8  605.26  4736.8  604.32  4784.1  605.16
  4862.8  604.06  4939.3  603.91  4959.6  603.14  4967.6  601.55  4967.9  601.05
  4971.6  601.55  4993.6  601.83  5019.9  603.57  5047.9  603.81  5060.9  604.87
  5083.7  604.06  5119.6  604.96  5151.9  604.33  5163.4  605.32  5237.4  607.03
  5323.1  607.66  5440.1  609.76  5468.6  611.37  5474.3  610.51  5544.7  612.04
#Mann=9,-1,0
  4402.7    0.07       0  4647.1   0.045       0  4862.8    0.07       0
  4967.6    0.05       0  4971.6    0.07       0  4993.6    0.12       0
  5237.4    0.07       0  5323.1   0.035       0  5440.1   0.045       0
Bank Sta=4967.6,4971.6
Exp/Cntr=0.3,0.1

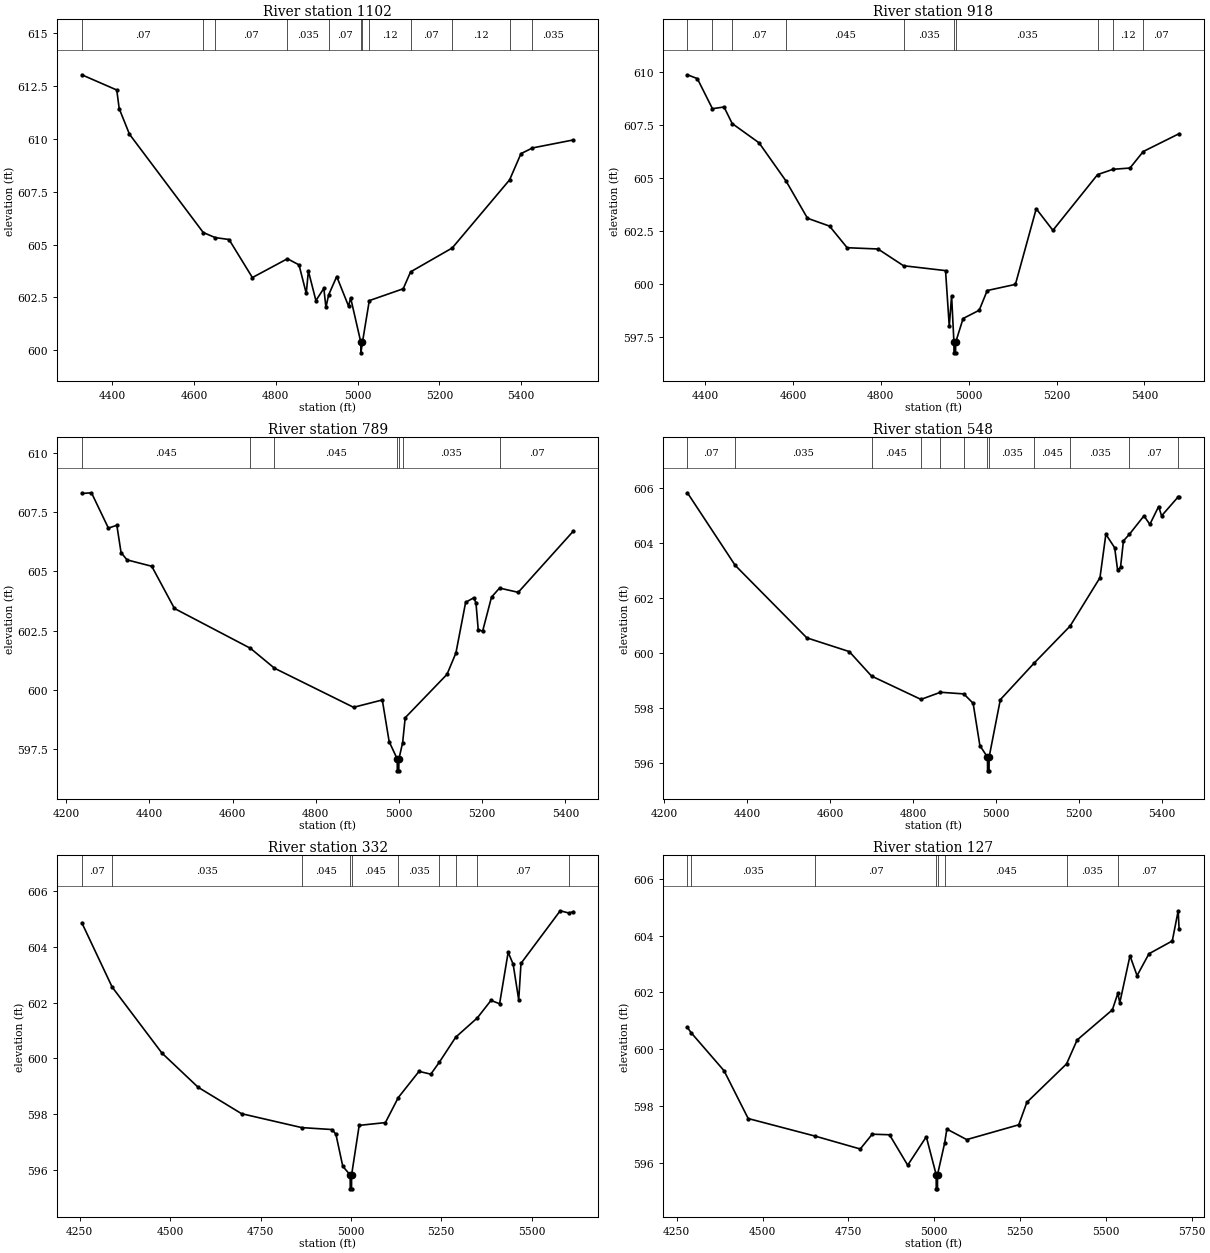
Type RM Length L Ch R = 1,1102,184,184,184
BEGIN DESCRIPTION:
A19337
END DESCRIPTION:
XS GIS Cut Line= 4
      2260015.89     13752267.47      2260166.93     13751710.20
      2260192.97     13751556.55      2260086.61     13751099.99
#Sta/Elev= 30
  4326.0  613.03  4411.4  612.31  4417.4  611.43  4442.5  610.22  4622.9  605.57
  4652.1  605.33  4685.9  605.24  4743.0  603.44  4828.7  604.33  4857.0  604.04
  4874.7  602.69  4879.9  603.75  4898.3  602.35  4917.7  602.93  4922.8  602.03
  4929.4  602.62  4949.2  603.49  4978.1  602.09  4983.2  602.48  5008.1  600.38
  5008.3  599.88  5012.1  600.38  5028.8  602.35  5111.7  602.91  5129.8  603.71
  5231.6  604.84  5371.8  608.06  5399.6  609.30  5427.7  609.57  5528.0  609.95
#Mann=12,-1,0
  4326.0    0.07       0  4622.9   0.045       0  4652.1    0.07       0
  4828.7   0.035       0  4929.4    0.07       0  5008.1    0.05       0
  5012.1    0.07       0  5028.8    0.12       0  5129.8    0.07       0
  5231.6    0.12       0  5371.8    0.07       0  5427.7   0.035       0
Bank Sta=5008.1,5012.1
Exp/Cntr=0.3,0.1

Type RM Length L Ch R = 1,918,129,129,129
BEGIN DESCRIPTION:
A19336
END DESCRIPTION:
XS GIS Cut Line= 4
      2260273.70     13752207.57      2260315.36     13751686.76
      2260385.68     13751478.43      2260274.24     13751118.22
#Sta/Elev= 30
  4359.6  609.85  4382.2  609.67  4416.6  608.25  4443.0  608.33  4461.5  607.55
  4522.7  606.64  4584.4  604.83  4633.0  603.08  4683.2  602.71  4723.3  601.69
  4793.5  601.63  4851.6  600.84  4947.3  600.61  4955.8  597.98  4961.1  599.43
  4966.4  597.23  4966.6  596.73  4970.1  596.73  4970.4  597.23  4987.3  598.35
  5024.0  598.74  5042.2  599.67  5106.4  599.96  5153.8  603.53  5191.7  602.51
  5293.5  605.14  5328.6  605.39  5367.2  605.45  5397.5  606.23  5479.0  607.07
#Mann=10,-1,0
  4359.6    0.07       0  4416.6   0.045       0  4461.5    0.07       0
  4584.4   0.045       0  4851.6   0.035       0  4966.4   0.035       0
  4970.4   0.035       0  5293.5    0.07       0  5328.6    0.12       0
  5397.5    0.07       0
Bank Sta=4966.4,4970.4
Exp/Cntr=0.3,0.1

Type RM Length L Ch R = 1,789,241,241,241
BEGIN DESCRIPTION:
GUADALUPE TRIBUTARY 2C 2.0
END DESCRIPTION:
XS GIS Cut Line= 3
      2260618.53     13752267.90      2260507.86     13751634.24
      2260316.89     13751130.79
#Sta/Elev= 30
  4237.8  608.28  4261.0  608.31  4301.7  606.82  4322.0  606.94  4332.1  605.79
  4346.4  605.48  4405.9  605.21  4460.4  603.43  4643.0  601.75  4700.8  600.91
  4890.9  599.26  4960.0  599.57  4976.5  597.81  4995.9  597.08  4996.1  596.58
  4999.6  596.58  4999.9  597.08  5008.9  597.77  5015.0  598.82  5115.5  600.65
  5136.9  601.55  5160.3  603.69  5179.7  603.88  5185.1  603.67  5190.5  602.54
  5201.1  602.47  5222.5  603.91  5241.8  604.29  5286.7  604.11  5419.5  606.70
#Mann=7,-1,0
  4237.8   0.045       0  4643.0   0.035       0  4700.8   0.045       0
  4995.9   0.045       0  4999.9   0.045       0  5008.9   0.035       0
  5241.8    0.07       0
Bank Sta=4995.9,4999.9
Exp/Cntr=0.3,0.1

Type RM Length L Ch R = 1,548,216,216,216
BEGIN DESCRIPTION:
GUADALUPE TRIBUTARY 2C 1.0
END DESCRIPTION:
XS GIS Cut Line= 3
      2260811.67     13752159.39      2260681.47     13751434.59
      2260364.64     13751115.60
#Sta/Elev= 30
  4255.9  605.82  4371.1  603.18  4544.0  600.54  4646.4  600.04  4700.0  599.15
  4819.3  598.30  4866.4  598.56  4922.6  598.50  4945.1  598.16  4961.4  596.62
  4979.7  596.20  4980.0  595.70  4983.5  595.70  4983.7  596.20  5010.7  598.29
  5092.2  599.62  5179.1  600.97  5251.1  602.73  5265.3  604.31  5286.5  603.82
  5293.6  603.01  5300.7  603.11  5307.7  604.07  5322.1  604.31  5357.2  604.98
  5371.4  604.67  5392.6  605.32  5399.7  604.98  5438.5  605.65  5441.9  605.66
#Mann=12,-1,0
  4255.9    0.07       0  4371.1   0.035       0  4700.0   0.045       0
  4819.3   0.035       0  4866.4   0.045       0  4922.6   0.035       0
  4979.7   0.035       0  4983.7   0.035       0  5092.2   0.045       0
  5179.1   0.035       0  5322.1    0.07       0  5438.5    0.12       0
Bank Sta=4979.7,4983.7
Exp/Cntr=0.3,0.1

Type RM Length L Ch R = 1,332,205,205,205
BEGIN DESCRIPTION:
A19335
END DESCRIPTION:
XS GIS Cut Line= 4
      2260846.40     13752116.03      2260889.80     13751430.25
      2260850.74     13751282.68      2260371.17     13751080.87
#Sta/Elev= 30
  4255.7  604.87  4339.6  602.56  4477.2  600.19  4577.4  598.96  4697.6  598.01
  4864.1  597.51  4948.3  597.44  4958.6  597.27  4977.6  596.12  4998.0  595.81
  4998.3  595.31  5001.8  595.31  5002.0  595.81  5023.0  597.59  5095.5  597.69
  5131.2  598.59  5188.5  599.53  5221.1  599.43  5244.2  599.85  5290.1  600.76
  5349.7  601.45  5387.6  602.08  5411.4  601.96  5435.1  603.81  5448.9  603.38
  5464.3  602.10  5470.6  603.41  5579.1  605.30  5602.8  605.22  5615.8  605.27
#Mann=10,-1,0
  4255.7    0.07       0  4339.6   0.035       0  4864.1   0.045       0
  4998.0   0.045       0  5002.0   0.045       0  5131.2   0.035       0
  5244.2   0.045       0  5290.1   0.035       0  5349.7    0.07       0
  5602.8    0.12       0
Bank Sta=4998,5002
Exp/Cntr=0.3,0.1

Type RM Length L Ch R = 1,127,0,0,0
BEGIN DESCRIPTION:
A19334
END DESCRIPTION:
XS GIS Cut Line= 5
      2261054.73     13752031.37      2261108.98     13751430.25
      2261041.71     13751269.66      2260900.65     13751145.96
      2260445.75     13751039.82
#Sta/Elev= 30
  4281.0  600.77  4292.3  600.58  4387.8  599.25  4458.1  597.57  4653.9  596.95
  4784.5  596.50  4819.5  597.02  4869.8  597.00  4922.8  595.93  4977.0  596.93
  5005.7  595.60  5006.0  595.10  5009.5  595.10  5009.7  595.60  5030.3  596.70
  5036.9  597.20  5094.7  596.83  5246.3  597.35  5270.0  598.14  5385.6  599.49
  5416.4  600.33  5519.1  601.39  5535.0  601.97  5540.7  601.64  5570.4  603.29
  5591.0  602.59  5625.7  603.36  5693.6  603.81  5710.8  604.87  5713.4  604.24
#Mann=8,-1,0
  4281.0    0.07       0  4292.3   0.035       0  4653.9    0.07       0
  5005.7    0.05       0  5009.7    0.07       0  5030.3   0.045       0
  5385.6   0.035       0  5535.0    0.07       0
Bank Sta=5005.7,5009.7
Exp/Cntr=0.3,0.1

Chan Stop Cuts=-1