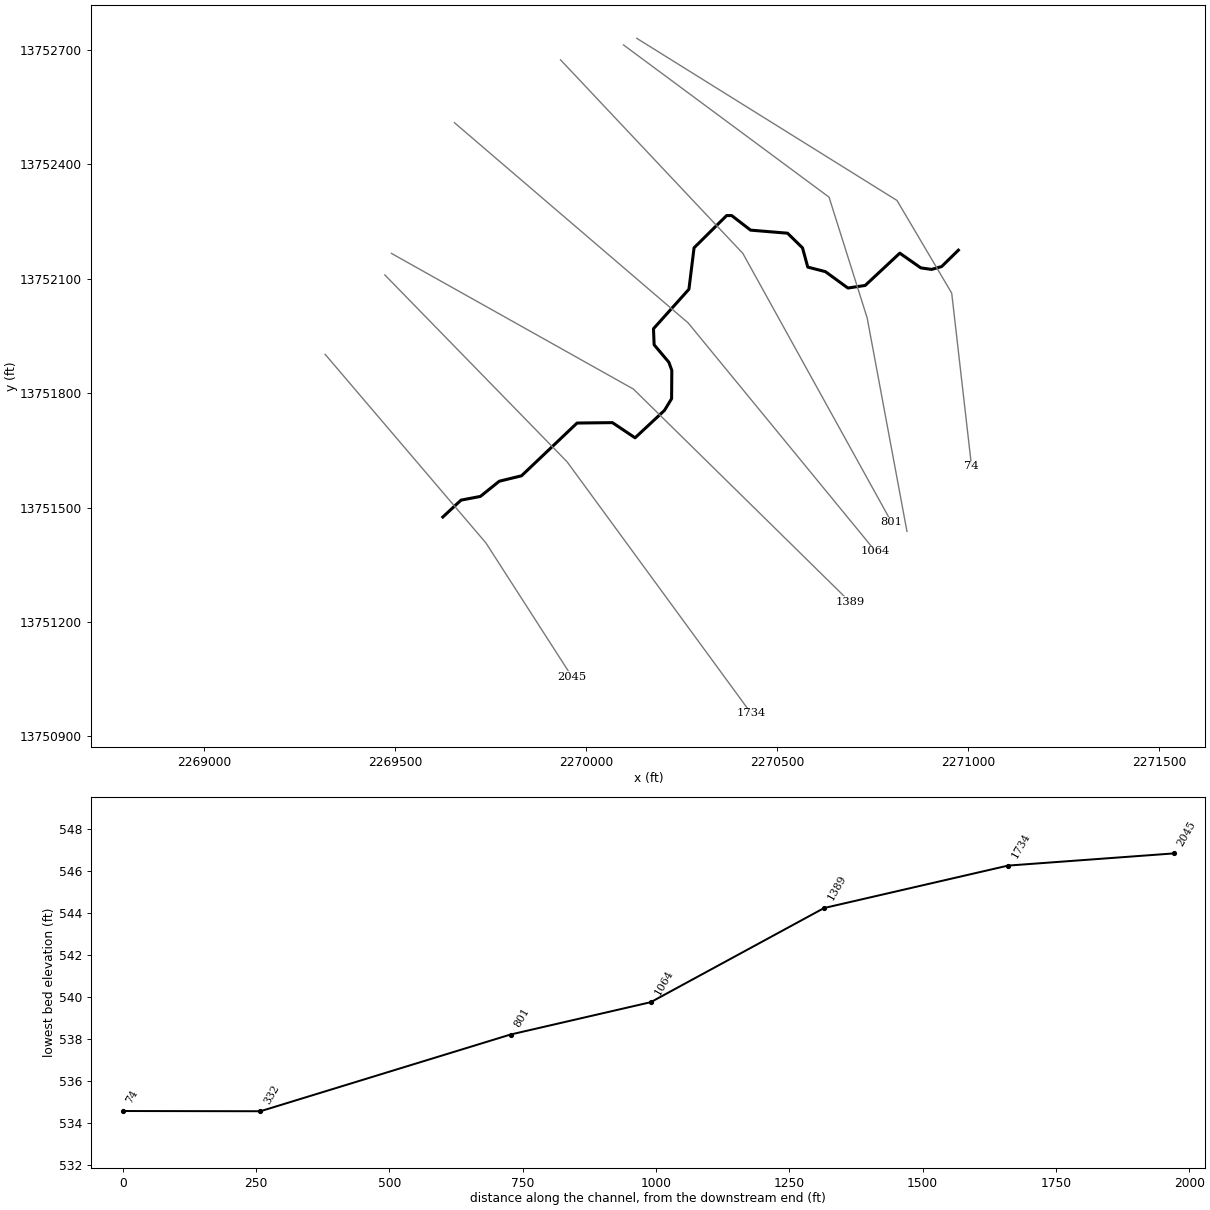
--- GUADALUPE TRIBUTARY 3A.prj (project) ---

Proj Title=GUADALUPE TRIBUTARY 3A Base Level Engineering
Current Plan=p01
Default Exp/Contr=0.3,0.1
English Units
Geom File=g01
Flow File=f01
Plan File=p01
BEGIN DESCRIPTION:
GUADALUPE TRIBUTARY 3A
END DESCRIPTION:

--- GUADALUPE TRIBUTARY 3A.p01 (plan) ---

Plan Title=Multiple Run
Short Identifier=Multiple
Geom File=g01
Flow File=f01
Subcritical Flow
K Sum by GR= 0
Std Step Tol= 0.01
Critical Tol= 0.01
Num of Std Step Trials= 20
Max Error Tol= 0.3
Flow Tol Ratio= 0.001
Split Flow NTrial= 30
Split Flow Tol= 0.02
Split Flow Ratio= 0.02
Log Output Level= 0
Friction Slope Method= 1
Unsteady Friction Slope Method= 2
Unsteady Bridges Friction Slope Method= 1
Parabolic Critical Depth
Global Vel Dist=  1 , 1 , 1
Global Log Level= 0
CheckData=True
Encroach Param= -1, 0, 0, 0
BEGIN DESCRIPTION:
Multiple Run
END DESCRIPTION:

--- GUADALUPE TRIBUTARY 3A.f01 (steady flow) ---

Flow Title=Multiple
Number of Profiles=7
Profile Names=10-year,25-year,50-year,1pct_min,100-year,1pct_plu,500-year
River Rch & RM= GUADALUPE TRIBUT,Reach-1,2045
     674    1091    1469     957    1910    3812    3198
Boundary for River Rch & Prof#=GUADALUPE TRIBUT,Reach-1,1
Up Type=0
Dn Type=3
Dn Slope=0.005
Boundary for River Rch & Prof#=GUADALUPE TRIBUT,Reach-1,2
Up Type=0
Dn Type=3
Dn Slope=0.005
Boundary for River Rch & Prof#=GUADALUPE TRIBUT,Reach-1,3
Up Type=0
Dn Type=3
Dn Slope=0.005
Boundary for River Rch & Prof#=GUADALUPE TRIBUT,Reach-1,4
Up Type=0
Dn Type=3
Dn Slope=0.005
Boundary for River Rch & Prof#=GUADALUPE TRIBUT,Reach-1,5
Up Type=0
Dn Type=3
Dn Slope=0.005
Boundary for River Rch & Prof#=GUADALUPE TRIBUT,Reach-1,6
Up Type=0
Dn Type=3
Dn Slope=0.005
Boundary for River Rch & Prof#=GUADALUPE TRIBUT,Reach-1,7
Up Type=0
Dn Type=3
Dn Slope=0.005

--- GUADALUPE TRIBUTARY 3A.g01 (geometry) ---

Geom Title=Existing Conditions

River Reach=GUADALUPE TRIBUT,Reach-1
Reach XY= 30
      2269625.00     13751475.00      2269672.64     13751519.33
      2269723.33     13751529.04      2269772.81     13751568.90
      2269831.06     13751583.14      2269976.50     13751721.54
      2270069.11     13751722.63      2270128.43     13751682.79
      2270205.42     13751754.76      2270224.07     13751785.47
      2270224.61     13751859.73      2270216.86     13751881.05
      2270178.34     13751926.75      2270176.63     13751968.96
      2270269.46     13752072.58      2270282.86     13752181.21
      2270368.24     13752265.88      2270381.52     13752265.72
      2270430.89     13752227.57      2270527.66     13752219.55
      2270566.85     13752181.08      2270580.62     13752130.62
      2270626.86     13752118.68      2270685.69     13752075.69
      2270731.05     13752082.52      2270821.60     13752167.18
      2270876.58     13752128.61      2270904.75     13752124.54
      2270931.14     13752131.98      2270975.00     13752175.00

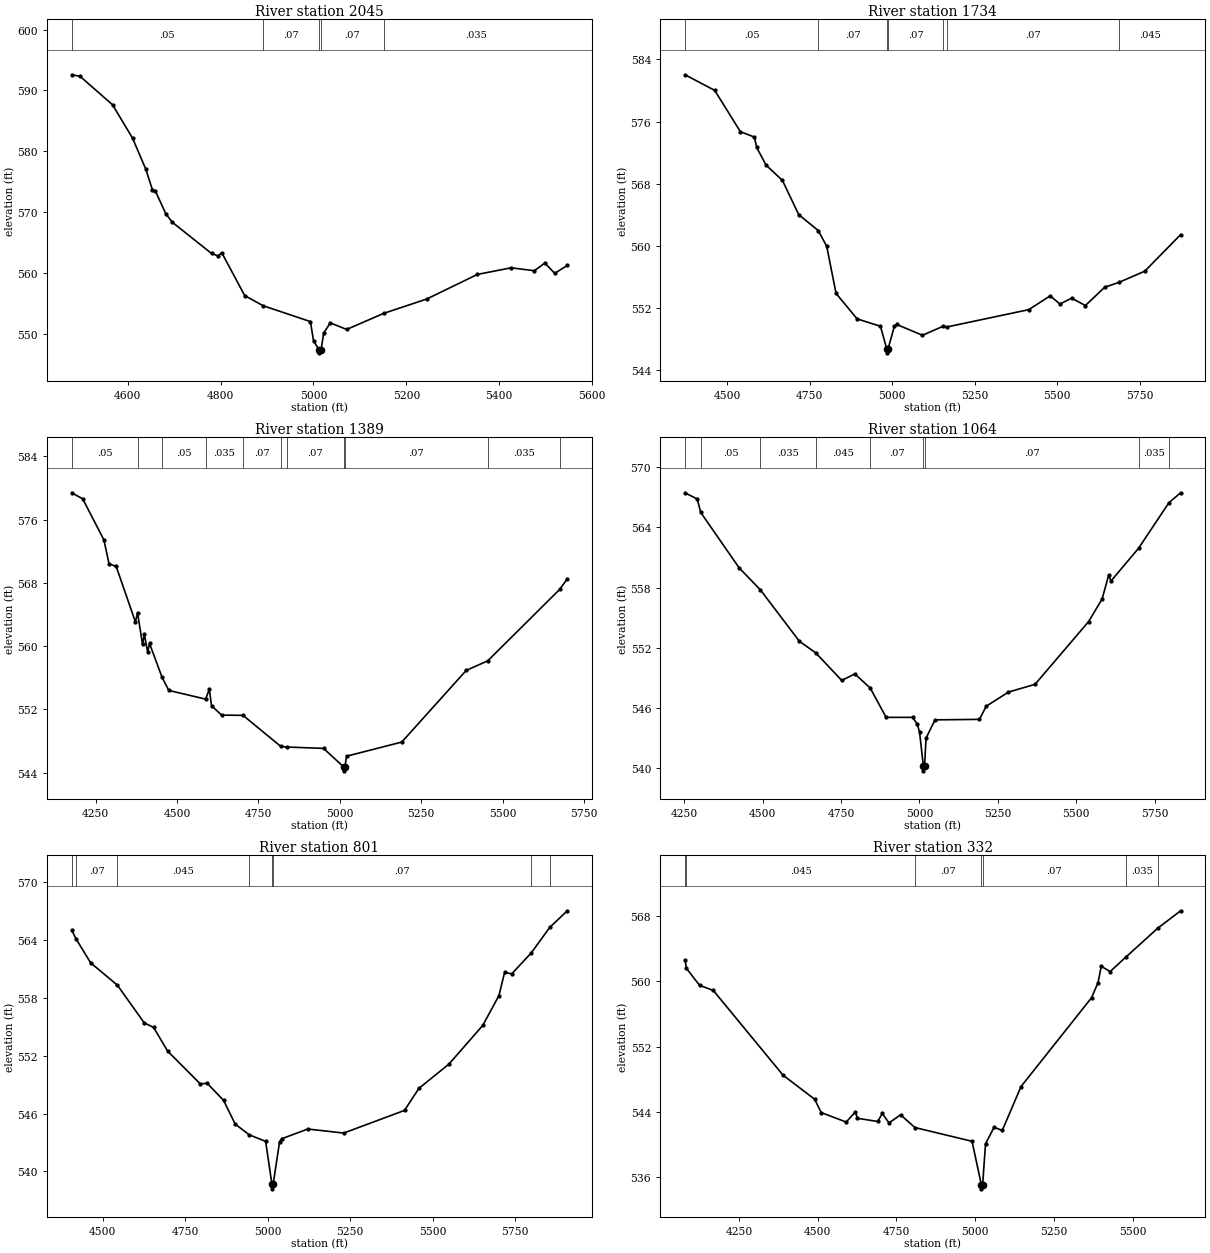
Type RM Length L Ch R = 1,2045,311,311,311
BEGIN DESCRIPTION:
A19352
END DESCRIPTION:
XS GIS Cut Line= 3
      2269316.95     13751901.71      2269737.93     13751406.94
      2269963.62     13751055.38
#Sta/Elev= 30
  4479.3  592.57  4497.1  592.32  4567.3  587.62  4610.2  582.15  4638.7  577.05
  4653.0  573.65  4659.6  573.42  4681.6  569.74  4695.8  568.31  4780.4  563.17
  4794.7  562.76  4802.4  563.30  4851.8  556.24  4891.2  554.58  4993.4  551.96
  5000.2  548.73  5012.3  547.32  5012.5  546.82  5016.3  547.32  5022.0  550.10
  5036.3  551.75  5071.4  550.67  5151.4  553.32  5243.8  555.67  5353.0  559.72
  5425.7  560.81  5475.9  560.33  5498.3  561.60  5519.5  559.90  5546.7  561.20
#Mann=5,-1,0
  4479.3    0.05       0  4891.2    0.07       0  5012.3    0.05       0
  5016.3    0.07       0  5151.4   0.035       0
Bank Sta=5012.3,5016.3
Exp/Cntr=0.3,0.1

Type RM Length L Ch R = 1,1734,345,345,345
BEGIN DESCRIPTION:
A19351
END DESCRIPTION:
XS GIS Cut Line= 3
      2269473.17     13752110.07      2269950.61     13751619.61
      2270432.34     13750959.95
#Sta/Elev= 30
  4372.9  582.03  4462.7  580.02  4540.4  574.71  4582.9  574.01  4589.8  572.68
  4618.1  570.41  4667.7  568.44  4717.2  564.03  4776.3  561.98  4802.0  559.95
  4830.3  553.89  4894.1  550.61  4964.8  549.66  4983.9  546.74  4984.2  546.24
  4987.9  546.74  5007.2  549.72  5014.2  549.89  5092.1  548.50  5155.6  549.68
  5166.2  549.57  5414.2  551.80  5479.1  553.58  5508.4  552.52  5543.9  553.28
  5585.7  552.33  5644.3  554.69  5686.8  555.30  5765.6  556.75  5874.2  561.46
#Mann=7,-1,0
  4372.9    0.05       0  4776.3    0.07       0  4983.9    0.05       0
  4987.9    0.07       0  5155.6   0.035       0  5166.2    0.07       0
  5686.8   0.045       0
Bank Sta=4983.9,4987.9
Exp/Cntr=0.3,0.1

Type RM Length L Ch R = 1,1389,325,325,325
BEGIN DESCRIPTION:
A19350
END DESCRIPTION:
XS GIS Cut Line= 3
      2269490.55     13752166.48      2270124.22     13751810.58
      2270691.41     13751252.05
#Sta/Elev= 30
  4176.2  579.39  4209.9  578.62  4275.0  573.43  4290.9  570.38  4312.6  570.09
  4371.9  563.04  4378.3  564.24  4393.6  560.23  4399.3  561.48  4409.5  559.24
  4415.2  560.33  4453.6  556.06  4474.5  554.39  4587.6  553.29  4598.9  554.53
  4605.7  552.46  4636.5  551.27  4702.4  551.24  4818.8  547.30  4837.7  547.23
  4949.9  547.06  5011.6  544.72  5011.8  544.22  5015.6  544.72  5020.6  546.07
  5190.3  547.86  5388.3  556.92  5454.4  558.13  5675.8  567.18  5699.0  568.51
#Mann=11,-1,0
  4176.2    0.05       0  4378.3    0.07       0  4453.6    0.05       0
  4587.6   0.035       0  4702.4    0.07       0  4818.8   0.035       0
  4837.7    0.07       0  5011.6    0.05       0  5015.6    0.07       0
  5454.4   0.035       0  5675.8   0.045       0
Bank Sta=5011.6,5015.6
Exp/Cntr=0.3,0.1

Type RM Length L Ch R = 1,1064,263,263,263
BEGIN DESCRIPTION:
A19349
END DESCRIPTION:
XS GIS Cut Line= 3
      2269655.47     13752509.36      2270267.45     13751984.19
      2270757.92     13751385.21
#Sta/Elev= 30
  4252.7  567.44  4291.4  566.83  4302.6  565.49  4425.3  559.96  4492.8  557.78
  4617.4  552.65  4669.7  551.49  4752.3  548.75  4794.1  549.40  4843.3  547.99
  4893.9  545.07  4978.4  545.07  4992.7  544.42  5000.4  543.64  5012.6  540.24
  5012.9  539.74  5016.6  540.24  5021.2  542.99  5049.8  544.82  5191.6  544.87
  5213.2  546.18  5284.2  547.59  5368.9  548.36  5539.7  554.61  5582.8  556.86
  5603.6  559.22  5611.5  558.67  5699.1  561.92  5796.1  566.47  5833.3  567.45
#Mann=9,-1,0
  4252.7    0.07       0  4302.6    0.05       0  4492.8   0.035       0
  4669.7   0.045       0  4843.3    0.07       0  5012.6    0.05       0
  5016.6    0.07       0  5699.1   0.035       0  5796.1   0.045       0
Bank Sta=5012.6,5016.6
Exp/Cntr=0.3,0.1

Type RM Length L Ch R = 1,801,469,469,469
BEGIN DESCRIPTION:
A19348
END DESCRIPTION:
XS GIS Cut Line= 3
      2269933.25     13752674.30      2270410.68     13752166.48
      2270800.36     13751460.72
#Sta/Elev= 30
  4405.7  565.00  4419.6  564.06  4462.9  561.63  4544.1  559.31  4625.6  555.40
  4653.9  554.93  4696.4  552.48  4795.5  549.08  4816.6  549.14  4866.3  547.36
  4901.5  544.91  4944.0  543.80  4993.8  543.12  5012.8  538.70  5013.1  538.20
  5016.8  538.70  5036.1  543.09  5043.1  543.40  5121.8  544.40  5230.6  543.98
  5415.1  546.33  5458.6  548.61  5549.9  551.13  5652.7  555.15  5701.3  558.22
  5718.7  560.63  5740.5  560.49  5799.7  562.66  5855.4  565.29  5908.9  567.02
#Mann=8,-1,0
  4405.7    0.05       0  4419.6    0.07       0  4544.1   0.045       0
  4944.0    0.07       0  5012.8    0.05       0  5016.8    0.07       0
  5799.7   0.035       0  5855.4   0.045       0
Bank Sta=5012.8,5016.8
Exp/Cntr=0.3,0.1

Type RM Length L Ch R = 1,332,258,258,258
BEGIN DESCRIPTION:
A19347
END DESCRIPTION:
XS GIS Cut Line= 4
      2270098.14     13752713.39      2270636.37     13752314.05
      2270736.20     13751997.21      2270840.37     13751437.31
#Sta/Elev= 30
  4079.4  562.61  4083.5  561.60  4125.3  559.51  4168.9  558.88  4390.1  548.49
  4490.3  545.54  4511.3  543.90  4590.4  542.74  4619.6  543.98  4625.9  543.20
  4690.6  542.81  4705.2  543.80  4726.0  542.63  4763.0  543.63  4808.2  542.07
  4989.6  540.38  5019.2  535.05  5019.5  534.55  5023.2  535.05  5032.4  540.07
  5059.5  542.10  5085.5  541.71  5145.1  547.10  5368.8  557.99  5389.2  559.83
  5399.4  561.84  5427.7  561.20  5478.7  563.01  5578.3  566.50  5651.3  568.65
#Mann=7,-1,0
  4079.4    0.07       0  4083.5   0.045       0  4808.2    0.07       0
  5019.2    0.05       0  5023.2    0.07       0  5478.7   0.035       0
  5578.3   0.045       0
Bank Sta=5019.2,5023.2
Exp/Cntr=0.3,0.1

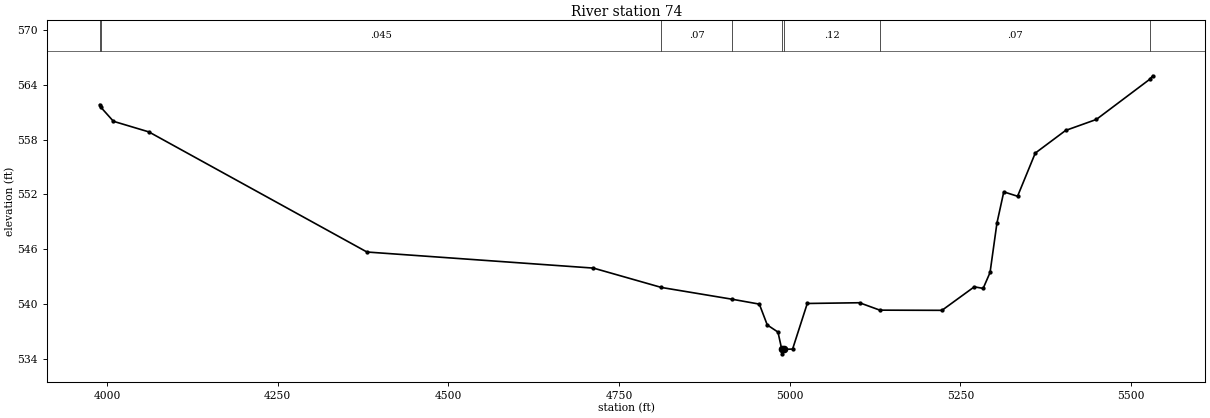
Type RM Length L Ch R = 1,74,0,0,0
BEGIN DESCRIPTION:
A19346
END DESCRIPTION:
XS GIS Cut Line= 4
      2270132.92     13752730.71      2270814.32     13752305.37
      2270957.55     13752062.32      2271009.45     13751608.25
#Sta/Elev= 30
  3989.2  561.83  3990.6  561.57  4009.4  560.00  4061.3  558.84  4380.7  545.70
  4712.4  543.94  4812.1  541.82  4915.1  540.54  4955.4  540.00  4967.0  537.72
  4982.7  536.94  4988.2  535.06  4988.5  534.56  4992.2  535.06  5004.1  535.08
  5025.6  540.07  5102.1  540.15  5131.9  539.34  5222.9  539.32  5270.2  541.89
  5283.2  541.72  5293.3  543.46  5303.4  548.87  5313.4  552.28  5333.6  551.80
  5359.5  556.52  5404.0  559.00  5448.9  560.20  5526.9  564.58  5531.6  564.98
#Mann=8,-1,0
  3989.2    0.07       0  3990.6   0.045       0  4812.1    0.07       0
  4915.1    0.12       0  4988.2    0.05       0  4992.2    0.12       0
  5131.9    0.07       0  5526.9   0.045       0
Bank Sta=4988.2,4992.2
Exp/Cntr=0.3,0.1

Chan Stop Cuts=-1