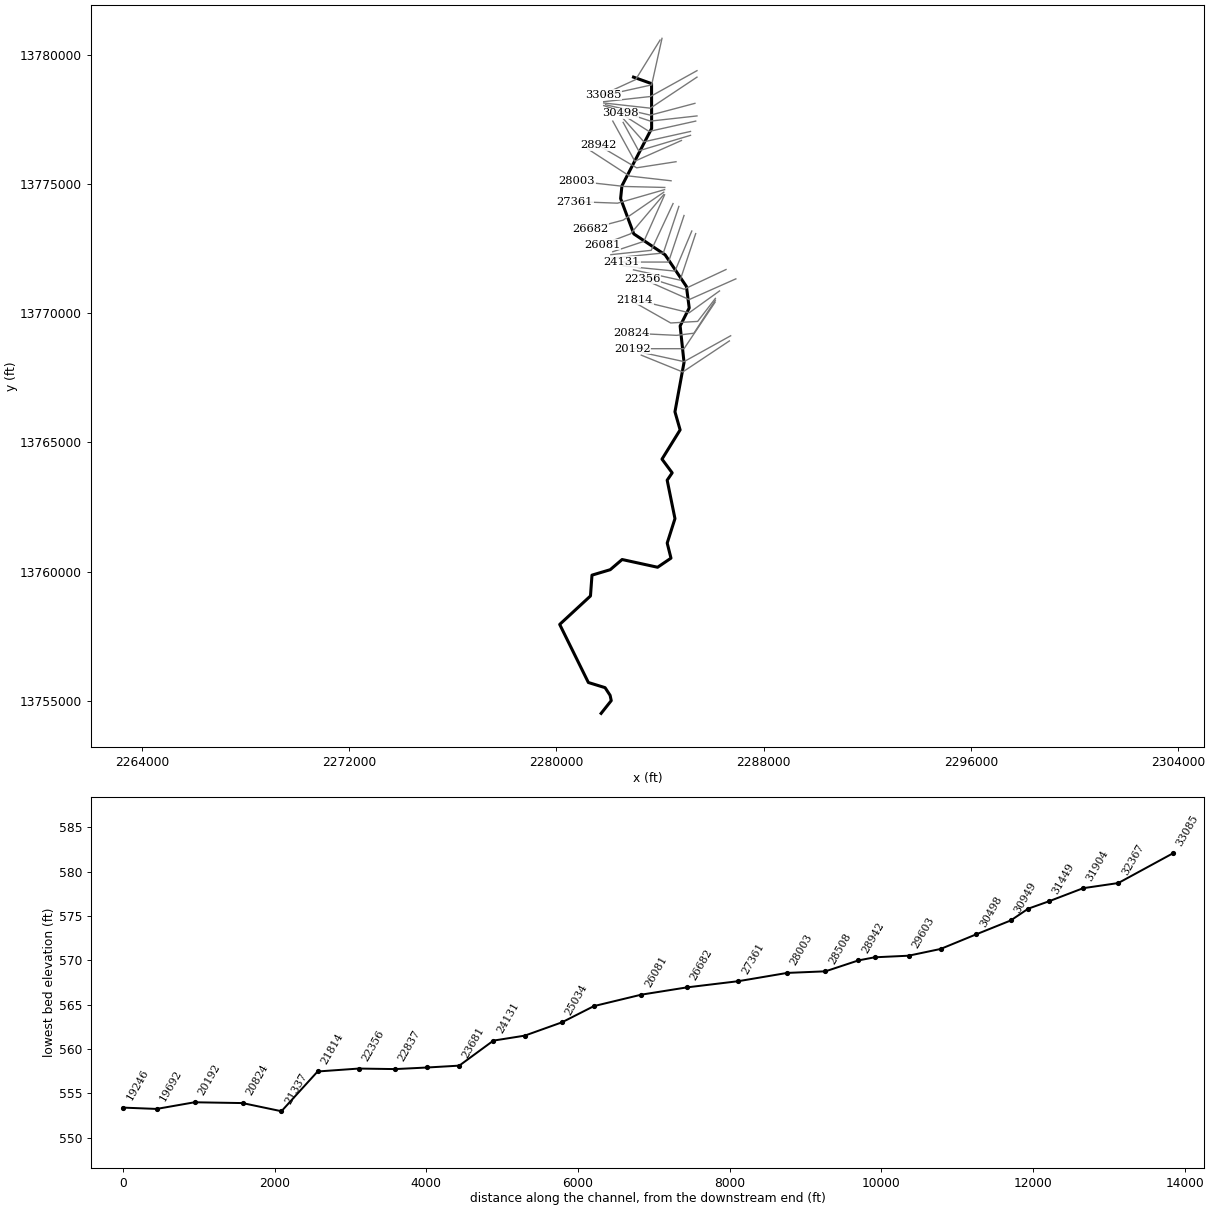
--- GUADALUPE TRIBUTARY 4A.prj (project) ---

Proj Title=GUADALUPE TRIBUTARY 4A Base Level Engineering
Current Plan=p01
Default Exp/Contr=0.3,0.1
English Units
Geom File=g01
Flow File=f01
Plan File=p01
Y Axis Title=Elevation
X Axis Title(PF)=Main Channel Distance
X Axis Title(XS)=Station
BEGIN DESCRIPTION:
GUADALUPE TRIBUTARY 4A
END DESCRIPTION:
DSS Export Rating Curves= 0
DSS Export Rating Curve Sorted= 0
DSS Export Volume Flow Curves= 0
DXF OffsetX= 0
DXF OffsetY= 0
DXF ScaleX= 1
DXF ScaleY= 10

--- GUADALUPE TRIBUTARY 4A.p01 (plan) ---

Plan Title=Multiple Run
Short Identifier=Multiple
Geom File=g01
Flow File=f01
Subcritical Flow
K Sum by GR= 0
Std Step Tol= 0.01
Critical Tol= 0.01
Num of Std Step Trials= 20
Max Error Tol= 0.3
Flow Tol Ratio= 0.001
Split Flow NTrial= 30
Split Flow Tol= 0.02
Split Flow Ratio= 0.02
Log Output Level= 0
Friction Slope Method= 1
Unsteady Friction Slope Method= 2
Unsteady Bridges Friction Slope Method= 1
Parabolic Critical Depth
Global Vel Dist=  1 , 1 , 1
Global Log Level= 0
CheckData=True
Encroach Param= -1, 0, 0, 0
BEGIN DESCRIPTION:
Multiple Run
END DESCRIPTION:

--- GUADALUPE TRIBUTARY 4A.f01 (steady flow) ---

Flow Title=Multiple
Number of Profiles=7
Profile Names=10-year,25-year,50-year,1pct_min,100-year,1pct_plu,500-year
River Rch & RM= GUADALUPE TRIBUT,Reach-1,33085
     581     914    1207     771    1538    3068    2468
River Rch & RM= GUADALUPE TRIBUT,Reach-1,30498
    1131    1849    2502    1633    3259    6502    5475
River Rch & RM= GUADALUPE TRIBUT,Reach-1,23681
    1376    2269    3089    2026    4043    8066    6863
River Rch & RM= GUADALUPE TRIBUT,Reach-1,18319
    1655    2757    3779    2495    4978    9932    8560
River Rch & RM= GUADALUPE TRIBUT,Reach-1,9020
    1645    2735    3743    2467    4922    9821    8438
River Rch & RM= GUADALUPE TRIBUT,Reach-1,5914
    3178    5553    7865    5364   10703   21356   19652
Boundary for River Rch & Prof#=GUADALUPE TRIBUT,Reach-1,1
Up Type=0
Dn Type=3
Dn Slope=0.0005
Boundary for River Rch & Prof#=GUADALUPE TRIBUT,Reach-1,2
Up Type=0
Dn Type=3
Dn Slope=0.0005
Boundary for River Rch & Prof#=GUADALUPE TRIBUT,Reach-1,3
Up Type=0
Dn Type=3
Dn Slope=0.0005
Boundary for River Rch & Prof#=GUADALUPE TRIBUT,Reach-1,4
Up Type=0
Dn Type=3
Dn Slope=0.0005
Boundary for River Rch & Prof#=GUADALUPE TRIBUT,Reach-1,5
Up Type=0
Dn Type=3
Dn Slope=0.0005
Boundary for River Rch & Prof#=GUADALUPE TRIBUT,Reach-1,6
Up Type=0
Dn Type=3
Dn Slope=0.0005
Boundary for River Rch & Prof#=GUADALUPE TRIBUT,Reach-1,7
Up Type=0
Dn Type=3
Dn Slope=0.0005

--- GUADALUPE TRIBUTARY 4A.g01 (geometry) ---

Geom Title=Existing Conditions
Program Version=4.10

River Reach=GUADALUPE TRIBUT,Reach-1
Reach XY= 30
        2282975.       13779125.      2283671.57     13778873.78
      2283674.61     13777140.16      2282528.82     13774923.42
      2282477.24     13774430.93       2282985.7     13773065.03
      2284195.39     13772255.16      2285016.84     13771031.05
      2285125.39       13770200.      2284775.05     13769504.96
      2284924.93     13768095.03      2284574.54     13766185.18
      2284774.07     13765485.48       2284074.7     13764354.83
      2284467.72     13763825.09      2284274.51      13763540.2
      2284575.21     13762054.79      2284275.51     13761109.79
      2284421.56     13760526.25       2283904.8      13760174.8
       2282535.5      13760473.8      2282077.43     13760080.52
      2281372.53     13759869.55      2281314.06     13759064.57
       2280126.2      13757964.5      2281232.68     13755718.48
       2281877.7     13755519.64      2282071.45     13755223.53
      2282115.87     13755018.26        2281725.       13754525.

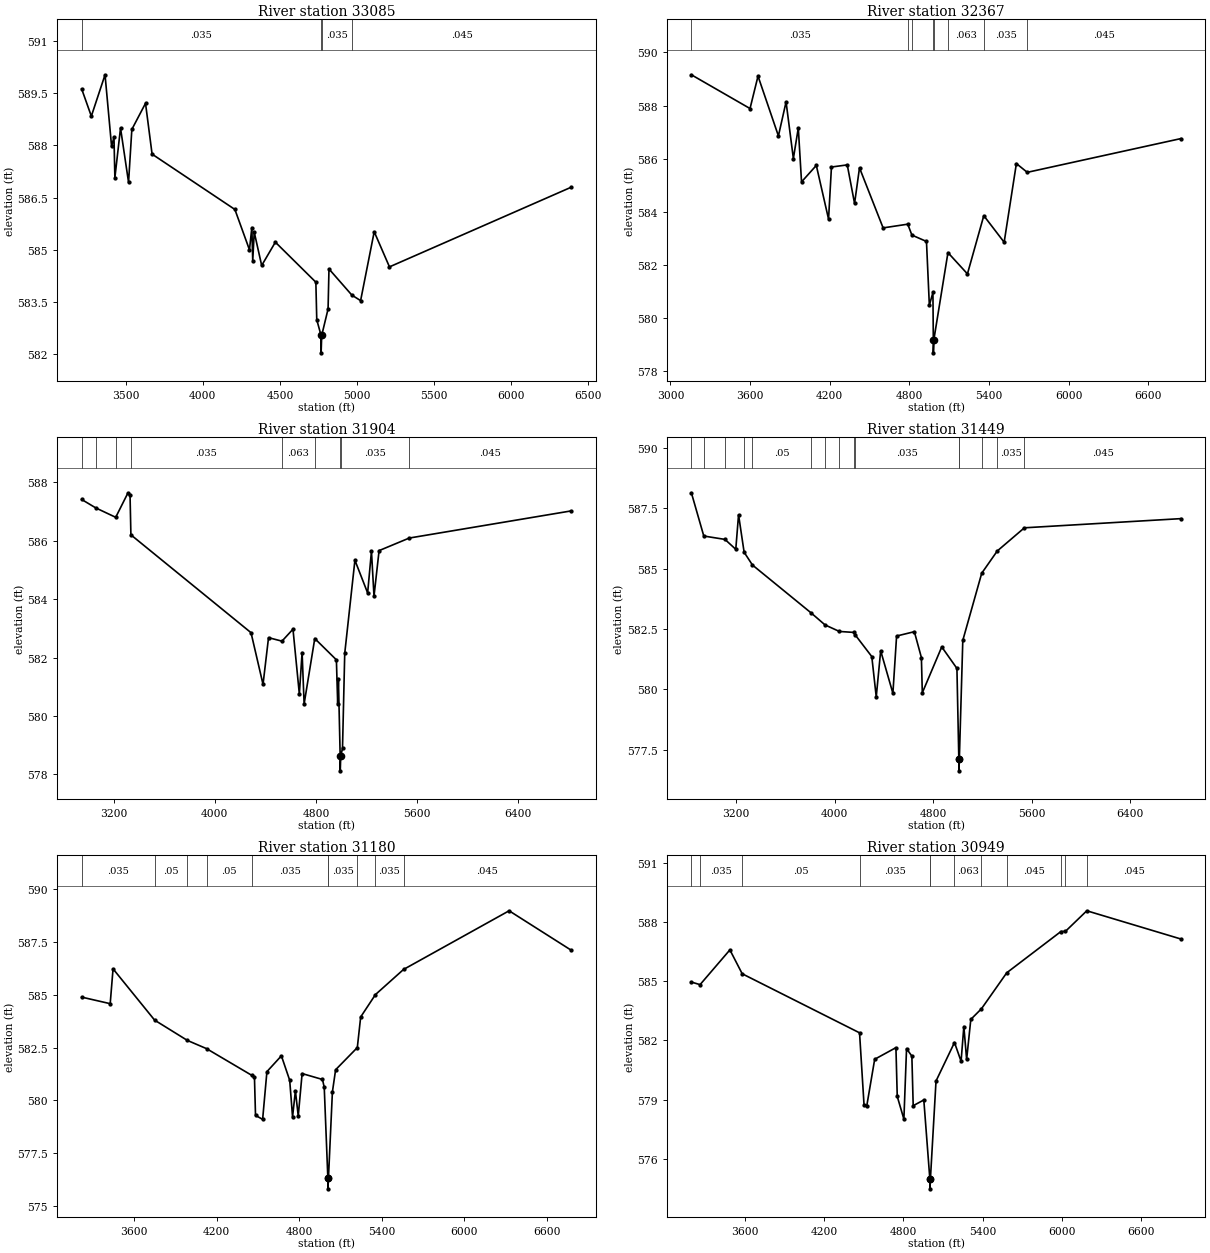
Type RM Length L Ch R = 1 ,33085   ,718,718,718
BEGIN DESCRIPTION:
A19389
END DESCRIPTION:
XS GIS Cut Line= 3
      2283999.99     13780557.79      2283057.84      13779030.6
      2281804.16     13778453.15
#Sta/Elev= 30
  3214.3  589.62  3276.8  588.84  3365.6  590.03  3408.1  587.97  3423.5  588.24
  3429.4  587.07    3466   588.5  3518.1  586.94  3539.4  588.46  3628.1  589.21
  3670.7  587.75  4207.6  586.16  4302.2     585  4317.6  585.64  4323.4  584.69
    4333  585.51  4381.4  584.55  4470.1  585.22  4732.7  584.07  4738.6  582.99
  4766.5  582.54  4766.8  582.04  4770.6  582.54  4811.9   583.3  4817.8  584.45
    4966   583.7  5022.9  583.54  5111.1  585.52    5210  584.51    6389   586.8
#Mann= 4 ,-1 , 0
  3214.3    .035       0  4766.5    .045       0  4770.6    .035       0
    4966    .045       0
Bank Sta=4766.5,4770.6
XS Rating Curve= 0 ,0
Exp/Cntr=0.3,0.1

Type RM Length L Ch R = 1 ,32367   ,463,463,463
BEGIN DESCRIPTION:
GUADALUPE TRIBUTARY 4A 50.0
END DESCRIPTION:
XS GIS Cut Line= 3
      2284075.01     13780625.05        2283675.       13778825.
      2281874.97     13778424.99
#Sta/Elev= 30
    3158  589.16  3599.8  587.89    3660  589.11  3813.7  586.86  3871.3  588.14
  3926.3  586.01  3963.5  587.16  3987.8  585.13  4099.2  585.75  4191.4  583.73
  4213.2  585.69  4332.3  585.77  4387.3  584.32  4424.5  585.66  4602.4   583.4
    4788  583.54  4819.1  583.13    4929  582.89  4950.7  580.49  4977.6  580.97
  4980.6   579.2  4980.9   578.7  4984.8   579.2  5090.8  582.47  5237.6  581.67
  5360.8  583.86  5514.2  582.86  5606.3  585.82  5688.3  585.49  6845.9  586.76
#Mann= 8 ,-1 , 0
    3158    .035       0    4788    .063       0  4819.1    .035       0
  4980.6    .035       0  4984.8    .035       0  5090.8    .063       0
  5360.8    .035       0  5688.3    .045       0
Bank Sta=4980.6,4984.8
XS Rating Curve= 0 ,0
Exp/Cntr=0.3,0.1

Type RM Length L Ch R = 1 ,31904   ,455,455,455
BEGIN DESCRIPTION:
GUADALUPE TRIBUTARY 4A 49.0
END DESCRIPTION:
XS GIS Cut Line= 3
      2285425.03     13779375.02        2283625.       13778375.
      2281825.03       13778175.
#Sta/Elev= 30
  2948.4  587.41  3060.5  587.12  3217.2   586.8  3314.5  587.64  3330.5  587.56
  3337.3   586.2  4286.9  582.85  4381.8  581.08  4425.3  582.68  4531.5  582.56
  4618.6  582.97  4668.9  580.75  4690.7  582.17  4706.7  580.41  4790.8  582.65
  4961.8  581.92  4972.1  580.41  4977.8  581.26  4991.7  578.62    4992  578.12
  4995.9  578.62  5010.1  578.89  5027.7  582.14  5108.2  585.33  5208.8  584.21
    5239  585.64  5259.1   584.1  5299.3  585.66  5537.8  586.09  6818.6  587.02
#Mann= 9 ,-1 , 0
  2948.4    .045       0  3060.5    .035       0  3217.2    .045       0
  3337.3    .035       0  4531.5    .063       0  4790.8    .035       0
  4991.7    .035       0  4995.9    .035       0  5537.8    .045       0
Bank Sta=4991.7,4995.9
XS Rating Curve= 0 ,0
Exp/Cntr=0.3,0.1

Type RM Length L Ch R = 1 ,31449   ,269,269,269
BEGIN DESCRIPTION:
GUADALUPE TRIBUTARY 4A 48.0
END DESCRIPTION:
XS GIS Cut Line= 3
      2285424.97     13779124.98        2283625.       13777925.
      2281824.97       13778125.
#Sta/Elev= 30
  2836.7  588.14  2937.5  586.35  3109.4  586.21  3197.2   585.8  3219.7  587.23
  3264.9  585.68  3332.4  585.15  3805.8  583.18  3921.9  582.67    4038   582.4
    4154  582.36  4164.8  582.27  4301.4  581.36  4337.5  579.69  4373.5   581.6
  4472.7  579.84  4502.7  582.21  4646.9  582.39    4704  581.32  4711.5  579.86
  4869.3  581.76  4992.5  580.87  5007.9  577.13  5008.2  576.63  5012.2  577.13
  5040.2  582.03  5193.8  584.81  5319.9  585.73  5540.2  586.69  6811.1  587.07
#Mann= 15 ,-1 , 0
  2836.7    .045       0  2937.5    .035       0  3109.4     .05       0
  3264.9    .035       0  3332.4     .05       0  3805.8     .07       0
  3921.9     .05       0    4038    .035       0    4154     .05       0
  4164.8    .035       0  5007.9    .035       0  5012.2    .035       0
  5193.8    .063       0  5319.9    .035       0  5540.2    .045       0
Bank Sta=5007.9,5012.2
XS Rating Curve= 0 ,0
Exp/Cntr=0.3,0.1

Type RM Length L Ch R = 1 ,31180   ,231,231,231
BEGIN DESCRIPTION:
A19388
END DESCRIPTION:
XS GIS Cut Line= 3
      2285344.93     13778111.24       2283627.7     13777655.34
      2281895.31     13778058.04
#Sta/Elev= 30
  3220.5  584.89  3427.4  584.58  3448.1  586.23  3750.1   583.8  3987.8  582.84
  4127.2  582.45  4457.1  581.18    4475   581.1  4482.7  579.29  4534.4   579.1
  4565.5  581.36  4670.7  582.11    4731  580.95  4751.7  579.22  4772.4  580.45
  4793.1  579.26  4821.1  581.27    4969  580.99  4981.8  580.62  5008.1  576.31
  5008.4  575.81  5012.4  576.31  5041.1   580.4  5064.4  581.45    5222   582.5
  5246.4  583.95  5353.6  585.01  5557.5   586.2  6324.4  588.98  6775.8  587.11
#Mann= 10 ,-1 , 0
  3220.5    .035       0  3750.1     .05       0  3987.8    .035       0
  4127.2     .05       0  4457.1    .035       0  5008.1    .035       0
  5012.4    .035       0    5222    .063       0  5353.6    .035       0
  5557.5    .045       0
Bank Sta=5008.1,5012.4
XS Rating Curve= 0 ,0
Exp/Cntr=0.3,0.1

Type RM Length L Ch R = 1 ,30949   ,451,451,451
BEGIN DESCRIPTION:
GUADALUPE TRIBUTARY 4A 47.0
END DESCRIPTION:
XS GIS Cut Line= 3
      2285424.98       13777625.        2283625.       13777425.
      2281825.02     13778024.99
#Sta/Elev= 30
  3193.3  584.95  3259.1  584.82  3485.1  586.58  3578.3  585.37  4467.2  582.38
  4501.3  578.72  4521.4  578.66  4581.8  581.04  4742.8  581.63  4752.8  579.16
  4803.1  578.01  4823.2  581.58  4863.5   581.2  4873.6  578.69    4954  578.98
  4999.7  574.98    5000  574.48    5004  574.98  5046.5  579.94  5186.3  581.89
  5236.3  580.94  5257.3   582.7  5278.4  581.03    5310  583.06  5390.8   583.6
  5582.2  585.42  5992.7  587.51  6027.1  587.52  6188.6  588.56  6901.7  587.13
#Mann= 12 ,-1 , 0
  3193.3    .045       0  3259.1    .035       0  3578.3     .05       0
  4467.2    .035       0  4999.7    .035       0    5004    .035       0
  5186.3    .063       0  5390.8    .035       0  5582.2    .045       0
  5992.7    .035       0  6027.1     .07       0  6188.6    .045       0
Bank Sta=4999.7,5004
XS Rating Curve= 0 ,0
Exp/Cntr=0.3,0.1

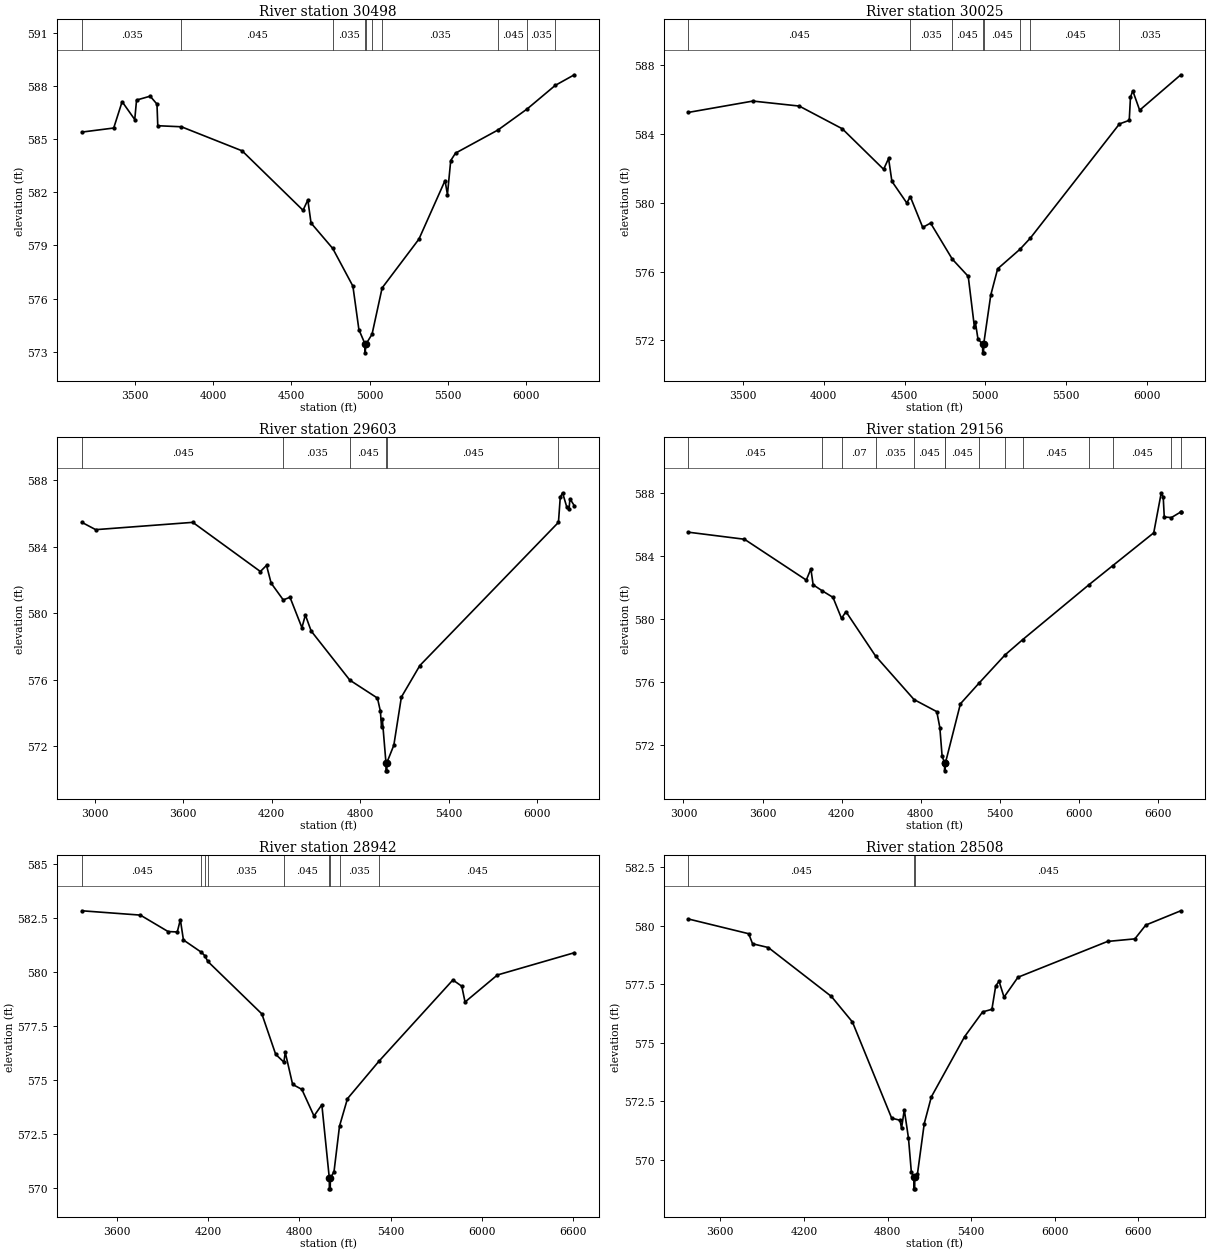
Type RM Length L Ch R = 1 ,30498   ,473,473,473
BEGIN DESCRIPTION:
GUADALUPE TRIBUTARY 4A 46.0
END DESCRIPTION:
XS GIS Cut Line= 3
      2285375.01       13777425.        2283575.       13777025.
      2282474.97     13777725.02
#Sta/Elev= 30
    3161  585.41  3364.6  585.64  3418.4  587.13  3499.1  586.12  3510.6  587.22
  3597.7  587.44  3641.2  586.99  3646.3  585.77  3797.5  585.71  4185.4  584.35
  4574.7  580.99  4605.4  581.57  4625.9  580.27  4764.7  578.83  4893.5   576.7
  4931.9  574.24    4971  573.43  4971.5  572.93  4977.4  573.43  5015.8  573.98
  5080.3   576.6  5315.6  579.36  5482.4  582.67  5497.7  581.88  5518.8   583.8
  5549.3  584.22    5821  585.53  6007.6  586.72  6186.8  588.05  6308.8  588.65
#Mann= 10 ,-1 , 0
    3161    .035       0  3797.5    .045       0  4764.7    .035       0
    4971    .035       0  4977.4    .035       0  5015.8    .045       0
  5080.3    .035       0    5821    .045       0  6007.6    .035       0
  6186.8     .07       0
Bank Sta=4971,4977.4
XS Rating Curve= 0 ,0
Exp/Cntr=0.3,0.1

Type RM Length L Ch R = 1 ,30025   ,422,422,422
BEGIN DESCRIPTION:
GUADALUPE TRIBUTARY 4A 45.0
END DESCRIPTION:
XS GIS Cut Line= 3
      2285175.02       13777025.        2283375.       13776625.
      2282574.99     13777525.01
#Sta/Elev= 30
  3161.5  585.26    3561  585.92  3847.9  585.63  4114.2  584.31  4370.3  581.95
    4401  582.58  4421.5  581.25  4513.7  579.99  4535.3  580.36  4612.3  578.57
    4661  578.82  4795.5  576.72    4894  575.72  4932.4  572.76  4937.6  573.08
  4954.2  572.08    4983  571.77  4983.5  571.27    4989  571.27  4989.5  571.77
  5033.4  574.63  5076.1  576.16  5214.6   577.3  5278.7  577.95  5829.8  584.59
  5890.6   584.8  5898.1  586.14  5912.3  586.52    5955  585.39  6209.6  587.45
#Mann= 8 ,-1 , 0
  3161.5    .045       0  4535.3    .035       0  4795.5    .045       0
    4983    .045       0  4989.5    .045       0  5214.6    .035       0
  5278.7    .045       0  5829.8    .035       0
Bank Sta=4983,4989.5
XS Rating Curve= 0 ,0
Exp/Cntr=0.3,0.1

Type RM Length L Ch R = 1 ,29603   ,447,447,447
BEGIN DESCRIPTION:
GUADALUPE TRIBUTARY 4A 44.0
END DESCRIPTION:
XS GIS Cut Line= 3
        2285175.       13776875.        2283175.       13776275.
      2282574.98     13777375.04
#Sta/Elev= 30
  2911.7  585.47  3005.7  585.03  3664.3  585.47  4122.8  582.51  4164.5  582.88
  4195.9  581.81  4278.1   580.8  4323.8  580.96  4404.7  579.13  4428.2  579.89
  4467.3  578.93  4729.7  575.97  4917.1  574.89  4937.1   574.1    4945  573.13
  4950.2  573.63  4974.7  571.01  4975.2  570.51  4980.8  570.51  4981.3  571.01
  5028.2  572.05  5079.5  574.95  5204.8  576.85  6145.1  585.47  6157.4  586.98
    6173  587.25    6201  586.41  6217.2  586.29  6222.9  586.89  6252.8  586.47
#Mann= 6 ,-1 , 0
  2911.7    .045       0  4278.1    .035       0  4729.7    .045       0
  4974.7    .045       0  4981.3    .045       0  6145.1    .035       0
Bank Sta=4974.7,4981.3
XS Rating Curve= 0 ,0
Exp/Cntr=0.3,0.1

Type RM Length L Ch R = 1 ,29156   ,214,214,214
BEGIN DESCRIPTION:
GUADALUPE TRIBUTARY 4A 43.0
END DESCRIPTION:
XS GIS Cut Line= 3
      2284825.03     13776675.01        2283025.       13775875.
      2282174.99     13777425.02
#Sta/Elev= 30
  3036.7  585.53  3462.8  585.08    3932  582.48  3966.9  583.19    3984  582.18
  4054.1  581.79  4134.5  581.38  4199.4  580.04    4233  580.47    4458  577.64
  4749.7  574.87  4922.4   574.1  4945.6  573.09  4962.7  571.28  4981.3  570.83
  4981.8  570.33  4987.9  570.83  5101.8   574.6  5245.6  575.94  5440.1  577.71
  5574.8  578.69  6075.4  582.17  6258.1   583.4    6569  585.49    6626  588.04
  6641.1  587.75  6648.8   586.5  6702.8  586.46  6772.6  586.81  6774.3  586.81
#Mann= 14 ,-1 , 0
  3036.7    .045       0  4054.1    .035       0  4199.4     .07       0
    4458    .035       0  4749.7    .045       0  4981.3    .045       0
  4987.9    .045       0  5245.6    .035       0  5440.1     .07       0
  5574.8    .045       0  6075.4     .07       0  6258.1    .045       0
  6702.8    .035       0  6772.6    .045       0
Bank Sta=4981.3,4987.9
XS Rating Curve= 0 ,0
Exp/Cntr=0.3,0.1

Type RM Length L Ch R = 1 ,28942   ,434,434,434
BEGIN DESCRIPTION:
A19387
END DESCRIPTION:
XS GIS Cut Line= 3
      2284615.49     13775854.58      2283095.83     13775619.03
       2281629.7     13776485.04
#Sta/Elev= 30
  3368.5  582.84  3753.5  582.64  3935.7  581.88  3996.4  581.86  4016.6  582.43
  4036.9  581.49  4155.3  580.92  4177.9  580.76    4197   580.5    4553  578.07
    4644   576.2  4697.8  575.84    4707  576.29  4755.4  574.81  4816.1  574.58
    4896  573.35  4947.7  573.87  4996.8  570.48  4997.3  569.98    5003  569.98
  5003.5  570.48  5027.7  570.77  5063.9  572.88  5116.3  574.15  5323.2  575.88
    5810  579.64  5868.6  579.35    5890  578.62  6102.7  579.87  6609.1   580.9
#Mann= 9 ,-1 , 0
  3368.5    .045       0  4155.3    .035       0  4177.9     .07       0
    4197    .035       0  4697.8    .045       0  4996.8    .045       0
  5003.5    .045       0  5063.9    .035       0  5323.2    .045       0
Bank Sta=4996.8,5003.5
XS Rating Curve= 0 ,0
Exp/Cntr=0.3,0.1

Type RM Length L Ch R = 1 ,28508   ,505,505,505
BEGIN DESCRIPTION:
A19386
END DESCRIPTION:
XS GIS Cut Line= 3
      2284425.52     13775117.55       2282822.3     13775299.91
      2281211.47     13776348.47
#Sta/Elev= 30
  3369.9  580.28  3803.2  579.65  3831.2  579.22  3944.1  579.06    4397  576.97
    4548  575.88  4829.8  571.77  4890.2  571.68  4900.5  571.33  4920.4  572.13
  4950.6  570.91  4970.7  569.49  4988.8  569.25  4989.3  568.75  4995.1  568.75
  4995.6  569.25  5015.2   569.4  5063.8  571.54  5114.7  572.68  5353.2  575.25
  5482.9  576.31  5549.4  576.42  5576.8  577.42  5600.7  577.62  5636.5  576.94
  5736.5  577.79  6379.5  579.32  6575.8  579.43  6654.2  580.02  6905.5  580.63
#Mann= 3 ,-1 , 0
  3369.9    .045       0  4988.8    .045       0  4995.6    .045       0
Bank Sta=4988.8,4995.6
XS Rating Curve= 0 ,0
Exp/Cntr=0.3,0.1

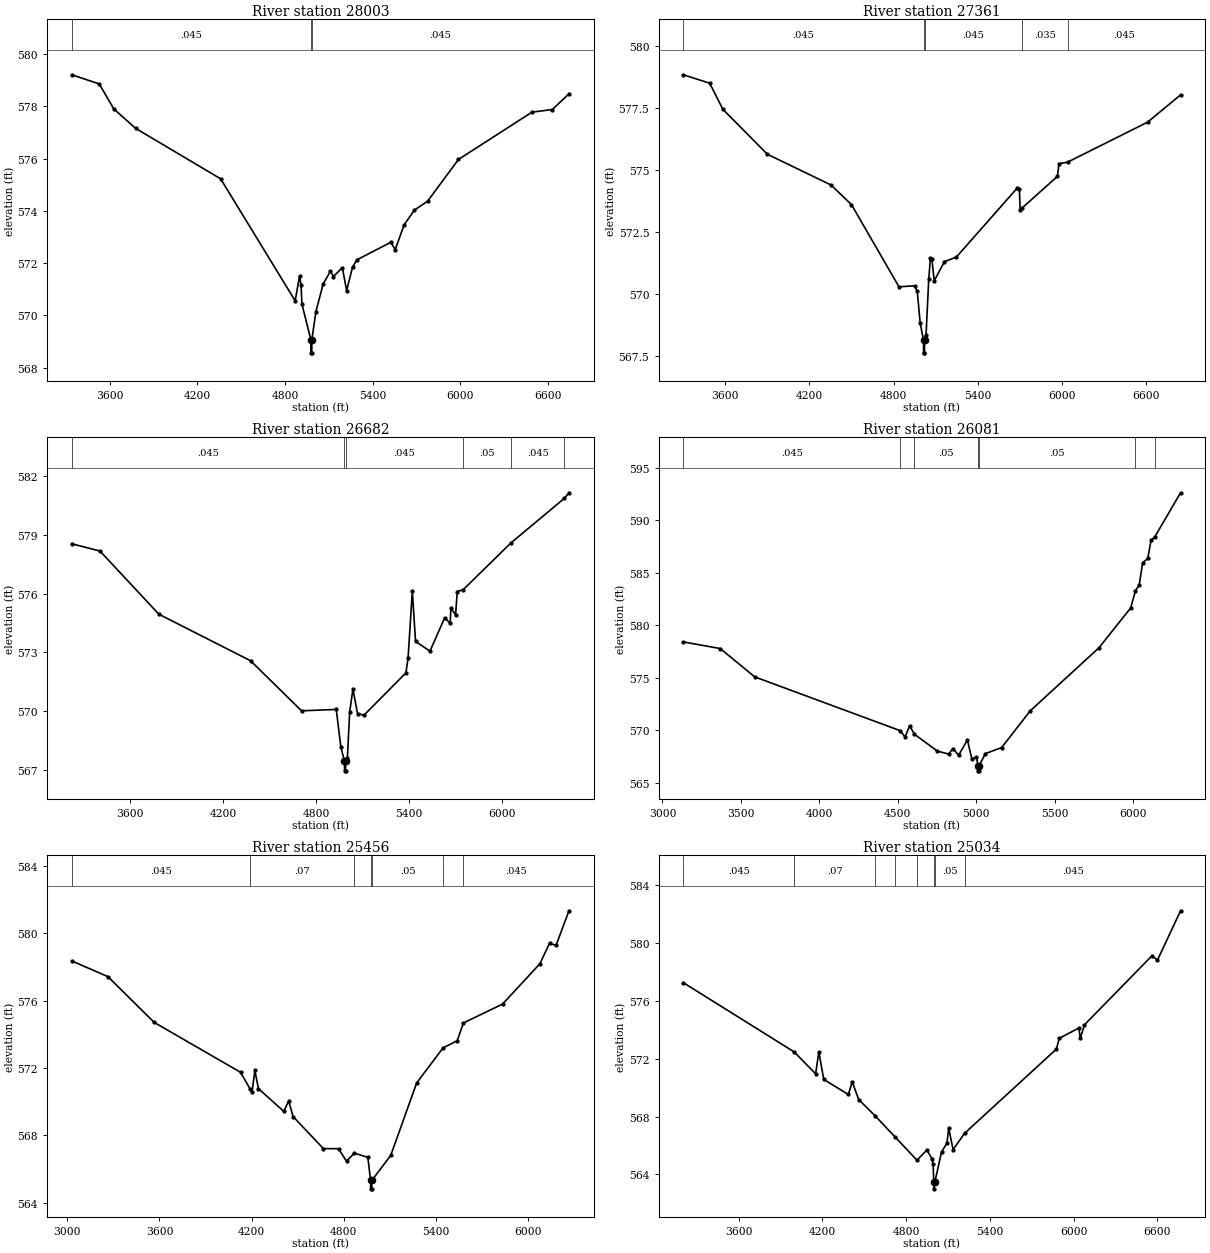
Type RM Length L Ch R = 1 ,28003   ,642,642,642
BEGIN DESCRIPTION:
A19385
END DESCRIPTION:
XS GIS Cut Line= 3
      2284182.36     13774859.22      2282632.35     13774897.21
      2280793.64     13775102.35
#Sta/Elev= 30
  3342.1  579.21  3529.5  578.86  3629.6   577.9  3778.4  577.16  4359.8  575.23
  4869.9  570.56    4900  571.52    4910  571.16  4916.4  570.43    4977  569.07
  4977.5  568.57  4983.4  568.57  4983.9  569.07  5011.8  570.15    5061   571.2
  5111.3   571.7  5131.4  571.49  5192.6  571.83    5222  570.95  5262.2  571.85
  5292.4  572.13  5523.8   572.8  5554.1  572.52  5614.4  573.46  5684.8  574.03
  5775.4  574.37  5986.7  575.97  6489.8  577.78  6628.5  577.88  6742.7  578.48
#Mann= 3 ,-1 , 0
  3342.1    .045       0    4977    .045       0  4983.9    .045       0
Bank Sta=4977,4983.9
XS Rating Curve= 0 ,0
Exp/Cntr=0.3,0.1

Type RM Length L Ch R = 1 ,27361   ,679,679,679
BEGIN DESCRIPTION:
A19384
END DESCRIPTION:
XS GIS Cut Line= 3
      2284174.76     13774775.63      2282358.81     13774251.37
      2280710.05     13774312.15
#Sta/Elev= 30
  3303.9  578.84    3491   578.5  3584.7  577.45  3901.6  575.64  4354.9   574.4
  4500.6  573.61  4838.7   570.3    4950  570.34    4969  570.12  4989.8  568.84
  5013.6  568.14  5014.1  567.64  5020.5  567.64    5021  568.14  5031.4  568.34
  5050.9  570.62  5062.7  571.45  5073.1  571.42  5089.7  570.54  5162.2  571.31
  5247.9   571.5  5678.2  574.26  5696.5  574.22  5701.5  573.41  5714.8  573.47
  5967.3  574.75  5978.4  575.26  6039.3  575.32  6608.8  576.93  6843.9  578.03
#Mann= 5 ,-1 , 0
  3303.9    .045       0  5013.6    .045       0    5021    .045       0
  5714.8    .035       0  6039.3    .045       0
Bank Sta=5013.6,5021
XS Rating Curve= 0 ,0
Exp/Cntr=0.3,0.1

Type RM Length L Ch R = 1 ,26682   ,601,601,601
BEGIN DESCRIPTION:
A19383
END DESCRIPTION:
XS GIS Cut Line= 3
      2284144.36     13774676.85      2282579.16     13773597.92
      2281318.92     13773263.88
#Sta/Elev= 30
  3224.9  578.55  3406.3  578.18    3786  574.95  4377.1  572.57  4705.9  570.01
  4929.5  570.08  4959.3  568.15  4982.4  567.44  4982.9  566.94  4989.7  566.94
  4990.2  567.44  5001.2  567.59  5016.1  569.96    5037  571.12  5066.8  569.86
  5108.7  569.79  5378.5  571.95  5392.5  572.71  5419.9  576.14  5440.6  573.56
  5533.7  573.06  5628.6  574.77  5663.6  574.48  5668.8  575.26  5698.7  574.92
  5709.6  576.11  5747.3   576.2  6054.9  578.59  6399.2  580.87  6429.7  581.16
#Mann= 6 ,-1 , 0
  3224.9    .045       0  4982.4    .045       0  4990.2    .045       0
  5747.3     .05       0  6054.9    .045       0  6399.2     .05       0
Bank Sta=4982.4,4990.2
XS Rating Curve= 0 ,0
Exp/Cntr=0.3,0.1

Type RM Length L Ch R = 1 ,26081   ,625,625,625
BEGIN DESCRIPTION:
A19382
END DESCRIPTION:
XS GIS Cut Line= 3
      2284144.35     13774585.65      2282860.29     13773066.05
       2281759.3     13772648.44
#Sta/Elev= 30
    3134   578.4  3368.6  577.77  3588.3  575.07  4516.1  569.94  4546.5  569.34
    4575  570.42  4605.3  569.61  4751.9     568  4823.4  567.72  4850.7  568.24
  4887.1  567.61  4943.1  569.06  4971.6  567.24  5000.2  567.44  5010.5  566.62
    5011  566.12    5018  566.12  5018.5  566.62  5057.4  567.76  5161.2  568.34
  5343.1  571.83  5781.5  577.85  5982.9  581.63  6013.9  583.28  6037.8  583.84
  6059.6  585.94  6091.7  586.35  6113.1  588.08  6137.2  588.42    6301  592.61
#Mann= 7 ,-1 , 0
    3134    .045       0  4516.1     .07       0  4605.3     .05       0
  5010.5     .05       0  5018.5     .05       0  6013.9     .07       0
  6137.2    .035       0
Bank Sta=5010.5,5018.5
XS Rating Curve= 0 ,0
Exp/Cntr=0.3,0.1

Type RM Length L Ch R = 1 ,25456   ,422,422,422
BEGIN DESCRIPTION:
GUADALUPE TRIBUTARY 4A 38.0
END DESCRIPTION:
XS GIS Cut Line= 3
      2284175.01     13774575.01        2283375.       13772775.
        2282175.       13772375.
#Sta/Elev= 30
  3030.2  578.36  3264.8  577.43  3566.4  574.71    4128  571.75    4190  570.76
  4203.2   570.6    4221  571.86  4244.2  570.78  4409.1  569.43  4441.2  570.05
  4469.9  569.12  4666.9  567.22  4765.4  567.21  4817.4  566.47  4868.4  566.95
  4956.2   566.7    4974  565.33  4974.5  564.83  4981.7  564.83  4982.2  565.33
  5105.4  566.82    5274  571.12  5445.6   573.2  5537.6  573.62  5578.1  574.68
  5832.7   575.8  6075.2  578.19  6138.4  579.41  6180.6  579.28  6264.9  581.34
#Mann= 7 ,-1 , 0
  3030.2    .045       0    4190     .07       0  4868.4     .05       0
    4974     .05       0  4982.2     .05       0  5445.6    .035       0
  5578.1    .045       0
Bank Sta=4974,4982.2
XS Rating Curve= 0 ,0
Exp/Cntr=0.3,0.1

Type RM Length L Ch R = 1 ,25034   ,490,490,490
BEGIN DESCRIPTION:
A19381
END DESCRIPTION:
XS GIS Cut Line= 3
      2284501.49     13774236.17       2283658.1     13772427.81
      2282100.51     13772260.65
#Sta/Elev= 30
  3203.6  577.26  3997.5  572.47  4150.9  570.96  4173.8  572.48    4209  570.57
    4385  569.53  4413.4   570.4  4459.2  569.18  4578.4  568.04  4719.1   566.6
  4876.9  564.98  4948.3  565.69  4984.2  565.08  4992.4  564.71  4997.4   563.5
  4997.9     563  5005.7   563.5  5052.8  565.55  5091.7  566.17  5104.1  567.19
  5135.9  565.72  5218.8  566.85  5875.9  572.67    5896  573.41  6036.8  574.13
  6046.9  573.41  6077.1  574.35  6559.8  579.12  6600.1  578.83  6765.5  582.24
#Mann= 8 ,-1 , 0
  3203.6    .045       0  3997.5     .07       0  4578.4    .045       0
  4719.1    .035       0  4876.9     .05       0  4997.4     .05       0
  5005.7     .05       0  5218.8    .045       0
Bank Sta=4997.4,5005.7
XS Rating Curve= 0 ,0
Exp/Cntr=0.3,0.1

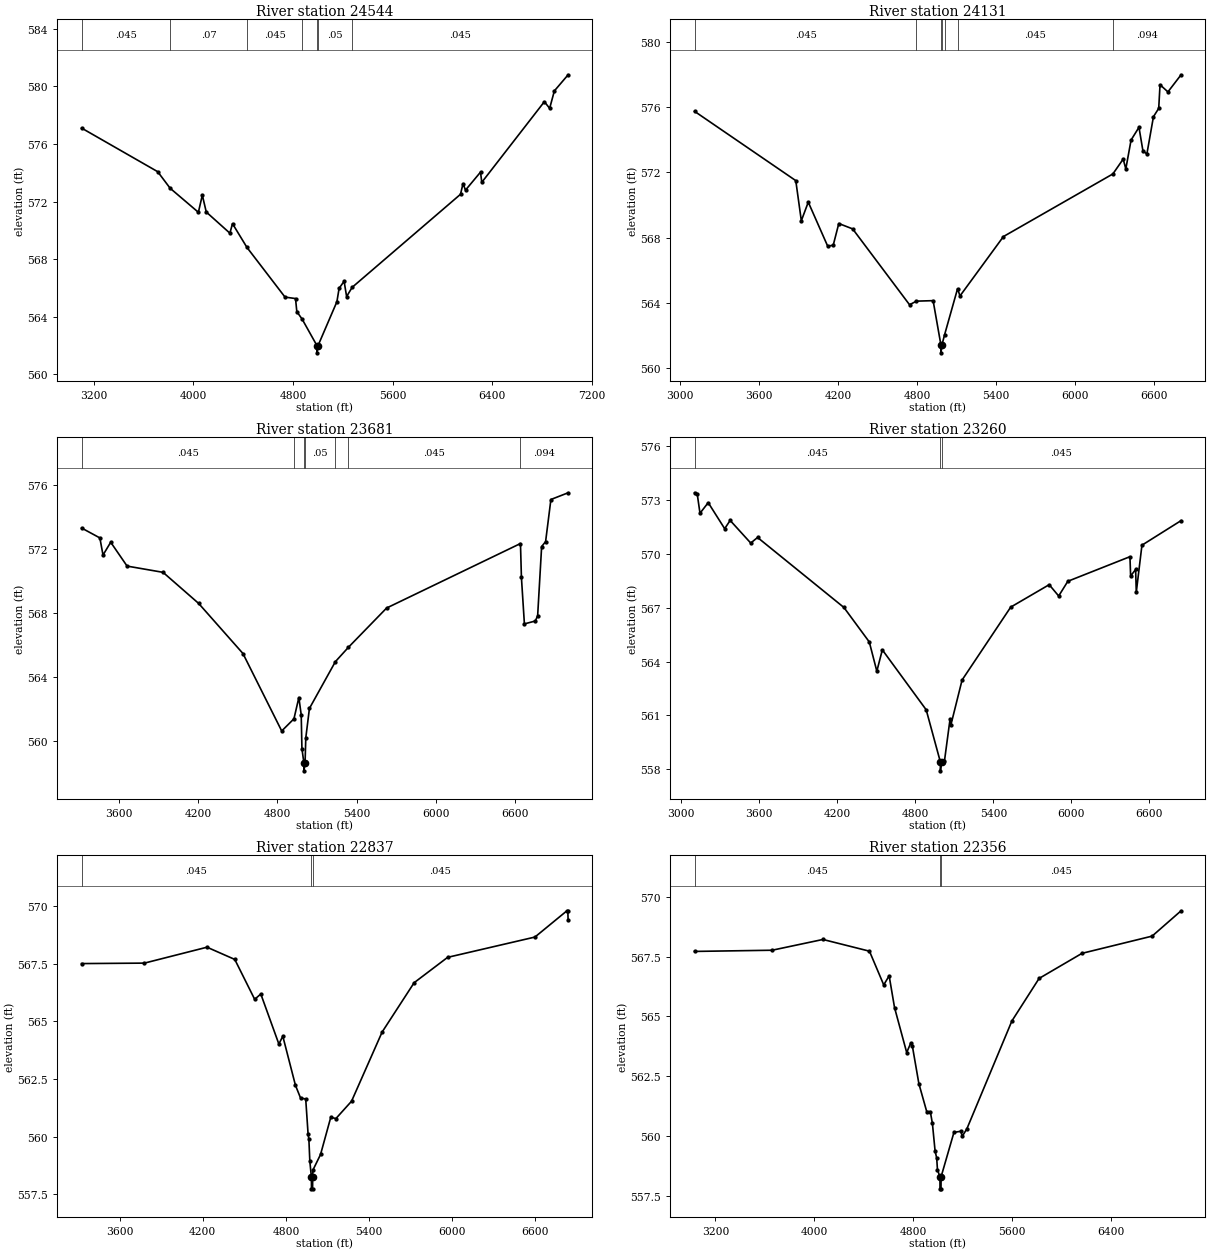
Type RM Length L Ch R = 1 ,24544   ,413,413,413
BEGIN DESCRIPTION:
GUADALUPE TRIBUTARY 4A 37.0
END DESCRIPTION:
XS GIS Cut Line= 3
        2284725.     13774125.01        2284125.       13772325.
      2282124.96       13772125.
#Sta/Elev= 30
  3102.9  577.11  3714.3  574.08  3814.3  572.93  4041.1  571.26  4072.7  572.45
  4104.3  571.28    4294  569.81  4315.1  570.47  4431.1  568.82  4736.8  565.37
  4821.1  565.27  4831.6  564.36  4874.3  563.84  4993.3     562  4993.8   561.5
  5001.9     562  5153.5  565.05  5171.1  565.98  5211.3  566.47  5231.4  565.41
  5276.1  566.05    6146  572.51  6166.1  573.25  6186.2   572.8  6306.8  574.05
  6316.8  573.34  6819.3  578.94    6862  578.48  6899.7  579.69  7010.3  580.81
#Mann= 7 ,-1 , 0
  3102.9    .045       0  3814.3     .07       0  4431.1    .045       0
  4874.3     .05       0  4993.3     .05       0  5001.9     .05       0
  5276.1    .045       0
Bank Sta=4993.3,5001.9
XS Rating Curve= 0 ,0
Exp/Cntr=0.3,0.1

Type RM Length L Ch R = 1 ,24131   ,450,450,450
BEGIN DESCRIPTION:
GUADALUPE TRIBUTARY 4A 36.0
END DESCRIPTION:
XS GIS Cut Line= 3
      2284925.01     13773775.03        2284325.       13771975.
        2282525.       13771975.
#Sta/Elev= 30
  3110.3  575.75  3879.8   571.5    3922  569.04  3974.7  570.18  4122.3  567.48
  4164.4  567.54  4206.6  568.87    4312  568.54  4744.2  563.89  4797.1  564.11
  4923.4  564.14  4982.3  561.44  4982.8  560.94  4990.9  561.44  5010.6  562.05
  5109.1  564.87  5127.7  564.43  5457.7  568.07  6289.4  571.91  6367.7  572.82
  6387.7  572.22  6427.7  573.99  6487.7  574.77  6517.7  573.33  6547.7  573.13
  6597.7  575.42  6637.7  575.93  6647.7  577.38  6707.7  576.94  6807.7  577.99
#Mann= 7 ,-1 , 0
  3110.3    .045       0  4797.1     .05       0  4982.3     .05       0
  4990.9     .05       0  5010.6     .07       0  5109.1    .045       0
  6289.4    .094       0
Bank Sta=4982.3,4990.9
XS Rating Curve= 0 ,0
Exp/Cntr=0.3,0.1

Type RM Length L Ch R = 1 ,23681   ,421,421,421
BEGIN DESCRIPTION:
GUADALUPE TRIBUTARY 4A 35.0
END DESCRIPTION:
XS GIS Cut Line= 3
      2285225.01     13773175.03        2284575.       13771625.
      2282574.98       13771825.
#Sta/Elev= 30
  3314.2  573.29  3453.1  572.67  3476.9   571.6  3535.3   572.4  3659.6  570.91
  3932.3  570.52  4202.2  568.58  4538.3  565.45  4832.4  560.61  4925.2  561.37
  4962.5   562.7  4980.4  561.62  4985.8  559.51  5000.6  558.62  5001.1  558.12
  5009.6  558.62  5015.1  560.18  5042.7  562.02  5239.5  564.94  5338.7  565.84
  5628.1  568.29  6643.5  572.32  6650.7   570.2  6673.3   567.3  6756.2  567.48
  6773.8  567.81    6804  572.13  6834.1  572.44  6874.3  575.07    7005  575.49
#Mann= 7 ,-1 , 0
  3314.2    .045       0  4925.2     .05       0  5000.6     .05       0
  5009.6     .05       0  5239.5     .07       0  5338.7    .045       0
  6643.5    .094       0
Bank Sta=5000.6,5009.6
XS Rating Curve= 0 ,0
Exp/Cntr=0.3,0.1

Type RM Length L Ch R = 1 ,23260   ,423,423,423
BEGIN DESCRIPTION:
GUADALUPE TRIBUTARY 4A 34.0
END DESCRIPTION:
XS GIS Cut Line= 3
      2285374.99     13773074.98        2284775.       13771275.
      2282974.95     13771675.01
#Sta/Elev= 30
  3102.2   573.4  3123.3  573.32  3144.3  572.26  3207.6  572.85  3334.1   571.4
  3376.2  571.86  3534.4   570.6  3587.1  570.91  4251.1  567.01  4446.1  565.09
  4504.1  563.46  4546.3  564.65  4883.6  561.31  4992.4  558.41  4992.9  557.91
  5001.4  558.41  5023.9  558.45  5067.4  560.81  5072.5  560.44  5159.6  562.97
  5533.5  567.03  5829.3  568.28  5902.3  567.65  5972.7  568.47  6450.3  569.84
  6455.5  568.76  6493.9  569.13    6499  567.86  6542.5  570.48  6843.5  571.85
#Mann= 3 ,-1 , 0
  3102.2    .045       0  4992.4    .045       0  5001.4    .045       0
Bank Sta=4992.4,5001.4
XS Rating Curve= 0 ,0
Exp/Cntr=0.3,0.1

Type RM Length L Ch R = 1 ,22837   ,481,481,481
BEGIN DESCRIPTION:
A19380
END DESCRIPTION:
XS GIS Cut Line= 3
      2286545.37     13771686.22      2284926.99     13770926.41
       2283286.9     13771450.33
#Sta/Elev= 30
  3326.1   567.5  3779.4  567.52  4230.9  568.21  4431.2  567.68  4574.8  565.95
    4619  566.18  4749.3  564.01  4777.7  564.35  4868.9  562.22  4906.3  561.66
  4942.9  561.63  4960.2  560.09  4965.7  559.89  4972.6  558.93    4984  558.23
  4984.5  557.73  4992.5  557.73    4993  558.23  4994.6  558.54  5049.9  559.22
  5123.5  560.83    5161  560.78  5273.5  561.53    5494  564.53  5724.9  566.67
  5966.4  567.77  6596.2  568.65  6827.2  569.79  6833.5  569.78  6835.7  569.37
#Mann= 3 ,-1 , 0
  3326.1    .045       0    4984    .045       0    4993    .045       0
Bank Sta=4984,4993
XS Rating Curve= 0 ,0
Exp/Cntr=0.3,0.1

Type RM Length L Ch R = 1 ,22356   ,542,542,542
BEGIN DESCRIPTION:
GUADALUPE TRIBUTARY 4A 33.0
END DESCRIPTION:
XS GIS Cut Line= 3
      2286924.96     13771324.98        2285125.       13770525.
        2283325.       13771325.
#Sta/Elev= 30
  3030.3  567.72  3658.8  567.77  4069.9  568.22  4446.7  567.73  4562.3  566.32
  4606.1   566.7  4649.8  565.37  4748.3  563.49  4781.2  563.89  4794.2  563.76
  4846.8  562.19  4910.4  561.02  4939.2  561.02  4956.3  560.53  4978.1  559.37
  4991.1  559.08  4997.3  558.59  5017.4  558.29  5017.9  557.79    5026  557.79
  5026.5  558.29  5130.7  560.15  5188.1   560.2    5197  559.98  5234.6  560.29
  5599.8  564.81  5820.1  566.59  6167.5  567.64  6735.2  568.36  6969.8  569.42
#Mann= 3 ,-1 , 0
  3030.3    .045       0  5017.4    .045       0  5026.5    .045       0
Bank Sta=5017.4,5026.5
XS Rating Curve= 0 ,0
Exp/Cntr=0.3,0.1

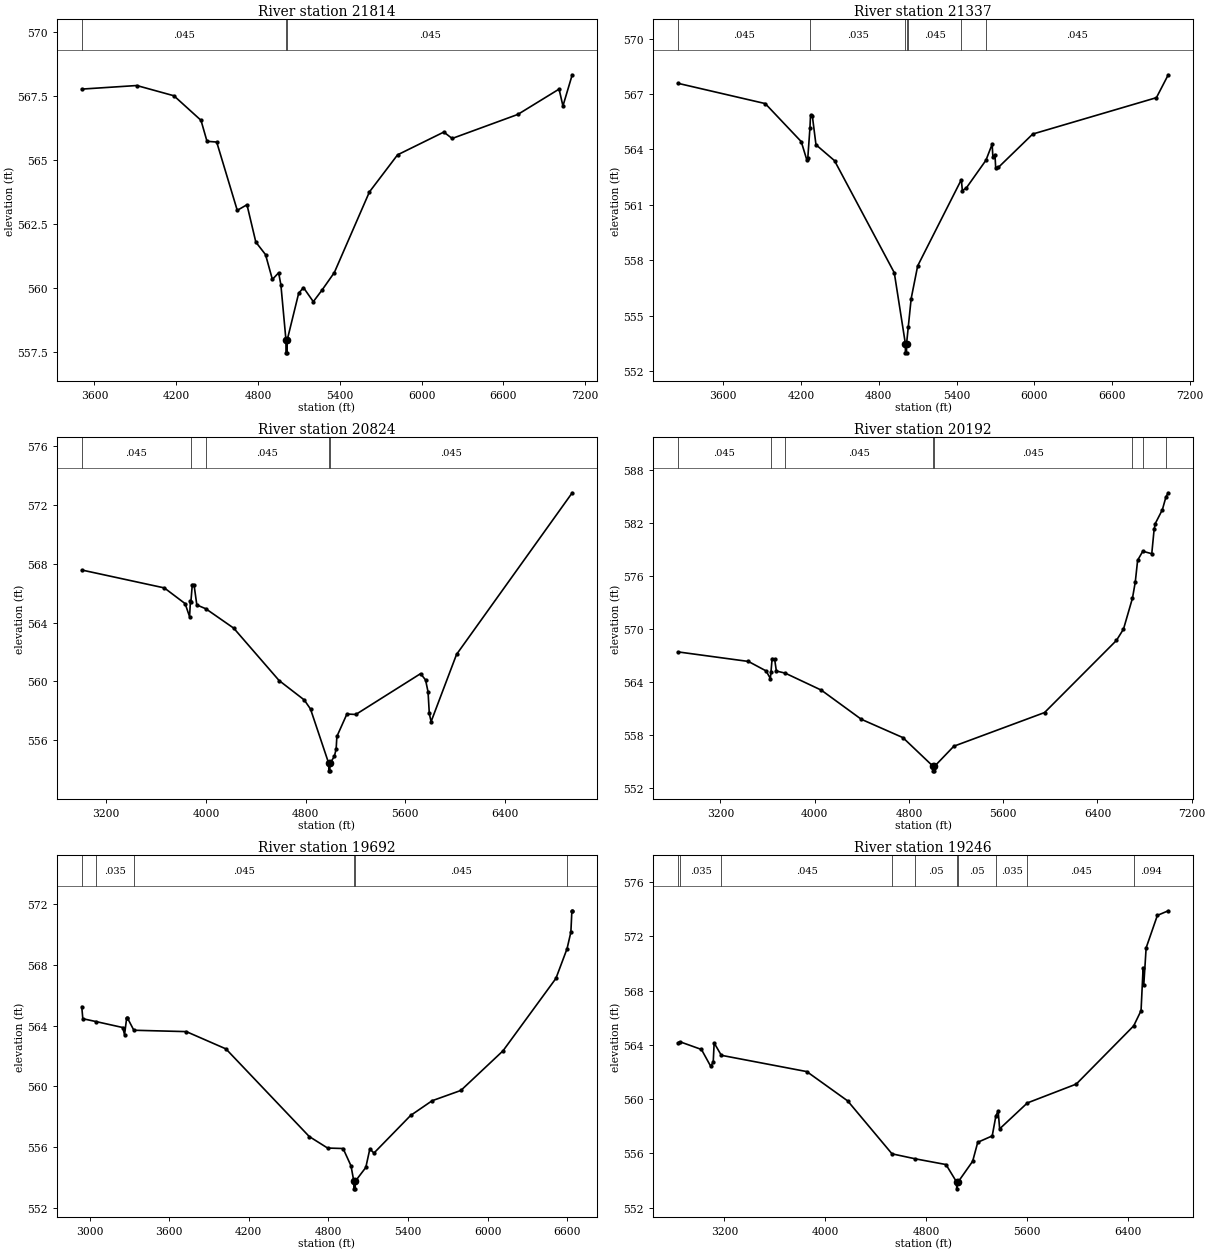
Type RM Length L Ch R = 1 ,21814   ,477,477,477
BEGIN DESCRIPTION:
GUADALUPE TRIBUTARY 4A 32.0
END DESCRIPTION:
XS GIS Cut Line= 3
      2286294.63     13770858.01      2285124.54     13770014.64
      2283028.77     13770523.39
#Sta/Elev= 30
    3507  567.77  3910.6  567.91    4183  567.51  4381.9  566.55    4426  565.73
  4497.2   565.7  4648.1  563.03  4719.3  563.25  4784.3  561.79  4855.5   561.3
  4905.8  560.33  4951.7  560.59  4968.2  560.12  5005.4  557.96  5005.9  557.46
    5014  557.46  5014.5  557.96  5098.7  559.79  5134.1  560.01  5206.1  559.46
  5270.9  559.92  5360.5   560.6  5617.8  563.75  5824.3   565.2  6163.7  566.09
  6224.9  565.84  6706.8  566.78  7009.5  567.77  7037.8  567.11    7106  568.33
#Mann= 3 ,-1 , 0
    3507    .045       0  5005.4    .045       0  5014.5    .045       0
Bank Sta=5005.4,5014.5
XS Rating Curve= 0 ,0
Exp/Cntr=0.3,0.1

Type RM Length L Ch R = 1 ,21337   ,513,513,513
BEGIN DESCRIPTION:
A19379
END DESCRIPTION:
XS GIS Cut Line= 4
      2286135.09      13770569.3      2285451.26     13769680.32
      2284410.31     13769619.53      2283004.63     13770417.35
#Sta/Elev= 30
    3251  567.58  3925.1  566.48  4202.6  564.42  4245.1  563.44  4253.1  563.52
  4269.8  565.17  4274.1  565.84  4288.6  565.79  4316.2  564.25    4459  563.39
  4919.8  557.32  5005.2  553.48  5005.7  552.98  5014.1  552.98  5014.6  553.48
  5027.3  554.36    5050  555.92  5100.1  557.69  5436.8  562.36  5444.4  561.77
  5475.1  561.91  5626.3  563.41  5674.1  564.28  5679.9  563.58  5695.7  563.72
  5701.5     563  5723.1  563.03    5987  564.83  6940.3   566.8  7031.6  568.04
#Mann= 7 ,-1 , 0
    3251    .045       0  4269.8    .035       0  5005.2    .035       0
  5014.6    .035       0  5027.3    .045       0  5436.8    .035       0
  5626.3    .045       0
Bank Sta=5005.2,5014.6
XS Rating Curve= 0 ,0
Exp/Cntr=0.3,0.1

Type RM Length L Ch R = 1 ,20824   ,632,632,632
BEGIN DESCRIPTION:
A19378
END DESCRIPTION:
XS GIS Cut Line= 4
      2286135.12     13770500.95       2285306.9     13769224.43
      2284638.26     13769140.85      2282899.17     13769224.38
#Sta/Elev= 30
  3003.5  567.58  3666.2  566.36  3833.1  565.29  3868.9   564.4  3875.6  565.44
  3879.5  565.42  3890.8  566.59  3904.6  566.58    3927   565.2  3999.2  564.94
    4223  563.62  4587.5  560.05  4789.1  558.73  4839.5  558.11    4986   554.4
  4986.5   553.9  4994.9   553.9  4995.4   554.4    5031  554.89  5045.3  555.39
  5051.1  556.24  5131.7  557.77  5203.1  557.74  5722.9  560.52  5762.9  560.09
  5782.9  559.28  5792.9  557.81  5807.3  557.25  6011.6  561.83  6940.1  572.84
#Mann= 5 ,-1 , 0
  3003.5    .045       0  3879.5    .035       0  3999.2    .045       0
    4986    .045       0  4995.4    .045       0
Bank Sta=4986,4995.4
XS Rating Curve= 0 ,0
Exp/Cntr=0.3,0.1

Type RM Length L Ch R = 1 ,20192   ,500,500,500
BEGIN DESCRIPTION:
GUADALUPE TRIBUTARY 4A 31.0
END DESCRIPTION:
XS GIS Cut Line= 3
      2286125.03     13770425.04        2284925.       13768625.
      2282924.98       13768625.
#Sta/Elev= 30
  2837.4  567.42  3436.9  566.34  3587.1  565.27  3623.2  564.41  3628.4  565.12
  3638.2  566.66  3659.2  566.63  3674.2  565.26  3749.1  565.02  4055.8   563.1
  4395.3  559.81  4748.4  557.74  5005.4  554.49  5005.9  553.99  5015.7  553.99
  5016.2  554.49  5180.8  556.77  5950.8  560.57  6560.8  568.71  6620.8  569.99
  6697.1  573.49  6720.8   575.3  6740.8  577.76  6784.7  578.78  6860.8   578.5
  6880.8  581.25  6890.8  581.91  6950.8  583.47  6981.6  584.93  7000.8  585.38
#Mann= 8 ,-1 , 0
  2837.4    .045       0  3628.4    .035       0  3749.1    .045       0
  5005.4    .045       0  5016.2    .045       0  6697.1    .094       0
  6784.7    .063       0  6981.6    .035       0
Bank Sta=5005.4,5016.2
XS Rating Curve= 0 ,0
Exp/Cntr=0.3,0.1

Type RM Length L Ch R = 1 ,19692   ,446,446,446
BEGIN DESCRIPTION:
GUADALUPE TRIBUTARY 4A 30.0
END DESCRIPTION:
XS GIS Cut Line= 3
      2286725.01       13769125.        2284925.       13768125.
      2283324.97     13768475.01
#Sta/Elev= 30
  2941.3  565.26  2949.3  564.46  3050.4  564.27  3250.2  563.88  3263.9   563.4
  3279.9  564.52  3285.6  564.51    3334   563.7  3729.5  563.61  4028.1  562.47
  4656.1  556.69  4794.5  555.93  4911.2   555.9  4970.7  554.76  4992.1  553.74
  4992.6  553.24  5002.6  553.24  5003.1  553.74  5082.3  554.65  5112.7  555.87
  5143.7   555.6  5420.1  558.08  5582.1  559.05  5798.9  559.73  6116.2  562.34
  6515.4  567.12    6599  569.07    6628  570.17  6635.7  571.58  6638.3  571.58
#Mann= 6 ,-1 , 0
  2941.3     .07       0  3050.4    .035       0    3334    .045       0
  4992.1    .045       0  5003.1    .045       0    6599    .094       0
Bank Sta=4992.1,5003.1
XS Rating Curve= 0 ,0
Exp/Cntr=0.3,0.1

Type RM Length L Ch R = 1 ,19246   ,429,429,429
BEGIN DESCRIPTION:
GUADALUPE TRIBUTARY 4A 29.0
END DESCRIPTION:
XS GIS Cut Line= 3
      2286675.02     13768925.01        2284875.       13767725.
      2283275.04     13768374.98
#Sta/Elev= 30
  2830.4  564.15  2846.8  564.23  3018.2  563.66  3090.3  562.44  3111.4   562.7
  3118.9  564.14  3175.7  563.23  3853.5  562.03    4178  559.87  4529.5  555.97
  4715.2   555.6  4957.7  555.18  5042.2  553.89  5042.7  553.39  5053.2  553.89
  5169.2  555.42  5209.6  556.82  5324.4  557.29  5353.9  558.78  5371.5  559.12
  5383.4  557.81  5603.1  559.72  5991.1  561.11  6446.6   565.4  6504.9  566.52
  6521.3  569.69  6526.7  568.44  6545.3  571.15  6634.4  573.54  6720.7  573.88
#Mann= 10 ,-1 , 0
  2830.4     .07       0  2846.8    .035       0  3175.7    .045       0
  4529.5    .035       0  4715.2     .05       0  5042.2     .05       0
  5053.2     .05       0  5353.9    .035       0  5603.1    .045       0
  6446.6    .094       0
Bank Sta=5042.2,5053.2
XS Rating Curve= 0 ,0
Exp/Cntr=0.3,0.1