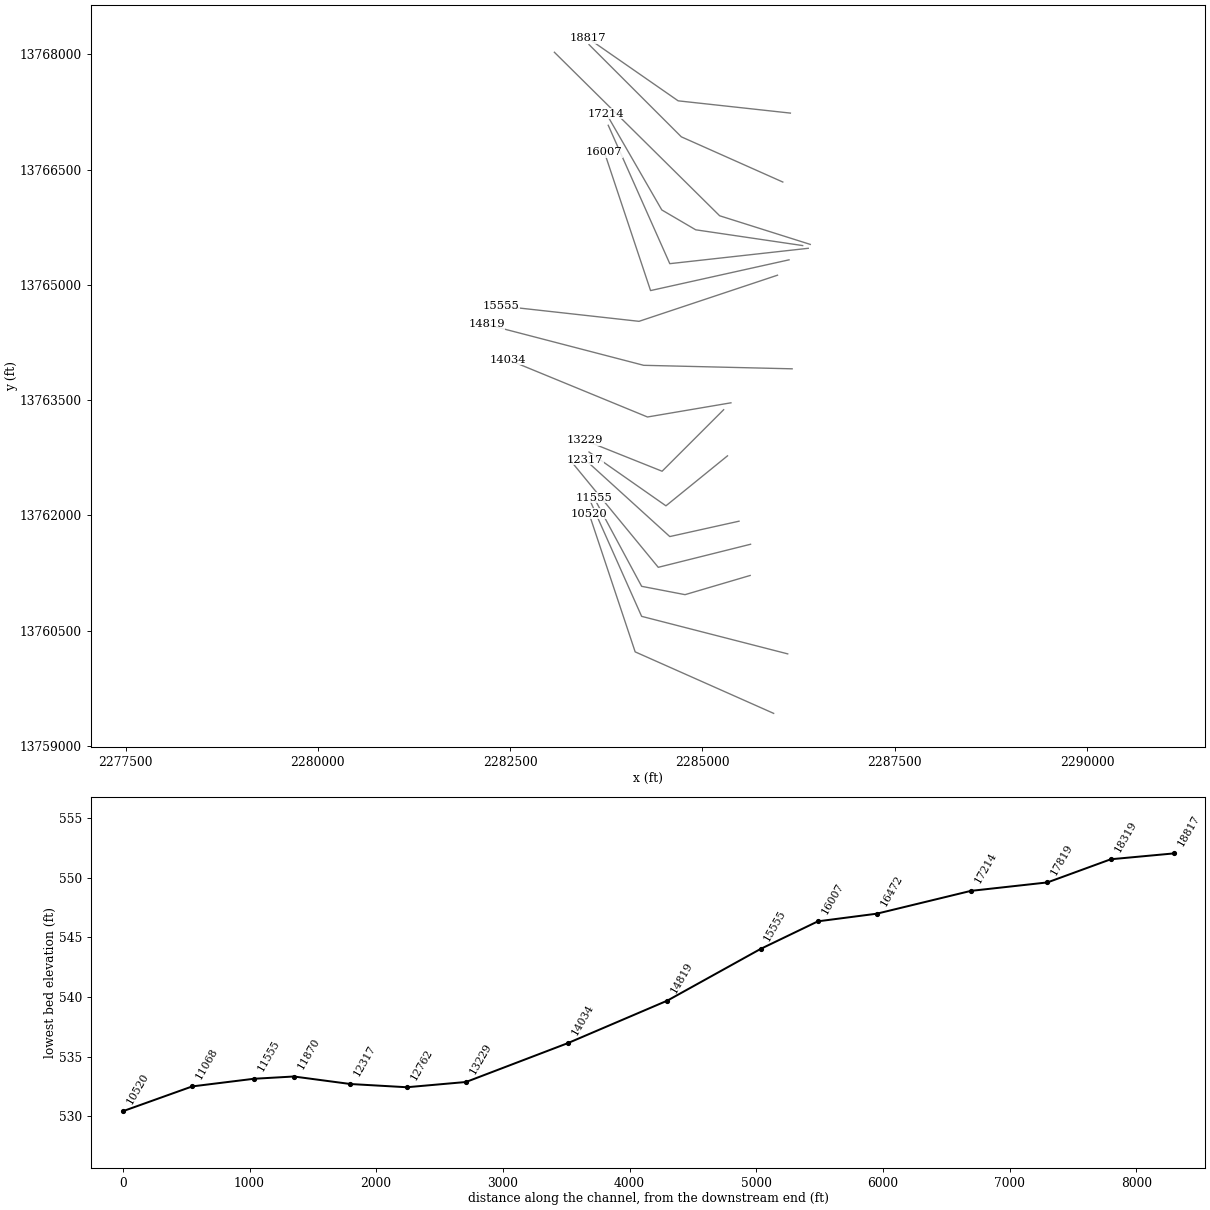
HEC-RAS study GUADALUPE TRIBUTARY 4A.prj: GUADALUPE TRIBUTARY 4A Base Level Engineering

--- GUADALUPE TRIBUTARY 4A.g01 (geometry) --- (continued)

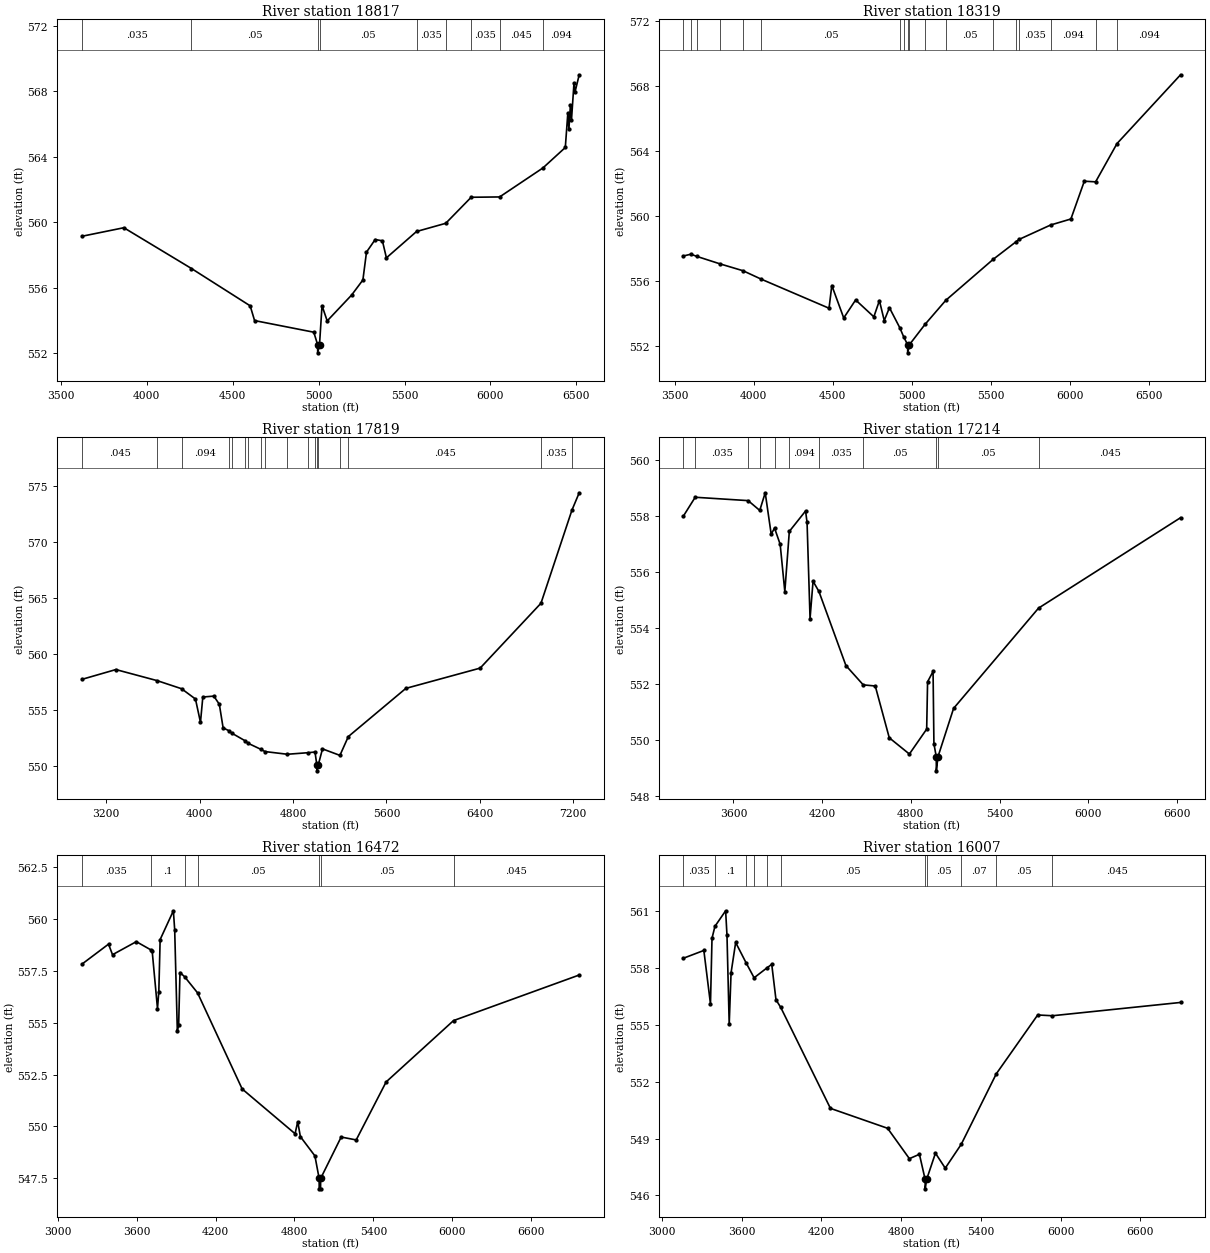
Type RM Length L Ch R = 1 ,18817   ,498,498,498
BEGIN DESCRIPTION:
A19377
END DESCRIPTION:
XS GIS Cut Line= 3
      2286142.69     13767233.71      2284683.85     13767393.27
      2283513.71     13768206.29
#Sta/Elev= 30
  3624.1  559.16  3867.1  559.68  4260.4  557.19  4602.1  554.91  4627.7  554.01
  4972.2   553.3  4994.4  552.54  4994.9  552.04  5005.5  552.54  5020.1  554.92
  5050.2  553.99  5192.4  555.57  5257.9  556.49  5278.8  558.19  5329.5  558.96
  5371.4  558.88  5394.7  557.84    5570  559.45  5739.9  559.95  5887.9  561.54
  6053.4  561.56  6305.3  563.33  6435.6  564.58  6450.4   566.7  6456.5  565.69
  6465.3  567.19  6471.4  566.25  6486.2  568.53  6492.3  567.98  6516.5  569.02
#Mann= 9 ,-1 , 0
  3624.1    .035       0  4260.4     .05       0  4994.4     .05       0
  5005.5     .05       0    5570    .035       0  5739.9    .094       0
  5887.9    .035       0  6053.4    .045       0  6305.3    .094       0
Bank Sta=4994.4,5005.5
XS Rating Curve= 0 ,0
Exp/Cntr=0.3,0.1

Type RM Length L Ch R = 1 ,18319   ,500,500,500
BEGIN DESCRIPTION:
GUADALUPE TRIBUTARY 4A 28.0
END DESCRIPTION:
XS GIS Cut Line= 3
      2286043.88     13766337.15        2284725.       13766925.
      2283525.01     13768124.99
#Sta/Elev= 30
  3555.9  557.52  3602.9  557.63    3642  557.49  3785.2  557.04  3932.6  556.61
  4047.8  556.09  4475.8   554.3  4493.5   555.7  4568.7   553.7  4643.9  554.81
    4759  553.77  4794.2  554.77  4824.7  553.54  4857.5  554.33  4922.8   553.1
  4947.4  552.54  4972.4  552.05  4972.9  551.55  4983.5  552.05    5082   553.3
  5213.8  554.79  5512.5  557.31  5657.8   558.4  5676.3  558.54    5876  559.43
    6004   559.8  6088.8  562.13  6160.2  562.09  6295.4  564.45  6696.9  568.69
#Mann= 18 ,-1 , 0
  3555.9    .035       0  3602.9    .063       0    3642    .035       0
  3785.2    .063       0  3932.6    .035       0  4047.8     .05       0
  4922.8    .035       0  4947.4     .05       0  4972.4     .05       0
  4983.5     .05       0    5082    .035       0  5213.8     .05       0
  5512.5    .035       0  5657.8     .05       0  5676.3    .035       0
    5876    .094       0  6160.2    .063       0  6295.4    .094       0
Bank Sta=4972.4,4983.5
XS Rating Curve= 0 ,0
Exp/Cntr=0.3,0.1

Type RM Length L Ch R = 1 ,17819   ,605,605,605
BEGIN DESCRIPTION:
GUADALUPE TRIBUTARY 4A 27.0
END DESCRIPTION:
XS GIS Cut Line= 3
      2286401.06     13765525.64      2285223.32     13765897.96
      2283074.98     13768025.02
#Sta/Elev= 30
  2992.6  557.78  3282.1  558.65    3636  557.66  3844.5  556.94  3963.8  556.02
  4006.7  553.94  4026.8   556.2  4121.2  556.28  4168.3  555.55  4200.6  553.45
  4250.3  553.19    4274  552.98  4386.2  552.31  4416.7  552.06    4522  551.54
  4559.5  551.33  4750.9  551.09  4929.5  551.23  4987.8  551.29  5003.8  550.11
  5004.3  549.61    5015  550.11  5051.9  551.57  5201.2  550.99  5273.3  552.67
    5766  556.97  6402.4  558.78  6923.4  564.57  7188.6  572.88    7251  574.43
#Mann= 18 ,-1 , 0
  2992.6    .045       0    3636    .035       0  3844.5    .094       0
  4250.3      .1       0    4274    .094       0  4386.2      .1       0
  4416.7    .063       0    4522      .1       0  4559.5    .063       0
  4750.9     .05       0  4929.5    .094       0  4987.8     .05       0
  5003.8     .05       0    5015     .05       0  5201.2    .094       0
  5273.3    .045       0  6923.4    .035       0  7188.6     .05       0
Bank Sta=5003.8,5015
XS Rating Curve= 0 ,0
Exp/Cntr=0.3,0.1

Type RM Length L Ch R = 1 ,17214   ,742,742,742
BEGIN DESCRIPTION:
A19376
END DESCRIPTION:
XS GIS Cut Line= 4
      2286302.26     13765510.45      2284911.79      13765715.6
       2284471.1     13765973.94      2283749.62     13767227.03
#Sta/Elev= 30
  3262.1     558  3341.7  558.67  3699.7  558.55  3778.3   558.2  3815.3  558.83
  3855.7  557.35  3878.3  557.57  3916.4  556.99  3947.9   555.3  3978.3  557.45
  4088.2  558.18  4098.3  557.77  4118.5  554.34  4138.8  555.67  4178.2  555.31
  4361.1  552.66  4478.2  551.97  4559.5  551.93  4654.3  550.08  4790.3   549.5
  4907.3  550.39  4913.4  552.08  4950.5  552.45  4956.3  549.87  4972.2   549.4
  4972.7   548.9  4983.5   549.4  5089.3  551.13  5663.7  554.71  6624.4  557.94
#Mann= 11 ,-1 , 0
  3262.1    .045       0  3341.7    .035       0  3699.7    .045       0
  3778.3    .035       0  3878.3      .1       0  3978.3    .094       0
  4178.2    .035       0  4478.2     .05       0  4972.2     .05       0
  4983.5     .05       0  5663.7    .045       0
Bank Sta=4972.2,4983.5
XS Rating Curve= 0 ,0
Exp/Cntr=0.3,0.1

Type RM Length L Ch R = 1 ,16472   ,465,465,465
BEGIN DESCRIPTION:
GUADALUPE TRIBUTARY 4A 26.0
END DESCRIPTION:
XS GIS Cut Line= 3
      2286375.01       13765475.        2284575.       13765275.
      2283774.98     13767075.04
#Sta/Elev= 30
  3184.6  557.84  3385.8   558.8    3416  558.29  3597.1  558.92  3705.7  558.53
  3717.9  558.45  3758.1  555.69  3768.2  556.51  3778.2  559.02  3878.9  560.41
  3888.9  559.49    3909  554.62  3919.1  554.92  3929.2  557.43  3963.9  557.23
  4062.7  556.45  4402.1  551.81  4804.5  549.65  4824.6  550.23  4844.8  549.51
  4955.4  548.58  4987.5  547.49    4988  546.99  4998.4  546.99  4998.9  547.49
    5155  549.49  5269.3  549.35    5497  552.15  6009.6  555.11  6965.5  557.31
#Mann= 7 ,-1 , 0
  3184.6    .035       0  3705.7      .1       0  3963.9    .094       0
  4062.7     .05       0  4987.5     .05       0  4998.9     .05       0
  6009.6    .045       0
Bank Sta=4987.5,4998.9
XS Rating Curve= 0 ,0
Exp/Cntr=0.3,0.1

Type RM Length L Ch R = 1 ,16007   ,452,452,452
BEGIN DESCRIPTION:
GUADALUPE TRIBUTARY 4A 25.0
END DESCRIPTION:
XS GIS Cut Line= 3
      2286125.01       13765325.        2284325.       13764925.
      2283724.99     13766725.02
#Sta/Elev= 30
  3161.4   558.5  3315.1  558.91    3365  556.09  3376.5  559.55  3398.5  560.18
    3479     561  3489.2  559.71  3505.9  555.02  3519.9  557.73  3554.5  559.33
  3632.1  558.27  3693.3  557.47  3793.5  558.01    3826  558.18    3858  556.31
  3893.7  555.91  4267.8  550.59    4698  549.54  4861.9  547.94  4937.4  548.17
  4980.4  546.85  4980.9  546.35  4991.9  546.85    5058  548.23  5131.8  547.44
  5252.4   548.7  5515.9  552.41  5827.5  555.51  5938.6  555.47  6902.7  556.17
#Mann= 11 ,-1 , 0
  3161.4    .035       0  3398.5      .1       0  3632.1    .063       0
  3693.3      .1       0  3793.5    .035       0  3893.7     .05       0
  4980.4     .05       0  4991.9     .05       0  5252.4     .07       0
  5515.9     .05       0  5938.6    .045       0
Bank Sta=4980.4,4991.9
XS Rating Curve= 0 ,0
Exp/Cntr=0.3,0.1

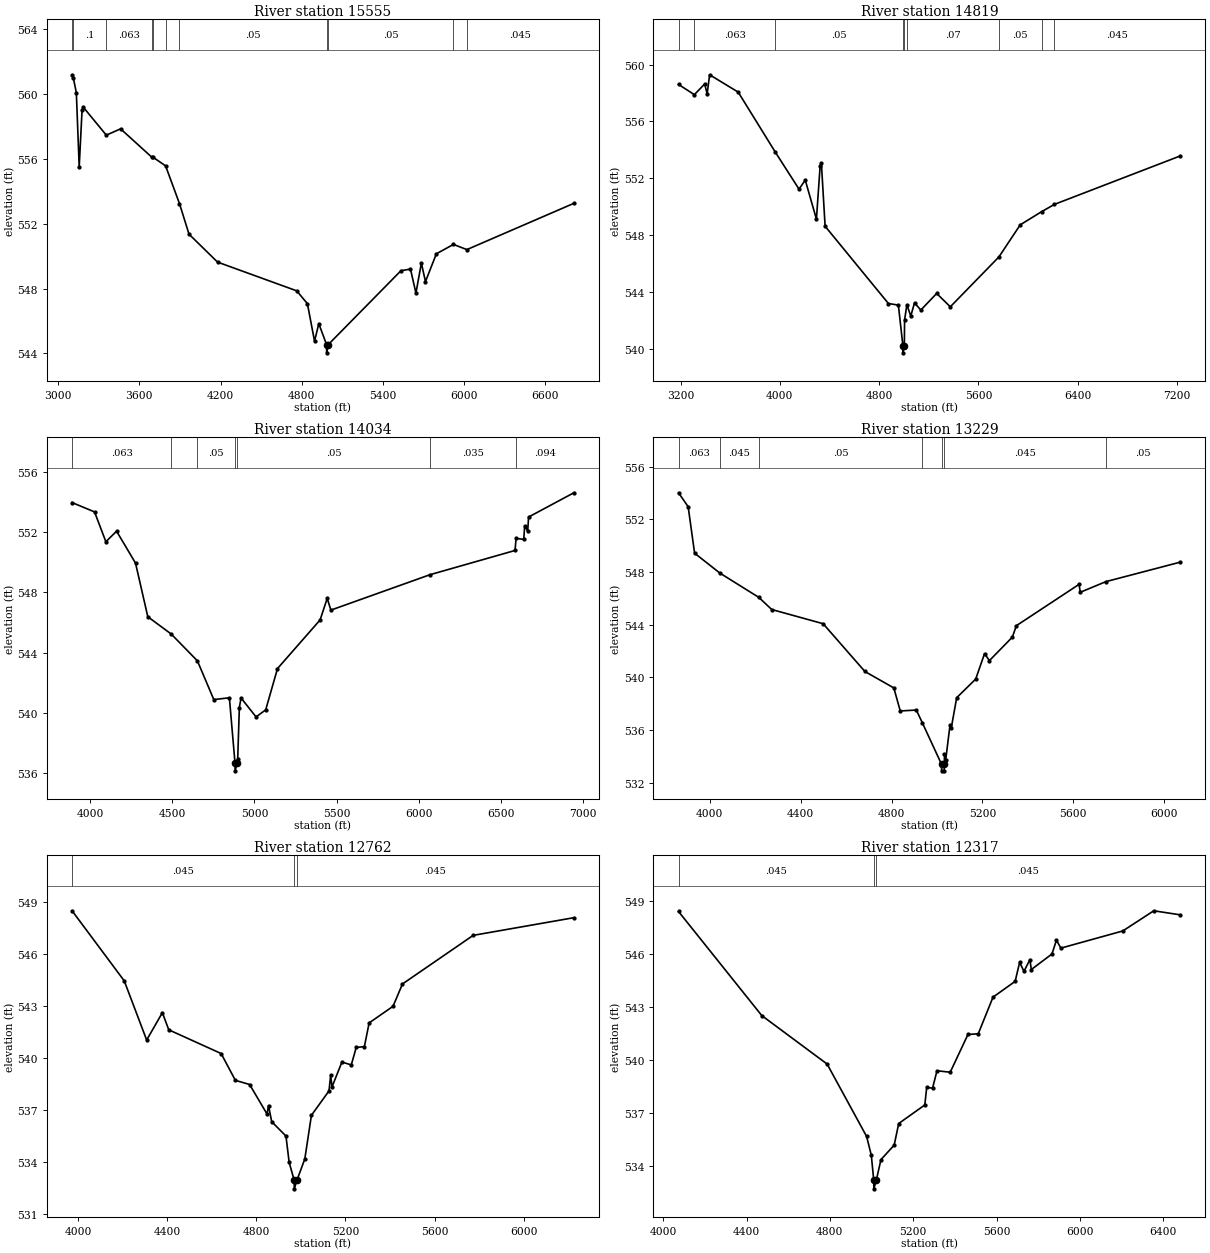
Type RM Length L Ch R = 1 ,15555   ,736,736,736
BEGIN DESCRIPTION:
GUADALUPE TRIBUTARY 4A 24.0
END DESCRIPTION:
XS GIS Cut Line= 3
      2285974.97     13765124.99        2284175.       13764525.
      2282375.01       13764725.
#Sta/Elev= 30
  3102.7  561.17  3112.1  560.98  3134.3  560.06  3155.4   555.5  3176.5  558.98
    3187  559.16  3355.8  557.45  3461.1  557.84    3691   556.1  3702.5  556.08
  3793.8  555.56  3896.6  553.23    3967  551.35  4177.8  549.63  4762.9  547.86
  4841.9  547.07  4894.6  544.76  4926.2  545.84  4983.7  544.54  4984.2  544.04
  4995.2  544.54  5533.3   549.1  5603.7   549.2    5644  547.72  5684.2  549.57
  5714.4  548.43  5794.9  550.14  5921.1  550.72  6020.5   550.4  6811.1  553.25
#Mann= 11 ,-1 , 0
  3102.7    .094       0  3112.1      .1       0  3355.8    .063       0
    3691    .035       0  3702.5      .1       0  3793.8    .094       0
  3896.6     .05       0  4983.7     .05       0  4995.2     .05       0
  5921.1     .07       0  6020.5    .045       0
Bank Sta=4983.7,4995.2
XS Rating Curve= 0 ,0
Exp/Cntr=0.3,0.1

Type RM Length L Ch R = 1 ,14819   ,785,785,785
BEGIN DESCRIPTION:
GUADALUPE TRIBUTARY 4A 23.0
END DESCRIPTION:
XS GIS Cut Line= 3
      2286165.47     13763907.24      2284235.56     13763952.83
      2282191.67      13764484.7
#Sta/Elev= 30
    3184   558.6  3311.4  557.88  3394.5  558.63  3414.5  557.94  3434.5  559.28
  3664.6  558.06    3964  553.83  4154.7  551.23  4204.8  551.87  4294.8  549.12
  4324.8  552.87  4334.8  553.05  4364.8  548.62  4874.9  543.18    4955  543.07
  4991.5  540.21    4992  539.71  5003.1  540.21    5005  542.02  5023.4  543.09
    5055   542.3    5085  543.23  5135.7  542.72  5263.5  543.89  5373.4  542.95
  5764.9  546.46  5936.8  548.72  6109.9  549.65  6212.5  550.16  7226.4  553.57
#Mann= 9 ,-1 , 0
    3184    .094       0  3311.4    .063       0    3964     .05       0
  4991.5     .05       0  5003.1     .05       0  5023.4     .07       0
  5764.9     .05       0  6109.9     .07       0  6212.5    .045       0
Bank Sta=4991.5,5003.1
XS Rating Curve= 0 ,0
Exp/Cntr=0.3,0.1

Type RM Length L Ch R = 1 ,14034   ,805,805,805
BEGIN DESCRIPTION:
GUADALUPE TRIBUTARY 4A 21.0
END DESCRIPTION:
XS GIS Cut Line= 3
      2285370.02       13763465.      2284284.93     13763280.54
      2282475.01       13764025.
#Sta/Elev= 30
  3888.6  553.96  4025.6  553.34  4094.5  551.36  4159.8  552.06  4275.3  549.94
  4350.1  546.38    4493  545.23  4652.4  543.45  4752.3  540.88  4847.2     541
  4881.6  536.65  4882.1  536.15  4893.9  536.65  4897.9  536.94    4908  540.35
  4918.2  540.99  5009.8  539.73  5068.5   540.2  5140.4  542.94  5400.1  546.17
  5443.3   547.6  5465.7  546.82  6069.2  549.17  6587.8  550.78  6594.2  551.58
  6641.1  551.52  6646.5  552.41    6665  552.06  6670.4     553  6946.3  554.61
#Mann= 7 ,-1 , 0
  3888.6    .063       0    4493    .035       0  4652.4     .05       0
  4881.6     .05       0  4893.9     .05       0  6069.2    .035       0
  6594.2    .094       0
Bank Sta=4881.6,4893.9
XS Rating Curve= 0 ,0
Exp/Cntr=0.3,0.1

Type RM Length L Ch R = 1 ,13229   ,467,467,467
BEGIN DESCRIPTION:
GUADALUPE TRIBUTARY 4A 20.0
END DESCRIPTION:
XS GIS Cut Line= 3
      2285274.97     13763374.97        2284475.       13762575.
      2283474.96     13762975.01
#Sta/Elev= 30
  3862.4  554.02  3904.8  552.96  3933.1  549.43  4044.1  547.92  4215.9  546.07
  4272.5  545.15  4498.8  544.07  4682.6  540.44  4809.9  539.19  4838.2  537.44
  4908.9  537.51    4936  536.52  5019.8  533.39  5020.3  532.89  5031.7  532.89
  5032.2  533.39  5032.8  534.15  5038.2  533.73    5057  536.34  5062.4  536.12
  5086.6  538.45  5170.1  539.86  5209.1  541.79  5230.7  541.27  5331.6  543.05
  5349.2  543.92  5625.1  547.06  5630.5  546.46  5743.6  547.27  6070.8  548.75
#Mann= 7 ,-1 , 0
  3862.4    .063       0  4044.1    .045       0  4215.9     .05       0
    4936    .045       0  5019.8    .045       0  5032.2    .045       0
  5743.6     .05       0
Bank Sta=5019.8,5032.2
XS Rating Curve= 0 ,0
Exp/Cntr=0.3,0.1

Type RM Length L Ch R = 1 ,12762   ,445,445,445
BEGIN DESCRIPTION:
GUADALUPE TRIBUTARY 4A 19.0
END DESCRIPTION:
XS GIS Cut Line= 3
      2285324.99       13762775.        2284525.       13762125.
      2283525.02     13762824.99
#Sta/Elev= 30
  3973.6  548.52  4207.7  544.47  4308.3  541.05  4378.7  542.63  4407.5  541.64
  4642.4  540.27  4706.3  538.72  4770.2  538.48  4848.5  536.77    4855  537.26
  4869.3  536.33  4933.3   535.5  4947.6  533.98  4970.1  532.95  4970.6  532.45
  4982.6  532.95  5017.9  534.18  5047.5   536.7  5126.4  538.11  5133.8  539.01
  5139.9  538.34  5184.4  539.78  5226.3  539.61  5248.5  540.62  5285.1  540.67
  5306.5  542.04  5413.7     543    5456  544.29  5773.4   547.1    6225  548.12
#Mann= 3 ,-1 , 0
  3973.6    .045       0  4970.1    .045       0  4982.6    .045       0
Bank Sta=4970.1,4982.6
XS Rating Curve= 0 ,0
Exp/Cntr=0.3,0.1

Type RM Length L Ch R = 1 ,12317   ,447,447,447
BEGIN DESCRIPTION:
GUADALUPE TRIBUTARY 4A 18.0
END DESCRIPTION:
XS GIS Cut Line= 3
      2285475.01       13761925.        2284575.       13761725.
      2283474.98     13762725.02
#Sta/Elev= 30
  4073.6  548.39  4473.1  542.51  4786.8  539.77  4976.4  535.68  4998.9  534.62
  5010.5  533.22    5011  532.72  5023.1  533.22  5045.2  534.37  5108.7  535.19
  5130.4  536.41  5255.7  537.46  5264.8  538.45  5292.9  538.41  5314.2  539.39
  5377.7  539.31  5462.8  541.44  5512.2  541.48  5583.1  543.55  5689.2  544.44
  5710.8  545.51  5731.8  545.01  5760.2  545.67  5766.9  545.11  5866.2  545.99
  5887.5  546.77  5908.8  546.32  6206.1  547.29  6354.8  548.43  6482.2   548.2
#Mann= 3 ,-1 , 0
  4073.6    .045       0  5010.5    .045       0  5023.1    .045       0
Bank Sta=5010.5,5023.1
XS Rating Curve= 0 ,0
Exp/Cntr=0.3,0.1

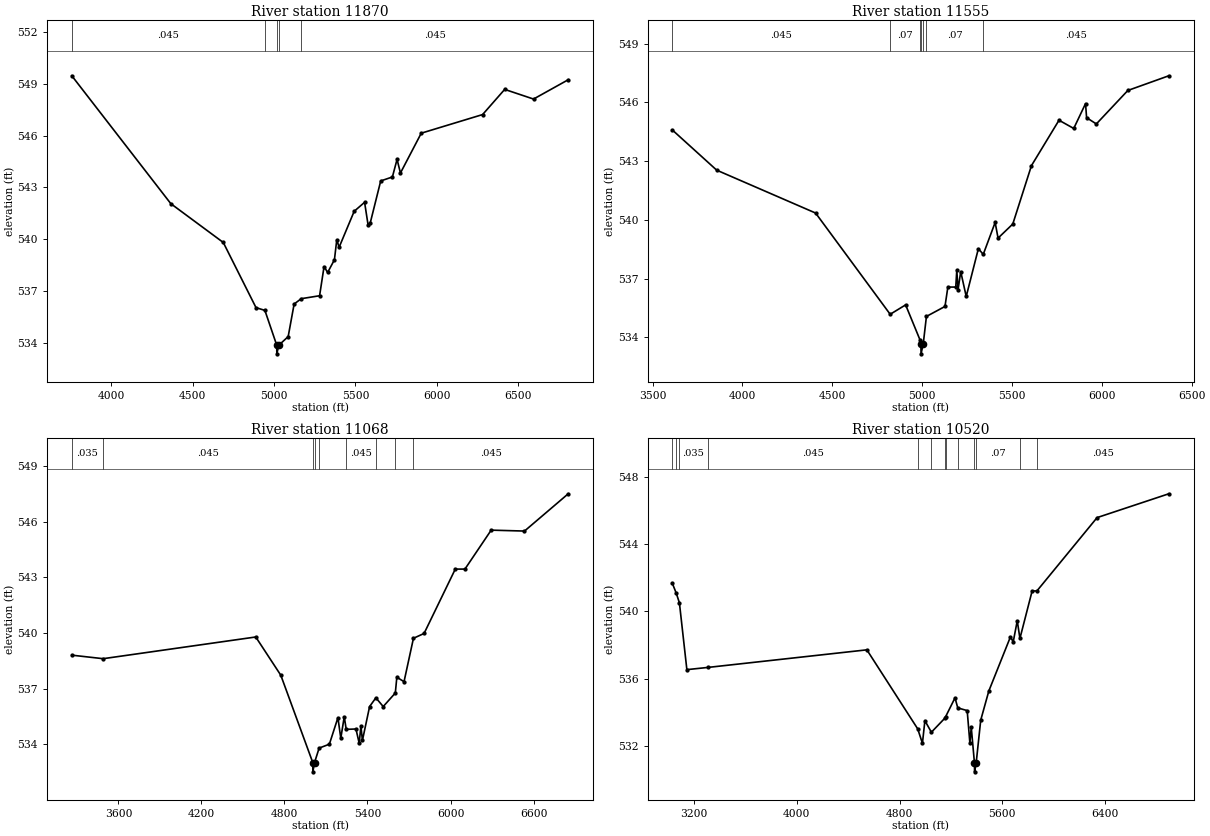
Type RM Length L Ch R = 1 ,11870   ,315,315,315
BEGIN DESCRIPTION:
GUADALUPE TRIBUTARY 4A 17.0
END DESCRIPTION:
XS GIS Cut Line= 3
      2285625.01       13761625.        2284425.       13761325.
      2283275.01     13762724.99
#Sta/Elev= 30
    3758  549.48  4366.2  542.06  4688.3  539.81  4889.3  536.03  4943.8  535.87
  5016.6  533.85  5017.1  533.35  5029.2  533.85  5086.8  534.35  5123.4  536.24
  5167.2  536.55  5279.7  536.72  5307.1  538.41  5329.3  538.07  5370.9  538.81
  5385.3  539.97  5399.6  539.53  5492.2  541.62  5556.1  542.14  5577.3  540.84
  5591.2  540.96  5655.1  543.38  5726.8  543.61  5755.5  544.63  5776.3  543.84
  5904.1  546.15  6280.8  547.23  6416.4  548.69  6593.6  548.13  6806.7  549.25
#Mann= 5 ,-1 , 0
    3758    .045       0  4943.8     .07       0  5016.6     .05       0
  5029.2     .07       0  5167.2    .045       0
Bank Sta=5016.6,5029.2
XS Rating Curve= 0 ,0
Exp/Cntr=0.3,0.1

Type RM Length L Ch R = 1 ,11555   ,487,487,487
BEGIN DESCRIPTION:
A19375
END DESCRIPTION:
XS GIS Cut Line= 4
       2285619.6     13761218.92      2284773.21     13760969.34
      2284208.98     13761077.85      2283590.49     13762228.01
#Sta/Elev= 30
  3609.9  544.59  3856.6  542.54    4407  540.35  4822.1  535.18    4908  535.66
    4989  533.85  4993.3  533.66  4993.8  533.16    5006  533.66  5023.8  535.07
  5127.1  535.58  5143.1  536.57  5187.1  536.57  5192.8  537.43  5199.9  536.44
  5214.7  537.36  5245.3  536.09  5312.9  538.53  5340.1  538.24  5406.3  539.87
  5422.5  539.07  5504.5  539.79  5608.3  542.77  5761.7  545.09  5843.7  544.67
  5909.4  545.94  5915.2  545.22  5969.5   544.9  6144.8  546.61  6372.8  547.36
#Mann= 7 ,-1 , 0
  3609.9    .045       0  4822.1     .07       0    4989    .045       0
  4993.3    .045       0    5006    .045       0  5023.8     .07       0
  5340.1    .045       0
Bank Sta=4993.3,5006
XS Rating Curve= 0 ,0
Exp/Cntr=0.3,0.1

Type RM Length L Ch R = 1 ,11068   ,548,548,548
BEGIN DESCRIPTION:
A19374
END DESCRIPTION:
XS GIS Cut Line= 3
      2286107.83     13760198.95      2284208.98     13760687.22
      2283547.07     13762173.79
#Sta/Elev= 30
  3262.9  538.81  3489.4  538.62  4592.4  539.79  4773.3  537.73  5004.5  533.02
    5005  532.52  5017.2  533.02  5050.4   533.8  5124.4  534.01  5186.3  535.44
    5207  534.33    5232  535.49  5246.2  534.81  5316.7  534.83    5340  534.06
  5352.5     535  5363.2  534.21  5415.2  536.04  5460.5  536.51  5513.6  536.04
  5601.1  536.77    5612  537.62    5664  537.38  5732.1  539.72  5808.9  539.98
  6034.5  543.45  6104.2  543.45  6293.9  545.55  6534.7   545.5  6850.8  547.51
#Mann= 9 ,-1 , 0
  3262.9    .035       0  3489.4    .045       0  5004.5    .045       0
  5017.2    .045       0  5050.4     .07       0  5246.2    .045       0
  5460.5    .035       0  5601.1     .07       0  5732.1    .045       0
Bank Sta=5004.5,5017.2
XS Rating Curve= 0 ,0
Exp/Cntr=0.3,0.1

Type RM Length L Ch R = 1 ,10520   ,426,426,426
BEGIN DESCRIPTION:
GUADALUPE TRIBUTARY 4A 16.0
END DESCRIPTION:
XS GIS Cut Line= 3
      2285925.02     13759424.99        2284125.       13760225.
      2283524.99     13762025.04
#Sta/Elev= 30
  3030.6  541.67  3061.1  541.08  3085.4  540.51  3143.5  536.53  3304.7  536.66
  4545.6  537.71  4941.8     533  4978.5  532.14  4997.7  533.49  5048.3   532.8
    5151  533.62  5158.8  533.72  5232.3  534.85  5253.8  534.25  5327.2  534.09
  5348.2  532.15  5358.8   533.1  5384.1  530.94  5384.6  530.44  5396.8  530.94
  5432.6  533.52  5495.8  535.26  5664.5  538.49  5685.6  538.18  5717.2  539.44
    5738  538.39  5833.1  541.22  5870.3  541.22  6339.1  545.59  6897.8  547.01
#Mann= 13 ,-1 , 0
  3030.6    .094       0  3061.1    .063       0  3085.4    .035       0
  3304.7    .045       0  4941.8     .07       0  5048.3     .12       0
    5151     .07       0  5158.8     .12       0  5253.8     .07       0
  5384.1     .05       0  5396.8     .07       0    5738    .035       0
  5870.3    .045       0
Bank Sta=5384.1,5396.8
XS Rating Curve= 0 ,0
Exp/Cntr=0.3,0.1