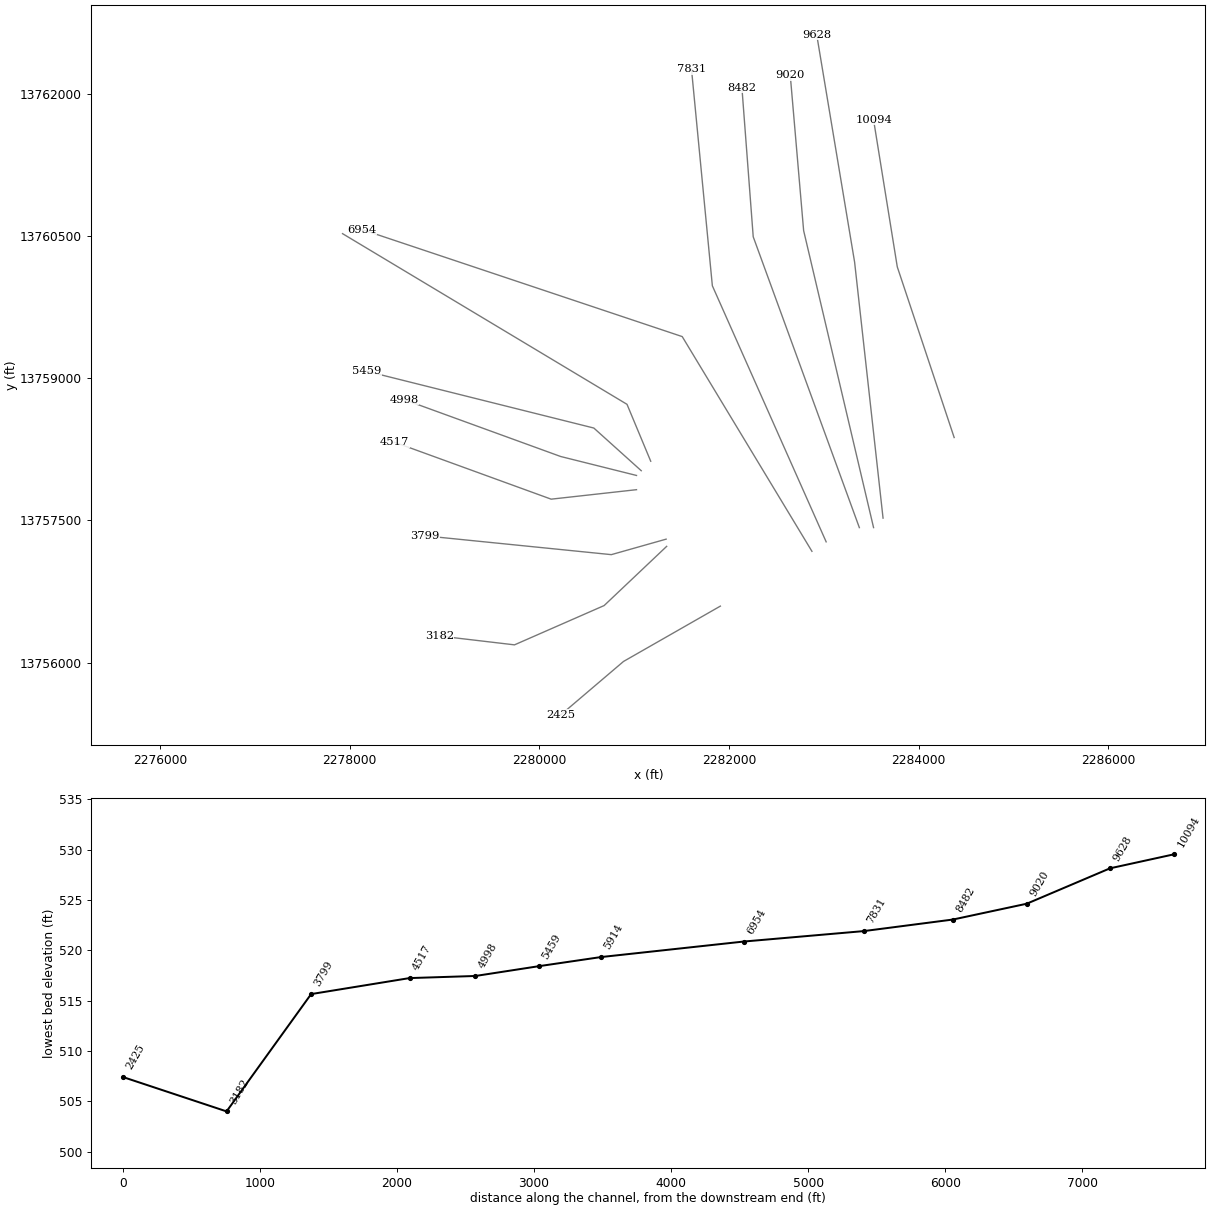
HEC-RAS study GUADALUPE TRIBUTARY 4A.prj: GUADALUPE TRIBUTARY 4A Base Level Engineering

--- GUADALUPE TRIBUTARY 4A.g01 (geometry) --- (continued)

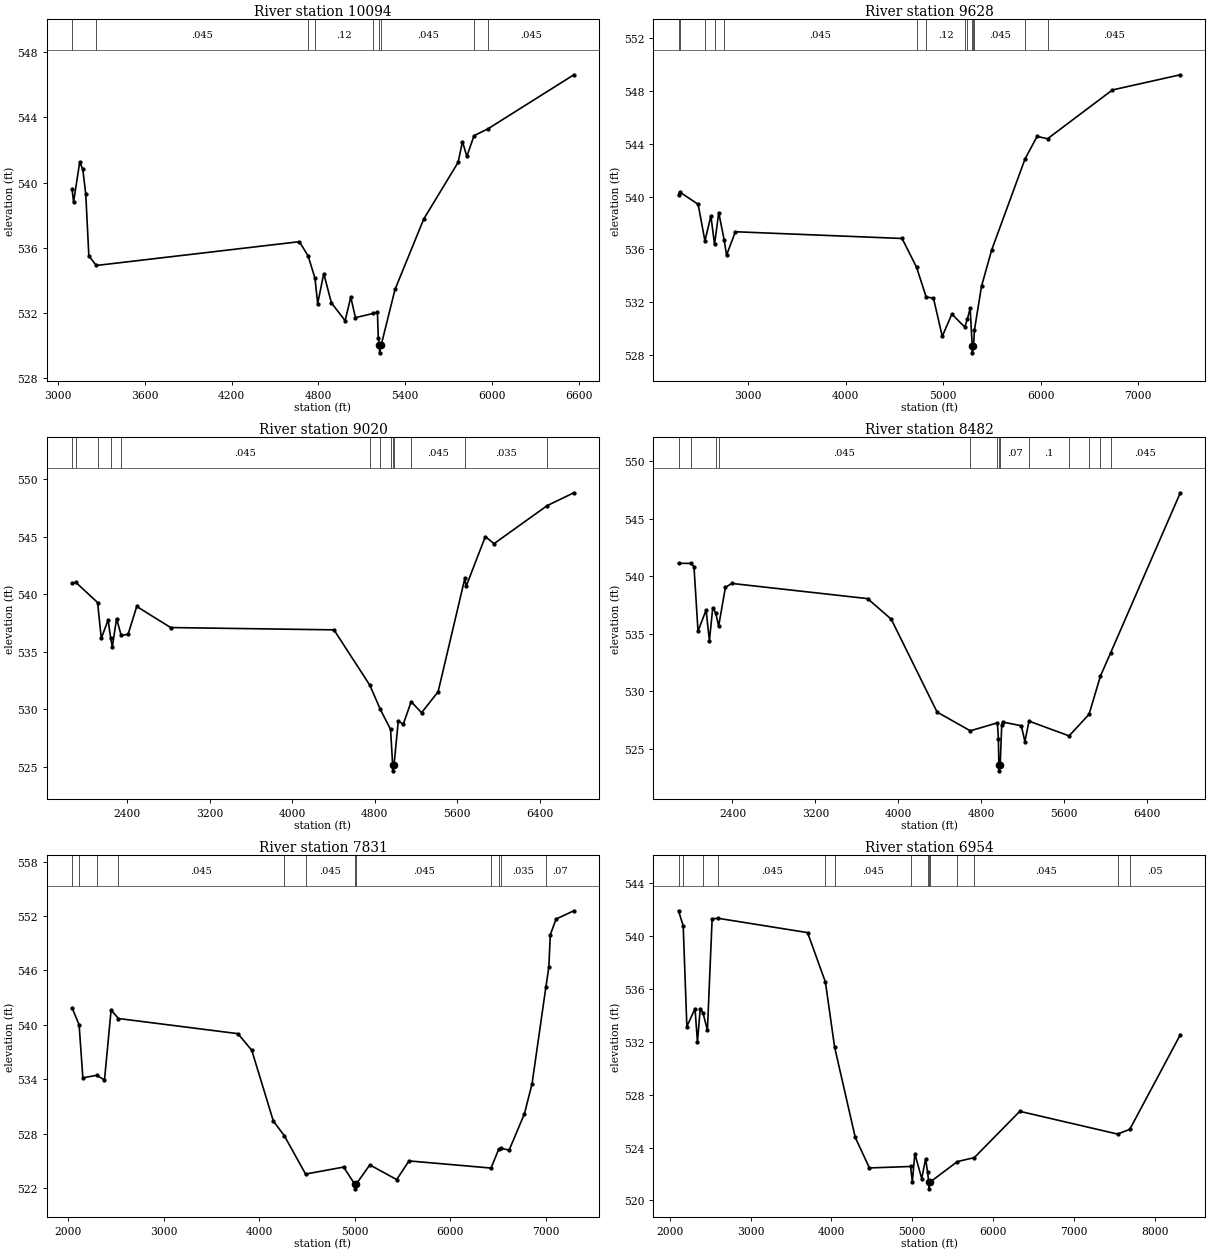
Type RM Length L Ch R = 1 ,10094   ,466,466,466
BEGIN DESCRIPTION:
GUADALUPE TRIBUTARY 4A 15.0
END DESCRIPTION:
XS GIS Cut Line= 3
      2284374.99     13758375.02        2283775.       13760175.
        2283525.     13761725.03
#Sta/Elev= 30
  3098.2  539.59  3108.7  538.81  3150.9  541.24    3172  540.83    3193  539.27
  3214.1   535.5  3265.4  534.91  4668.8  536.37  4729.6  535.49  4776.6  534.13
  4795.3  532.57  4837.4  534.41  4890.1  532.62    4985  531.52  5023.9  532.97
  5056.3  531.71    5181  531.97  5208.3  532.05  5214.3  530.43  5222.2  530.05
  5222.7  529.55  5234.9  530.05  5329.8  533.44  5528.3  537.76  5765.4  541.23
  5795.8  542.51  5826.1   541.6  5875.6  542.87  5974.9  543.31  6565.6  546.61
#Mann= 9 ,-1 , 0
  3098.2    .063       0  3265.4    .045       0  4729.6     .07       0
  4776.6     .12       0    5181    .045       0  5222.2     .05       0
  5234.9    .045       0  5875.6    .035       0  5974.9    .045       0
Bank Sta=5222.2,5234.9
XS Rating Curve= 0 ,0
Exp/Cntr=0.3,0.1

Type RM Length L Ch R = 1 ,9628    ,608,608,608
BEGIN DESCRIPTION:
GUADALUPE TRIBUTARY 4A 14.0
END DESCRIPTION:
XS GIS Cut Line= 3
        2283625.     13757525.02        2283325.       13760225.
        2282925.       13762625.
#Sta/Elev= 30
  2283.4  540.16  2295.8  540.35  2484.6  539.42  2554.3  536.64  2615.4  538.54
    2653  536.38  2695.9  538.79  2751.7  536.72  2776.4  535.57    2867  537.34
  4577.4  536.83  4726.1  534.65  4824.8  532.39  4899.4  532.31  4989.9  529.41
  5088.7   531.1    5221  530.11  5247.4  530.71  5276.3  531.54  5297.7  528.66
  5298.2  528.16  5310.5  528.66  5320.3   529.9  5392.8  533.21  5496.8  535.95
  5838.9  542.85  5963.1  544.57  6070.5  544.39  6736.1  548.09  7433.1  549.24
#Mann= 14 ,-1 , 0
  2283.4    .045       0  2295.8    .035       0  2554.3    .094       0
    2653    .063       0  2751.7    .045       0  4726.1     .07       0
  4824.8     .12       0    5221    .045       0  5247.4     .12       0
  5297.7     .05       0  5310.5     .12       0  5320.3    .045       0
  5838.9    .035       0  6070.5    .045       0
Bank Sta=5297.7,5310.5
XS Rating Curve= 0 ,0
Exp/Cntr=0.3,0.1

Type RM Length L Ch R = 1 ,9020    ,538,538,538
BEGIN DESCRIPTION:
GUADALUPE TRIBUTARY 4A 13.0
END DESCRIPTION:
XS GIS Cut Line= 3
      2283524.99     13757425.05      2282787.54     13760557.02
      2282646.48     13762195.44
#Sta/Elev= 30
  1866.9  540.94  1904.4  541.01  2114.5  539.26  2149.9  536.15  2216.1  537.74
  2241.4  536.15  2257.2  535.41  2298.3  537.87  2341.9  536.43  2409.2  536.49
  2493.5  538.92  2822.3  537.09  4404.4  536.89  4752.2  532.08  4852.6     530
    4953  528.24  4973.3  525.14  4973.8  524.64  4986.2  525.14    5028  528.99
  5075.5  528.68  5152.6  530.65  5253.1  529.69  5413.7  531.51  5672.8  541.37
  5684.7  540.66  5871.1  544.99  5955.7  544.38  6471.7  547.69    6729   548.8
#Mann= 13 ,-1 , 0
  1866.9    .045       0  1904.4    .035       0  2114.5    .094       0
  2241.4    .035       0  2341.9    .045       0  4752.2     .07       0
  4852.6     .12       0    4953     .07       0  4973.3     .05       0
  4986.2     .07       0  5152.6    .045       0  5672.8    .035       0
  6471.7    .045       0
Bank Sta=4973.3,4986.2
XS Rating Curve= 0 ,0
Exp/Cntr=0.3,0.1

Type RM Length L Ch R = 1 ,8482    ,651,651,651
BEGIN DESCRIPTION:
GUADALUPE TRIBUTARY 4A 12.0
END DESCRIPTION:
XS GIS Cut Line= 3
      2283374.99     13757425.02      2282255.85     13760491.91
      2282136.49     13762065.29
#Sta/Elev= 30
  1879.8  541.11  1998.5   541.1  2028.8  540.83  2067.7  535.22  2145.9  537.04
  2177.8  534.37  2209.8  537.23    2238  536.82    2267  535.65  2332.1  539.02
  2393.2  539.36  3704.2  538.04  3932.7  536.25    4375  528.18  4695.1  526.55
  4957.1  527.24  4966.8  525.85    4971  523.57  4971.5  523.07  4983.9  523.57
  4998.8  527.05  5009.4  527.31  5187.7  526.99  5222.3  525.62  5261.9  527.39
  5648.8  526.11  5841.4  527.98  5951.4  531.31  6049.9  533.33  6722.4  547.24
#Mann= 13 ,-1 , 0
  1879.8    .035       0  1998.5    .094       0    2238    .035       0
    2267    .045       0  4695.1     .12       0  4957.1     .07       0
    4971     .05       0  4983.9     .07       0  5261.9      .1       0
  5648.8     .12       0  5841.4    .045       0  5951.4    .035       0
  6049.9    .045       0
Bank Sta=4971,4983.9
XS Rating Curve= 0 ,0
Exp/Cntr=0.3,0.1

Type RM Length L Ch R = 1 ,7831    ,877,877,877
BEGIN DESCRIPTION:
GUADALUPE TRIBUTARY 4A 11.0
END DESCRIPTION:
XS GIS Cut Line= 3
      2283025.02     13757274.96        2281825.       13759975.
      2281604.83     13762260.32
#Sta/Elev= 30
  2040.5  541.89  2114.2     540  2153.4  534.16  2297.4  534.44  2379.8  533.93
  2448.9  541.63    2526   540.7  3775.7  539.03  3920.7   537.2  4146.4   529.4
  4261.9  527.77  4483.9  523.55  4882.3  524.32  4998.8  522.42  4999.3  521.92
  5011.7  522.42  5156.3  524.56  5437.2  522.94  5565.8     525  6424.8  524.21
  6505.3  526.31  6525.5  526.37  6614.6  526.21  6773.4  530.18  6853.8  533.51
  6998.4  544.17  7029.1  546.35  7044.6  549.93  7104.9  551.67  7291.1  552.58
#Mann= 12 ,-1 , 0
  2040.5    .035       0  2114.2    .094       0  2297.4    .035       0
    2526    .045       0  4261.9    .035       0  4483.9    .045       0
  4998.8    .045       0  5011.7    .045       0  6424.8    .035       0
  6505.3     .07       0  6525.5    .035       0  6998.4     .07       0
Bank Sta=4998.8,5011.7
XS Rating Curve= 0 ,0
Exp/Cntr=0.3,0.1

Type RM Length L Ch R = 1 ,6954    ,1040,1040,1040
BEGIN DESCRIPTION:
GUADALUPE TRIBUTARY 4A 10.0
END DESCRIPTION:
XS GIS Cut Line= 3
      2282875.02     13757174.96      2281507.15     13759439.39
      2278132.55     13760567.88
#Sta/Elev= 30
  2109.7   541.9  2167.3  540.76  2212.6  533.15  2313.5   534.5  2343.4  531.99
  2378.4   534.5  2412.4  534.17  2466.8  532.87    2525  541.29  2600.6  541.33
  3704.9  540.25  3925.8  536.51  4038.8  531.61  4294.4  524.77  4469.7  522.46
  4978.3  522.57    5000  521.41  5031.6  523.53    5116  521.66  5165.2  523.15
  5188.5  522.13  5204.4  521.38  5204.9  520.88  5217.3  521.38  5556.7  522.94
  5766.5  523.24  6328.5  526.74    7538  525.02  7688.7  525.38  8313.5  532.53
#Mann= 14 ,-1 , 0
  2109.7    .035       0  2167.3    .094       0  2412.4    .035       0
  2600.6    .045       0  3925.8     .07       0  4038.8    .045       0
  4978.3    .035       0  5188.5    .045       0  5204.4    .035       0
  5217.3    .045       0  5556.7    .035       0  5766.5    .045       0
    7538    .035       0  7688.7     .05       0
Bank Sta=5204.4,5217.3
XS Rating Curve= 0 ,0
Exp/Cntr=0.3,0.1

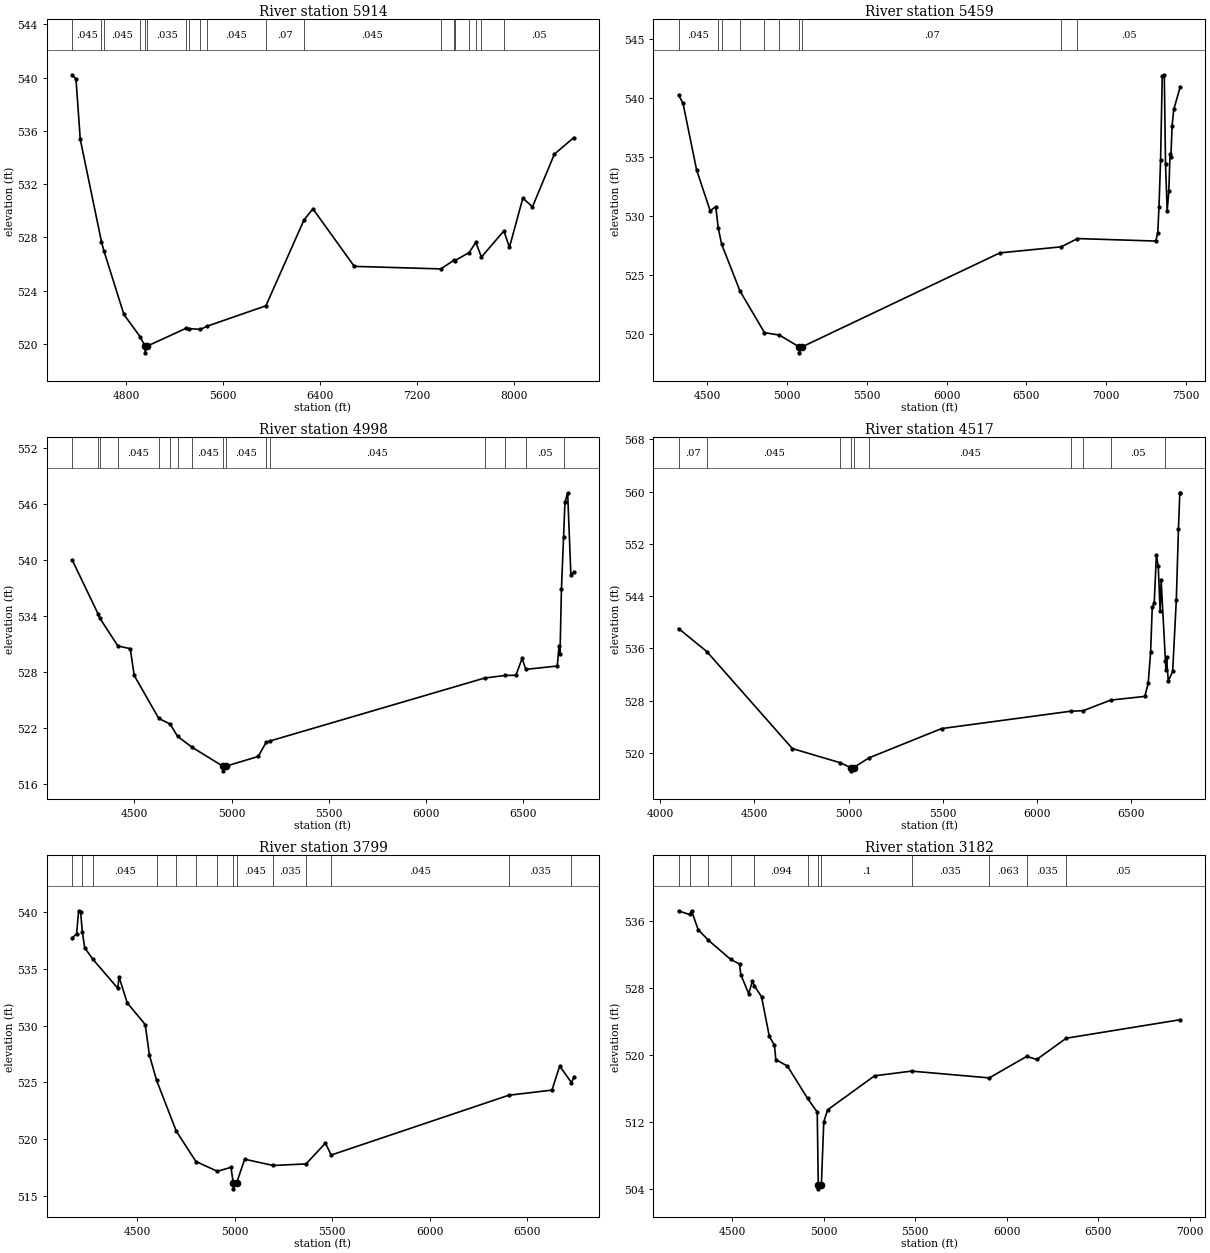
Type RM Length L Ch R = 1 ,5914    ,455,455,455
BEGIN DESCRIPTION:
GUADALUPE TRIBUTARY 4A 9.0
END DESCRIPTION:
XS GIS Cut Line= 3
      2281175.01     13758124.97        2280925.       13758725.
      2277925.01       13760525.
#Sta/Elev= 30
  4350.2  540.21  4382.7  539.89  4417.9  535.37    4593  527.69  4612.6  527.02
  4778.7  522.22  4912.1  520.56  4953.6  519.84  4954.1  519.34    4970  519.84
  5294.4  521.19  5317.7  521.16  5411.3   521.1  5466.4  521.34  5952.6  522.87
    6268  529.32  6341.4  530.15  6683.4  525.83  7398.9  525.64  7505.6  526.28
  7515.8  526.27  7632.8  526.86  7687.9  527.63  7734.7  526.53  7920.2  528.49
  7966.2  527.26    8077  530.95  8156.7   530.3  8337.5  534.25  8498.8   535.5
#Mann= 19 ,-1 , 0
  4350.2    .045       0    4593    .035       0  4612.6    .045       0
  4912.1    .035       0  4953.6    .035       0    4970    .035       0
  5294.4     .07       0  5317.7    .045       0  5411.3     .07       0
  5466.4    .045       0  5952.6     .07       0    6268    .045       0
  7398.9    .035       0  7505.6    .094       0  7515.8     .05       0
  7632.8     .07       0  7687.9     .05       0  7734.7     .07       0
  7920.2     .05       0
Bank Sta=4953.6,4970
XS Rating Curve= 0 ,0
Exp/Cntr=0.3,0.1

Type RM Length L Ch R = 1 ,5459    ,461,461,461
BEGIN DESCRIPTION:
GUADALUPE TRIBUTARY 4A 8.0
END DESCRIPTION:
XS GIS Cut Line= 3
      2281074.98     13758025.02        2280575.       13758475.
      2278175.01       13759075.
#Sta/Elev= 30
  4318.4  540.25  4346.4  539.55  4431.6  533.91  4516.8  530.45  4551.9   530.8
  4567.2     529  4588.7  527.62  4703.4  523.67  4857.3  520.14  4950.7  519.93
  5075.6  518.93  5076.1  518.43  5092.1  518.93  6333.6  526.89  6717.9   527.4
  6820.1   528.1  7310.3  527.89  7323.2  528.54  7330.9  530.73  7341.2  534.77
  7351.5  541.85  7364.4  541.96  7372.1   534.4  7382.5  530.47  7392.8  532.13
  7400.5  535.27  7405.6  535.01  7413.4  537.65  7423.7  539.03  7464.9  540.96
#Mann= 10 ,-1 , 0
  4318.4    .045       0  4567.2     .07       0  4588.7    .045       0
  4703.4     .07       0  4857.3    .045       0  4950.7     .07       0
  5075.6     .05       0  5092.1     .07       0  6717.9    .063       0
  6820.1     .05       0
Bank Sta=5075.6,5092.1
XS Rating Curve= 0 ,0
Exp/Cntr=0.3,0.1

Type RM Length L Ch R = 1 ,4998    ,481,481,481
BEGIN DESCRIPTION:
GUADALUPE TRIBUTARY 4A 7.0
END DESCRIPTION:
XS GIS Cut Line= 3
      2281025.03     13757974.99        2280225.       13758175.
      2278574.96     13758775.01
#Sta/Elev= 30
  4179.7  540.08  4313.5  534.27  4321.3  533.85  4415.5  530.84  4478.7  530.55
  4499.3  527.68  4625.3  523.08  4684.2  522.47  4722.3  521.15    4798  519.97
  4954.8  517.96  4955.3  517.46  4971.4  517.96  5136.7     519  5177.8  520.51
  5197.4  520.66    6301   527.4    6407  527.68  6462.1   527.7    6494   529.5
  6512.9  528.33  6674.9  528.69  6683.6  530.81  6688.9  529.98  6696.2   536.9
  6707.2  542.51  6714.2  546.21  6728.1  547.25  6744.8  538.44  6760.1  538.78
#Mann= 16 ,-1 , 0
  4179.7     .07       0  4313.5    .045       0  4321.3     .07       0
  4415.5    .045       0  4625.3    .035       0  4684.2     .07       0
  4722.3    .035       0    4798    .045       0  4954.8    .045       0
  4971.4    .045       0  5177.8    .035       0  5197.4    .045       0
    6301    .035       0    6407    .063       0  6512.9     .05       0
  6707.2      .1       0
Bank Sta=4954.8,4971.4
XS Rating Curve= 0 ,0
Exp/Cntr=0.3,0.1

Type RM Length L Ch R = 1 ,4517    ,718,718,718
BEGIN DESCRIPTION:
GUADALUPE TRIBUTARY 4A 6.0
END DESCRIPTION:
XS GIS Cut Line= 3
      2281025.03       13757825.        2280125.       13757725.
      2278474.98     13758325.01
#Sta/Elev= 30
  4098.5  539.04  4248.1  535.52  4702.2  520.66    4957  518.48  5011.1  517.75
  5011.6  517.25  5027.7  517.75    5108  519.23  5493.5  523.72  6178.8  526.38
  6244.9  526.46  6390.7  528.08  6571.6  528.65  6589.5  530.67  6602.2  535.42
  6610.8  542.26  6621.4  542.98  6632.8  550.28  6642.7  548.57  6652.7   541.7
    6658  546.41    6681  534.03  6683.3   532.7  6686.6  534.63  6695.9  530.99
  6719.2  532.49  6738.5  543.43  6749.8  554.22  6757.1  559.82  6759.8  559.82
#Mann= 10 ,-1 , 0
  4098.5     .07       0  4248.1    .045       0    4957    .035       0
  5011.1    .035       0  5027.7    .035       0    5108    .045       0
  6178.8    .063       0  6244.9    .035       0  6390.7     .05       0
    6681      .1       0
Bank Sta=5011.1,5027.7
XS Rating Curve= 0 ,0
Exp/Cntr=0.3,0.1

Type RM Length L Ch R = 1 ,3799    ,617,617,617
BEGIN DESCRIPTION:
A19373
END DESCRIPTION:
XS GIS Cut Line= 3
      2281337.41     13757303.35      2280759.66     13757139.94
      2278792.86     13757338.38
#Sta/Elev= 30
  4164.2  537.67  4187.5  538.07  4197.9  540.08  4208.2  540.01  4216.5  538.26
  4229.1  536.83  4270.7  535.83  4398.8  533.28  4405.7  534.26  4447.3     532
  4539.8  530.09  4561.6  527.39  4598.1   525.2  4699.6  520.72  4800.3  518.06
  4910.6   517.2  4980.4  517.55  4992.2  516.16  4992.7  515.66  5008.8  516.16
  5050.7  518.26  5197.4  517.71  5365.9  517.85  5465.2  519.67  5495.2  518.63
    6407  523.88  6628.7  524.33  6668.9  526.44    6729  524.99  6741.4  525.45
#Mann= 14 ,-1 , 0
  4164.2    .045       0  4216.5    .035       0  4270.7    .045       0
  4598.1     .07       0  4699.6    .045       0  4800.3     .07       0
  4910.6    .045       0  4992.2    .045       0  5008.8    .045       0
  5197.4    .035       0  5365.9     .07       0  5495.2    .045       0
    6407    .035       0    6729     .05       0
Bank Sta=4992.2,5008.8
XS Rating Curve= 0 ,0
Exp/Cntr=0.3,0.1

Type RM Length L Ch R = 1 ,3182    ,757,757,757
BEGIN DESCRIPTION:
A19372
END DESCRIPTION:
XS GIS Cut Line= 4
      2281343.25     13757227.46      2280683.79     13756603.02
      2279738.33     13756188.65      2278944.58     13756282.03
#Sta/Elev= 30
  4207.4  537.19  4267.3  536.77  4278.6  537.21  4314.2  534.97  4370.5  533.69
  4491.2  531.42  4540.3  530.85  4547.6  529.59  4590.1  527.31  4611.1   528.8
  4621.2  528.25  4660.5  526.95  4702.9  522.23  4731.2  521.13  4738.5  519.44
    4802  518.66  4912.2  514.79  4964.7  513.17  4970.3   504.5  4970.8     504
  4987.3   504.5  5000.3  511.98  5021.3  513.44    5278   517.5  5479.4  518.06
  5903.9  517.25  6108.6  519.82  6162.9  519.45  6324.4  521.99  6947.1   524.2
#Mann= 12 ,-1 , 0
  4207.4    .045       0  4267.3    .035       0  4370.5    .045       0
  4491.2    .035       0  4621.2    .094       0  4912.2      .1       0
  4970.3     .05       0  4987.3      .1       0  5479.4    .035       0
  5903.9    .063       0  6108.6    .035       0  6324.4     .05       0
Bank Sta=4970.3,4987.3
XS Rating Curve= 0 ,0
Exp/Cntr=0.3,0.1

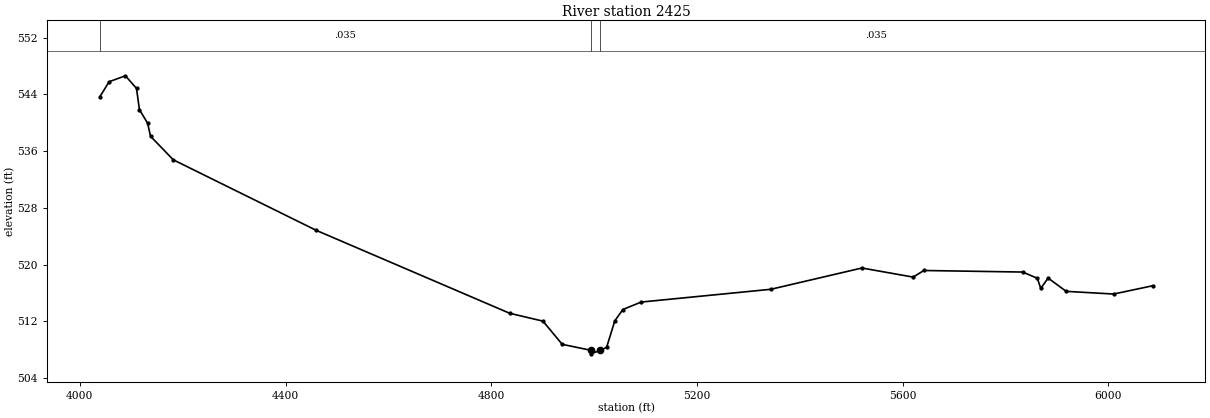
Type RM Length L Ch R = 1 ,2425    ,0,0,0
BEGIN DESCRIPTION:
A19370
END DESCRIPTION:
XS GIS Cut Line= 3
      2281909.38     13756597.18      2280888.05     13756013.56
      2280224.25     13755448.75
#Sta/Elev= 30
  4038.5  543.61  4056.9  545.78  4088.6  546.62  4110.2  544.84  4115.9  541.84
  4131.8  539.94  4137.5  538.09  4181.8  534.77    4460  524.82  4835.8  513.14
  4900.6  512.03    4938  508.76  4993.8  507.92  4994.3  507.42  5011.8  507.92
  5024.4  508.34  5040.2  512.06    5056  513.67  5091.6  514.72  5343.7  516.52
  5520.8  519.52  5620.4  518.24  5641.3  519.17  5833.5  518.95    5862  518.07
  5868.6  516.65  5882.9   518.1    5918  516.23  6010.3  515.85  6086.4  517.02
#Mann= 3 ,-1 , 0
  4038.5    .035       0  4993.8    .035       0  5011.8    .035       0
Bank Sta=4993.8,5011.8
XS Rating Curve= 0 ,0
Exp/Cntr=0.3,0.1

Chan Stop Cuts=-1
Use User Specified Reach Order=0
Composite Channel Slope=5