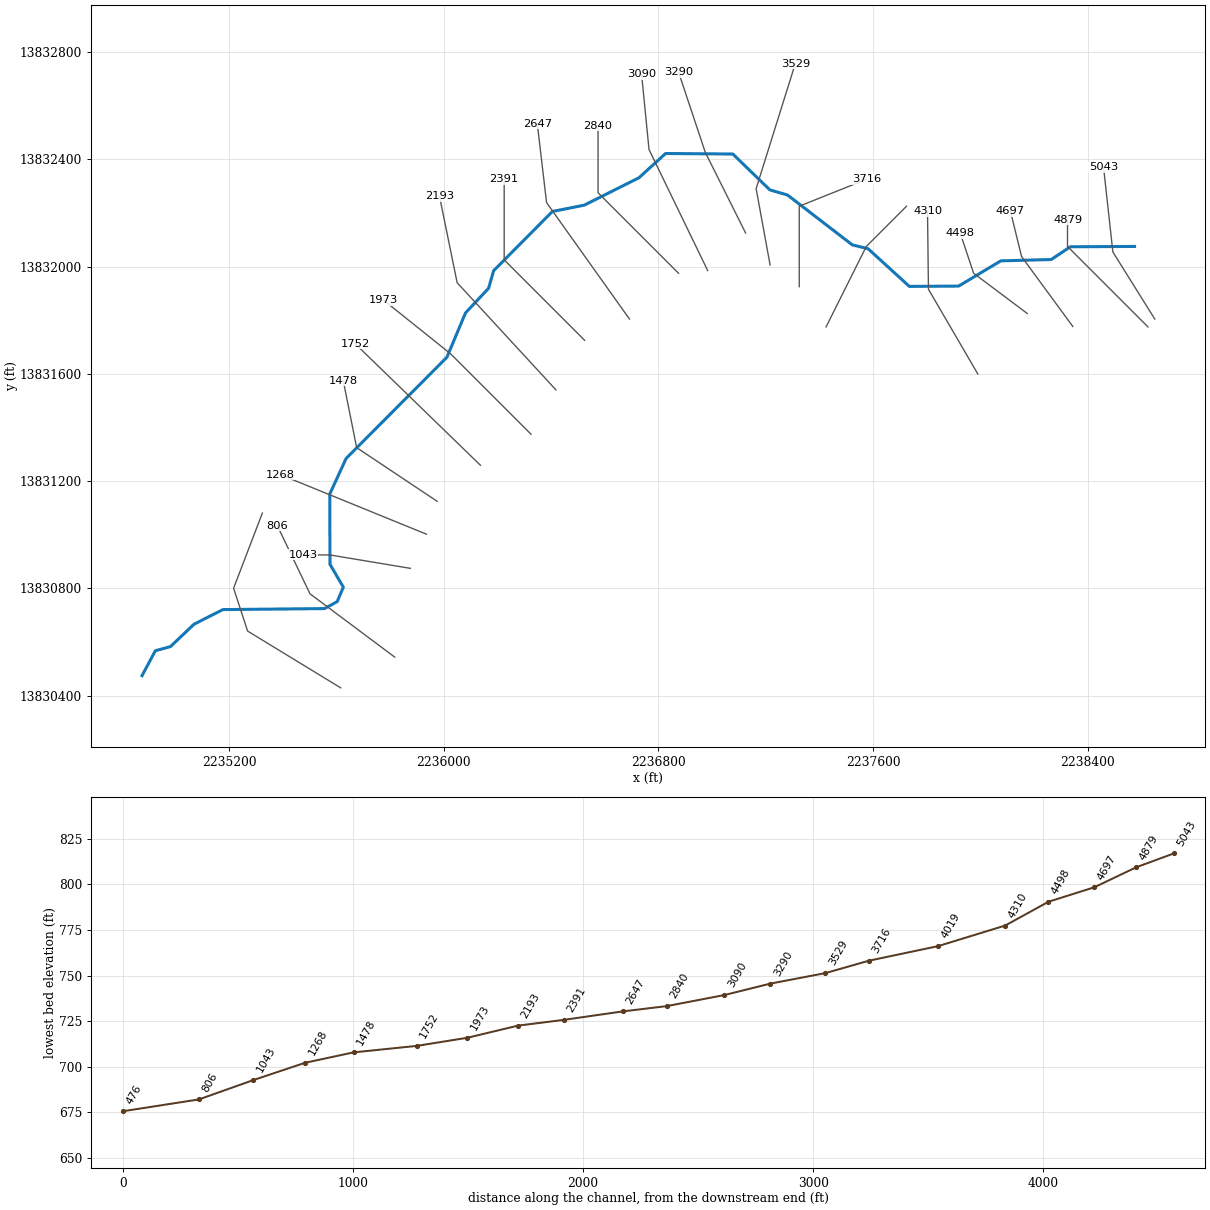
--- Guadalupe Tributary 11.prj (project) ---

Proj Title=Guadalupe Tributary 11 Base Level Engineering
Current Plan=p01
Default Exp/Contr=0.3,0.1
English Units
Geom File=g01
Flow File=f01
Plan File=p01
Y Axis Title=Elevation
X Axis Title(PF)=Main Channel Distance
X Axis Title(XS)=Station
BEGIN DESCRIPTION:
Guadalupe Tributary 11
END DESCRIPTION:
DSS Export Rating Curves= 0
DSS Export Rating Curve Sorted= 0
DSS Export Volume Flow Curves= 0
DXF OffsetX= 0
DXF OffsetY= 0
DXF ScaleX= 1
DXF ScaleY= 10

--- Guadalupe Tributary 11.p01 (plan) ---

Plan Title=Multiple Run
Short Identifier=Multiple
Geom File=g01
Flow File=f01
Subcritical Flow
K Sum by GR= 0
Std Step Tol= 0.01
Critical Tol= 0.01
Num of Std Step Trials= 20
Max Error Tol= 0.3
Flow Tol Ratio= 0.001
Split Flow NTrial= 30
Split Flow Tol= 0.02
Split Flow Ratio= 0.02
Log Output Level= 0
Friction Slope Method= 1
Unsteady Friction Slope Method= 2
Unsteady Bridges Friction Slope Method= 1
Parabolic Critical Depth
Global Vel Dist=  1 , 1 , 1
Global Log Level= 0
CheckData=True
Encroach Param= -1, 0, 0, 0
BEGIN DESCRIPTION:
Multiple Run
END DESCRIPTION:

--- Guadalupe Tributary 11.f01 (steady flow) ---

Flow Title=Multiple
Number of Profiles=7
Profile Names=10-year,25-year,50-year,1pct_min,100-year,1pct_plu,500-year
River Rch & RM= Guadalupe Tribut,Reach-1,5043
     496     802    1081     709    1415    2824    2392
Boundary for River Rch & Prof#=Guadalupe Tribut,Reach-1,1
Up Type=0
Dn Type=3
Dn Slope=0.005
Boundary for River Rch & Prof#=Guadalupe Tribut,Reach-1,2
Up Type=0
Dn Type=3
Dn Slope=0.005
Boundary for River Rch & Prof#=Guadalupe Tribut,Reach-1,3
Up Type=0
Dn Type=3
Dn Slope=0.005
Boundary for River Rch & Prof#=Guadalupe Tribut,Reach-1,4
Up Type=0
Dn Type=3
Dn Slope=0.005
Boundary for River Rch & Prof#=Guadalupe Tribut,Reach-1,5
Up Type=0
Dn Type=3
Dn Slope=0.005
Boundary for River Rch & Prof#=Guadalupe Tribut,Reach-1,6
Up Type=0
Dn Type=3
Dn Slope=0.005
Boundary for River Rch & Prof#=Guadalupe Tribut,Reach-1,7
Up Type=0
Dn Type=3
Dn Slope=0.005

--- Guadalupe Tributary 11.g01 (geometry) ---

Geom Title=Existing Conditions
Program Version=4.10

River Reach=Guadalupe Tribut,Reach-1
Reach XY= 30
        2238575.       13832075.       2238335.5     13832073.78
      2238264.49     13832026.22      2238076.55     13832021.25
      2237919.07     13831927.24      2237735.43     13831926.05
      2237581.39     13832066.61      2237522.72     13832080.87
      2237281.04     13832266.82      2237215.32     13832285.78
      2237077.45     13832419.54      2236826.47     13832421.45
      2236727.29     13832330.85      2236523.41     13832228.83
      2236404.84     13832205.37      2236185.78     13831984.68
      2236166.82     13831918.96      2236080.85     13831827.29
      2236011.38     13831661.79      2235635.76     13831284.68
      2235574.89     13831152.32      2235575.54     13830890.21
      2235625.39     13830804.71       2235602.5     13830751.03
      2235555.15     13830724.91      2235176.55     13830721.25
      2235068.95     13830666.84      2234980.93     13830583.24
      2234924.53     13830567.74        2234875.       13830475.

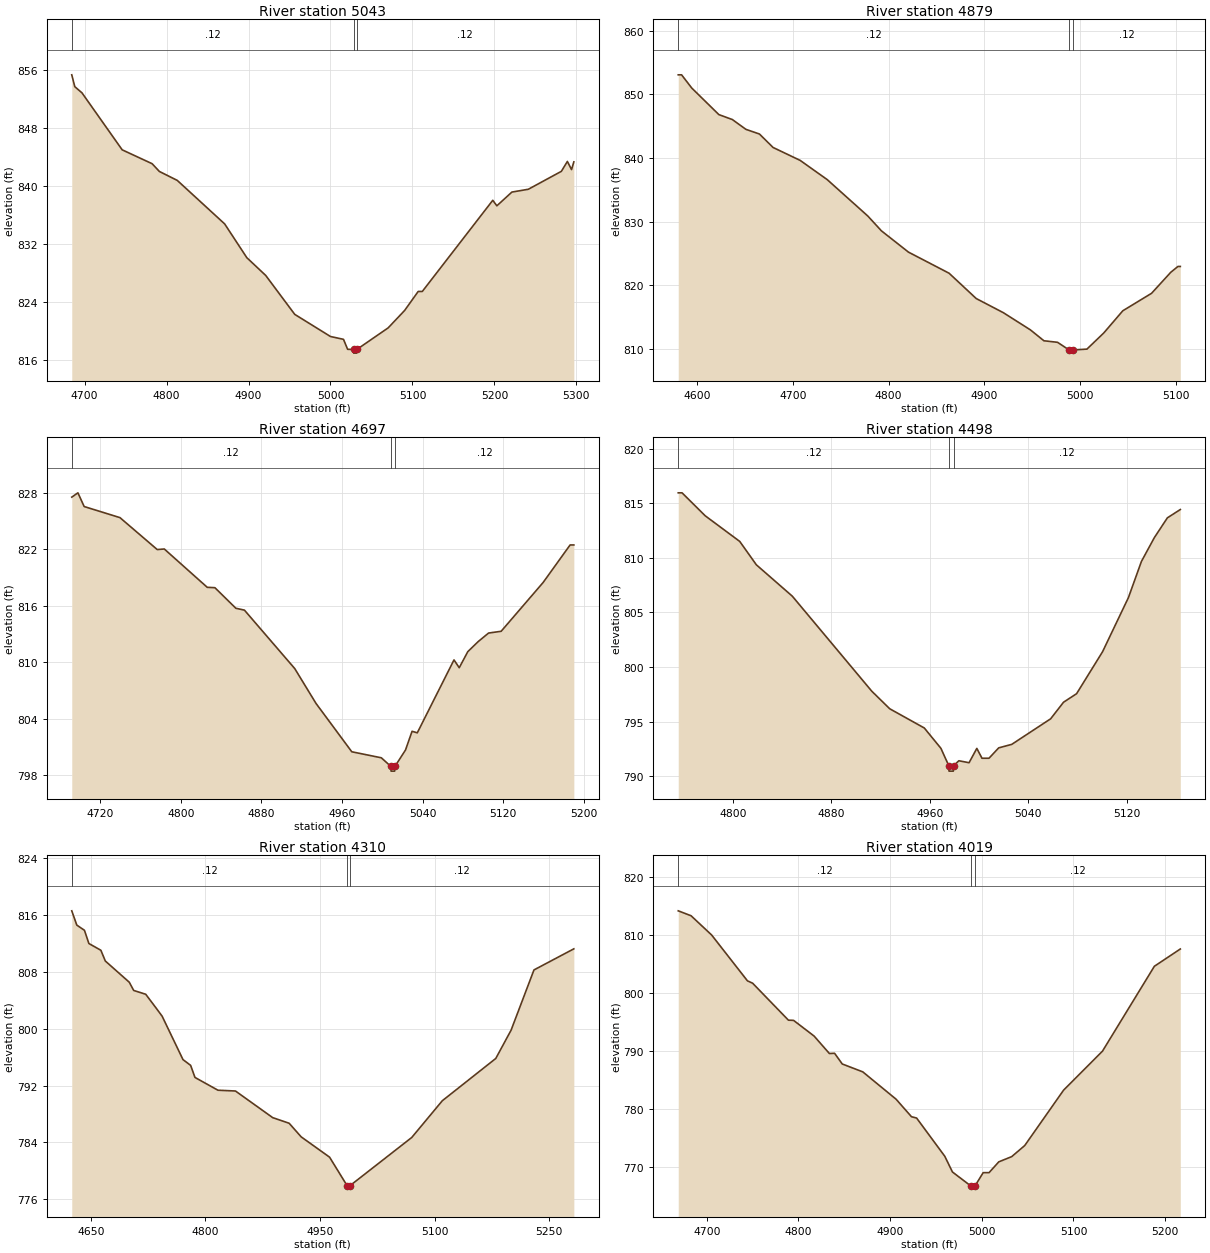
Type RM Length L Ch R = 1 ,5043    ,164,164,164
BEGIN DESCRIPTION:
A19113
END DESCRIPTION:
XS GIS Cut Line= 3
      2238650.37     13831804.37       2238494.1     13832054.42
       2238459.4     13832370.15
#Sta/Elev= 30
  4684.4  855.33  4688.1   853.7  4696.9  852.84  4745.9     845  4782.4  843.09
  4791.3  842.02  4813.1  840.79  4870.9   834.8    4898  830.14    4921   827.7
  4956.4  822.34    5000  819.29  5015.9   818.9  5020.9  817.53  5028.1   817.5
  5028.4     817  5031.9     817  5032.1   817.5  5070.4  820.48  5090.5  822.88
    5107  825.49    5112  825.49    5198  838.05    5203  837.29  5221.3  839.18
  5241.4  839.57  5281.7  842.04    5289   843.4  5294.1  842.28  5296.9  843.34
#Mann= 3 ,-1 , 0
  4684.4     .12       0  5028.1     .05       0  5032.1     .12       0
Bank Sta=5028.1,5032.1
XS Rating Curve= 0 ,0
Exp/Cntr=0.3,0.1

Type RM Length L Ch R = 1 ,4879    ,182,182,182
BEGIN DESCRIPTION:
Guadalupe Tributary 11 11.0
END DESCRIPTION:
XS GIS Cut Line= 3
      2238624.98     13831775.02        2238325.       13832075.
        2238325.     13832174.96
#Sta/Elev= 30
  4580.3  853.05  4583.8  853.05  4594.4  850.98  4622.7  846.81  4636.8  846.03
    4651  844.49  4665.1  843.76  4679.3  841.65  4707.6  839.62  4735.8  836.61
  4778.3  830.88  4792.4  828.57  4820.7  825.22  4863.1  821.91  4891.4  817.94
  4919.7  815.72    4948  813.02  4962.1  811.31  4976.3  811.07  4988.4  809.87
  4988.6  809.37  4992.1  809.37  4992.4  809.87    5007     810  5024.5  812.52
  5044.5  816.02  5074.5  818.76  5094.5  822.05    5102  822.97  5104.5  822.97
#Mann= 3 ,-1 , 0
  4580.3     .12       0  4988.4     .05       0  4992.4     .12       0
Bank Sta=4988.4,4992.4
XS Rating Curve= 0 ,0
Exp/Cntr=0.3,0.1

Type RM Length L Ch R = 1 ,4697    ,199,199,199
BEGIN DESCRIPTION:
A19112
END DESCRIPTION:
XS GIS Cut Line= 3
      2238344.79     13831776.64      2238153.82     13832037.06
      2238112.15      13832207.2
#Sta/Elev= 30
  4691.9  827.57    4698  828.03  4704.2  826.57  4739.7  825.39  4776.7  821.99
  4783.7  822.05  4826.3  817.97  4833.9  817.93  4854.7  815.74  4863.2  815.54
  4913.1  809.32  4934.2  805.61  4969.7  800.46    4999  799.82  5008.5   798.9
  5008.7   798.4  5012.2   798.4  5012.5   798.9    5023  800.65  5029.5  802.64
  5034.7  802.48  5071.1  810.24  5076.3  809.41  5084.8  811.12  5095.1  812.19
  5105.4   813.1  5117.9  813.29  5159.5  818.48  5186.3  822.48    5190  822.48
#Mann= 3 ,-1 , 0
  4691.9     .12       0  5008.5     .05       0  5012.5     .12       0
Bank Sta=5008.5,5012.5
XS Rating Curve= 0 ,0
Exp/Cntr=0.3,0.1

Type RM Length L Ch R = 1 ,4498    ,188,188,188
BEGIN DESCRIPTION:
Guadalupe Tributary 11 10.0
END DESCRIPTION:
XS GIS Cut Line= 3
      2238174.99     13831825.01        2237975.       13831975.
        2237925.       13832125.
#Sta/Elev= 30
  4755.5  815.95  4758.6  815.95  4777.4  813.85  4805.5   811.5    4819  809.36
  4848.2  806.49  4912.8  797.79  4927.4  796.18  4955.5  794.42    4969  792.56
  4975.4  790.97  4975.6  790.47  4979.1  790.47  4979.4  790.97  4983.6  791.42
  4991.9  791.24  4998.2  792.55  5002.4  791.65  5008.1  791.65    5016   792.6
  5026.6  792.92  5058.2  795.26  5068.7  796.78  5079.3  797.56  5100.4   801.4
  5121.4  806.35    5132  809.67  5142.5  811.85  5153.1  813.66  5163.6  814.42
#Mann= 3 ,-1 , 0
  4755.5     .12       0  4975.4     .05       0  4979.4     .12       0
Bank Sta=4975.4,4979.4
XS Rating Curve= 0 ,0
Exp/Cntr=0.3,0.1

Type RM Length L Ch R = 1 ,4310    ,291,291,291
BEGIN DESCRIPTION:
A19111
END DESCRIPTION:
XS GIS Cut Line= 3
      2237990.61     13831599.58       2237806.6     13831915.53
      2237803.13     13832207.18
#Sta/Elev= 30
  4625.1  816.59  4631.7  814.58  4641.7  813.85  4647.5  811.99  4663.2  811.04
    4669  809.53  4700.4  806.54  4706.2  805.38  4721.9  804.85  4735.5  802.91
  4743.4  801.76  4770.7  795.65  4780.7  794.84  4786.4  793.14  4816.5  791.34
  4839.4  791.23  4888.2  787.48  4909.7  786.69  4925.4  784.78  4962.6  781.92
  4985.5  777.92  4985.8  777.42  4989.3  777.42  4989.5  777.92  5070.2  784.69
  5110.2  789.86  5180.2  795.81  5200.2  799.78  5230.2  808.27  5282.4  811.24
#Mann= 3 ,-1 , 0
  4625.1     .12       0  4985.5     .05       0  4989.5     .12       0
Bank Sta=4985.5,4989.5
XS Rating Curve= 0 ,0
Exp/Cntr=0.3,0.1

Type RM Length L Ch R = 1 ,4019    ,303,303,303
BEGIN DESCRIPTION:
Guadalupe Tributary 11 9.0
END DESCRIPTION:
XS GIS Cut Line= 3
      2237424.99     13831774.98        2237575.       13832075.
      2237725.02     13832225.02
#Sta/Elev= 30
  4668.9  814.11  4682.9  813.26  4705.3  809.95  4744.4  802.04    4750  801.64
  4789.1  795.26  4794.7  795.23  4817.1  792.52  4833.8  789.51  4839.4  789.56
  4847.8  787.71  4870.2  786.35  4906.5  781.64  4923.3  778.62  4928.9  778.39
  4959.6  771.81    4968  769.09  4988.4  766.64  4988.6  766.14  4992.1  766.14
  4992.4  766.64  5001.5  768.98  5007.9  768.98  5018.5  770.84  5032.6  771.74
  5046.8  773.65  5089.2   783.2  5131.6  789.92  5188.2  804.55  5216.5  807.53
#Mann= 3 ,-1 , 0
  4668.9     .12       0  4988.4     .05       0  4992.4     .12       0
Bank Sta=4988.4,4992.4
XS Rating Curve= 0 ,0
Exp/Cntr=0.3,0.1

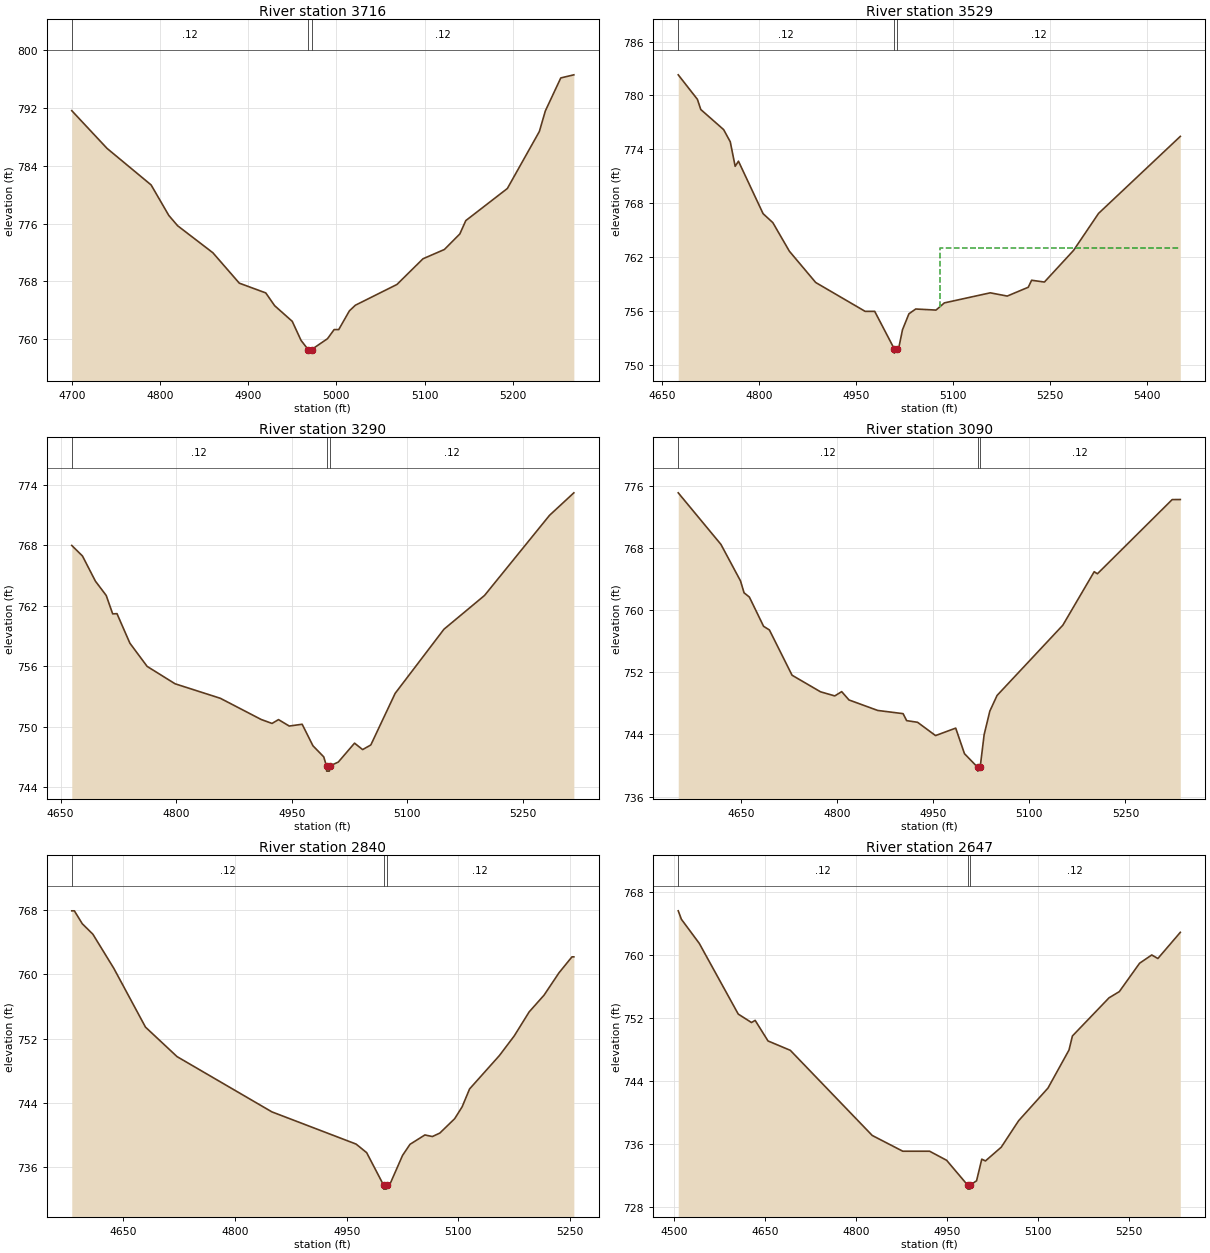
Type RM Length L Ch R = 1 ,3716    ,187,187,187
BEGIN DESCRIPTION:
Guadalupe Tributary 11 8.0
END DESCRIPTION:
XS GIS Cut Line= 3
        2237325.     13831924.99        2237325.       13832225.
      2237575.03     13832325.01
#Sta/Elev= 30
    4700  791.63    4740  786.41    4790  781.35    4810  777.14    4820  775.71
    4860  771.97    4890  767.76    4920  766.41    4930  764.65    4950  762.48
    4960  759.84    4968  758.58  4968.3  758.08  4971.8  758.08    4972  758.58
    4990  760.08  4997.5  761.34  5002.7  761.34  5014.8  763.93  5021.6  764.71
  5068.7  767.58  5098.3  771.14  5122.5  772.42    5140  774.57  5146.8  776.42
  5193.9  780.86  5230.2  788.75    5237   791.6  5254.5  796.16  5269.3  796.59
#Mann= 3 ,-1 , 0
    4700     .12       0    4968     .05       0    4972     .12       0
Bank Sta=4968,4972
XS Rating Curve= 0 ,0
Exp/Cntr=0.3,0.1

Type RM Length L Ch R = 1 ,3529    ,239,239,239
BEGIN DESCRIPTION:
A19110
END DESCRIPTION:
XS GIS Cut Line= 3
      2237216.32      13832005.8      2237164.24     13832290.53
      2237310.03     13832755.67
#Sta/Elev= 30
  4674.7   782.3  4704.4  779.57  4709.6  778.44    4745   776.2  4755.2  774.85
  4762.8  772.12  4767.9  772.69    4806  766.85  4821.1  765.85  4846.7  762.67
  4887.4  759.19  4963.9  755.98  4978.7  755.98  5008.8  751.83    5009  751.33
  5012.8  751.83  5016.4  752.07  5021.7  753.93  5031.7  755.71  5042.2  756.24
  5073.6  756.12  5086.5  756.92  5157.5  758.04  5183.8  757.68  5216.3  758.66
  5221.5  759.44  5241.3  759.24  5286.4  762.76  5325.1  766.88  5451.6  775.45
#Mann= 3 ,-1 , 0
  4674.7     .12       0  5008.8     .05       0  5012.8     .12       0
#XS Ineff= 2 , 0
       0                    5080       0     763
Permanent Ineff=
       F       F
Bank Sta=5008.8,5012.8
XS Rating Curve= 0 ,0
Exp/Cntr=0.3,0.1

Type RM Length L Ch R = 1 ,3290    ,200,200,200
BEGIN DESCRIPTION:
Guadalupe Tributary 11 7.0
END DESCRIPTION:
XS GIS Cut Line= 3
      2237124.99     13832125.02        2236975.       13832425.
        2236875.     13832724.99
#Sta/Elev= 30
  4664.5     768  4678.4  766.95  4695.2  764.45  4709.2  763.03  4717.6   761.2
  4723.2  761.22  4739.9  758.29  4762.3  755.98  4798.6  754.25  4857.3  752.81
  4910.4   750.7  4924.4  750.31  4932.8  750.69  4946.8  750.05  4963.5  750.23
  4977.5  748.09  4991.5  746.99  4995.1  746.07  4995.3  745.57  4998.8  745.57
  4999.1  746.07  5010.4  746.47  5031.5  748.35    5042  747.71  5052.6  748.17
  5084.2   753.3  5147.5  759.67  5200.2  763.03  5284.5  770.99  5316.1  773.23
#Mann= 3 ,-1 , 0
  4664.5     .12       0  4995.1     .05       0  4999.1     .12       0
Bank Sta=4995.1,4999.1
XS Rating Curve= 0 ,0
Exp/Cntr=0.3,0.1

Type RM Length L Ch R = 1 ,3090    ,250,250,250
BEGIN DESCRIPTION:
A19109
END DESCRIPTION:
XS GIS Cut Line= 3
      2236983.66     13831985.01      2236764.93     13832436.36
      2236737.15     13832717.63
#Sta/Elev= 30
  4551.6  775.07  4618.3  768.44  4648.9  763.74  4654.4  762.22  4662.7  761.67
  4684.9  757.91    4694  757.44  4729.4  751.62  4773.8  749.49  4796.1  748.96
  4806.9  749.51  4818.3  748.44  4863.2  747.09  4902.8  746.68  4908.4  745.78
  4925.4  745.57  4953.5  743.86    4985  744.82  4998.7  741.53  5019.2  739.79
  5019.5  739.29  5023.2  739.79  5029.4  743.98  5038.3  747.01  5049.6  749.02
  5152.3  758.05  5201.3  764.93  5206.3  764.66  5323.1   774.2  5335.8  774.21
#Mann= 3 ,-1 , 0
  4551.6     .12       0  5019.2     .05       0  5023.2     .12       0
Bank Sta=5019.2,5023.2
XS Rating Curve= 0 ,0
Exp/Cntr=0.3,0.1

Type RM Length L Ch R = 1 ,2840    ,193,193,193
BEGIN DESCRIPTION:
Guadalupe Tributary 11 6.0
END DESCRIPTION:
XS GIS Cut Line= 3
      2236874.99     13831975.01        2236575.       13832275.
        2236575.     13832524.95
#Sta/Elev= 30
  4580.8  767.94  4584.3  767.94  4594.9  766.33  4609.1  765.03  4637.3  760.76
  4679.8  753.43  4722.2  749.75  4849.5  742.86  4962.6  738.84  4976.8  737.77
  4999.5  733.72  4999.8  733.22  5003.3  733.22  5003.5  733.72  5007.5  733.72
    5025  737.43    5035  738.81    5055  739.98    5065  739.78    5075  740.21
    5095  742.01    5105  743.49    5115  745.72    5155  749.88    5175  752.34
    5195  755.33    5215  757.42    5235   760.2  5252.5   762.2    5255   762.2
#Mann= 3 ,-1 , 0
  4580.8     .12       0  4999.5     .05       0  5003.5     .12       0
Bank Sta=4999.5,5003.5
XS Rating Curve= 0 ,0
Exp/Cntr=0.3,0.1

Type RM Length L Ch R = 1 ,2647    ,256,256,256
BEGIN DESCRIPTION:
A19108
END DESCRIPTION:
XS GIS Cut Line= 3
      2236692.03     13831804.39      2236382.99     13832238.44
      2236348.48     13832531.79
#Sta/Elev= 30
  4506.6  765.59  4511.8  764.52  4541.3  761.46  4605.6  752.49  4627.4  751.42
  4633.5  751.69  4654.7  749.08  4691.5  747.89  4826.6  737.09    4877  735.09
  4921.2  735.09  4949.3  733.94  4984.1  730.78  4984.4  730.28  4987.9  730.28
  4988.1  730.78  4998.7  731.34  5007.3  734.08  5013.4  733.86  5039.4   735.6
  5068.1  738.96  5116.5   743.1  5151.2  747.93  5156.8  749.71  5217.2  754.55
  5234.2  755.34  5267.6  758.94  5287.7  759.99  5297.8  759.54  5334.8  762.86
#Mann= 3 ,-1 , 0
  4506.6     .12       0  4984.1     .05       0  4988.1     .12       0
Bank Sta=4984.1,4988.1
XS Rating Curve= 0 ,0
Exp/Cntr=0.3,0.1

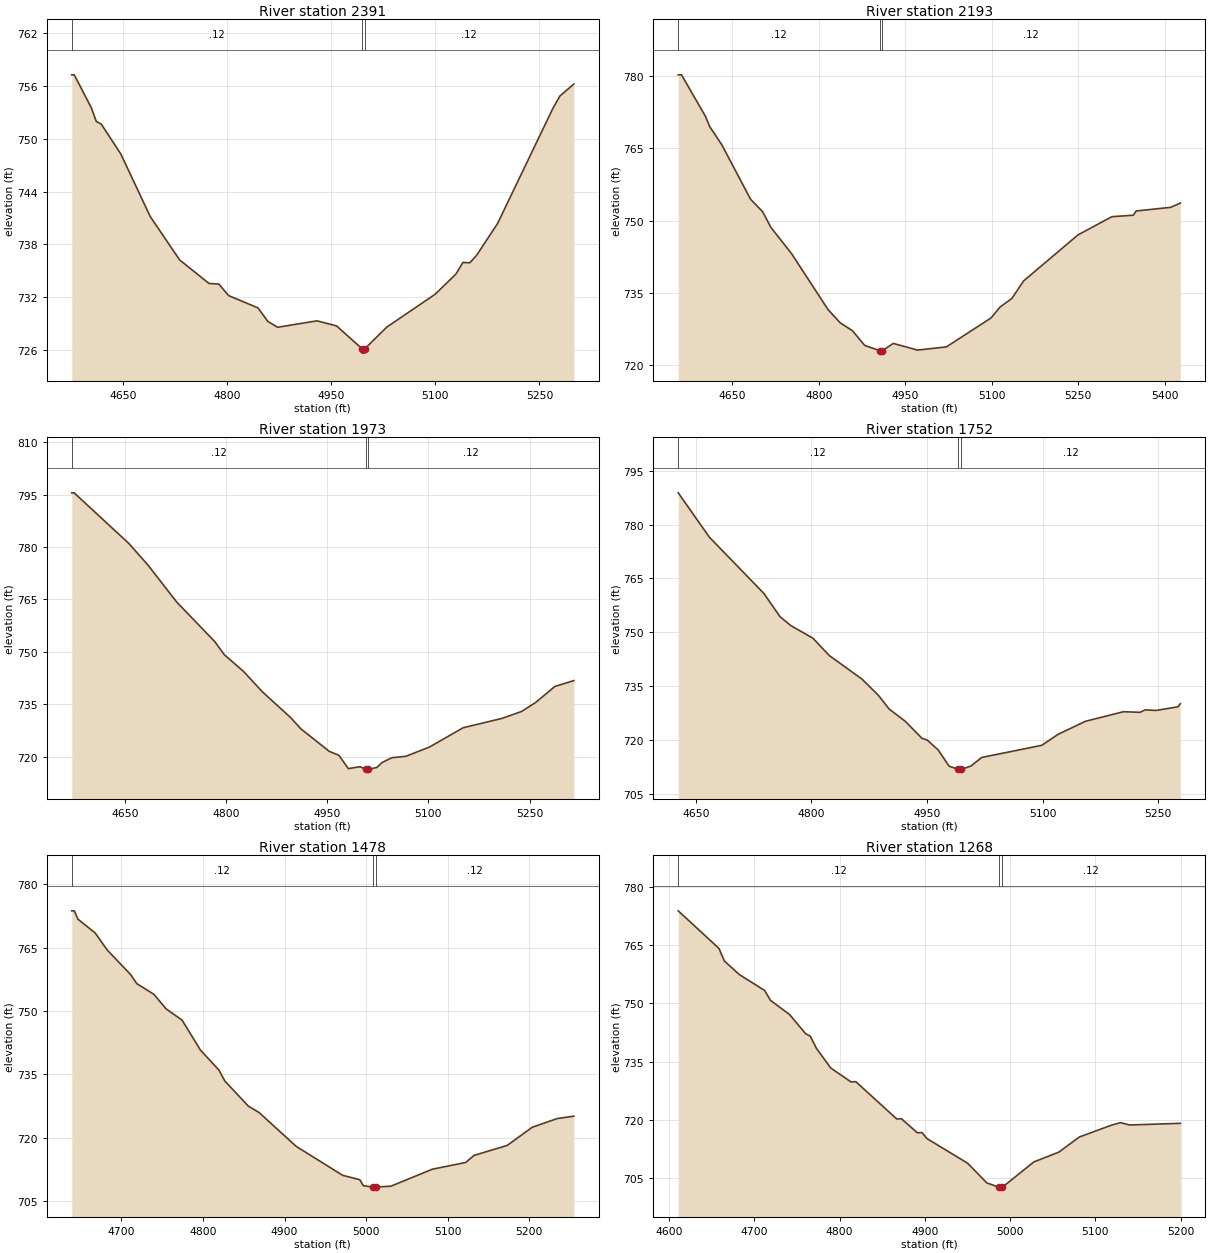
Type RM Length L Ch R = 1 ,2391    ,198,198,198
BEGIN DESCRIPTION:
Guadalupe Tributary 11 5.0
END DESCRIPTION:
XS GIS Cut Line= 3
      2236525.02     13831724.98        2236225.       13832025.
        2236225.       13832325.
#Sta/Elev= 30
  4575.4  757.28    4579  757.28  4603.7  753.52  4610.8  751.98  4617.9  751.68
  4646.1  748.29  4688.6  741.17    4731  736.24  4773.4  733.56  4787.6  733.49
  4801.7  732.18  4844.1  730.78  4858.3  729.24  4872.4  728.58    4929  729.31
  4957.3  728.74  4994.2  726.14  4994.4  725.64  4997.9  725.64  4998.2  726.14
  5029.7  728.59  5099.7  732.34  5129.7  734.64  5139.7  735.95  5149.7  735.91
  5159.7  736.79  5189.7  740.38  5269.7   753.5  5279.7  754.88  5299.7  756.23
#Mann= 3 ,-1 , 0
  4575.4     .12       0  4994.2     .05       0  4998.2     .12       0
Bank Sta=4994.2,4998.2
XS Rating Curve= 0 ,0
Exp/Cntr=0.3,0.1

Type RM Length L Ch R = 1 ,2193    ,220,220,220
BEGIN DESCRIPTION:
A19107
END DESCRIPTION:
XS GIS Cut Line= 3
      2236417.73     13831540.51      2236049.65     13831939.83
      2235983.96     13832261.41
#Sta/Elev= 30
    4556  780.21  4561.7  780.21  4603.3  771.59  4610.7  769.46  4631.7  765.69
  4681.6   754.4  4702.6  751.81  4716.7  748.59  4752.5  743.16    4816  731.53
  4836.9  728.81  4858.5  727.13  4879.5  724.11  4905.8     723  4906.1   722.5
  4909.6   722.5  4909.8     723  4929.3  724.51  4971.3  723.13  5021.3  723.79
  5098.8  729.79  5114.6  732.07    5135  733.84  5155.4  737.48  5249.8  747.02
  5308.5  750.79  5345.7   751.1  5350.8  751.98  5410.6  752.73  5427.3  753.62
#Mann= 3 ,-1 , 0
    4556     .12       0  4905.8     .05       0  4909.8     .12       0
Bank Sta=4905.8,4909.8
XS Rating Curve= 0 ,0
Exp/Cntr=0.3,0.1

Type RM Length L Ch R = 1 ,1973    ,221,221,221
BEGIN DESCRIPTION:
Guadalupe Tributary 11 4.0
END DESCRIPTION:
XS GIS Cut Line= 3
      2236324.99     13831375.01        2236025.       13831675.
      2235775.01     13831874.99
#Sta/Elev= 30
  4571.2  795.51  4574.7  795.51    4656  780.99  4684.3   774.8  4726.8  764.24
  4783.3   752.9  4797.5  749.14  4825.7  744.42    4854  738.51  4896.5  731.03
  4910.6  727.99    4953   721.5  4967.2  720.38  4981.3  716.56  4998.7  717.11
  5007.1  716.34  5007.3  715.84  5010.8  715.84  5011.1  716.34  5023.5   716.9
  5031.5  718.33  5045.9  719.68  5066.7  720.09  5101.9  722.77  5151.5  728.26
  5209.2  730.94    5238  732.91  5258.8  735.47  5287.6  740.09  5315.6  741.76
#Mann= 3 ,-1 , 0
  4571.2     .12       0  5007.1     .05       0  5011.1     .12       0
Bank Sta=5007.1,5011.1
XS Rating Curve= 0 ,0
Exp/Cntr=0.3,0.1

Type RM Length L Ch R = 1 ,1752    ,274,274,274
BEGIN DESCRIPTION:
A19106
END DESCRIPTION:
XS GIS Cut Line= 2
      2236136.45     13831259.29      2235668.82     13831713.06
#Sta/Elev= 30
  4627.2  788.83  4667.7  776.46  4738.4  760.82  4759.5   754.3  4773.7  751.83
    4802  748.37  4823.3  743.53  4865.7  736.98  4886.9  732.49    4901  728.64
  4922.1   725.2  4943.4  720.52  4950.4  720.01  4964.6  717.27  4978.7  712.75
  4990.8  711.87  4991.1  711.37  4994.6  711.37  4994.8  711.87    5007  712.78
  5021.1  715.18  5099.1  718.56  5120.2  721.62  5155.6  725.23  5205.1  727.91
  5226.4  727.74  5233.3  728.41  5247.5  728.26  5275.8  729.28  5278.8  730.13
#Mann= 3 ,-1 , 0
  4627.2     .12       0  4990.8     .05       0  4994.8     .12       0
Bank Sta=4990.8,4994.8
XS Rating Curve= 0 ,0
Exp/Cntr=0.3,0.1

Type RM Length L Ch R = 1 ,1478    ,210,210,210
BEGIN DESCRIPTION:
Guadalupe Tributary 11 3.0
END DESCRIPTION:
XS GIS Cut Line= 3
      2235975.04     13831124.97        2235675.       13831325.
      2235624.99     13831575.05
#Sta/Elev= 30
  4639.1   773.7  4642.2   773.7  4646.7  771.72  4667.7  768.48  4682.7   764.4
  4711.3   758.6  4718.8  756.47  4739.8  753.93  4754.8  750.49  4774.4  747.81
  4796.9  740.72  4819.4  736.04  4826.9  733.38  4855.5  727.48    4869  725.91
  4914.1  717.96  4971.2  711.08  4992.2  710.04  4996.7  708.61  5007.9  708.31
  5008.1  707.81  5011.9  708.31  5030.3   708.5  5081.3  712.53  5122.1  714.12
  5132.3  715.79  5173.1  718.17  5203.7  722.46  5234.3  724.52  5254.7  725.08
#Mann= 3 ,-1 , 0
  4639.1     .12       0  5007.9     .05       0  5011.9     .12       0
Bank Sta=5007.9,5011.9
XS Rating Curve= 0 ,0
Exp/Cntr=0.3,0.1

Type RM Length L Ch R = 1 ,1268    ,225,225,225
BEGIN DESCRIPTION:
A19105
END DESCRIPTION:
XS GIS Cut Line= 2
      2235935.11     13831002.32      2235389.96     13831224.54
#Sta/Elev= 30
  4610.9  773.85  4658.7  764.15    4665  760.92  4682.7   757.4  4712.2  753.33
    4719  750.79  4741.6   747.1  4760.3  742.18  4765.7  741.55    4773  738.39
  4789.7  733.35  4813.7  729.73  4819.1  729.83  4867.2  720.19  4872.6  720.27
  4891.3  716.65  4896.7  716.71  4902.6  715.15  4950.2  708.81  4972.8  703.72
    4987  702.63  4987.2  702.13    4991  702.63  5027.7  709.12  5057.1  711.66
  5081.2  715.56  5118.6  718.59  5129.3  719.27  5140.2  718.66  5199.6  719.09
#Mann= 3 ,-1 , 0
  4610.9     .12       0    4987     .05       0    4991     .12       0
Bank Sta=4987,4991
XS Rating Curve= 0 ,0
Exp/Cntr=0.3,0.1

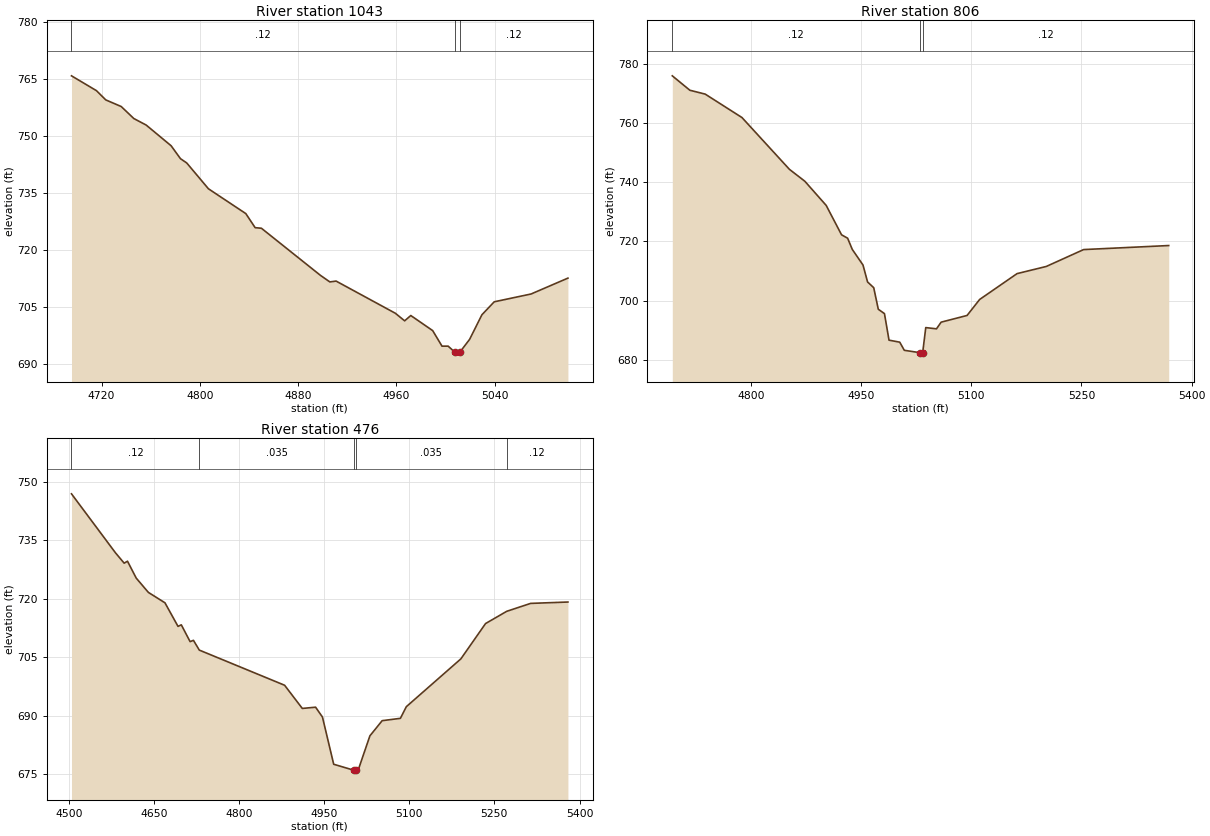
Type RM Length L Ch R = 1 ,1043    ,237,237,237
BEGIN DESCRIPTION:
Guadalupe Tributary 11 2.0
END DESCRIPTION:
XS GIS Cut Line= 3
      2235874.98       13830875.        2235575.       13830925.
      2235475.02       13830925.
#Sta/Elev= 30
  4695.5  765.94  4715.8  762.04  4723.4   759.6    4736  757.85  4746.2   754.7
  4756.3  752.97  4776.6  747.52  4784.2  744.12  4789.3  742.99    4807  736.18
  4837.4  729.65    4845  725.94  4850.1  725.79  4898.2  713.37  4905.8  711.65
  4910.9  711.87  4959.1   703.4  4966.7   701.4  4971.7   702.8  4989.5  698.83
  4997.1  694.73  5002.1  694.73  5007.6  693.13  5007.9  692.63  5011.6  693.13
  5019.6  696.53  5029.6     703  5039.6  706.41  5069.6  708.47  5099.6  712.65
#Mann= 3 ,-1 , 0
  4695.5     .12       0  5007.6     .05       0  5011.6     .12       0
Bank Sta=5007.6,5011.6
XS Rating Curve= 0 ,0
Exp/Cntr=0.3,0.1

Type RM Length L Ch R = 1 ,806     ,330,330,330
BEGIN DESCRIPTION:
A19104
END DESCRIPTION:
XS GIS Cut Line= 3
      2235816.98     13830544.03      2235501.04     13830780.11
      2235379.51     13831033.58
#Sta/Elev= 30
  4693.3  775.86  4717.2     771  4738.1  769.69  4788.1  761.79  4852.7  744.32
  4873.6  740.32  4902.7  732.16  4923.6  722.25  4931.9  721.09  4938.2  717.32
  4952.8  712.05    4959  706.35  4967.4   704.4  4973.6  697.14    4982  695.66
  4988.2  686.71  5002.8  686.03    5009  683.29    5030   682.5  5030.2     682
    5034   682.5  5038.2  690.95  5052.8  690.53  5059.1  692.78  5094.4  695.04
  5111.5  700.43  5162.4  709.15  5202.1  711.56    5253  717.26  5368.8  718.62
#Mann= 3 ,-1 , 0
  4693.3     .12       0    5030     .05       0    5034     .12       0
Bank Sta=5030,5034
XS Rating Curve= 0 ,0
Exp/Cntr=0.3,0.1

Type RM Length L Ch R = 1 ,476     ,0,0,0
BEGIN DESCRIPTION:
A19103
END DESCRIPTION:
XS GIS Cut Line= 4
      2235615.59     13830429.44       2235268.4     13830641.22
      2235216.32     13830800.94      2235323.55     13831081.14
#Sta/Elev= 30
  4504.9  746.92  4582.3  731.81  4597.7  729.13  4603.6  729.63    4619  725.29
  4640.4  721.63  4669.6  718.96  4692.6  712.91  4698.4  713.31  4713.9     709
  4719.8  709.33  4730.1  706.83  4880.4  697.81  4911.6  691.86    4935  692.18
  4947.1  689.65  4966.9  677.54  5002.1  676.02  5002.3  675.52  5006.1  676.02
  5010.2  676.11  5030.7  684.83  5052.3  688.72  5084.4  689.32  5094.9  692.31
    5191  704.58  5234.5  713.64  5271.8  716.78  5313.9  718.81  5379.6  719.16
#Mann= 5 ,-1 , 0
  4504.9     .12       0  4730.1    .035       0  5002.1    .035       0
  5006.1    .035       0  5271.8     .12       0
Bank Sta=5002.1,5006.1
XS Rating Curve= 0 ,0
Exp/Cntr=0.3,0.1

Chan Stop Cuts=-1
Use User Specified Reach Order=0
Composite Channel Slope=5