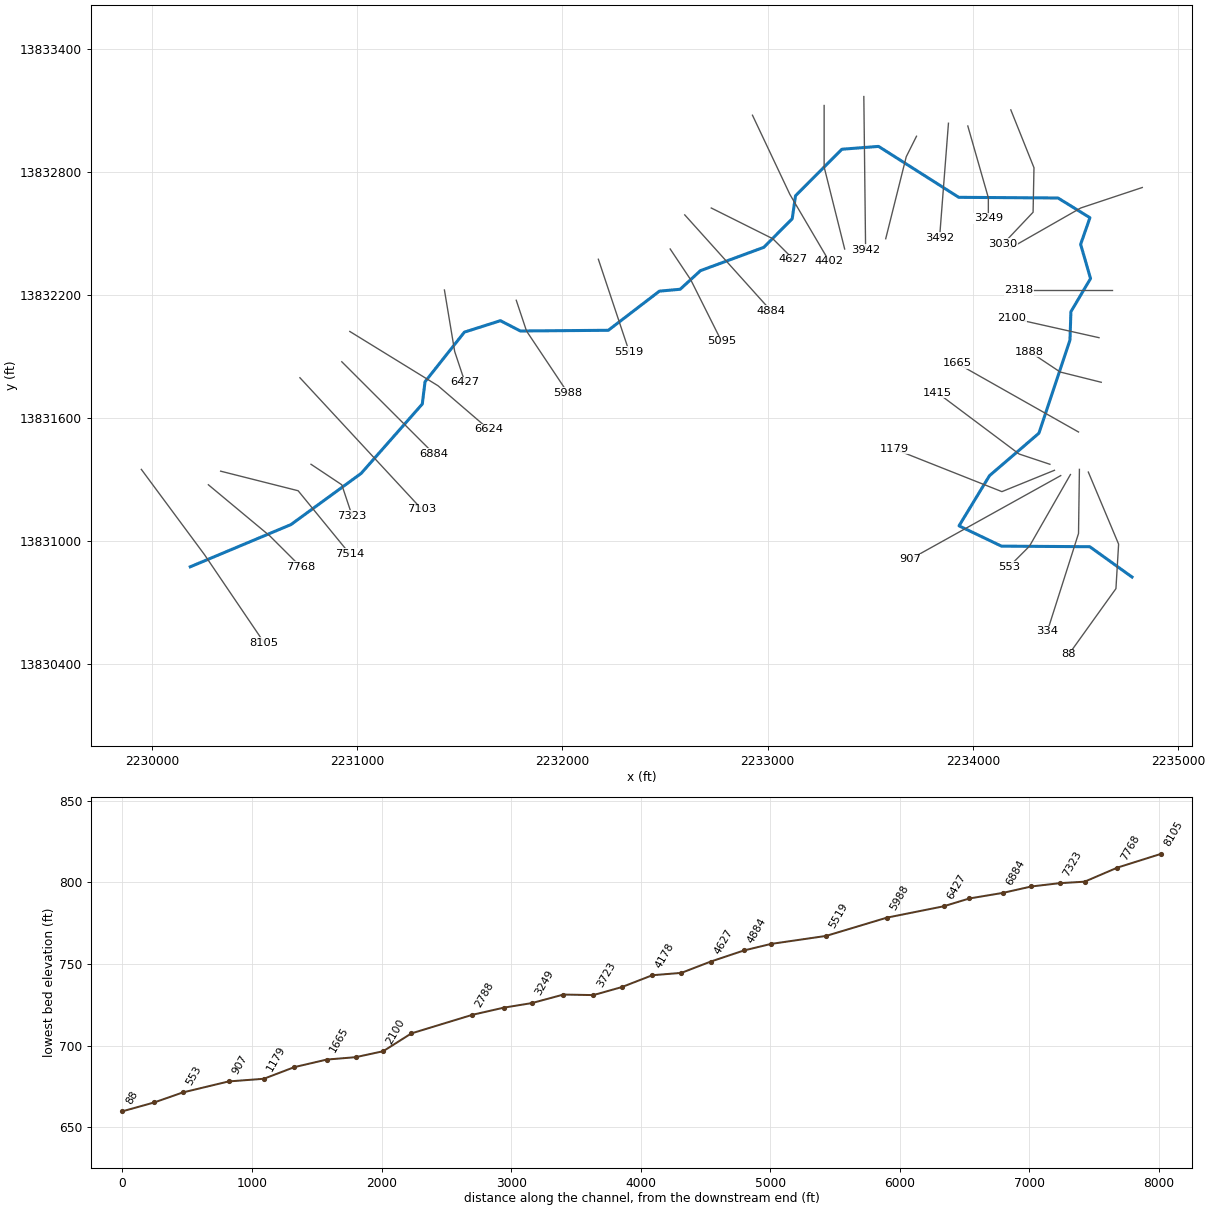
--- Guadalupe Tributary 12.prj (project) ---

Proj Title=Guadalupe Tributary 12 Base Level Engineering
Current Plan=p01
Default Exp/Contr=0.3,0.1
English Units
Geom File=g01
Flow File=f01
Plan File=p01
BEGIN DESCRIPTION:
Guadalupe Tributary 12
END DESCRIPTION:

--- Guadalupe Tributary 12.p01 (plan) ---

Plan Title=Multiple Run
Short Identifier=Multiple
Geom File=g01
Flow File=f01
Subcritical Flow
K Sum by GR= 0
Std Step Tol= 0.01
Critical Tol= 0.01
Num of Std Step Trials= 20
Max Error Tol= 0.3
Flow Tol Ratio= 0.001
Split Flow NTrial= 30
Split Flow Tol= 0.02
Split Flow Ratio= 0.02
Log Output Level= 0
Friction Slope Method= 1
Unsteady Friction Slope Method= 2
Unsteady Bridges Friction Slope Method= 1
Parabolic Critical Depth
Global Vel Dist=  1 , 1 , 1
Global Log Level= 0
CheckData=True
Encroach Param= -1, 0, 0, 0
BEGIN DESCRIPTION:
Multiple Run
END DESCRIPTION:

--- Guadalupe Tributary 12.f01 (steady flow) ---

Flow Title=Multiple
Number of Profiles=7
Profile Names=10-year,25-year,50-year,1pct_min,100-year,1pct_plu,500-year
River Rch & RM= Guadalupe Tribut,Reach-1,8105
     604     996    1361     905    1805    3601    3133
River Rch & RM= Guadalupe Tribut,Reach-1,7514
    1357    2338    3287    2240    4470    8919    8175
River Rch & RM= Guadalupe Tribut,Reach-1,4402
    1575    2722    3836    2617    5221   10418    9572
Boundary for River Rch & Prof#=Guadalupe Tribut,Reach-1,1
Up Type=0
Dn Type=3
Dn Slope=0.005
Boundary for River Rch & Prof#=Guadalupe Tribut,Reach-1,2
Up Type=0
Dn Type=3
Dn Slope=0.005
Boundary for River Rch & Prof#=Guadalupe Tribut,Reach-1,3
Up Type=0
Dn Type=3
Dn Slope=0.005
Boundary for River Rch & Prof#=Guadalupe Tribut,Reach-1,4
Up Type=0
Dn Type=3
Dn Slope=0.005
Boundary for River Rch & Prof#=Guadalupe Tribut,Reach-1,5
Up Type=0
Dn Type=3
Dn Slope=0.005
Boundary for River Rch & Prof#=Guadalupe Tribut,Reach-1,6
Up Type=0
Dn Type=3
Dn Slope=0.005
Boundary for River Rch & Prof#=Guadalupe Tribut,Reach-1,7
Up Type=0
Dn Type=3
Dn Slope=0.005

--- Guadalupe Tributary 12.g01 (geometry) ---

Geom Title=Existing Conditions

River Reach=Guadalupe Tribut,Reach-1
Reach XY= 30
      2230186.88     13830875.00      2230677.29     13831080.85
      2231019.38     13831330.62      2231317.14     13831668.83
      2231330.52     13831777.43      2231522.33     13832019.58
      2231697.81     13832075.38      2231795.03     13832025.09
      2232223.53     13832028.55      2232472.58     13832219.46
      2232573.50     13832228.63      2232672.58     13832319.46
      2232981.06     13832433.14      2233119.48     13832572.57
      2233135.52     13832684.79      2233361.68     13832911.63
      2233540.18     13832925.44      2233930.86     13832677.06
      2234414.50     13832673.80      2234570.01     13832577.55
      2234524.63     13832447.81      2234572.86     13832280.97
      2234477.25     13832119.07      2234472.73     13831980.94
      2234321.39     13831526.50      2234080.62     13831319.38
      2233932.18     13831074.67      2234138.92     13830975.68
      2234569.15     13830972.94      2234775.00     13830825.00

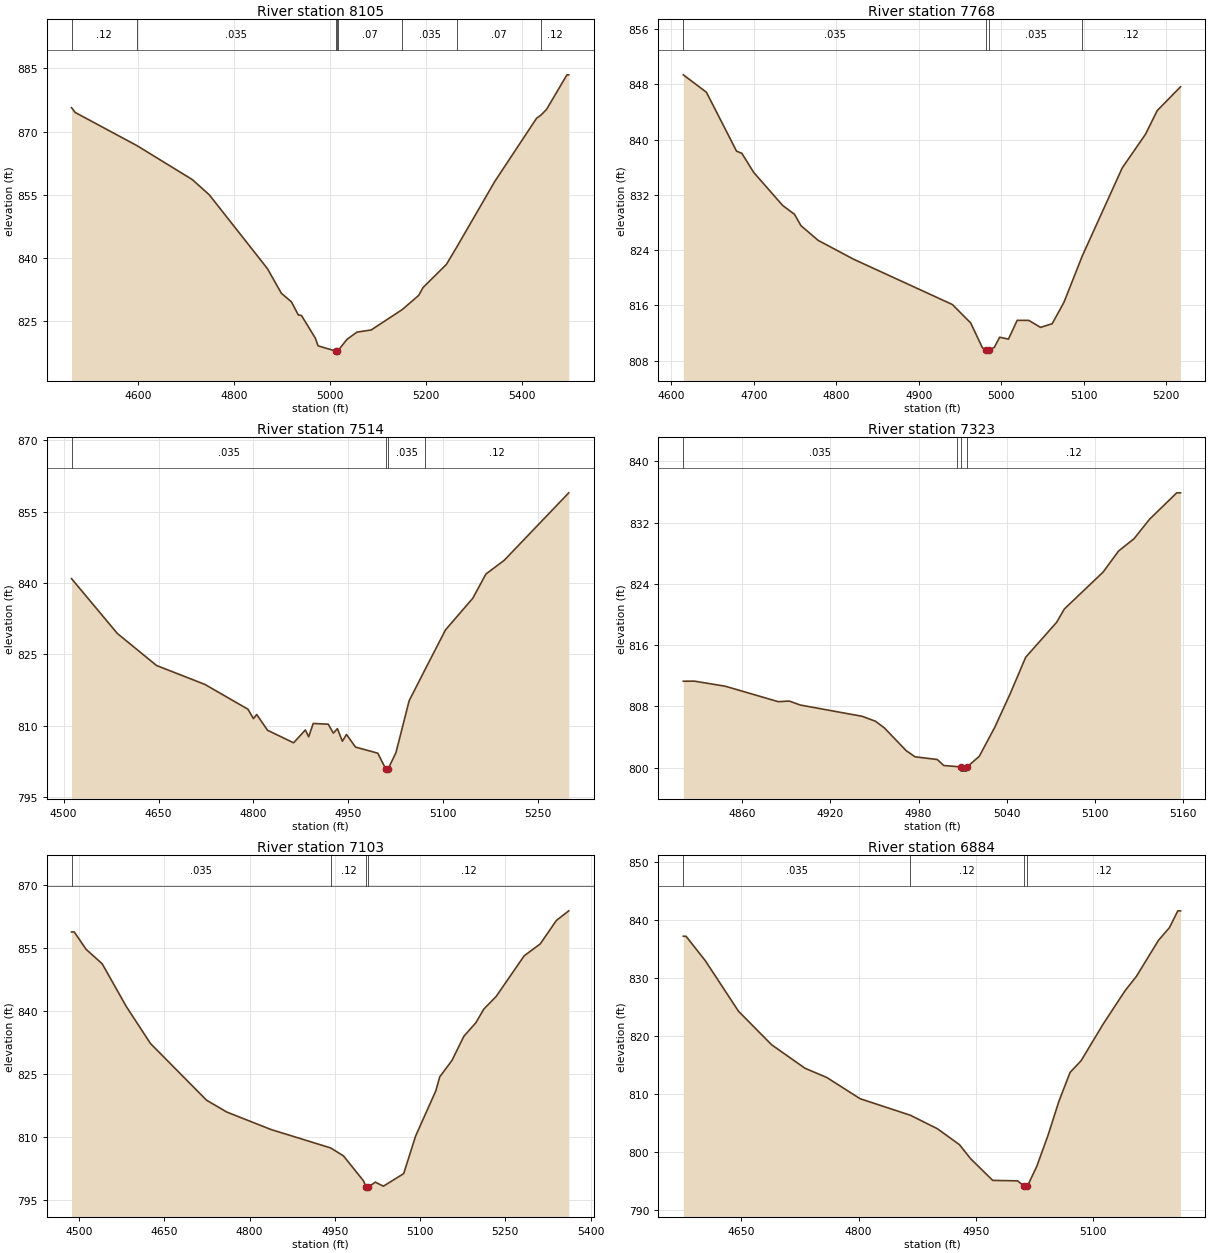
Type RM Length L Ch R = 1,8105,337,337,337
BEGIN DESCRIPTION:
A19136
END DESCRIPTION:
XS GIS Cut Line= 3
      2229948.37     13831350.10      2230256.55     13830933.41
      2230547.34     13830503.73
#Sta/Elev= 30
  4461.0  875.67  4468.7  874.53  4596.9  866.71  4712.9  858.63  4748.4  855.01
  4869.5  837.54  4898.7  831.68  4919.6  829.66  4934.2  826.52  4940.4  826.45
  4969.7  821.02  4975.2  819.23  5011.6  818.00  5011.8  817.50  5015.6  818.00
  5016.5  818.04  5035.3  820.74  5056.3  822.48  5086.0  822.99  5150.5  827.80
  5185.2  831.19  5194.1  833.03  5243.0  838.54  5264.6  842.66  5344.0  858.22
  5430.8  873.13  5440.5  873.95  5451.8  875.26  5494.3  883.45  5498.1  883.45
#Mann=8,-1,0
  4461.0    0.12       0  4596.9   0.035       0  5011.6   0.035       0
  5015.6   0.035       0  5016.5    0.07       0  5150.5   0.035       0
  5264.6    0.07       0  5440.5    0.12       0
Bank Sta=5011.6,5015.6
Exp/Cntr=0.3,0.1

Type RM Length L Ch R = 1,7768,254,254,254
BEGIN DESCRIPTION:
Guadalupe Tributary 12 17.0
END DESCRIPTION:
XS GIS Cut Line= 3
      2230274.97     13831275.03      2230575.00     13831025.00
      2230725.01     13830874.99
#Sta/Elev= 30
  4614.7  849.38  4642.7  846.86  4679.2  838.33  4685.7  838.01  4700.0  835.25
  4735.1  830.47  4749.5  829.18  4757.3  827.54  4778.1  825.41  4821.1  822.68
  4940.8  816.12  4962.9  813.47  4977.3  809.85  4981.8  809.58  4982.0  809.08
  4985.5  809.08  4985.8  809.58  4991.6  809.90  4998.1  811.38  5008.8  811.11
  5019.4  813.83  5033.5  813.82  5047.7  812.81  5061.8  813.34  5076.0  816.42
  5098.1  823.10  5146.7  835.90  5175.0  840.79  5189.1  844.20  5217.4  847.65
#Mann=4,-1,0
  4614.7   0.035       0  4981.8   0.035       0  4985.8   0.035       0
  5098.1    0.12       0
Bank Sta=4981.8,4985.8
Exp/Cntr=0.3,0.1

Type RM Length L Ch R = 1,7514,191,191,191
BEGIN DESCRIPTION:
A19135
END DESCRIPTION:
XS GIS Cut Line= 3
      2230334.69     13831341.39      2230712.28     13831245.91
      2230963.07     13830938.90
#Sta/Elev= 30
  4512.4  840.94  4584.9  829.39  4646.8  822.66  4723.1  818.69  4791.2  813.47
  4800.0  811.49  4805.1  812.35  4822.2  809.04  4863.4  806.40  4882.0  809.11
  4887.2  807.65  4894.4  810.47  4918.2  810.31  4926.2  808.44  4932.6  809.38
  4940.5  806.73  4947.0  808.16  4961.2  805.50  4996.5  804.21  5008.9  800.94
  5009.1  800.44  5012.9  800.94  5025.2  804.34  5046.0  815.24  5070.6  821.66
  5103.5  830.16  5146.6  836.81  5167.4  841.91  5196.1  844.77  5298.3  858.99
#Mann=4,-1,0
  4512.4   0.035       0  5008.9   0.035       0  5012.9   0.035       0
  5070.6    0.12       0
Bank Sta=5008.9,5012.9
Exp/Cntr=0.3,0.1

Type RM Length L Ch R = 1,7323,220,220,220
BEGIN DESCRIPTION:
Guadalupe Tributary 12 16.0
END DESCRIPTION:
XS GIS Cut Line= 3
      2230775.00     13831375.00      2230925.00     13831275.00
      2230975.00     13831125.00
#Sta/Elev= 30
  4819.9  811.29  4827.4  811.30  4848.4  810.64  4884.5  808.62  4892.0  808.70
  4899.5  808.18  4941.6  806.71  4950.6  806.07  4956.6  805.22  4971.6  802.22
  4977.6  801.42  4992.7  801.07  4997.2  800.28  5006.4  800.14  5008.7  800.05
  5009.0  799.55  5012.5  799.55  5012.7  800.05  5021.3  801.48  5031.8  805.25
  5042.3  809.63  5052.9  814.42  5074.0  818.99  5079.2  820.72  5105.6  825.54
  5116.1  828.29  5126.7  829.91  5137.2  832.44  5155.7  835.89  5158.3  835.89
#Mann=4,-1,0
  4819.9   0.035       0  5006.4    0.12       0  5008.7   0.035       0
  5012.7    0.12       0
Bank Sta=5008.7,5012.7
Exp/Cntr=0.3,0.1

Type RM Length L Ch R = 1,7103,219,219,219
BEGIN DESCRIPTION:
A19134
END DESCRIPTION:
XS GIS Cut Line= 2
      2230720.98     13831797.10      2231315.58     13831154.76
#Sta/Elev= 30
  4486.4  858.85  4491.2  858.85  4512.1  854.70  4540.4  851.26  4582.9  841.05
  4625.4  832.24  4724.1  818.72  4759.8  815.89  4837.5  811.73  4942.5  807.34
  4965.1  805.44  5000.2  799.52  5005.1  798.01  5005.3  797.51  5009.1  798.01
  5021.2  799.18  5035.4  798.21  5071.1  801.21  5092.1  810.17  5127.8  820.99
  5134.6  824.30  5156.1  828.20  5177.1  833.98  5198.1  837.19  5212.3  840.48
  5233.8  843.45  5283.2  853.16  5311.5  856.00  5339.9  861.59  5361.7  863.89
#Mann=4,-1,0
  4486.4   0.035       0  4942.5    0.12       0  5005.1    0.05       0
  5009.1    0.12       0
Bank Sta=5005.1,5009.1
Exp/Cntr=0.3,0.1

Type RM Length L Ch R = 1,6884,260,260,260
BEGIN DESCRIPTION:
Guadalupe Tributary 12 15.0
END DESCRIPTION:
XS GIS Cut Line= 3
      2230925.00     13831875.00      2231225.00     13831575.00
      2231375.01     13831424.99
#Sta/Elev= 30
  4575.7  837.26  4579.2  837.26  4604.0  833.01  4646.4  824.30  4688.8  818.52
  4731.3  814.48  4759.5  812.86  4802.0  809.21  4866.4  806.35  4901.0  804.02
  4929.2  801.27  4943.4  798.85  4971.7  795.11  5003.5  795.03  5012.1  794.10
  5012.4  793.60  5015.9  793.60  5016.1  794.10  5028.2  797.57  5042.4  802.86
  5056.5  808.80  5070.7  813.75  5084.8  815.77  5113.1  822.11  5141.4  827.92
  5155.5  830.31  5183.8  836.55  5197.9  838.75  5208.6  841.65  5212.1  841.65
#Mann=4,-1,0
  4575.7   0.035       0  4866.4    0.12       0  5012.1    0.05       0
  5016.1    0.12       0
Bank Sta=5012.1,5016.1
Exp/Cntr=0.3,0.1

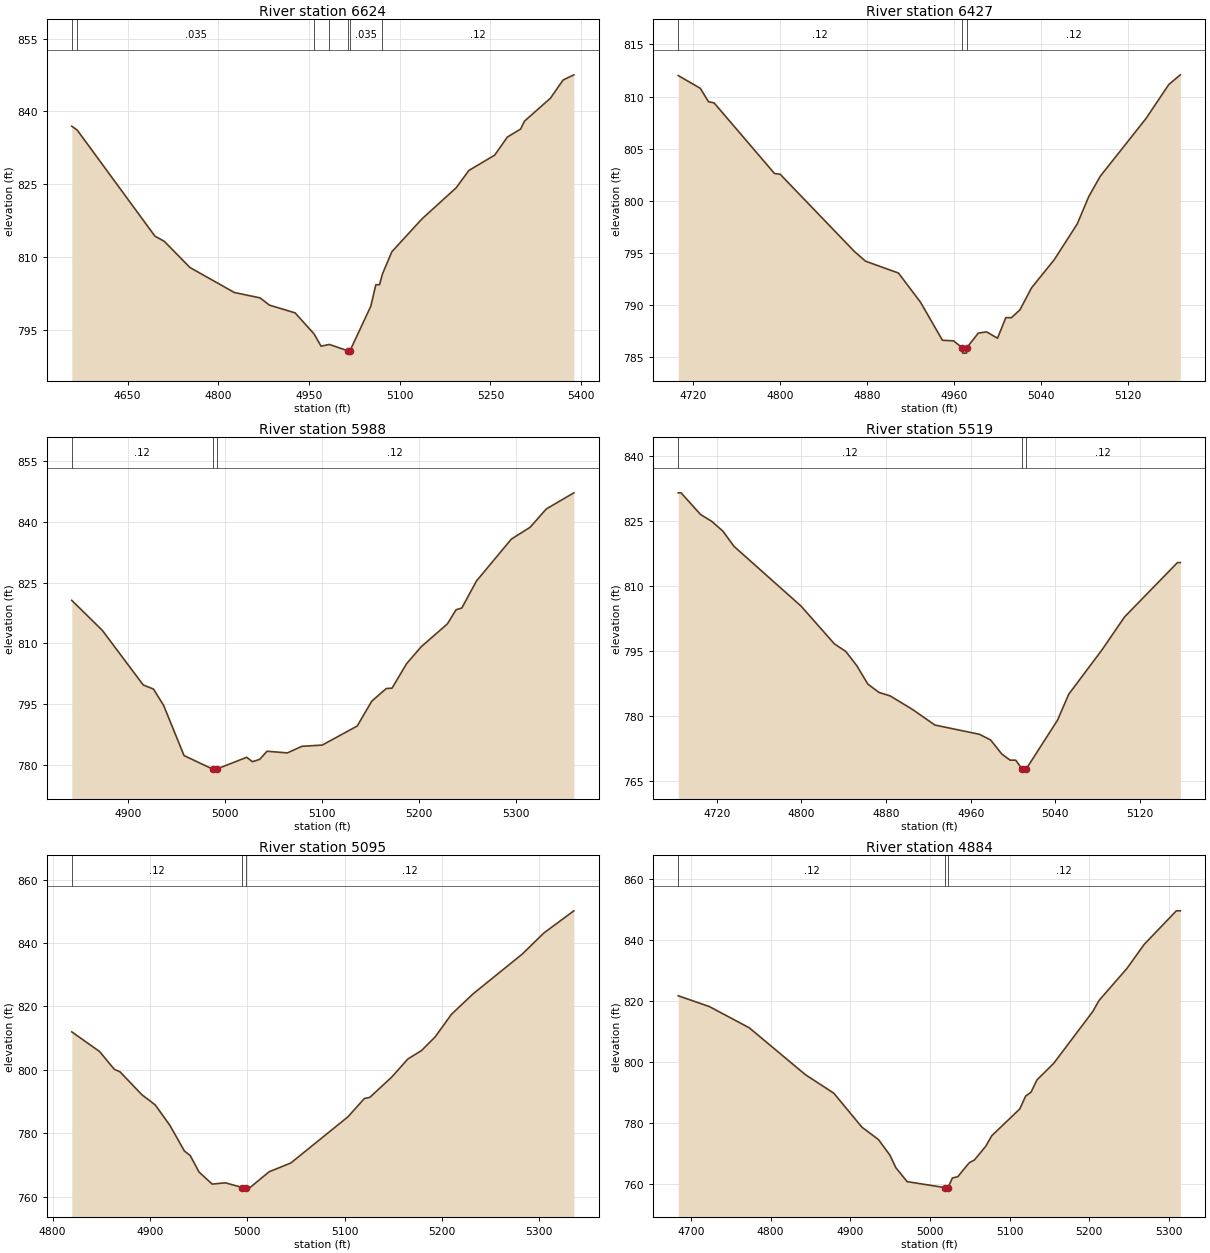
Type RM Length L Ch R = 1,6624,197,197,197
BEGIN DESCRIPTION:
A19133
END DESCRIPTION:
XS GIS Cut Line= 3
      2230964.04     13832022.80      2231393.70     13831758.06
      2231640.55     13831545.86
#Sta/Elev= 30
  4557.7  836.95  4566.7  836.15  4695.2  814.28  4710.6  813.22  4753.2  807.81
  4826.5  802.66  4869.1  801.55  4884.5  800.06  4927.0  798.46  4958.4  794.11
  4969.9  791.59  4983.7  791.95  5013.8  790.66  5014.0  790.16  5017.8  790.66
  5052.2  799.84  5060.5  804.26  5066.5  804.26  5071.5  806.50  5087.0  811.07
  5136.4  817.79  5193.4  824.26  5214.3  827.82  5257.1  830.99  5277.9  834.70
  5299.9  836.36  5306.4  838.01  5349.2  842.72  5370.1  846.47  5387.9  847.54
#Mann=7,-1,0
  4557.7    0.12       0  4566.7   0.035       0  4958.4    0.12       0
  4983.7   0.035       0  5013.8   0.035       0  5017.8   0.035       0
  5071.5    0.12       0
Bank Sta=5013.8,5017.8
Exp/Cntr=0.3,0.1

Type RM Length L Ch R = 1,6427,439,439,439
BEGIN DESCRIPTION:
Guadalupe Tributary 12 14.0
END DESCRIPTION:
XS GIS Cut Line= 3
      2231424.99     13832225.03      2231475.00     13831925.00
      2231525.01     13831774.98
#Sta/Elev= 30
  4706.1  812.02  4726.4  810.80  4734.0  809.51  4739.1  809.40  4794.8  802.62
  4799.9  802.56  4868.3  795.15  4878.5  794.22  4908.9  793.08  4929.2  790.28
  4949.4  786.63  4959.6  786.58  4967.7  785.90  4968.0  785.40  4971.5  785.40
  4971.7  785.90  4982.4  787.32  4990.0  787.44  5000.1  786.83  5007.7  788.80
  5012.9  788.80  5020.8  789.56  5031.4  791.66  5052.4  794.37  5073.5  797.79
  5084.1  800.41  5094.6  802.35  5136.8  807.90  5157.8  811.16  5168.4  812.09
#Mann=3,-1,0
  4706.1    0.12       0  4967.7    0.05       0  4971.7    0.12       0
Bank Sta=4967.7,4971.7
Exp/Cntr=0.3,0.1

Type RM Length L Ch R = 1,5988,469,469,469
BEGIN DESCRIPTION:
Guadalupe Tributary 12 13.0
END DESCRIPTION:
XS GIS Cut Line= 3
      2231774.99     13832175.03      2231825.00     13832025.00
      2232025.00     13831725.00
#Sta/Elev= 30
  4841.4  820.59  4873.1  813.15  4915.2  799.71  4925.8  798.69  4936.3  794.66
  4957.4  782.27  4987.0  778.93  4987.3  778.43  4991.0  778.93  5022.1  781.84
  5028.1  780.76  5035.6  781.34  5043.1  783.34  5064.1  782.93  5079.2  784.56
  5100.2  784.86  5136.3  789.57  5151.3  795.70  5166.3  798.82  5172.3  798.92
  5187.3  804.95  5202.4  809.14  5229.4  814.77  5238.4  818.26  5244.4  818.71
  5259.4  825.34  5295.5  835.71  5315.0  838.65  5331.6  843.15  5360.1  847.14
#Mann=3,-1,0
  4841.4    0.12       0  4987.0    0.05       0  4991.0    0.12       0
Bank Sta=4987,4991
Exp/Cntr=0.3,0.1

Type RM Length L Ch R = 1,5519,424,424,424
BEGIN DESCRIPTION:
Guadalupe Tributary 12 12.0
END DESCRIPTION:
XS GIS Cut Line= 3
      2232174.99     13832375.04      2232275.00     13832075.00
      2232325.01     13831924.98
#Sta/Elev= 30
  4683.7  831.44  4686.4  831.44  4704.8  826.44  4715.4  824.85  4725.9  822.60
  4736.4  819.09  4799.7  805.33  4831.3  796.59  4841.9  794.88  4852.4  791.58
  4862.9  787.31  4873.5  785.39  4884.0  784.60  4905.1  781.47  4926.2  777.88
  4968.3  775.75  4978.9  774.43  4989.4  771.20  4997.3  769.78  5002.6  769.78
  5008.5  767.75  5008.8  767.25  5012.3  767.25  5012.5  767.75  5042.1  779.01
  5052.7  785.00  5084.3  795.29  5105.4  802.81  5155.4  815.35  5158.1  815.35
#Mann=3,-1,0
  4683.7    0.12       0  5008.5    0.05       0  5012.5    0.12       0
Bank Sta=5008.5,5012.5
Exp/Cntr=0.3,0.1

Type RM Length L Ch R = 1,5095,211,211,211
BEGIN DESCRIPTION:
Guadalupe Tributary 12 11.0
END DESCRIPTION:
XS GIS Cut Line= 3
      2232524.98     13832425.03      2232625.00     13832275.00
      2232774.99     13831975.02
#Sta/Elev= 30
  4819.7  811.96  4848.3  805.76  4863.3  800.18  4869.3  799.35  4891.8  792.12
  4905.4  788.94  4920.4  782.53  4935.4  774.38  4941.4  772.95  4950.4  767.77
  4964.0  763.95  4977.5  764.36  4995.0  762.87  4995.3  762.37  4999.0  762.87
  5002.8  762.87  5022.4  767.84  5044.7  770.61  5103.4  785.18  5120.2  790.94
  5125.8  791.30  5148.2  797.66  5164.9  803.41  5178.9  806.06  5192.9  810.35
  5209.6  817.47  5232.0  823.97  5282.3  836.46  5304.7  843.16  5335.4  850.13
#Mann=3,-1,0
  4819.7    0.12       0  4995.0    0.05       0  4999.0    0.12       0
Bank Sta=4995,4999
Exp/Cntr=0.3,0.1

Type RM Length L Ch R = 1,4884,257,257,257
BEGIN DESCRIPTION:
A19132
END DESCRIPTION:
XS GIS Cut Line= 2
      2232595.94     13832591.41      2233016.98     13832122.63
#Sta/Elev= 30
  4684.2  821.82  4723.3  818.27  4773.4  811.29  4843.7  795.93  4879.5  789.82
  4914.7  778.68  4935.6  774.57  4949.8  769.51  4957.3  765.37  4971.5  760.79
  5018.8  758.83  5019.1  758.33  5022.8  758.83  5028.3  761.99  5035.0  762.40
  5049.2  766.94  5055.9  767.90  5070.1  772.39  5077.6  775.84  5112.8  784.65
  5120.2  788.88  5127.0  790.19  5134.4  794.19  5155.4  799.63  5204.7  816.74
  5212.2  820.24  5247.3  830.78  5269.0  838.70  5309.3  849.71  5314.3  849.71
#Mann=3,-1,0
  4684.2    0.12       0  5018.8    0.05       0  5022.8    0.12       0
Bank Sta=5018.8,5022.8
Exp/Cntr=0.3,0.1

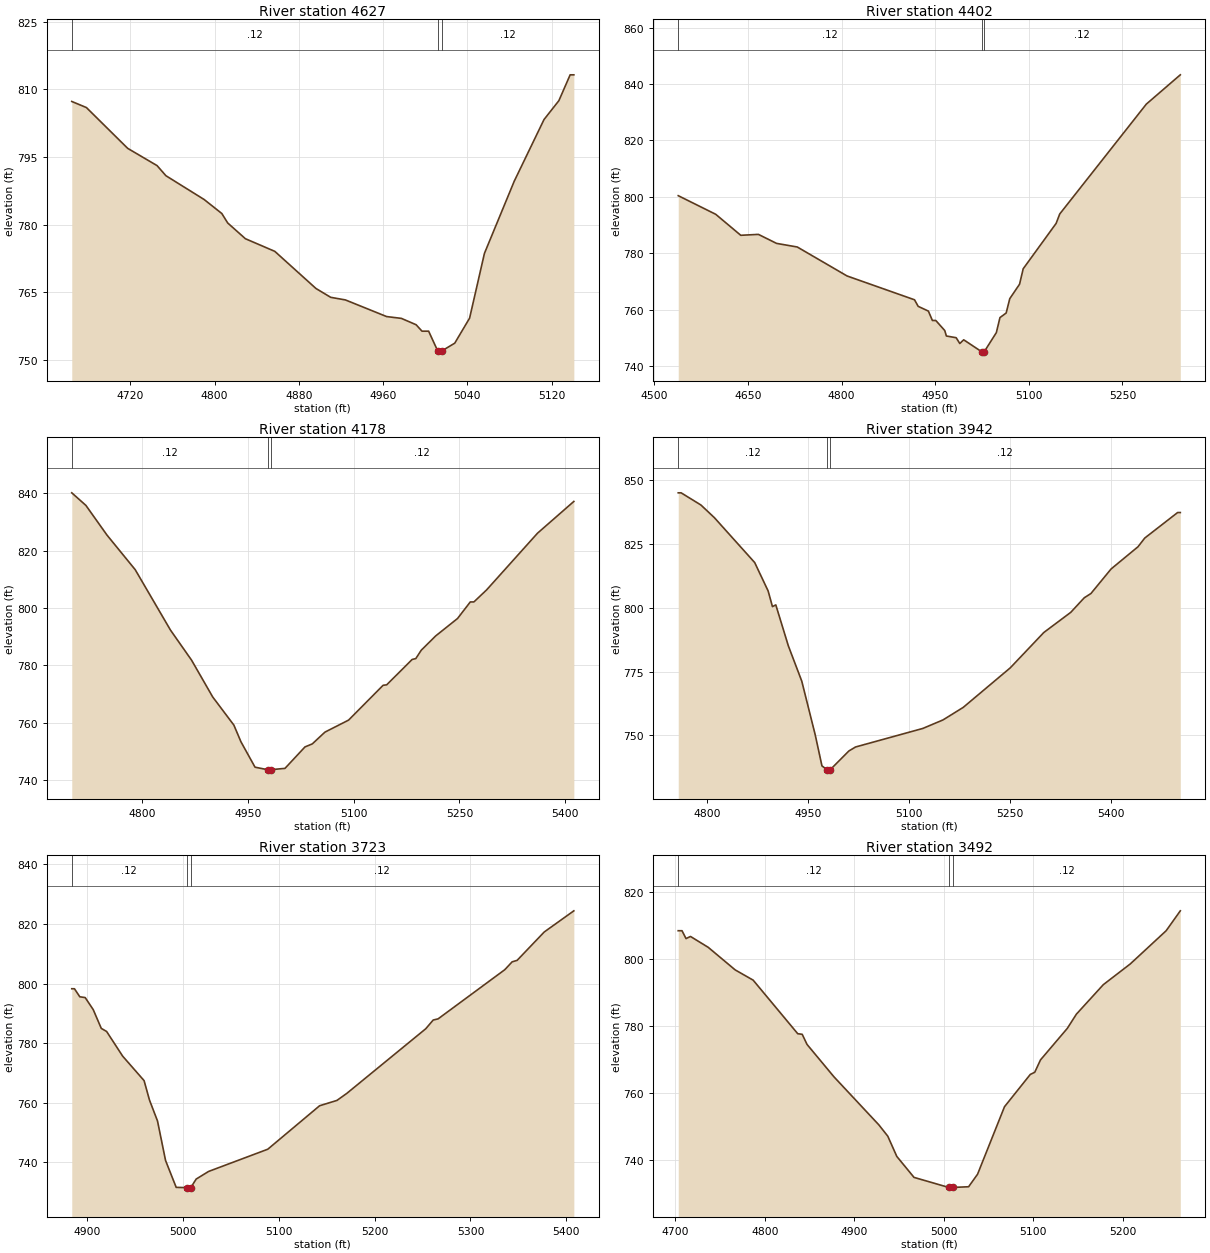
Type RM Length L Ch R = 1,4627,225,225,225
BEGIN DESCRIPTION:
Guadalupe Tributary 12 10.0
END DESCRIPTION:
XS GIS Cut Line= 3
      2232725.04     13832624.98      2233025.00     13832475.00
      2233125.01     13832374.99
#Sta/Elev= 30
  4664.4  807.34  4678.3  805.99  4717.5  796.94  4745.4  793.11  4753.8  790.87
  4790.1  785.59  4806.9  782.48  4812.5  780.38  4829.3  776.89  4857.2  774.09
  4896.3  765.85  4910.3  763.89  4924.3  763.31  4963.4  759.62  4977.4  759.22
  4991.4  757.81  4997.0  756.38  5003.3  756.38  5011.9  752.01  5012.2  751.51
  5015.7  751.51  5015.9  752.01  5028.1  753.72  5042.2  759.27  5056.3  773.64
  5084.6  789.65  5112.9  803.34  5127.0  807.52  5137.7  813.25  5141.2  813.25
#Mann=3,-1,0
  4664.4    0.12       0  5011.9    0.05       0  5015.9    0.12       0
Bank Sta=5011.9,5015.9
Exp/Cntr=0.3,0.1

Type RM Length L Ch R = 1,4402,224,224,224
BEGIN DESCRIPTION:
A19131
END DESCRIPTION:
XS GIS Cut Line= 3
      2232925.82     13833077.51      2233108.11     13832691.22
      2233299.11     13832365.66
#Sta/Elev= 30
  4538.1  800.43  4598.2  793.83  4638.3  786.39  4666.6  786.71  4695.7  783.52
  4728.9  782.24  4808.7  771.97  4916.8  763.53  4922.6  761.21  4939.0  759.52
  4945.4  756.20  4950.9  756.19  4965.2  752.64  4967.8  750.70  4983.5  750.09
  4989.3  748.04  4995.6  749.35  5024.3  745.13  5024.6  744.63  5028.5  745.13
  5047.9  751.90  5053.7  757.23  5063.6  758.84  5069.4  763.93  5085.1  769.06
  5090.9  774.52  5143.7  790.61  5149.5  793.95  5288.2  832.87  5342.7  843.26
#Mann=3,-1,0
  4538.1    0.12       0  5024.3    0.05       0  5028.5    0.12       0
Bank Sta=5024.3,5028.5
Exp/Cntr=0.3,0.1

Type RM Length L Ch R = 1,4178,236,236,236
BEGIN DESCRIPTION:
Guadalupe Tributary 12 9.0
END DESCRIPTION:
XS GIS Cut Line= 3
      2233275.00     13833124.95      2233275.00     13832825.00
      2233375.01     13832424.96
#Sta/Elev= 30
  4700.1  840.14  4720.1  835.77  4750.1  825.41  4790.1  813.37  4840.1  792.34
  4870.1  781.83  4900.1  769.01  4930.1  759.22  4940.1  753.42  4960.1  744.56
  4978.0  743.69  4978.2  743.19  4982.2  743.69  5002.6  744.15  5031.0  751.63
  5041.3  752.67  5059.3  756.78  5092.8  760.96  5141.8  773.09  5146.9  773.26
  5183.0  782.09  5188.2  782.40  5195.9  785.31  5216.5  790.31  5247.4  796.36
  5265.5  802.13  5270.6  802.13  5288.7  806.34  5360.8  826.06  5412.4  837.14
#Mann=3,-1,0
  4700.1    0.12       0  4978.0    0.05       0  4982.2    0.12       0
Bank Sta=4978,4982.2
Exp/Cntr=0.3,0.1

Type RM Length L Ch R = 1,3942,219,219,219
BEGIN DESCRIPTION:
A19130
END DESCRIPTION:
XS GIS Cut Line= 2
      2233468.36     13833168.65      2233477.04     13832422.10
#Sta/Elev= 30
  4756.5  845.09  4760.8  845.09  4790.2  840.32  4810.2  835.36  4870.2  817.74
  4890.2  806.59  4896.6  800.46  4901.6  801.13  4920.2  785.10  4940.2  771.22
  4960.2  750.17  4970.2  737.99  4978.1  736.43  4978.3  735.93  4982.3  736.43
  5010.2  743.82  5020.2  745.40  5120.2  752.67  5150.2  756.01  5180.2  760.91
  5250.2  776.43  5300.2  790.32  5340.2  798.21  5360.2  803.90  5370.2  805.60
  5400.2  815.23  5440.2  823.94  5450.2  827.34  5499.1  837.36  5503.1  837.36
#Mann=3,-1,0
  4756.5    0.12       0  4978.1    0.05       0  4982.3    0.12       0
Bank Sta=4978.1,4982.3
Exp/Cntr=0.3,0.1

Type RM Length L Ch R = 1,3723,231,231,231
BEGIN DESCRIPTION:
Guadalupe Tributary 12 8.0
END DESCRIPTION:
XS GIS Cut Line= 3
      2233725.01     13832975.03      2233675.00     13832875.00
      2233575.01     13832475.05
#Sta/Elev= 30
  4883.8  798.28  4886.6  798.28  4892.2  795.58  4897.8  795.32  4906.2  791.27
  4914.6  784.98  4920.2  783.93  4936.9  775.67  4959.3  767.44  4964.9  760.95
  4973.3  753.90  4981.7  740.65  4992.8  731.62  5003.8  731.53  5004.1  731.03
  5008.0  731.53  5013.7  734.41  5026.6  736.96  5088.4  744.42  5142.5  759.01
  5160.6  760.80  5170.9  763.16  5253.3  784.85  5261.1  787.78  5266.2  788.17
  5335.8  804.67  5343.5  807.31  5348.7  807.81  5377.0  817.33  5407.9  824.43
#Mann=3,-1,0
  4883.8    0.12       0  5003.8    0.05       0  5008.0    0.12       0
Bank Sta=5003.8,5008
Exp/Cntr=0.3,0.1

Type RM Length L Ch R = 1,3492,243,243,243
BEGIN DESCRIPTION:
A19129
END DESCRIPTION:
XS GIS Cut Line= 2
      2233880.68     13833038.45      2233837.33     13832479.23
#Sta/Elev= 30
  4703.3  808.37  4707.5  808.37  4712.0  806.03  4717.0  806.66  4736.8  803.42
  4766.9  796.70  4787.0  793.64  4836.8  777.68  4841.8  777.50  4847.2  774.48
  4877.3  764.82  4927.4  750.52  4937.4  747.14  4947.5  741.10  4966.7  734.86
  5005.5  731.86  5005.8  731.36  5009.8  731.86  5027.7  732.07  5037.7  735.80
  5067.8  755.92  5096.6  765.54  5101.6  766.19  5108.0  769.87  5138.0  779.28
  5148.1  783.50  5178.2  792.30  5208.3  798.47  5248.4  808.37  5264.2  814.30
#Mann=3,-1,0
  4703.3    0.12       0  5005.5    0.05       0  5009.8    0.12       0
Bank Sta=5005.5,5009.8
Exp/Cntr=0.3,0.1

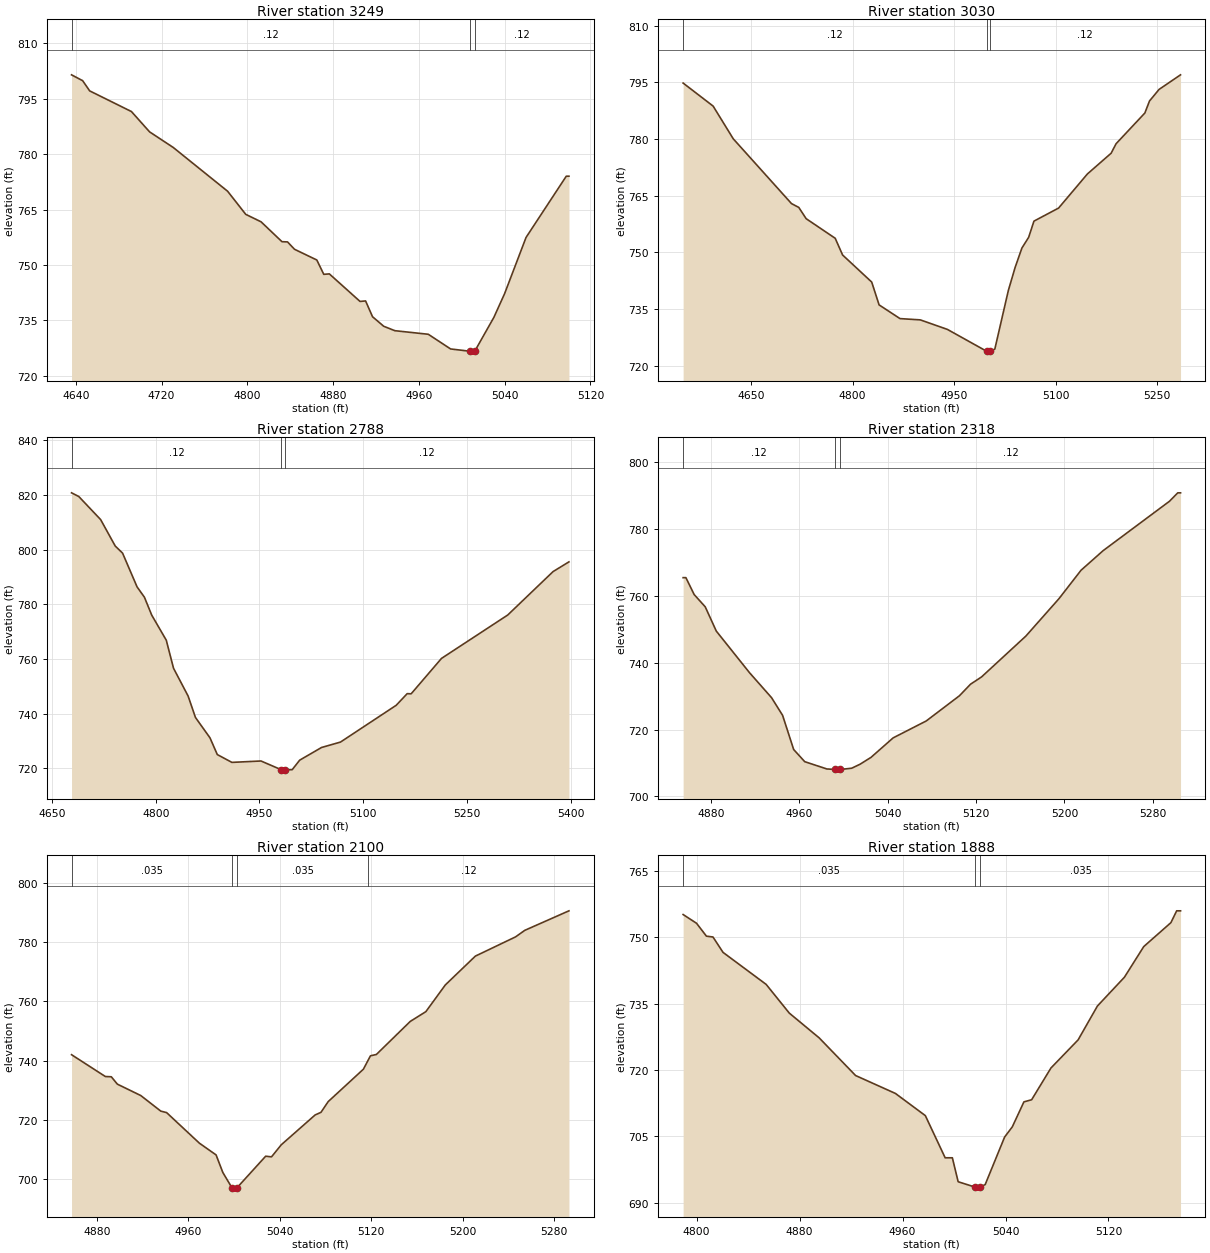
Type RM Length L Ch R = 1,3249,219,219,219
BEGIN DESCRIPTION:
Guadalupe Tributary 12 7.0
END DESCRIPTION:
XS GIS Cut Line= 3
      2233975.01     13833024.96      2234075.00     13832675.00
      2234075.00     13832574.96
#Sta/Elev= 30
  4636.0  801.46  4646.4  799.87  4652.9  797.12  4691.9  791.52  4708.8  786.03
  4730.9  781.80  4781.6  769.96  4798.5  763.71  4812.8  761.69  4832.3  756.31
  4837.5  756.25  4844.0  754.26  4864.8  751.36  4871.3  747.48  4876.5  747.60
  4905.1  740.15  4910.3  740.28  4916.8  736.00  4927.2  733.43  4937.6  732.23
  4968.8  731.26  4989.6  727.29  5007.8  726.66  5008.1  726.16  5012.1  726.66
  5030.0  735.85  5040.0  742.27  5060.0  757.47  5097.5  774.03  5100.0  774.03
#Mann=3,-1,0
  4636.0    0.12       0  5007.8    0.05       0  5012.1    0.12       0
Bank Sta=5007.8,5012.1
Exp/Cntr=0.3,0.1

Type RM Length L Ch R = 1,3030,242,242,242
BEGIN DESCRIPTION:
A19128
END DESCRIPTION:
XS GIS Cut Line= 4
      2234184.49     13833103.57      2234297.35     13832821.43
      2234293.01     13832604.41      2234146.30     13832449.07
#Sta/Elev= 30
  4549.7  794.81  4594.0  788.71  4623.7  780.06  4709.7  762.91  4720.5  761.89
  4731.4  758.91  4774.3  753.72  4785.2  749.30  4828.2  742.13  4839.1  736.09
  4870.0  732.46  4900.0  732.12  4940.0  729.60  4997.9  723.82  4998.2  723.32
  5002.2  723.82  5010.0  724.37  5030.0  739.91  5040.0  746.00  5050.0  751.13
  5060.0  753.98  5067.8  758.26  5104.2  761.72  5146.7  770.74  5181.8  776.24
  5189.1  778.75  5231.6  786.88  5238.5  790.07  5252.6  793.13  5284.3  796.99
#Mann=3,-1,0
  4549.7    0.12       0  4997.9    0.05       0  5002.2    0.12       0
Bank Sta=4997.9,5002.2
Exp/Cntr=0.3,0.1

Type RM Length L Ch R = 1,2788,470,470,470
BEGIN DESCRIPTION:
Guadalupe Tributary 12 6.0
END DESCRIPTION:
XS GIS Cut Line= 3
      2234824.97     13832724.99      2234525.00     13832625.00
      2234175.01     13832425.00
#Sta/Elev= 30
  4678.3  820.81  4688.8  819.46  4720.4  811.01  4741.5  801.33  4752.1  798.74
  4773.1  786.37  4783.7  782.60  4794.2  776.08  4815.3  766.87  4825.8  756.59
  4846.9  746.42  4857.5  738.58  4878.5  731.13  4889.1  725.00  4910.2  722.14
  4952.3  722.65  4981.7  719.44  4982.0  718.94  4986.3  719.44  4997.4  719.46
  5008.2  722.95  5039.8  727.59  5067.2  729.57  5147.8  743.04  5163.7  747.30
  5169.4  747.24  5213.3  760.20  5309.1  776.09  5374.6  791.97  5397.6  795.54
#Mann=3,-1,0
  4678.3    0.12       0  4981.7    0.05       0  4986.3    0.12       0
Bank Sta=4981.7,4986.3
Exp/Cntr=0.3,0.1

Type RM Length L Ch R = 1,2318,218,218,218
BEGIN DESCRIPTION:
Guadalupe Tributary 12 5.0
END DESCRIPTION:
XS GIS Cut Line= 3
      2234675.05     13832225.00      2234525.00     13832225.00
      2234225.05     13832225.00
#Sta/Elev= 30
  4855.0  765.42  4857.5  765.42  4865.0  760.36  4875.0  756.70  4885.0  749.45
  4915.0  737.03  4935.0  729.54  4945.0  724.25  4955.0  714.04  4965.0  710.41
  4985.0  708.23  4992.7  708.08  4993.0  707.58  4997.0  707.58  4997.3  708.08
  5007.5  708.45  5015.0  709.63  5025.0  711.70  5045.0  717.52  5075.0  722.59
  5105.0  730.12  5115.0  733.56  5125.0  735.75  5165.0  747.93  5195.0  759.13
  5215.0  767.64  5235.0  773.50  5295.0  788.26  5302.5  790.78  5305.0  790.78
#Mann=3,-1,0
  4855.0    0.12       0  4992.7    0.05       0  4997.3    0.12       0
Bank Sta=4992.7,4997.3
Exp/Cntr=0.3,0.1

Type RM Length L Ch R = 1,2100,212,212,212
BEGIN DESCRIPTION:
A19127
END DESCRIPTION:
XS GIS Cut Line= 2
      2234614.17     13831992.44      2234189.44     13832087.79
#Sta/Elev= 30
  4857.7  741.99  4887.3  734.63  4892.5  734.55  4897.8  732.06  4918.3  728.22
  4935.8  722.97  4940.9  722.47  4969.6  712.16  4984.2  708.20  4990.1  702.29
  4998.0  697.17  4998.3  696.67  5002.6  697.17  5027.6  707.77  5032.7  707.55
  5041.3  711.64  5070.9  721.68  5076.0  722.56  5082.3  726.17  5113.1  737.09
  5117.5  740.30  5119.3  741.61  5124.5  742.07  5154.1  753.20  5167.8  756.51
  5184.8  765.50  5211.1  775.22  5246.3  781.71  5254.4  783.92  5293.0  790.49
#Mann=4,-1,0
  4857.7   0.035       0  4998.0   0.035       0  5002.6   0.035       0
  5117.5    0.12       0
Bank Sta=4998,5002.6
Exp/Cntr=0.3,0.1

Type RM Length L Ch R = 1,1888,223,223,223
BEGIN DESCRIPTION:
Guadalupe Tributary 12 4.0
END DESCRIPTION:
XS GIS Cut Line= 3
      2234625.04     13831774.99      2234425.00     13831825.00
      2234274.98     13831925.01
#Sta/Elev= 30
  4789.5  755.15  4799.9  753.18  4807.6  750.26  4812.7  750.07  4820.5  746.59
  4854.0  739.35  4872.0  732.85  4895.2  727.25  4923.5  718.73  4954.5  714.67
  4977.7  709.66  4993.1  700.12  4998.7  700.12  5003.2  694.70  5015.9  693.53
  5016.2  693.03  5020.5  693.53  5024.2  694.06  5039.3  704.81  5045.3  707.13
  5054.3  712.77  5060.3  713.25  5075.3  720.43  5096.4  726.79  5111.4  734.45
  5132.4  740.97  5147.4  747.90  5168.5  753.31  5173.0  755.99  5176.0  755.99
#Mann=3,-1,0
  4789.5   0.035       0  5015.9   0.035       0  5020.5   0.035       0
Bank Sta=5015.9,5020.5
Exp/Cntr=0.3,0.1

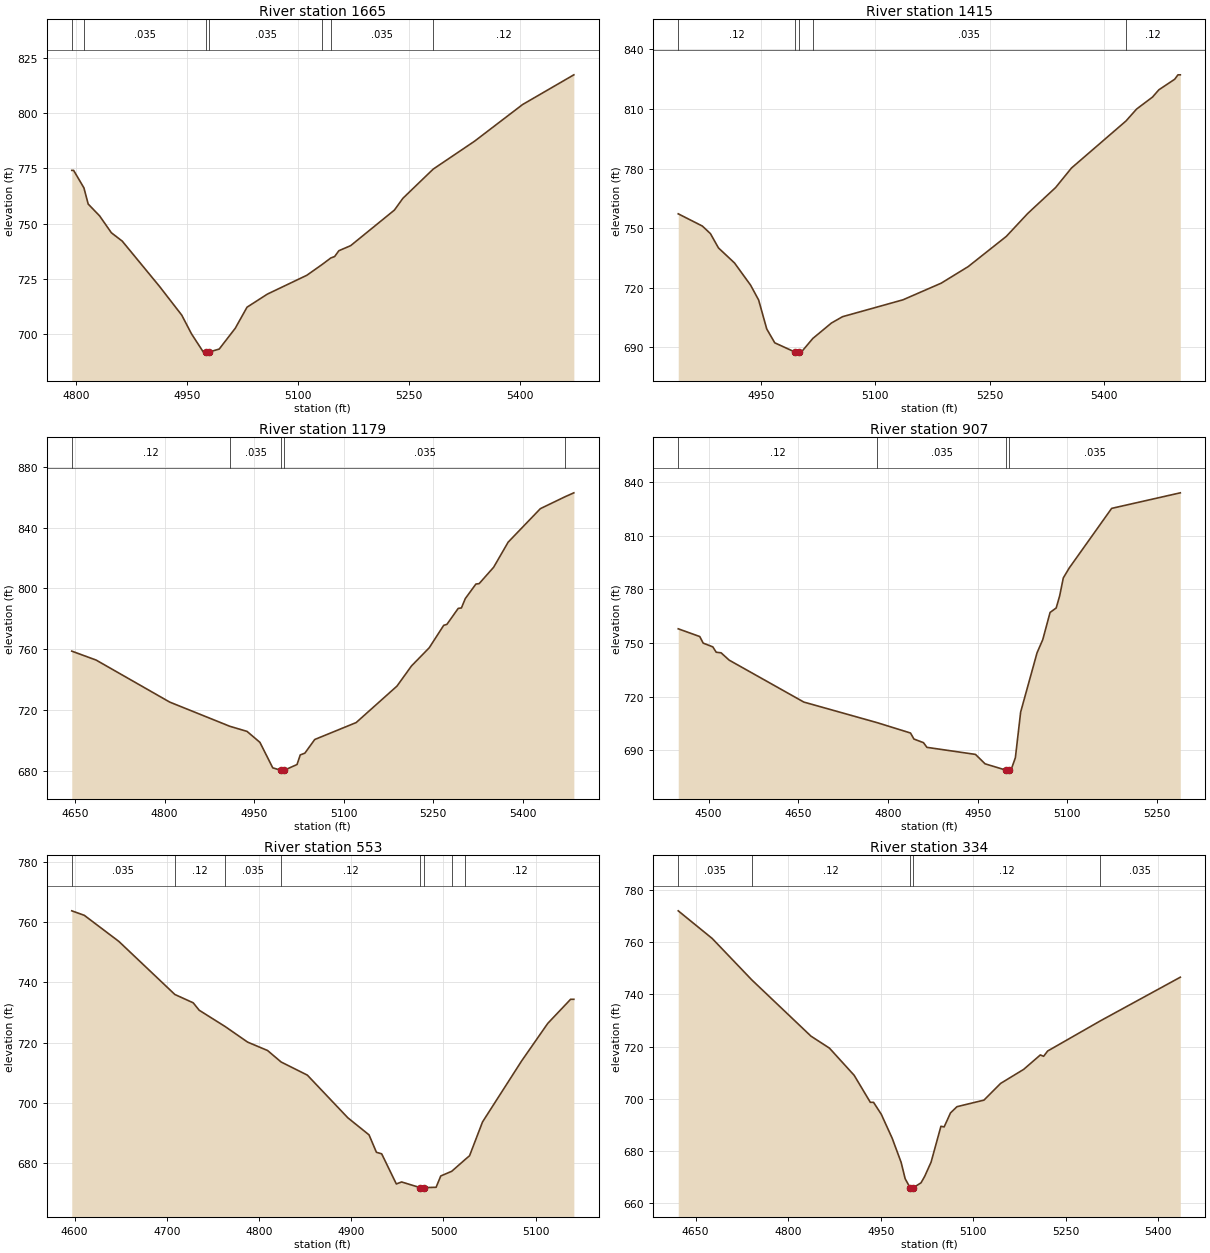
Type RM Length L Ch R = 1,1665,250,250,250
BEGIN DESCRIPTION:
A19126
END DESCRIPTION:
XS GIS Cut Line= 2
      2234514.34     13831532.38      2233924.08     13831866.57
#Sta/Elev= 30
  4794.2  774.07  4796.7  774.07  4810.6  766.19  4816.4  758.87  4831.8  753.53
  4847.7  745.90  4862.4  742.13  4912.6  721.75  4942.8  708.72  4955.9  700.31
  4971.8  692.12  4975.2  692.07  4975.5  691.57  4979.9  692.07  4993.4  693.41
  5015.1  702.81  5031.0  712.31  5058.4  718.20  5111.8  726.72  5132.3  731.55
  5144.2  734.53  5149.3  735.17  5155.1  737.81  5171.0  740.09  5230.1  756.15
  5241.6  761.48  5282.5  774.64  5338.3  787.22  5403.3  803.80  5472.5  817.20
#Mann=7,-1,0
  4794.2    0.12       0  4810.6   0.035       0  4975.2   0.035       0
  4979.9   0.035       0  5132.3    0.12       0  5144.2   0.035       0
  5282.5    0.12       0
Bank Sta=4975.2,4979.9
Exp/Cntr=0.3,0.1

Type RM Length L Ch R = 1,1415,236,236,236
BEGIN DESCRIPTION:
Guadalupe Tributary 12 3.0
END DESCRIPTION:
XS GIS Cut Line= 3
      2234375.03     13831374.99      2234225.00     13831425.00
      2233825.03     13831724.98
#Sta/Elev= 30
  4841.9  757.16  4873.5  751.00  4884.1  747.18  4894.6  739.99  4915.7  732.38
  4936.8  721.18  4947.3  713.72  4957.9  699.15  4968.4  692.15  4995.1  687.45
  4995.4  686.95  4999.8  687.45  5003.2  687.45  5018.3  694.34  5042.7  702.12
  5057.3  705.32  5136.5  713.82  5186.5  722.19  5221.9  730.54  5271.9  745.77
  5300.0  757.34  5336.5  770.38  5357.3  780.22  5428.8  803.95  5442.7  809.96
  5463.6  816.01  5471.9  819.67  5492.7  825.00  5496.9  827.21  5500.0  827.21
#Mann=5,-1,0
  4841.9    0.12       0  4995.1    0.05       0  4999.8    0.12       0
  5018.3   0.035       0  5428.8    0.12       0
Bank Sta=4995.1,4999.8
Exp/Cntr=0.3,0.1

Type RM Length L Ch R = 1,1179,272,272,272
BEGIN DESCRIPTION:
A19125
END DESCRIPTION:
XS GIS Cut Line= 3
      2234397.14     13831345.72      2234141.10     13831241.57
      2233615.93     13831449.90
#Sta/Elev= 30
  4644.5  758.78  4685.4  752.88  4808.7  725.23  4909.3  709.33  4938.2  705.96
  4959.8  698.76  4981.3  681.98  4995.4  680.31  4995.7  679.81  5000.1  680.31
  5022.0  684.16  5027.4  690.48  5035.1  691.62  5051.7  700.63  5121.1  711.77
  5189.5  735.76  5213.8  749.02  5243.5  760.96  5267.8  775.75  5273.2  776.40
  5292.1  786.89  5297.5  787.20  5304.0  793.37  5321.8  802.93  5327.2  803.20
  5351.5  813.97  5375.8  830.48  5429.8  852.53  5471.0  860.34  5485.9  862.95
#Mann=5,-1,0
  4644.5    0.12       0  4909.3   0.035       0  4995.4   0.035       0
  5000.1   0.035       0  5471.0    0.12       0
Bank Sta=4995.4,5000.1
Exp/Cntr=0.3,0.1

Type RM Length L Ch R = 1,907,354,354,354
BEGIN DESCRIPTION:
A19124
END DESCRIPTION:
XS GIS Cut Line= 2
      2234427.56     13831319.69      2233694.09     13830911.73
#Sta/Elev= 30
  4449.4  757.95  4485.4  753.61  4491.1  749.92  4507.2  747.83  4512.9  744.81
  4521.0  744.50  4534.6  740.38  4659.3  716.89  4781.8  705.36  4837.7  699.54
  4843.4  696.17  4859.4  694.12  4865.1  691.51  4946.3  687.55  4962.3  682.28
  4997.7  678.68  4998.0  678.18  5002.4  678.68  5005.8  678.91  5013.0  685.72
  5021.8  711.28  5049.2  744.48  5058.8  751.91  5071.0  767.12  5081.2  769.62
  5087.0  776.38  5093.1  786.47  5103.0  792.02  5173.9  825.44  5288.7  834.16
#Mann=4,-1,0
  4449.4    0.12       0  4781.8   0.035       0  4997.7   0.035       0
  5002.4   0.035       0
Bank Sta=4997.7,5002.4
Exp/Cntr=0.3,0.1

Type RM Length L Ch R = 1,553,219,219,219
BEGIN DESCRIPTION:
Guadalupe Tributary 12 1.0
END DESCRIPTION:
XS GIS Cut Line= 3
      2234474.98     13831324.96      2234275.00     13830975.00
      2234174.99     13830874.99
#Sta/Elev= 30
  4596.9  763.70  4610.5  762.21  4648.0  753.55  4708.7  735.96  4728.6  733.20
  4735.1  730.74  4763.4  725.30  4787.6  720.17  4809.2  717.39  4824.0  713.56
  4852.4  709.22  4896.3  695.07  4919.3  689.41  4927.3  683.63  4933.0  683.13
  4948.9  673.13  4954.6  673.80  4974.6  671.92  4974.9  671.42  4979.3  671.92
  4992.0  672.03  4997.1  675.79  5009.0  677.34  5023.5  681.24  5028.3  682.49
  5042.4  693.72  5084.8  713.94  5113.1  726.37  5137.9  734.37  5141.4  734.37
#Mann=8,-1,0
  4596.9   0.035       0  4708.7    0.12       0  4763.4   0.035       0
  4824.0    0.12       0  4974.6    0.05       0  4979.3    0.12       0
  5009.0   0.035       0  5023.5    0.12       0
Bank Sta=4974.6,4979.3
Exp/Cntr=0.3,0.1

Type RM Length L Ch R = 1,334,246,246,246
BEGIN DESCRIPTION:
A19123
END DESCRIPTION:
XS GIS Cut Line= 3
      2234518.70     13831350.10      2234514.36     13831037.57
      2234362.44     13830560.12
#Sta/Elev= 30
  4622.0  772.07  4677.1  761.45  4741.3  745.56  4837.1  724.01  4867.1  719.40
  4907.1  708.99  4933.3  698.63  4938.5  698.63  4951.0  694.06  4968.7  684.86
  4983.2  675.61  4989.7  669.35  4997.8  665.84  4998.2  665.34  5002.6  665.84
  5015.4  667.75  5021.2  670.16  5031.7  675.67  5047.7  689.44  5052.9  689.20
  5063.2  694.57  5073.7  696.96  5117.4  699.47  5144.4  705.88  5181.8  711.27
  5208.8  716.80  5214.1  716.28  5220.6  718.30  5306.2  729.89  5435.6  746.61
#Mann=5,-1,0
  4622.0   0.035       0  4741.3    0.12       0  4997.8    0.05       0
  5002.6    0.12       0  5306.2   0.035       0
Bank Sta=4997.8,5002.6
Exp/Cntr=0.3,0.1

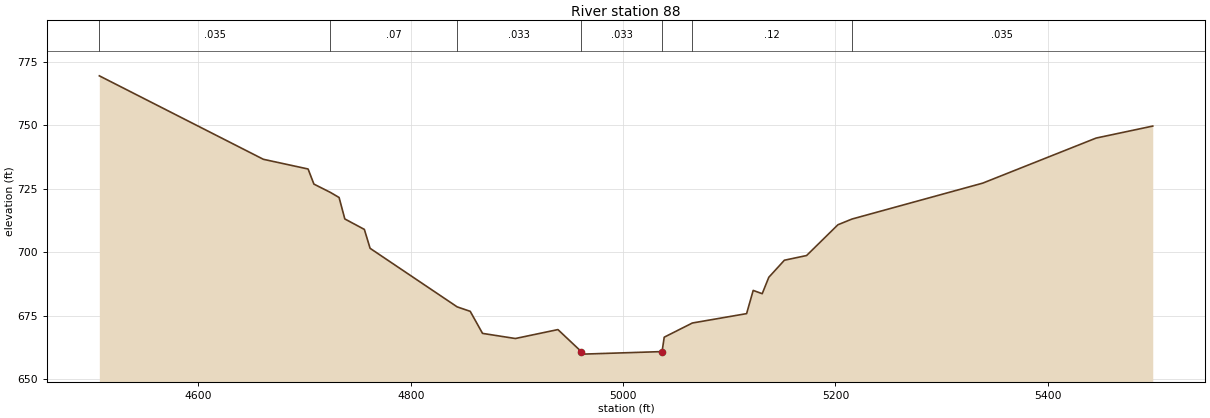
Type RM Length L Ch R = 1,88,0,0,0
BEGIN DESCRIPTION:
A19122
END DESCRIPTION:
XS GIS Cut Line= 4
      2234562.11     13831337.05      2234709.67     13830985.49
      2234696.65     13830768.48      2234467.58     13830448.63
#Sta/Elev= 30
  4506.7  769.55  4661.2  736.66  4703.3  732.84  4708.8  726.89  4724.4  723.60
  4732.5  721.61  4737.9  713.16  4756.3  709.04  4761.7  701.59  4843.7  678.52
  4856.0  676.76  4867.6  668.07  4898.5  666.05  4938.6  669.57  4960.6  660.90
  4962.1  659.90  5036.7  660.90  5038.7  666.57  5065.2  672.16  5116.3  675.86
  5122.5  685.00  5131.0  683.71  5137.2  690.17  5151.9  696.90  5172.8  698.75
  5202.3  710.87  5215.6  713.13  5338.6  727.26  5445.5  745.03  5498.8  749.75
#Mann=7,-1,0
  4506.7   0.035       0  4724.4    0.07       0  4843.7   0.033       0
  4960.6   0.033       0  5036.7   0.033       0  5065.2    0.12       0
  5215.6   0.035       0
Bank Sta=4960.6,5036.7
Exp/Cntr=0.3,0.1

Chan Stop Cuts=-1