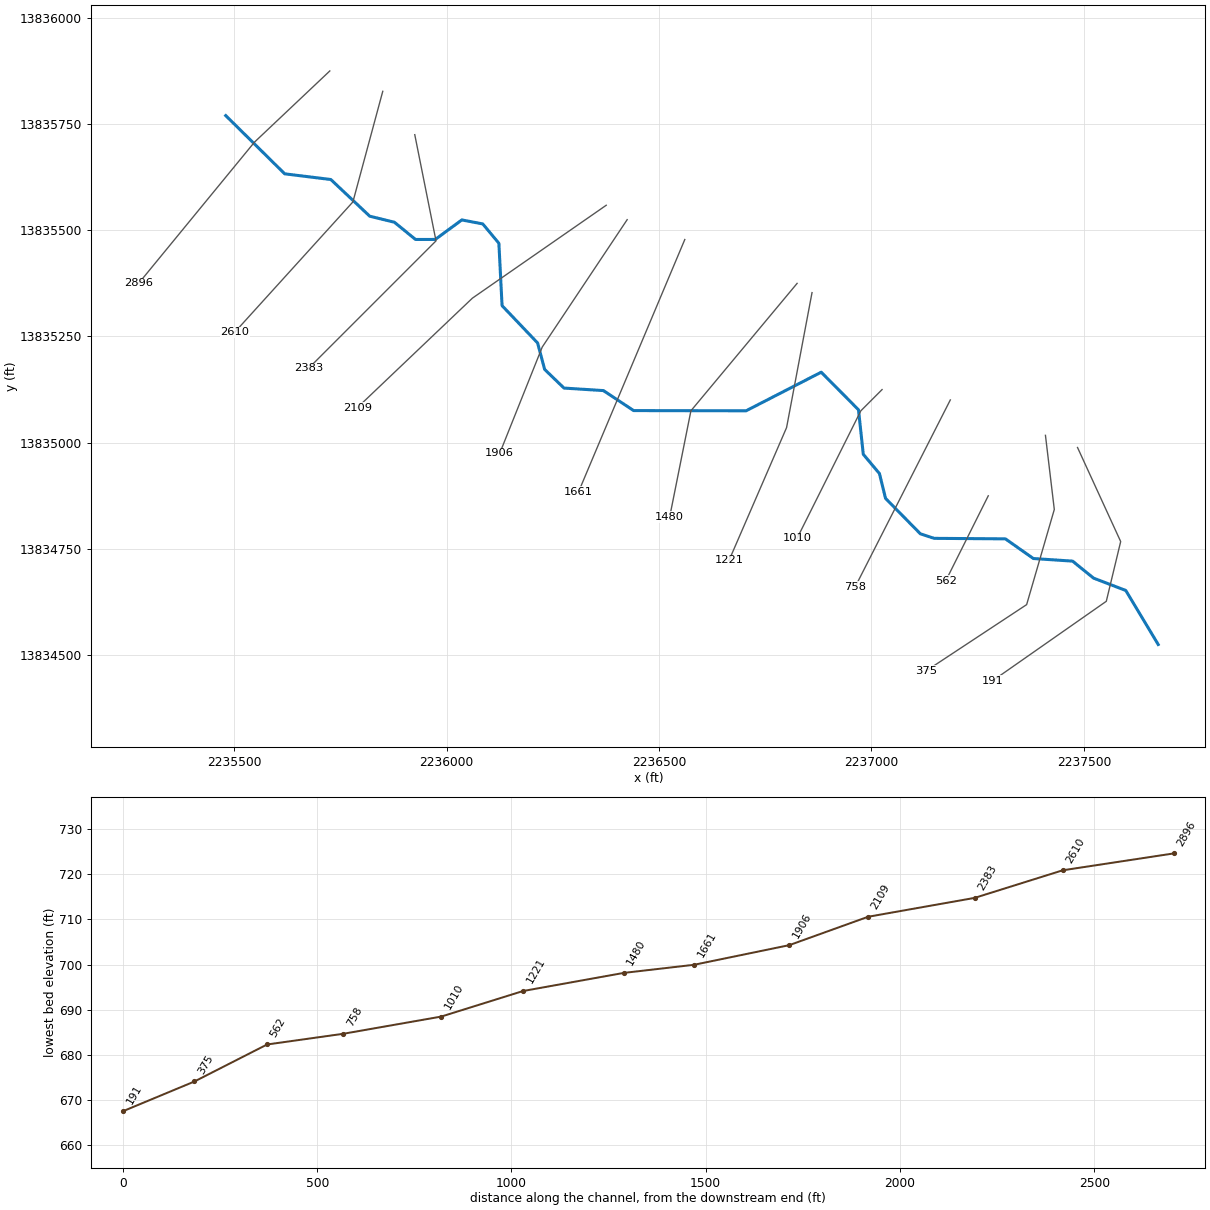
--- Guadalupe Tributary 16.prj (project) ---

Proj Title=Guadalupe Tributary 16 Base Level Engineering
Current Plan=p01
Default Exp/Contr=0.3,0.1
English Units
Geom File=g01
Flow File=f01
Plan File=p01
BEGIN DESCRIPTION:
Guadalupe Tributary 16
END DESCRIPTION:

--- Guadalupe Tributary 16.p01 (plan) ---

Plan Title=Multiple Run
Short Identifier=Multiple
Geom File=g01
Flow File=f01
Subcritical Flow
K Sum by GR= 0
Std Step Tol= 0.01
Critical Tol= 0.01
Num of Std Step Trials= 20
Max Error Tol= 0.3
Flow Tol Ratio= 0.001
Split Flow NTrial= 30
Split Flow Tol= 0.02
Split Flow Ratio= 0.02
Log Output Level= 0
Friction Slope Method= 1
Unsteady Friction Slope Method= 2
Unsteady Bridges Friction Slope Method= 1
Parabolic Critical Depth
Global Vel Dist=  1 , 1 , 1
Global Log Level= 0
CheckData=True
Encroach Param= -1, 0, 0, 0
BEGIN DESCRIPTION:
Multiple Run
END DESCRIPTION:

--- Guadalupe Tributary 16.f01 (steady flow) ---

Flow Title=Multiple
Number of Profiles=7
Profile Names=10-year,25-year,50-year,1pct_min,100-year,1pct_plu,500-year
River Rch & RM= Guadalupe Tribut,Reach-1,2896
    1328    2288    3218    2194    4378    8735    8012
Boundary for River Rch & Prof#=Guadalupe Tribut,Reach-1,1
Up Type=0
Dn Type=3
Dn Slope=0.005
Boundary for River Rch & Prof#=Guadalupe Tribut,Reach-1,2
Up Type=0
Dn Type=3
Dn Slope=0.005
Boundary for River Rch & Prof#=Guadalupe Tribut,Reach-1,3
Up Type=0
Dn Type=3
Dn Slope=0.005
Boundary for River Rch & Prof#=Guadalupe Tribut,Reach-1,4
Up Type=0
Dn Type=3
Dn Slope=0.005
Boundary for River Rch & Prof#=Guadalupe Tribut,Reach-1,5
Up Type=0
Dn Type=3
Dn Slope=0.005
Boundary for River Rch & Prof#=Guadalupe Tribut,Reach-1,6
Up Type=0
Dn Type=3
Dn Slope=0.005
Boundary for River Rch & Prof#=Guadalupe Tribut,Reach-1,7
Up Type=0
Dn Type=3
Dn Slope=0.005

--- Guadalupe Tributary 16.g01 (geometry) ---

Geom Title=Existing Conditions

River Reach=Guadalupe Tribut,Reach-1
Reach XY= 30
      2235480.09     13835769.91      2235618.83     13835632.86
      2235727.42     13835619.46      2235818.95     13835533.16
      2235877.19     13835518.82      2235926.72     13835478.34
      2235973.28     13835478.40      2236035.75     13835524.28
      2236085.06     13835514.97      2236123.01     13835469.37
      2236130.48     13835322.56      2236214.19     13835234.65
      2236230.74     13835172.43      2236276.28     13835128.52
      2236369.02     13835122.64      2236440.22     13835075.52
      2236704.97     13835075.06      2236881.75     13835165.90
      2236969.48     13835077.46      2236980.77     13834972.68
      2237018.86     13834927.17      2237033.13     13834868.92
      2237115.18     13834785.47      2237147.64     13834774.80
      2237315.34     13834773.62      2237380.98     13834727.36
      2237473.42     13834721.18      2237522.84     13834681.14
      2237598.66     13834652.15      2237675.00     13834525.00

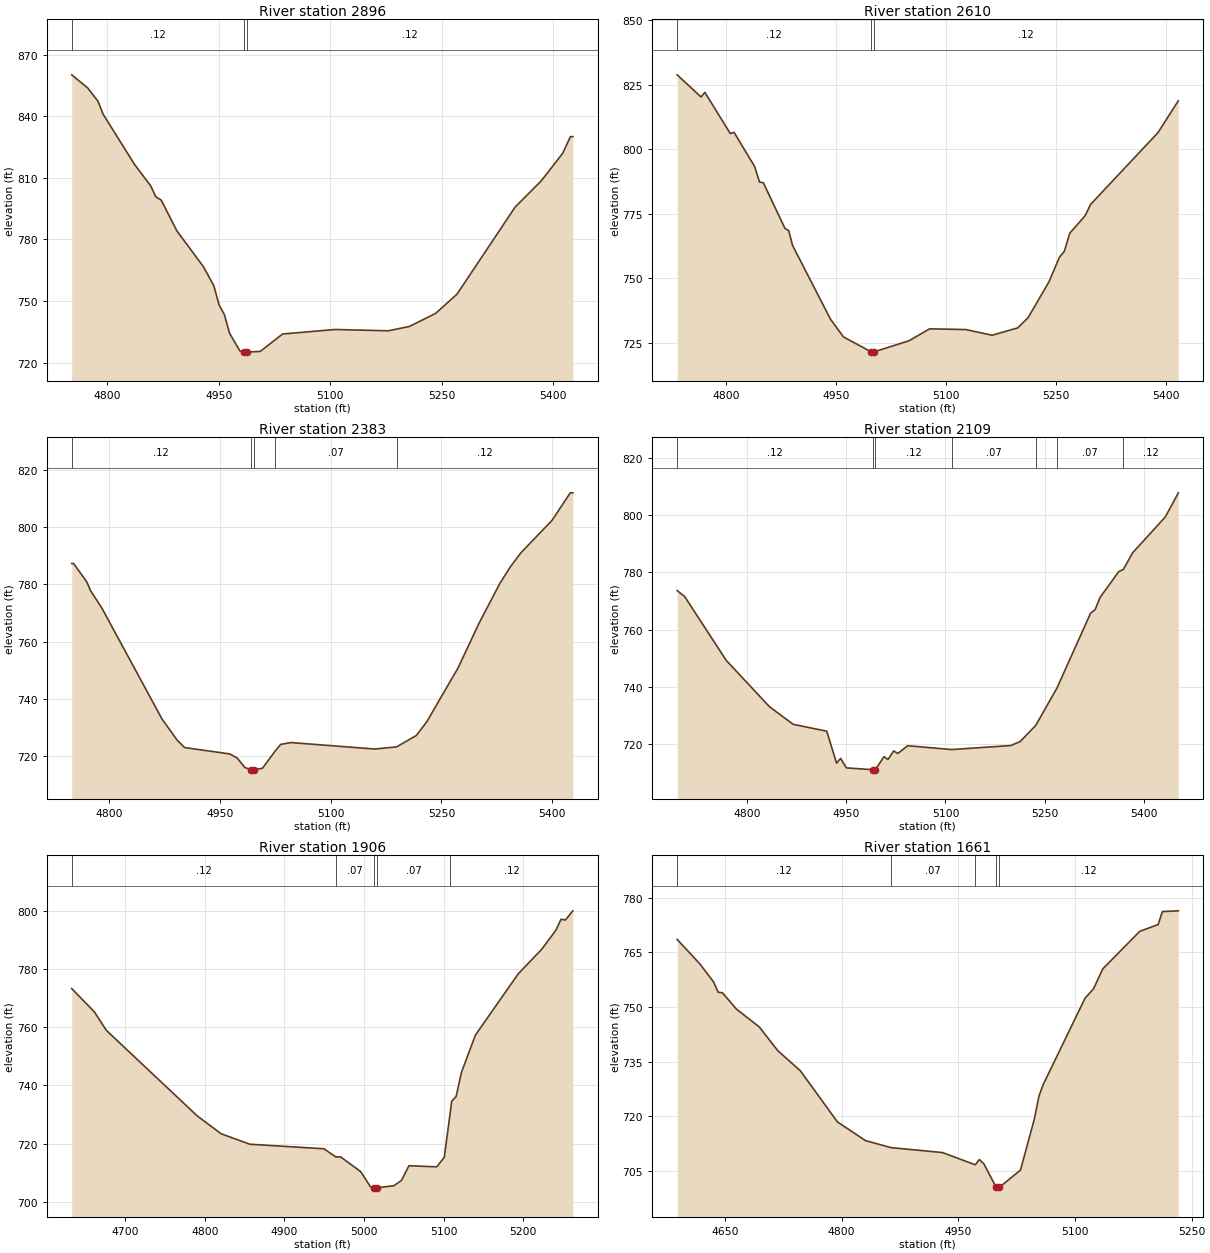
Type RM Length L Ch R = 1,2896,286,286,286
BEGIN DESCRIPTION:
Guadalupe Tributary 16 6.0
END DESCRIPTION:
XS GIS Cut Line= 3
      2235725.02     13835875.02      2235547.60     13835707.35
      2235274.97     13835374.97
#Sta/Elev= 30
  4752.3  860.18  4773.6  853.84  4787.7  847.26  4794.6  840.97  4837.1  816.36
  4858.5  806.13  4865.4  800.77  4872.7  799.14  4893.7  784.19  4929.3  766.80
  4943.5  757.41  4950.4  748.16  4957.6  743.42  4964.5  734.39  4978.7  725.57
  4984.0  725.13  4984.2  724.63  4988.0  725.13  5005.9  725.47  5035.9  733.94
  5106.2  736.14  5178.0  735.51  5206.4  737.61  5241.8  744.00  5270.5  753.36
  5348.7  795.80  5383.9  808.59  5412.6  821.97  5423.0  830.08  5426.3  830.08
#Mann=3,-1,0
  4752.3    0.12       0  4984.0    0.05       0  4988.0    0.12       0
Bank Sta=4984,4988
Exp/Cntr=0.3,0.1

Type RM Length L Ch R = 1,2610,227,227,227
BEGIN DESCRIPTION:
A19172
END DESCRIPTION:
XS GIS Cut Line= 3
      2235849.67     13835827.10      2235779.37     13835566.73
      2235501.00     13835259.74
#Sta/Elev= 30
  4733.4  828.83  4766.0  820.24  4771.2  822.04  4805.9  806.07  4811.1  806.50
  4839.2  793.25  4845.8  787.24  4851.0  786.99  4880.5  769.29  4885.7  768.39
  4890.9  762.68  4942.7  734.05  4960.3  727.20  4998.2  721.39  4998.4  720.89
  5002.2  721.39  5049.7  725.66  5078.1  730.32  5127.5  730.03  5163.3  727.83
  5198.4  730.69  5212.6  734.70  5241.0  748.58  5255.2  758.10  5261.9  760.39
  5269.4  767.42  5290.3  774.21  5297.8  778.59  5389.7  806.40  5417.5  818.76
#Mann=3,-1,0
  4733.4    0.12       0  4998.2    0.05       0  5002.2    0.12       0
Bank Sta=4998.2,5002.2
Exp/Cntr=0.3,0.1

Type RM Length L Ch R = 1,2383,274,274,274
BEGIN DESCRIPTION:
Guadalupe Tributary 16 5.0
END DESCRIPTION:
XS GIS Cut Line= 3
      2235925.00     13835725.01      2235975.00     13835475.00
      2235675.02     13835175.02
#Sta/Elev= 30
  4749.0  787.30  4751.6  787.30  4769.4  780.90  4774.5  777.84  4789.8  771.76
  4871.4  732.96  4891.8  725.64  4902.0  723.00  4963.2  720.78  4973.4  719.31
  4983.6  716.05  4991.8  715.27  4992.0  714.77  4995.8  715.27  5007.5  715.77
  5023.9  721.51  5032.2  724.11  5046.4  724.75  5159.5  722.49  5189.2  723.23
  5216.1  727.24  5230.2  732.00  5272.7  750.88  5300.9  766.37  5329.2  780.33
  5343.4  786.11  5357.5  790.98  5399.9  802.36  5424.7  812.00  5428.2  812.00
#Mann=5,-1,0
  4749.0    0.12       0  4991.8    0.05       0  4995.8    0.12       0
  5023.9    0.07       0  5189.2    0.12       0
Bank Sta=4991.8,4995.8
Exp/Cntr=0.3,0.1

Type RM Length L Ch R = 1,2109,203,203,203
BEGIN DESCRIPTION:
A19171
END DESCRIPTION:
XS GIS Cut Line= 3
      2236375.69     13835558.89      2236060.62     13835340.16
      2235789.91     13835082.47
#Sta/Elev= 30
  4694.6  773.63  4705.9  771.55  4768.7  749.27  4834.2  733.05  4870.0  726.92
  4920.6  724.54  4935.5  713.38  4941.6  715.05  4950.3  711.72  4990.2  711.09
  4990.5  710.59  4994.2  711.09  5007.1  715.63  5013.2  714.68  5021.9  717.66
  5028.0  716.75  5042.9  719.46  5109.6  718.12  5198.8  719.53  5213.0  720.93
  5236.5  726.57  5268.7  739.68  5319.3  765.73  5326.2  766.95  5333.5  771.17
  5361.8  780.23  5368.8  781.01  5382.9  786.82  5432.2  799.31  5451.9  807.75
#Mann=7,-1,0
  4694.6    0.12       0  4990.2    0.05       0  4994.2    0.12       0
  5109.6    0.07       0  5236.5    0.12       0  5268.7    0.07       0
  5368.8    0.12       0
Bank Sta=4990.2,4994.2
Exp/Cntr=0.3,0.1

Type RM Length L Ch R = 1,1906,245,245,245
BEGIN DESCRIPTION:
Guadalupe Tributary 16 4.0
END DESCRIPTION:
XS GIS Cut Line= 3
      2236424.98     13835524.97      2236225.00     13835225.00
      2236124.99     13834974.98
#Sta/Elev= 30
  4632.7  773.34  4661.2  765.32  4676.2  758.97  4790.4  729.52  4820.5  723.36
  4856.5  719.76  4949.7  718.19  4964.5  715.40  4970.7  715.38  4995.9  710.33
  5008.0  705.16  5012.8  704.80  5013.0  704.30  5016.8  704.80  5037.6  705.46
  5047.1  707.32  5056.5  712.35  5091.5  711.98  5100.9  715.26  5108.3  730.48
  5110.3  734.59  5115.7  736.14  5122.5  744.51  5140.0  757.33  5193.8  778.41
  5223.4  786.90  5240.9  793.34  5247.7  797.23  5253.1  796.96  5262.5  800.12
#Mann=5,-1,0
  4632.7    0.12       0  4964.5    0.07       0  5012.8    0.05       0
  5016.8    0.07       0  5108.3    0.12       0
Bank Sta=5012.8,5016.8
Exp/Cntr=0.3,0.1

Type RM Length L Ch R = 1,1661,181,181,181
BEGIN DESCRIPTION:
A19170
END DESCRIPTION:
XS GIS Cut Line= 2
      2236560.62     13835478.19      2236310.63     13834884.47
#Sta/Elev= 30
  4588.6  768.59  4617.6  761.90  4635.5  756.88  4641.3  754.06  4646.7  753.94
  4665.0  749.40  4694.2  744.53  4717.9  738.02  4747.1  732.44  4794.6  718.43
  4830.8  713.28  4863.7  711.35  4929.5  710.01  4971.8  706.64  4977.0  708.07
  4982.7  706.96  4998.7  700.45  4999.0  699.95  5002.7  700.45  5029.9  705.18
  5047.8  719.26  5053.6  725.47  5059.0  728.63  5112.9  752.44  5123.7  754.99
  5135.7  760.49  5183.1  770.79  5206.9  772.68  5212.3  776.24  5232.8  776.45
#Mann=5,-1,0
  4588.6    0.12       0  4863.7    0.07       0  4971.8    0.12       0
  4998.7    0.05       0  5002.7    0.12       0
Bank Sta=4998.7,5002.7
Exp/Cntr=0.3,0.1

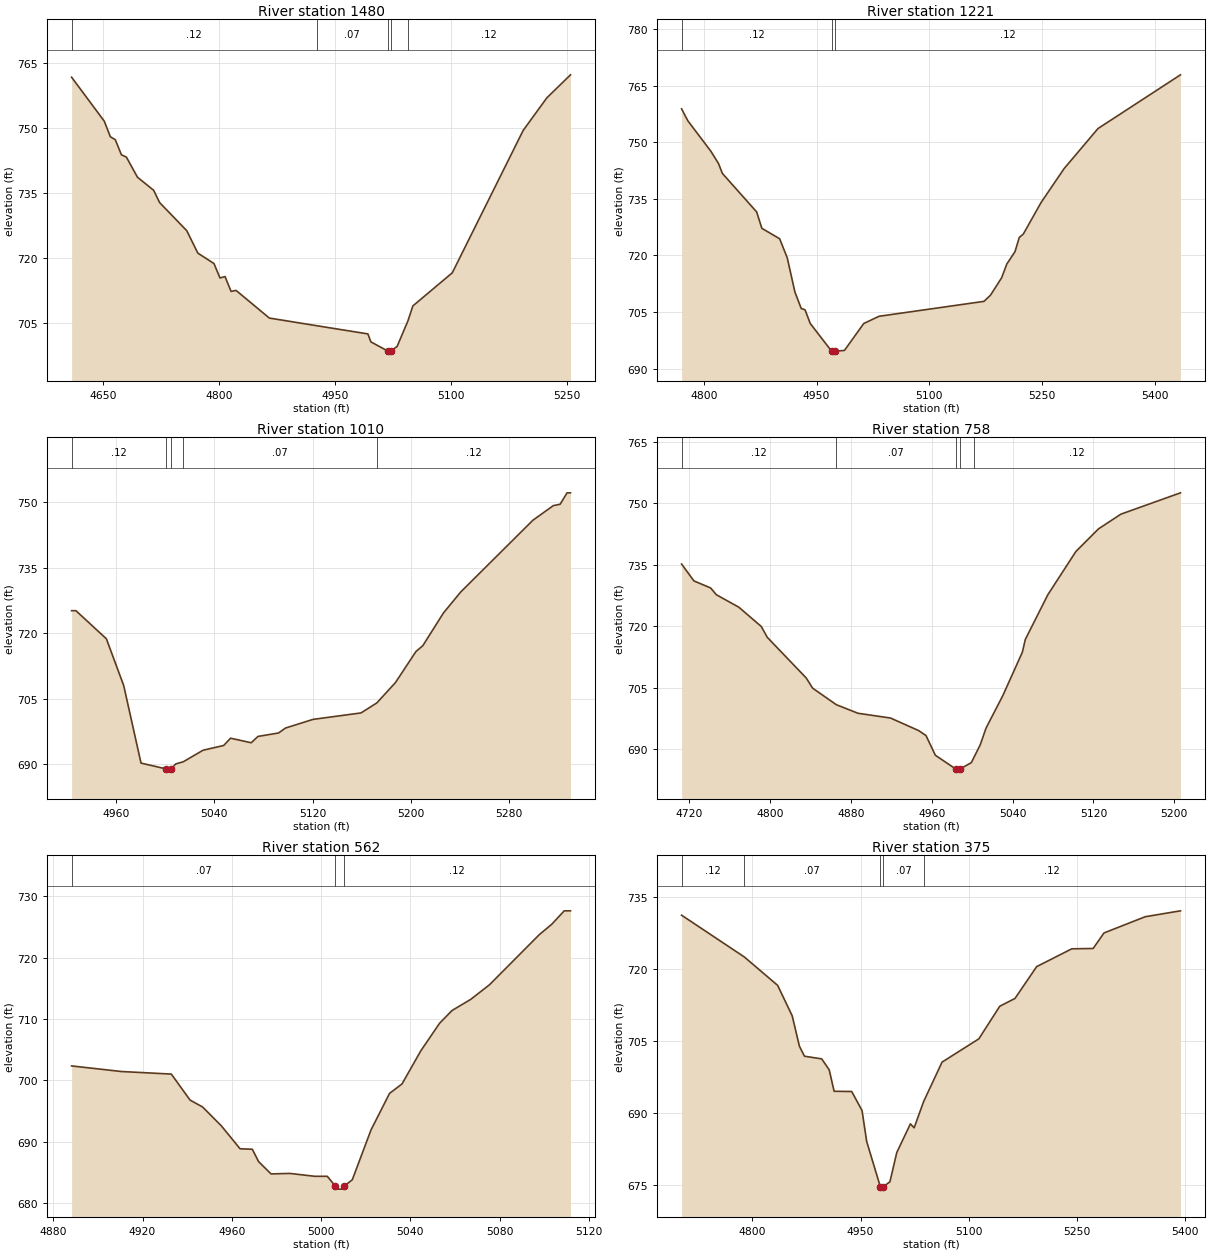
Type RM Length L Ch R = 1,1480,259,259,259
BEGIN DESCRIPTION:
Guadalupe Tributary 16 3.0
END DESCRIPTION:
XS GIS Cut Line= 3
      2236824.98     13835374.98      2236575.00     13835075.00
      2236525.01     13834825.03
#Sta/Elev= 30
  4609.5  761.73  4651.8  751.59  4659.6  748.02  4666.1  747.31  4673.9  743.87
  4680.4  743.31  4694.7  738.69  4715.6  735.68  4723.4  732.84  4758.5  726.36
  4772.8  721.20  4793.7  718.79  4801.5  715.46  4808.0  715.80  4815.8  712.37
  4822.3  712.60  4865.3  706.23  4926.8  704.46  4992.8  702.58  4996.7  700.74
  5018.4  698.65  5018.6  698.15  5022.4  698.65  5030.6  699.68  5044.7  705.63
  5051.0  709.03  5102.0  716.66  5193.7  749.47  5224.3  756.97  5254.9  762.28
#Mann=5,-1,0
  4609.5    0.12       0  4926.8    0.07       0  5018.4    0.05       0
  5022.4    0.07       0  5044.7    0.12       0
Bank Sta=5018.4,5022.4
Exp/Cntr=0.3,0.1

Type RM Length L Ch R = 1,1221,211,211,211
BEGIN DESCRIPTION:
A19169
END DESCRIPTION:
XS GIS Cut Line= 3
      2236860.10     13835353.21      2236800.20     13835035.48
      2236664.79     13834722.98
#Sta/Elev= 30
  4770.4  758.83  4778.8  755.65  4809.3  747.63  4819.5  744.36  4824.7  741.73
  4870.3  731.54  4877.2  727.20  4900.9  724.43  4911.0  719.38  4921.2  710.33
  4929.6  705.96  4934.7  705.61  4941.6  702.00  4970.1  694.64  4970.3  694.14
  4974.1  694.64  4987.1  694.85  5012.8  701.98  5033.2  703.90  5172.8  707.85
  5181.4  709.47  5196.3  714.09  5203.2  717.74  5214.1  721.02  5219.8  724.77
  5225.2  725.69  5248.7  734.00  5279.5  743.03  5324.6  753.63  5434.3  767.85
#Mann=3,-1,0
  4770.4    0.12       0  4970.1    0.05       0  4974.1    0.12       0
Bank Sta=4970.1,4974.1
Exp/Cntr=0.3,0.1

Type RM Length L Ch R = 1,1010,252,252,252
BEGIN DESCRIPTION:
Guadalupe Tributary 16 2.0
END DESCRIPTION:
XS GIS Cut Line= 3
      2237024.99     13835124.99      2236975.00     13835075.00
      2236825.00     13834775.00
#Sta/Elev= 30
  4923.8  725.19  4927.3  725.19  4952.1  718.76  4966.2  708.07  4980.3  690.31
  5000.9  688.97  5001.1  688.47  5004.9  688.97  5008.5  690.11  5014.7  690.61
  5030.8  693.25  5047.6  694.34  5053.2  696.01  5070.0  694.96  5075.5  696.41
  5092.3  697.20  5097.9  698.33  5120.3  700.31  5159.4  701.79  5172.3  704.09
  5187.4  708.73  5204.1  715.84  5209.7  717.18  5226.5  724.67  5240.5  729.45
  5299.2  745.86  5315.9  749.23  5321.5  749.55  5327.1  752.16  5329.9  752.16
#Mann=5,-1,0
  4923.8    0.12       0  5000.9    0.05       0  5004.9    0.12       0
  5014.7    0.07       0  5172.3    0.12       0
Bank Sta=5000.9,5004.9
Exp/Cntr=0.3,0.1

Type RM Length L Ch R = 1,758,196,196,196
BEGIN DESCRIPTION:
A19168
END DESCRIPTION:
XS GIS Cut Line= 2
      2237185.63     13835100.61      2236961.68     13834660.52
#Sta/Elev= 30
  4712.3  735.20  4724.5  731.08  4741.0  729.37  4746.7  727.71  4769.0  724.66
  4791.2  719.95  4797.1  717.32  4835.7  707.38  4842.0  704.91  4865.4  700.88
  4886.9  698.78  4919.1  697.62  4946.9  694.56  4954.2  693.35  4963.5  688.53
  4983.8  685.16  4984.0  684.66  4987.8  685.16  4999.1  686.74  5001.9  688.12
  5008.0  691.14  5013.6  695.14  5030.3  703.11  5049.6  713.69  5052.5  716.78
  5074.8  727.70  5102.6  738.27  5124.9  743.77  5147.1  747.37  5206.1  752.58
#Mann=5,-1,0
  4712.3    0.12       0  4865.4    0.07       0  4983.8    0.05       0
  4987.8    0.07       0  5001.9    0.12       0
Bank Sta=4983.8,4987.8
Exp/Cntr=0.3,0.1

Type RM Length L Ch R = 1,562,187,187,187
BEGIN DESCRIPTION:
Guadalupe Tributary 16 1.0
END DESCRIPTION:
XS GIS Cut Line= 3
      2237274.99     13834874.99      2237225.00     13834775.00
      2237175.00     13834674.99
#Sta/Elev= 30
  4888.2  702.37  4910.5  701.46  4932.9  701.04  4941.3  696.80  4946.9  695.68
  4955.3  692.61  4963.7  688.87  4969.2  688.79  4972.0  686.78  4977.6  684.77
  4986.0  684.85  4997.2  684.38  5002.8  684.38  5006.4  682.79  5006.6  682.29
  5010.1  682.29  5010.4  682.79  5014.0  683.81  5022.4  691.94  5030.7  697.89
  5036.3  699.44  5044.7  704.82  5053.1  709.31  5058.7  711.40  5067.1  713.22
  5075.5  715.60  5097.8  723.76  5103.4  725.46  5109.0  727.65  5111.8  727.65
#Mann=3,-1,0
  4888.2    0.07       0  5006.4    0.05       0  5010.4    0.12       0
Bank Sta=5006.4,5010.4
Exp/Cntr=0.3,0.1

Type RM Length L Ch R = 1,375,184,184,184
BEGIN DESCRIPTION:
A19167
END DESCRIPTION:
XS GIS Cut Line= 4
      2237409.57     13835017.28      2237430.41     13834842.77
      2237365.30     13834618.81      2237129.19     13834463.13
#Sta/Elev= 30
  4701.8  731.20  4788.7  722.50  4835.0  716.57  4855.2  710.21  4865.2  703.87
  4872.2  701.80  4896.1  701.24  4906.5  698.96  4913.3  694.49  4937.7  694.44
  4952.0  690.49  4958.5  684.00  4977.4  674.59  4977.6  674.09  4981.4  674.59
  4990.7  675.62  5000.2  681.73  5019.1  687.70  5024.3  686.88  5037.5  692.37
  5063.0  700.57  5114.0  705.42  5143.0  712.22  5164.1  713.84  5194.2  720.48
  5242.9  724.19  5272.5  724.26  5287.6  727.50  5344.7  730.88  5393.6  732.11
#Mann=5,-1,0
  4701.8    0.12       0  4788.7    0.07       0  4977.4    0.05       0
  4981.4    0.07       0  5037.5    0.12       0
Bank Sta=4977.4,4981.4
Exp/Cntr=0.3,0.1

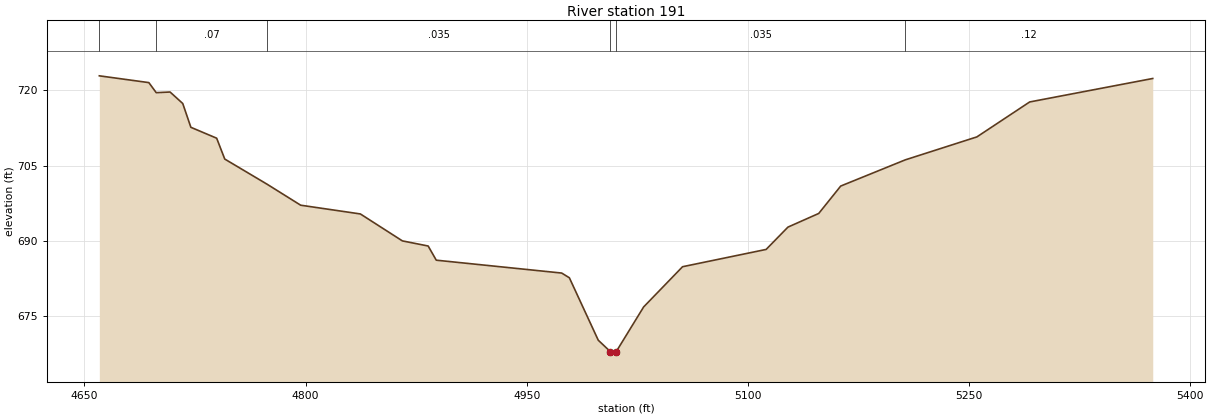
Type RM Length L Ch R = 1,191,0,0,0
BEGIN DESCRIPTION:
A19166
END DESCRIPTION:
XS GIS Cut Line= 4
      2237485.08     13834988.63      2237586.66     13834767.25
      2237552.80     13834626.62      2237285.21     13834439.57
#Sta/Elev= 30
  4660.1  722.87  4693.7  721.52  4698.7  719.52  4708.1  719.65  4716.7  717.36
  4722.2  712.63  4739.7  710.46  4745.2  706.31  4774.0  701.29  4796.7  697.13
  4837.2  695.39  4865.7  690.03  4883.2  689.01  4888.7  686.19  4973.8  683.63
  4979.0  682.69  4998.6  670.27  5006.8  668.00  5007.1  667.50  5010.8  668.00
  5029.4  676.89  5055.8  684.89  5112.5  688.33  5127.3  692.77  5148.2  695.49
  5163.1  700.94  5206.9  706.15  5255.5  710.72  5291.3  717.67  5374.8  722.34
#Mann=6,-1,0
  4660.1    0.12       0  4698.7    0.07       0  4774.0   0.035       0
  5006.8   0.035       0  5010.8   0.035       0  5206.9    0.12       0
Bank Sta=5006.8,5010.8
Exp/Cntr=0.3,0.1

Chan Stop Cuts=-1