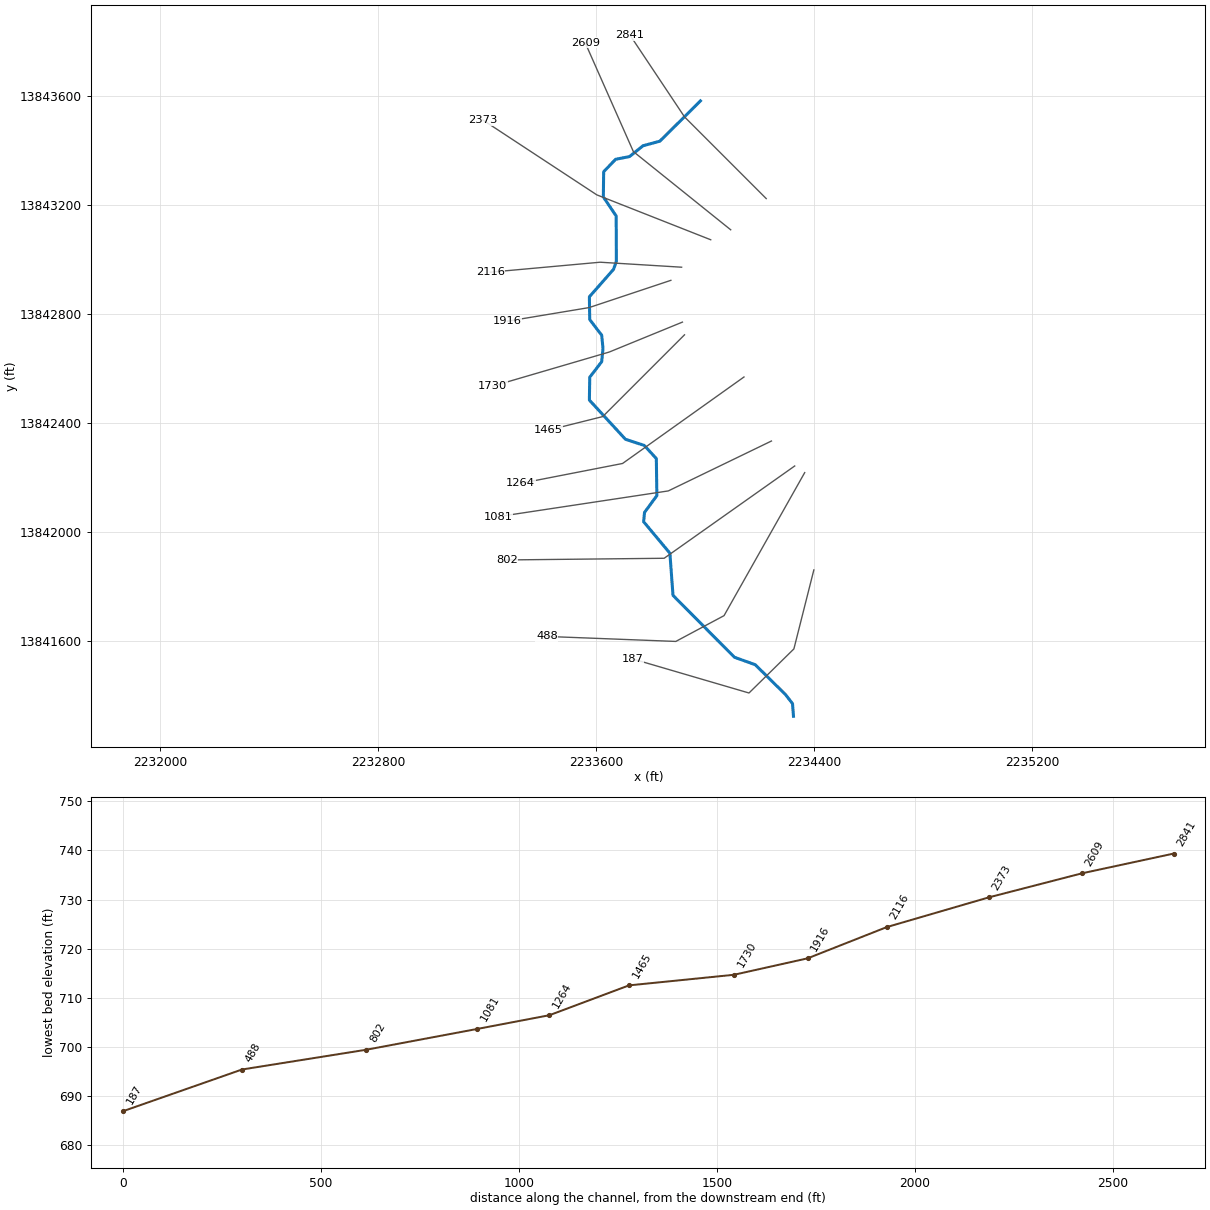
--- Guadalupe Tributary 18.prj (project) ---

Proj Title=Guadalupe Tributary 18 Base Level Engineering
Current Plan=p01
Default Exp/Contr=0.3,0.1
English Units
Geom File=g01
Flow File=f01
Plan File=p01
BEGIN DESCRIPTION:
Guadalupe Tributary 18
END DESCRIPTION:

--- Guadalupe Tributary 18.p01 (plan) ---

Plan Title=Multiple Run
Short Identifier=Multiple
Geom File=g01
Flow File=f01
Subcritical Flow
K Sum by GR= 0
Std Step Tol= 0.01
Critical Tol= 0.01
Num of Std Step Trials= 20
Max Error Tol= 0.3
Flow Tol Ratio= 0.001
Split Flow NTrial= 30
Split Flow Tol= 0.02
Split Flow Ratio= 0.02
Log Output Level= 0
Friction Slope Method= 1
Unsteady Friction Slope Method= 2
Unsteady Bridges Friction Slope Method= 1
Parabolic Critical Depth
Global Vel Dist=  1 , 1 , 1
Global Log Level= 0
CheckData=True
Encroach Param= -1, 0, 0, 0
BEGIN DESCRIPTION:
Multiple Run
END DESCRIPTION:

--- Guadalupe Tributary 18.f01 (steady flow) ---

Flow Title=Multiple
Number of Profiles=7
Profile Names=10-year,25-year,50-year,1pct_min,100-year,1pct_plu,500-year
River Rch & RM= Guadalupe Tribut,Reach-1,2841
     935    1574    2180    1466    2925    5836    5202
Boundary for River Rch & Prof#=Guadalupe Tribut,Reach-1,1
Up Type=0
Dn Type=3
Dn Slope=0.005
Boundary for River Rch & Prof#=Guadalupe Tribut,Reach-1,2
Up Type=0
Dn Type=3
Dn Slope=0.005
Boundary for River Rch & Prof#=Guadalupe Tribut,Reach-1,3
Up Type=0
Dn Type=3
Dn Slope=0.005
Boundary for River Rch & Prof#=Guadalupe Tribut,Reach-1,4
Up Type=0
Dn Type=3
Dn Slope=0.005
Boundary for River Rch & Prof#=Guadalupe Tribut,Reach-1,5
Up Type=0
Dn Type=3
Dn Slope=0.005
Boundary for River Rch & Prof#=Guadalupe Tribut,Reach-1,6
Up Type=0
Dn Type=3
Dn Slope=0.005
Boundary for River Rch & Prof#=Guadalupe Tribut,Reach-1,7
Up Type=0
Dn Type=3
Dn Slope=0.005

--- Guadalupe Tributary 18.g01 (geometry) ---

Geom Title=Existing Conditions

River Reach=Guadalupe Tribut,Reach-1
Reach XY= 30
      2233983.62     13843583.62      2233834.68     13843435.76
      2233772.81     13843418.90      2233723.23     13843379.20
      2233672.41     13843369.28      2233628.37     13843323.72
      2233627.16     13843230.98      2233674.32     13843161.08
      2233675.04     13842994.99      2233664.50     13842965.21
      2233575.94     13842864.52      2233577.17     13842780.98
      2233621.29     13842723.40      2233625.82     13842675.00
      2233621.29     13842626.60      2233577.28     13842569.43
      2233575.93     13842485.48      2233708.34     13842341.66
      2233777.50     13842319.02      2233821.67     13842270.81
      2233823.61     13842134.66      2233778.34     13842073.25
      2233775.10     13842039.04      2233871.44     13841923.53
      2233882.82     13841768.81      2234108.33     13841541.65
      2234184.68     13841514.22      2234295.88     13841404.58
      2234321.51     13841371.43      2234325.00     13841325.00

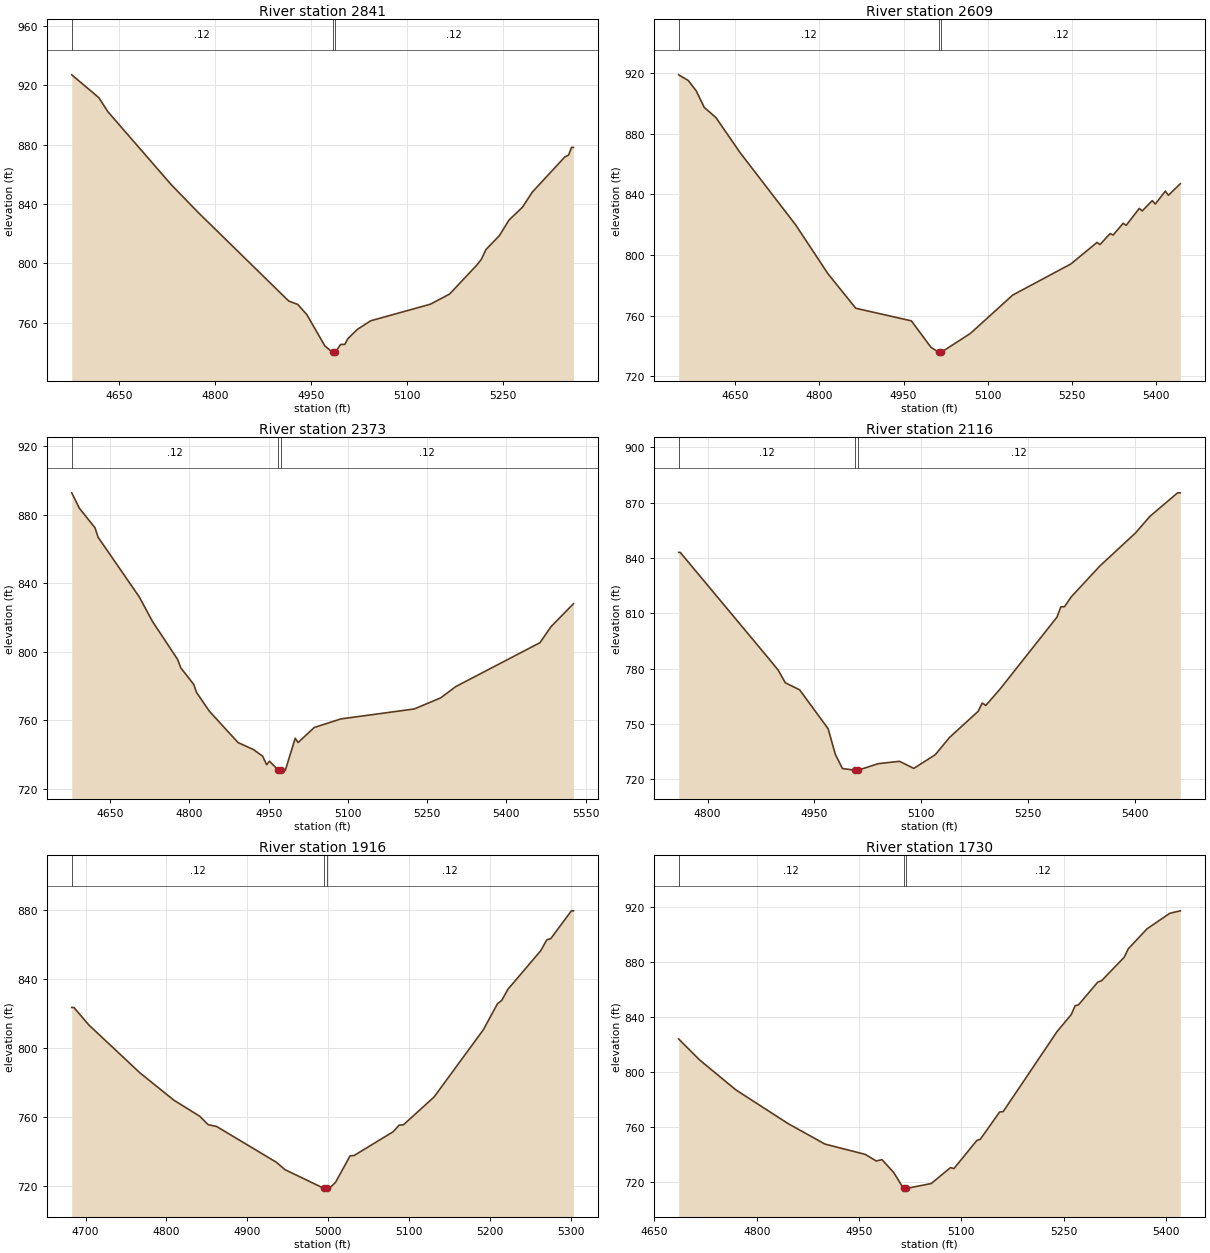
Type RM Length L Ch R = 1,2841,232,232,232
BEGIN DESCRIPTION:
Guadalupe Tributary 18 6.0
END DESCRIPTION:
XS GIS Cut Line= 3
      2234224.98     13843225.02      2233925.00     13843525.00
      2233725.00     13843825.00
#Sta/Elev= 30
  4575.8  927.03  4618.2  911.62  4632.3  902.19  4731.3  853.03  4773.8  834.13
  4915.2  774.51  4929.3  772.22  4943.5  765.40  4971.8  744.20  4983.9  739.87
  4984.1  739.37  4987.9  739.87  4996.5  745.25  5003.0  745.25  5007.6  749.04
  5022.6  755.39  5043.6  761.19  5136.7  772.34  5166.8  779.16  5208.9  798.47
  5216.4  802.50  5223.9  809.29  5244.9  818.66  5259.9  829.12  5281.0  837.80
  5296.0  847.80  5347.1  871.64  5353.1  872.92  5357.6  878.09  5360.6  878.09
#Mann=3,-1,0
  4575.8    0.12       0  4983.9    0.05       0  4987.9    0.12       0
Bank Sta=4983.9,4987.9
Exp/Cntr=0.3,0.1

Type RM Length L Ch R = 1,2609,236,236,236
BEGIN DESCRIPTION:
A19184
END DESCRIPTION:
XS GIS Cut Line= 3
      2234094.57     13843110.52      2233737.45     13843397.44
      2233560.41     13843797.30
#Sta/Elev= 30
  4548.7  918.71  4565.6  915.04  4580.0  908.18  4594.4  897.22  4615.2  890.54
  4658.4  867.42  4757.6  819.80  4815.2  787.63  4864.8  764.91  4964.0  756.61
  4999.2  739.12  5013.1  735.84  5013.3  735.34  5017.1  735.84  5069.4  748.31
  5144.8  773.56  5248.9  794.13  5295.4  808.28  5300.9  806.92  5318.7  814.11
  5324.2  813.14  5342.0  820.87  5347.5  819.56  5370.8  830.67  5376.2  829.06
  5394.0  835.81  5399.5  833.59  5417.3  842.08  5422.8  839.36  5444.1  846.95
#Mann=3,-1,0
  4548.7    0.12       0  5013.1    0.05       0  5017.1    0.12       0
Bank Sta=5013.1,5017.1
Exp/Cntr=0.3,0.1

Type RM Length L Ch R = 1,2373,257,257,257
BEGIN DESCRIPTION:
Guadalupe Tributary 18 5.0
END DESCRIPTION:
XS GIS Cut Line= 3
      2234021.30     13843073.91      2233603.15     13843238.73
      2233184.98     13843513.44
#Sta/Elev= 30
  4577.1  892.65  4591.5  883.68  4621.2  872.25  4626.9  866.81  4705.1  831.89
  4729.5  817.90  4777.4  795.60  4783.7  790.55  4808.1  780.96  4813.4  776.30
  4837.8  765.28  4892.0  747.07  4921.7  742.90  4938.6  739.09  4946.1  734.16
  4951.5  736.20  4968.5  730.92  4968.7  730.42  4972.5  730.92  4981.6  730.99
  5000.2  749.62  5005.6  747.09  5036.3  755.88  5086.8  760.86  5225.5  766.66
  5275.6  773.11  5303.8  779.64  5463.5  805.27  5484.6  814.67  5526.9  827.98
#Mann=3,-1,0
  4577.1    0.12       0  4968.5    0.05       0  4972.5    0.12       0
Bank Sta=4968.5,4972.5
Exp/Cntr=0.3,0.1

Type RM Length L Ch R = 1,2116,200,200,200
BEGIN DESCRIPTION:
A19183
END DESCRIPTION:
XS GIS Cut Line= 3
      2233914.44     13842973.19      2233615.36     13842991.50
      2233212.46     13842954.87
#Sta/Elev= 30
  4759.4  842.96  4761.6  842.96  4889.1  783.90  4899.1  779.12  4909.1  772.27
  4929.2  768.45  4969.2  747.37  4979.3  733.50  4989.3  725.78  5007.3  724.88
  5007.6  724.38  5011.3  724.88  5039.5  728.43  5069.4  729.70  5089.5  725.86
  5119.7  733.32  5139.7  742.68  5179.9  756.83  5185.5  761.27  5190.5  760.01
  5210.0  768.61  5290.4  807.84  5295.9  813.44  5301.0  813.52  5310.4  818.84
  5350.6  835.57  5400.8  853.54  5420.9  862.51  5459.8  875.25  5463.6  875.25
#Mann=3,-1,0
  4759.4    0.12       0  5007.3    0.05       0  5011.3    0.12       0
Bank Sta=5007.3,5011.3
Exp/Cntr=0.3,0.1

Type RM Length L Ch R = 1,1916,186,186,186
BEGIN DESCRIPTION:
Guadalupe Tributary 18 4.0
END DESCRIPTION:
XS GIS Cut Line= 3
      2233875.04     13842925.01      2233575.00     13842825.00
      2233275.01     13842775.00
#Sta/Elev= 30
  4682.9  823.55  4685.6  823.55  4704.0  813.41  4767.3  785.54  4809.4  769.62
  4841.1  760.40  4851.6  755.46  4862.1  754.40  4935.9  733.64  4946.5  729.35
  4994.5  718.51  4994.8  718.01  4998.5  718.51  5001.7  718.51  5009.3  722.08
  5027.1  737.36  5032.1  737.54  5080.3  751.33  5087.9  755.22  5093.0  755.35
  5131.0  771.55  5191.8  810.53  5209.5  825.80  5214.6  827.63  5222.2  834.05
  5262.8  856.51  5270.4  862.86  5275.4  863.60  5300.8  879.71  5303.3  879.71
#Mann=3,-1,0
  4682.9    0.12       0  4994.5    0.05       0  4998.5    0.12       0
Bank Sta=4994.5,4998.5
Exp/Cntr=0.3,0.1

Type RM Length L Ch R = 1,1730,265,265,265
BEGIN DESCRIPTION:
A19182
END DESCRIPTION:
XS GIS Cut Line= 3
      2233917.51     13842771.73      2233648.94     13842661.86
      2233221.66     13842536.73
#Sta/Elev= 30
  4685.5  823.83  4715.9  808.70  4769.3  786.83  4846.7  762.06  4900.1  747.38
  4959.0  739.93  4975.1  735.14  4983.6  736.07  5000.6  726.83  5015.1  715.16
  5015.3  714.66  5019.1  715.16  5055.7  718.71  5083.9  730.27  5089.1  729.64
  5122.5  749.99  5127.7  750.92  5156.0  770.72  5161.2  771.00  5240.3  829.26
  5261.1  841.63  5266.6  847.93  5271.8  848.70  5300.1  865.27  5305.3  866.07
  5338.7  883.25  5344.5  889.28  5372.1  903.89  5405.5  915.19  5420.9  916.96
#Mann=3,-1,0
  4685.5    0.12       0  5015.1    0.05       0  5019.1    0.12       0
Bank Sta=5015.1,5019.1
Exp/Cntr=0.3,0.1

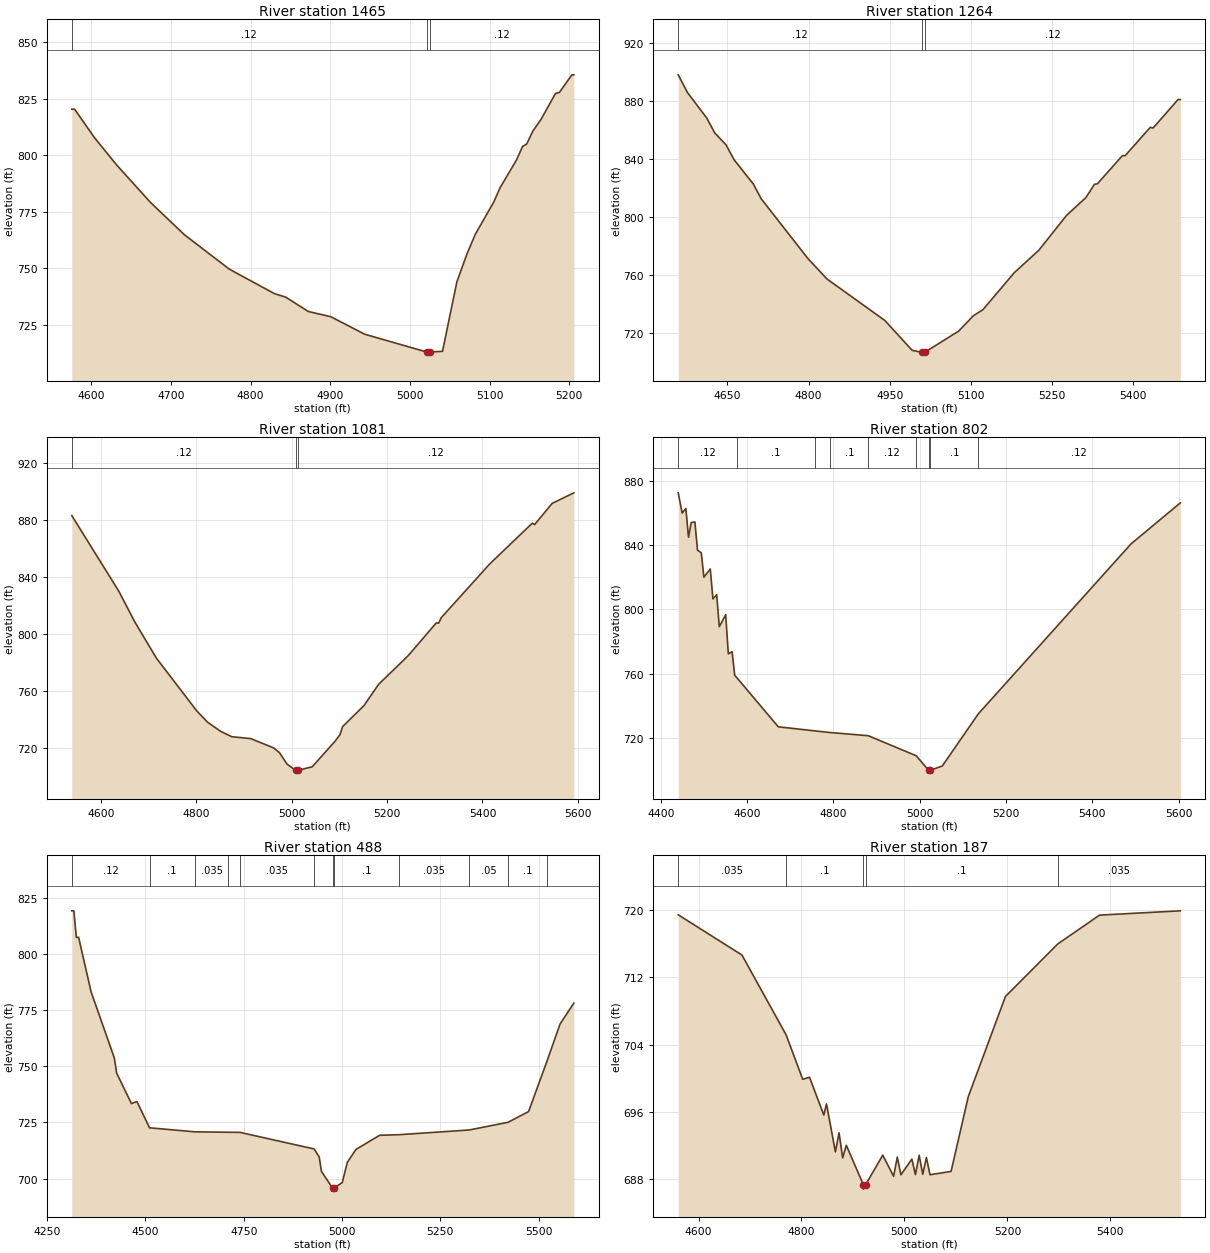
Type RM Length L Ch R = 1,1465,201,201,201
BEGIN DESCRIPTION:
Guadalupe Tributary 18 3.0
END DESCRIPTION:
XS GIS Cut Line= 3
      2233925.02     13842725.02      2233625.00     13842425.00
      2233425.05     13842375.01
#Sta/Elev= 30
  4575.4  820.28  4579.0  820.28  4603.7  807.81  4632.0  795.54  4674.4  779.04
  4716.9  764.79  4773.4  749.57  4830.0  738.76  4844.1  737.23  4872.4  730.90
  4900.7  728.58  4943.1  720.87  5020.9  713.00  5021.1  712.50  5024.9  713.00
  5040.9  713.29  5059.0  744.08  5071.8  756.49  5082.2  765.11  5105.3  779.28
  5113.1  785.55  5133.7  797.77  5141.4  803.80  5146.6  804.89  5154.3  810.59
  5164.6  815.79  5182.7  827.21  5187.8  827.75  5203.3  835.48  5205.8  835.48
#Mann=3,-1,0
  4575.4    0.12       0  5020.9    0.05       0  5024.9    0.12       0
Bank Sta=5020.9,5024.9
Exp/Cntr=0.3,0.1

Type RM Length L Ch R = 1,1264,183,183,183
BEGIN DESCRIPTION:
A19181
END DESCRIPTION:
XS GIS Cut Line= 3
      2234143.38     13842570.29      2233697.77     13842252.87
      2233323.34     13842179.81
#Sta/Elev= 30
  4559.0  898.04  4576.1  885.83  4611.7  868.32  4626.5  858.06  4647.4  849.83
  4662.1  839.68  4697.8  822.90  4712.6  812.63  4798.6  771.65  4834.3  757.42
  4941.2  728.90  4991.6  708.35  5010.5  706.92  5010.8  706.42  5014.5  706.92
  5077.7  721.59  5104.7  732.11  5122.6  736.36  5180.3  761.72  5225.8  777.20
  5277.4  801.34  5312.7  813.41  5329.0  822.74  5334.1  822.94  5380.5  842.40
  5385.6  842.39  5432.1  861.88  5437.2  861.40  5483.7  881.13  5487.6  880.99
#Mann=3,-1,0
  4559.0    0.12       0  5010.5    0.05       0  5014.5    0.12       0
Bank Sta=5010.5,5014.5
Exp/Cntr=0.3,0.1

Type RM Length L Ch R = 1,1081,279,279,279
BEGIN DESCRIPTION:
A19180
END DESCRIPTION:
XS GIS Cut Line= 3
      2234244.15     13842335.29      2233865.64     13842152.14
      2233239.94     13842057.53
#Sta/Elev= 30
  4538.4  883.24  4637.1  830.06  4670.8  808.37  4716.0  782.99  4800.8  745.87
  4823.4  737.97  4851.5  731.42  4874.1  727.79  4913.7  726.47  4961.7  719.98
  4974.0  716.65  4989.9  708.59  5008.1  704.11  5008.4  703.61  5012.1  704.11
  5042.8  706.67  5091.0  724.71  5101.1  729.24  5106.6  734.92  5151.7  749.79
  5182.0  764.56  5244.3  784.80  5303.0  807.77  5308.0  807.56  5313.5  811.43
  5414.7  849.06  5504.4  877.85  5509.5  876.92  5546.1  891.77  5591.7  899.21
#Mann=3,-1,0
  4538.4    0.12       0  5008.1    0.05       0  5012.1    0.12       0
Bank Sta=5008.1,5012.1
Exp/Cntr=0.3,0.1

Type RM Length L Ch R = 1,802,314,314,314
BEGIN DESCRIPTION:
A19179
END DESCRIPTION:
XS GIS Cut Line= 3
      2234329.55     13842243.69      2233850.38     13841904.92
      2233273.55     13841898.81
#Sta/Elev= 30
  4440.2  872.60  4449.3  859.99  4457.9  862.81  4464.0  844.92  4470.3  854.14
  4478.8  854.51  4484.9  836.90  4493.6  835.29  4499.7  820.08  4514.5  825.22
  4520.6  806.60  4529.3  809.16  4535.4  789.26  4550.2  796.79  4556.3  772.40
  4565.0  773.70  4571.1  759.02  4576.7  757.32  4672.1  726.98  4757.6  724.42
  4792.7  723.40  4880.5  721.45  4991.8  708.96  5020.6  699.89  5020.9  699.39
  5024.6  699.89  5052.4  702.65  5135.6  735.00  5489.6  840.80  5603.9  866.34
#Mann=9,-1,0
  4440.2    0.12       0  4576.7     0.1       0  4757.6    0.12       0
  4792.7     0.1       0  4880.5    0.12       0  4991.8     0.1       0
  5020.6    0.05       0  5024.6     0.1       0  5135.6    0.12       0
Bank Sta=5020.6,5024.6
Exp/Cntr=0.3,0.1

Type RM Length L Ch R = 1,488,301,301,301
BEGIN DESCRIPTION:
A19178
END DESCRIPTION:
XS GIS Cut Line= 4
      2234366.20     13842219.29      2234070.14     13841694.32
      2233893.11     13841599.70      2233420.00     13841618.01
#Sta/Elev= 30
  4312.7  819.13  4318.0  819.13  4324.3  807.31  4330.1  807.38  4361.9  783.06
  4421.0  753.65  4426.9  746.94  4464.5  733.39  4478.4  734.32  4510.5  722.63
  4625.4  720.85  4710.8  720.65  4740.3  720.61  4929.0  713.22  4942.0  709.68
  4947.7  703.23  4975.9  695.86  4976.2  695.36  4979.9  695.86  5000.6  698.29
  5013.5  707.27  5035.5  713.03  5095.6  719.30  5146.1  719.58  5323.5  721.66
  5422.2  725.08  5474.5  729.85  5520.9  752.07  5554.6  768.80  5589.6  778.09
#Mann=12,-1,0
  4312.7    0.12       0  4510.5     0.1       0  4625.4   0.035       0
  4710.8    0.12       0  4740.3   0.035       0  4929.0     0.1       0
  4975.9    0.05       0  4979.9     0.1       0  5146.1   0.035       0
  5323.5    0.05       0  5422.2     0.1       0  5520.9    0.12       0
Bank Sta=4975.9,4979.9
Exp/Cntr=0.3,0.1

Type RM Length L Ch R = 1,187,0,0,0
BEGIN DESCRIPTION:
A19177
END DESCRIPTION:
XS GIS Cut Line= 4
      2234399.78     13841862.21      2234326.52     13841572.23
      2234161.70     13841410.46      2233734.39     13841535.60
#Sta/Elev= 30
  4560.6  719.42  4684.4  714.64  4770.2  705.16  4802.4  699.89  4815.6  700.13
  4843.4  695.65  4848.6  696.97  4865.9  691.27  4873.0  693.54  4880.0  690.56
  4887.1  692.05  4920.4  687.35  4920.7  686.85  4924.4  687.35  4957.9  690.88
  4979.0  688.37  4986.1  690.65  4993.2  688.55  5014.4  690.41  5021.4  688.57
  5028.6  690.87  5035.6  688.62  5042.7  690.60  5049.7  688.56  5090.6  688.95
  5124.1  697.84  5196.2  709.72  5297.7  715.95  5379.0  719.38  5535.9  719.89
#Mann=5,-1,0
  4560.6   0.035       0  4770.2     0.1       0  4920.4    0.05       0
  4924.4     0.1       0  5297.7   0.035       0
Bank Sta=4920.4,4924.4
Exp/Cntr=0.3,0.1

Chan Stop Cuts=-1