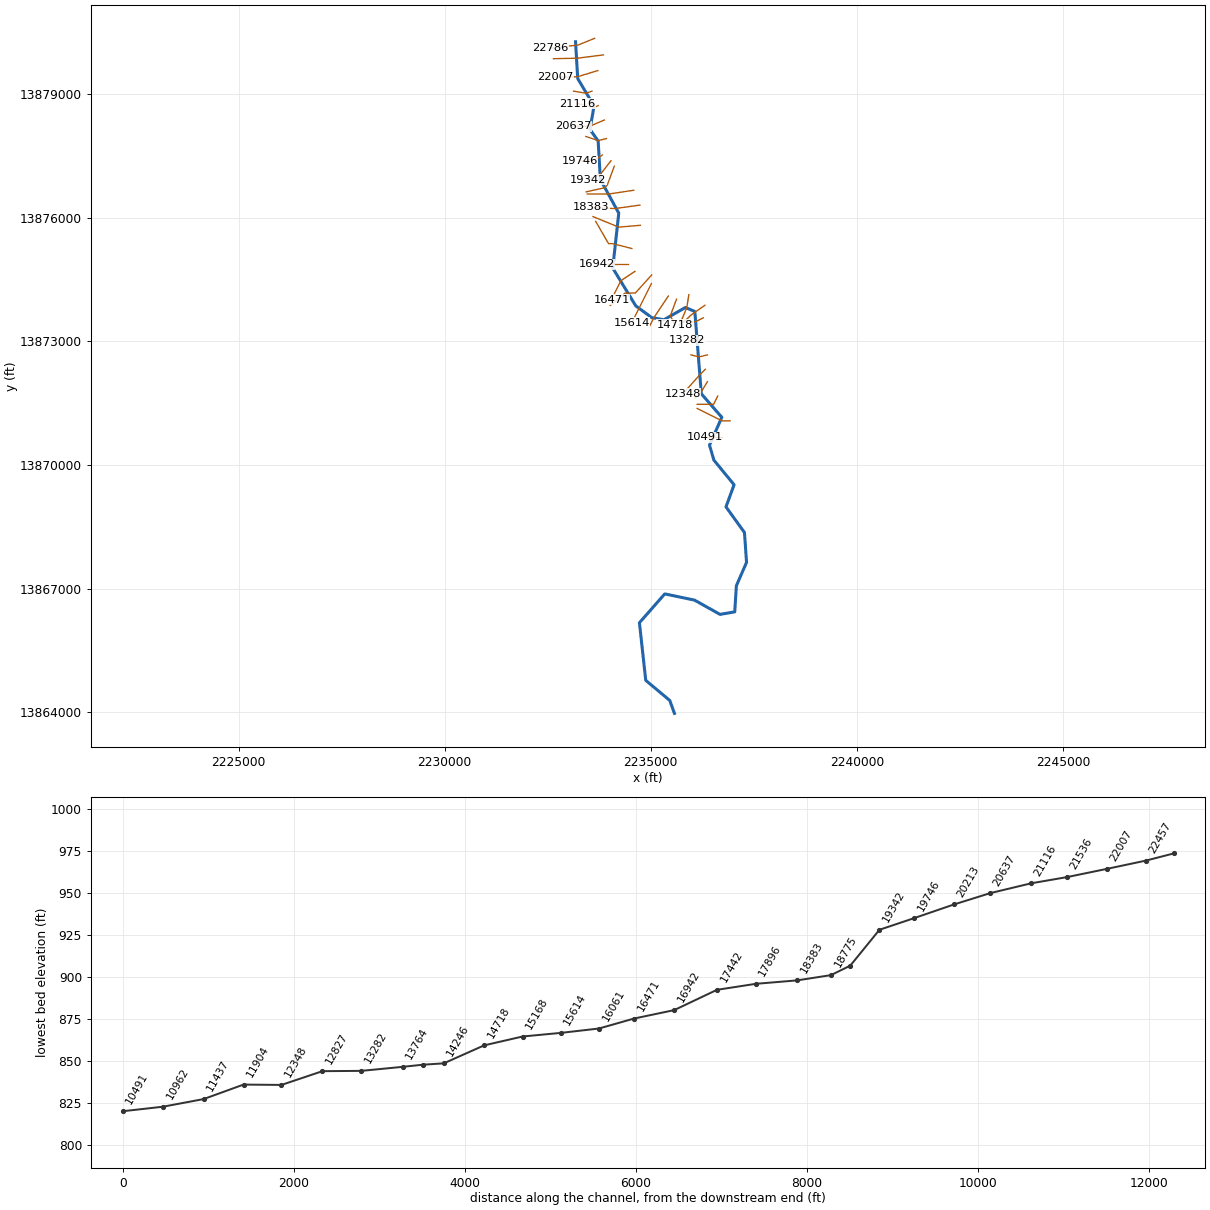
--- Guadalupe Tributary 23.prj (project) ---

Proj Title=Guadalupe Tributary 23 Base Level Engineering
Current Plan=p01
Default Exp/Contr=0.3,0.1
English Units
Geom File=g01
Flow File=f01
Plan File=p01
Y Axis Title=Elevation
X Axis Title(PF)=Main Channel Distance
X Axis Title(XS)=Station
BEGIN DESCRIPTION:
Guadalupe Tributary 23
END DESCRIPTION:
DSS Export Rating Curves= 0
DSS Export Rating Curve Sorted= 0
DSS Export Volume Flow Curves= 0
DXF OffsetX= 0
DXF OffsetY= 0
DXF ScaleX= 1
DXF ScaleY= 10

--- Guadalupe Tributary 23.p01 (plan) ---

Plan Title=Multiple Run
Short Identifier=Multiple
Geom File=g01
Flow File=f01
Subcritical Flow
K Sum by GR= 0
Std Step Tol= 0.01
Critical Tol= 0.01
Num of Std Step Trials= 20
Max Error Tol= 0.3
Flow Tol Ratio= 0.001
Split Flow NTrial= 30
Split Flow Tol= 0.02
Split Flow Ratio= 0.02
Log Output Level= 0
Friction Slope Method= 1
Unsteady Friction Slope Method= 2
Unsteady Bridges Friction Slope Method= 1
Parabolic Critical Depth
Global Vel Dist=  1 , 1 , 1
Global Log Level= 0
CheckData=True
Encroach Param= -1, 0, 0, 0
BEGIN DESCRIPTION:
Multiple Run
END DESCRIPTION:

--- Guadalupe Tributary 23.f01 (steady flow) ---

Flow Title=Multiple
Number of Profiles=7
Profile Names=10-year,25-year,50-year,1pct_min,100-year,1pct_plu,500-year
River Rch & RM= Guadalupe Tribut,Reach-1,22786
    1218    2064    2868    1930    3852    7685    6869
River Rch & RM= Guadalupe Tribut,Reach-1,18775
    2596    4559    6487    4456    8892   17742   16545
River Rch & RM= Guadalupe Tribut,Reach-1,16942
    3445    6107    8745    6040   12052   24047   22668
River Rch & RM= Guadalupe Tribut,Reach-1,9597
    3603    6400    9176    6345   12660   25259   23864
River Rch & RM= Guadalupe Tribut,Reach-1,6858
    4605    8251   11899    8269   16500   32921   31418
River Rch & RM= Guadalupe Tribut,Reach-1,2342
    4993    8977   12978    9039   18034   35983   34492
River Rch & RM= Guadalupe Tribut,Reach-1,936
    5015    9016   13033    9077   18110   36135   34633
Boundary for River Rch & Prof#=Guadalupe Tribut,Reach-1,1
Up Type=0
Dn Type=3
Dn Slope=0.005
Boundary for River Rch & Prof#=Guadalupe Tribut,Reach-1,2
Up Type=0
Dn Type=3
Dn Slope=0.005
Boundary for River Rch & Prof#=Guadalupe Tribut,Reach-1,3
Up Type=0
Dn Type=3
Dn Slope=0.005
Boundary for River Rch & Prof#=Guadalupe Tribut,Reach-1,4
Up Type=0
Dn Type=3
Dn Slope=0.005
Boundary for River Rch & Prof#=Guadalupe Tribut,Reach-1,5
Up Type=0
Dn Type=3
Dn Slope=0.005
Boundary for River Rch & Prof#=Guadalupe Tribut,Reach-1,6
Up Type=0
Dn Type=3
Dn Slope=0.005
Boundary for River Rch & Prof#=Guadalupe Tribut,Reach-1,7
Up Type=0
Dn Type=3
Dn Slope=0.005

--- Guadalupe Tributary 23.g01 (geometry) ---

Geom Title=Existing Conditions
Program Version=4.10

River Reach=Guadalupe Tribut,Reach-1
Reach XY= 30
        2233175.     13880273.13      2233227.24     13879380.93
       2233623.8      13878714.5      2233524.79     13878145.05
      2233723.64     13877865.35      2233777.07     13876930.86
      2234223.94     13876114.56      2234077.24     13874780.93
      2234635.63       13873865.      2235022.58     13873580.54
      2235319.07     13873527.23      2235840.27     13873824.63
      2236069.64      13873727.7      2236226.99     13871730.68
      2236724.62     13871159.73      2236425.76     13870485.69
      2236530.52     13870122.57      2237021.89     13869523.35
      2236826.05     13868985.43       2237273.8      13868364.5
      2237324.49     13867640.21      2237077.07     13867069.14
      2237038.36      13866438.4      2236680.94     13866377.26
      2236063.05     13866723.07      2235340.21     13866874.49
        2234725.       13866175.      2234878.53     13864776.47
      2235461.37     13864288.21        2235575.       13863975.

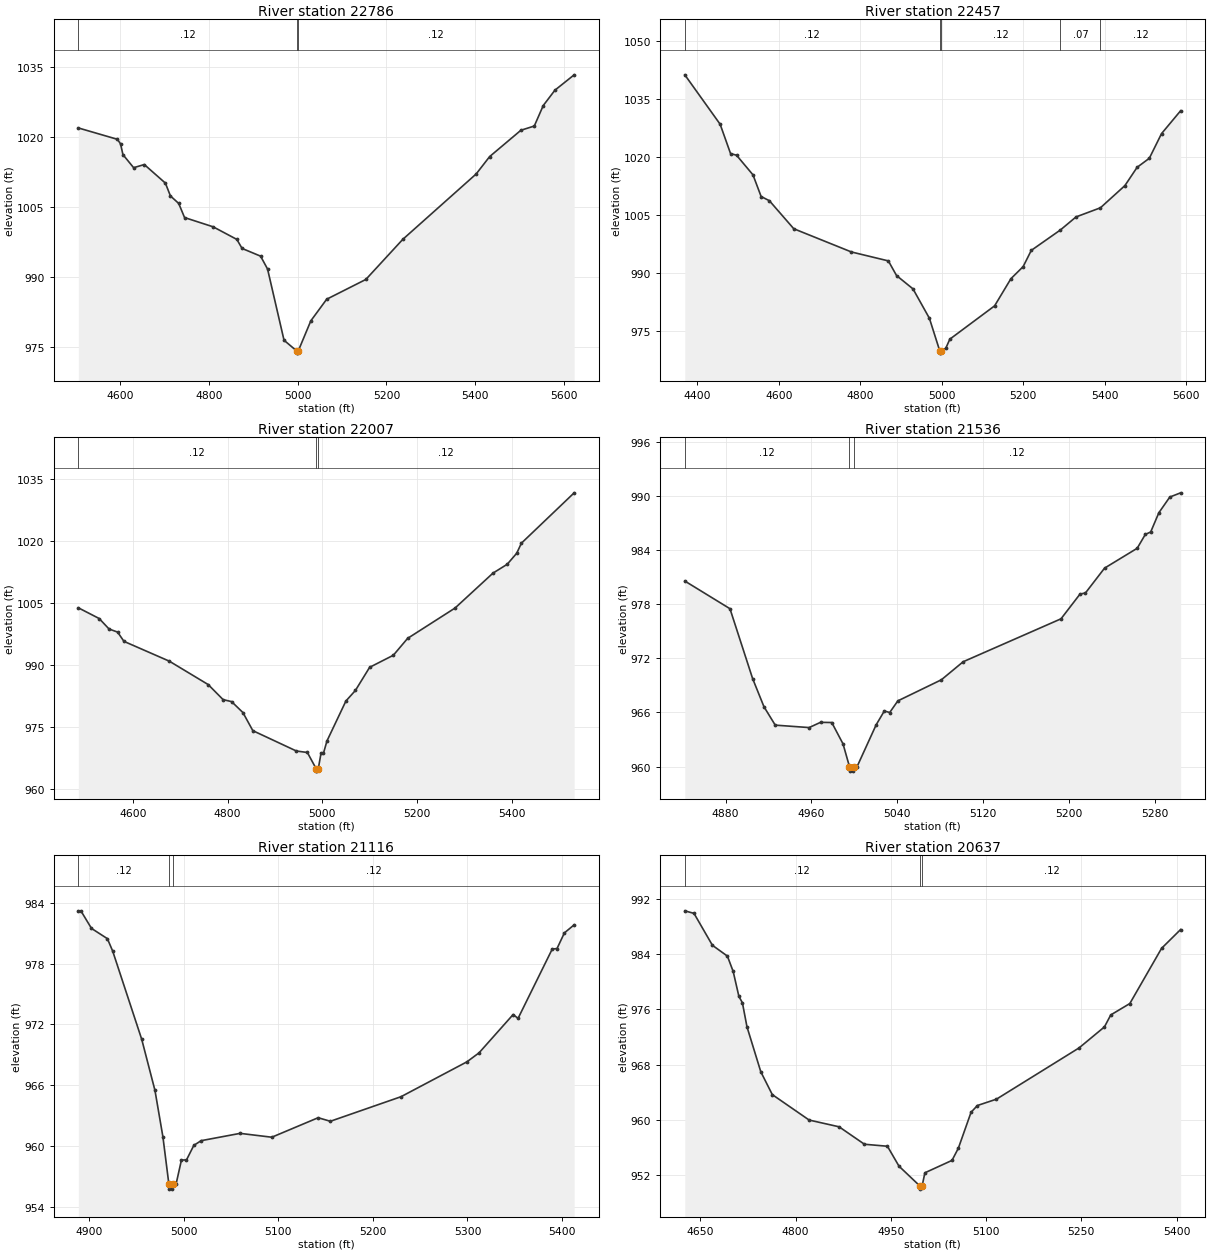
Type RM Length L Ch R = 1 ,22786   ,329,329,329
BEGIN DESCRIPTION:
A19251
END DESCRIPTION:
XS GIS Cut Line= 3
      2233636.59     13880356.53      2233241.83     13880195.56
      2232555.85     13880115.08
#Sta/Elev= 30
    4506    1022  4594.1 1019.55  4601.1 1018.57  4606.5 1016.26  4630.6 1013.45
  4654.6 1014.13  4702.1 1010.14  4713.5 1007.38  4732.1 1005.77  4745.3 1002.73
  4809.7 1000.74  4863.1  998.03  4874.9  996.09  4916.6  994.43  4932.3  991.66
  4969.4  976.35  4997.6  974.08  4997.9  973.58  5001.6  974.08  5029.8  980.53
  5065.5  985.17  5153.7  989.42  5236.9  998.04  5402.3 1012.11  5432.6 1015.84
    5503  1021.5  5533.2 1022.41  5553.4 1026.82  5579.7 1030.12    5623 1033.42
#Mann= 3 ,-1 , 0
    4506     .12       0  4997.6     .05       0  5001.6     .12       0
Bank Sta=4997.6,5001.6
XS Rating Curve= 0 ,0
Exp/Cntr=0.3,0.1

Type RM Length L Ch R = 1 ,22457   ,450,450,450
BEGIN DESCRIPTION:
Guadalupe Tributary 23 46.0
END DESCRIPTION:
XS GIS Cut Line= 3
      2233851.13     13879954.13        2233225.       13879875.
      2232638.15      13879862.2
#Sta/Elev= 30
  4368.9 1041.28  4455.7  1028.5  4481.3 1020.91    4496 1020.48  4536.4  1015.4
  4556.4  1009.8  4576.7 1008.71  4636.6 1001.46  4778.3  995.45    4869  993.14
  4889.1  989.35  4929.5   985.9  4969.8   978.3  4995.5  969.78  4995.7  969.28
  4999.5  969.78    5010  970.53    5020  972.89    5130  981.51  5170.1  988.54
  5200.1  991.66  5220.1  995.86  5291.5 1001.13  5330.1 1004.52    5390 1006.88
  5450.1 1012.62  5480.1 1017.35  5510.1 1019.69  5540.1 1026.07    5587 1031.99
#Mann= 5 ,-1 , 0
  4368.9     .12       0  4995.5     .05       0  4999.5     .12       0
  5291.5     .07       0    5390     .12       0
Bank Sta=4995.5,4999.5
XS Rating Curve= 0 ,0
Exp/Cntr=0.3,0.1

Type RM Length L Ch R = 1 ,22007   ,471,471,471
BEGIN DESCRIPTION:
Guadalupe Tributary 23 45.0
END DESCRIPTION:
XS GIS Cut Line= 3
      2233717.03     13879574.75        2233225.       13879425.
      2232693.83     13879413.79
#Sta/Elev= 30
  4485.3 1003.95  4529.2 1001.36  4550.1  998.82  4568.1  998.07  4581.5  995.83
  4677.1  991.04  4759.2  985.37  4790.6  981.73  4808.5  981.25  4832.4   978.6
  4853.3  974.22  4945.1   969.3  4968.3  968.94  4987.2  964.93  4987.4  964.43
  4991.2  964.93    4997   968.7  5002.1   968.7  5009.6  971.73  5049.6   981.4
  5069.6  983.95  5099.6  989.55  5149.6  992.47  5179.7  996.55  5279.7 1003.89
  5359.7 1012.34  5389.7 1014.48  5409.7 1017.14  5419.7 1019.59  5530.9 1031.77
#Mann= 3 ,-1 , 0
  4485.3     .12       0  4987.2     .05       0  4991.2     .12       0
Bank Sta=4987.2,4991.2
XS Rating Curve= 0 ,0
Exp/Cntr=0.3,0.1

Type RM Length L Ch R = 1 ,21536   ,420,420,420
BEGIN DESCRIPTION:
Guadalupe Tributary 23 44.0
END DESCRIPTION:
XS GIS Cut Line= 3
      2233574.97     13879074.99        2233425.       13879025.
      2233125.02       13879075.
#Sta/Elev= 30
  4841.9  980.57    4884   977.5  4905.1  969.76  4915.7  966.63  4926.2  964.59
  4957.8  964.32  4968.4   964.9  4978.9  964.88  4989.4  962.51  4995.4  959.99
  4995.6  959.49  4999.1  959.49  4999.4  959.99  5002.5  959.99  5020.3  964.63
  5027.9  966.16  5032.9  965.99  5040.5  967.28  5081.1  969.62  5101.4  971.62
  5192.6  976.38  5210.3  979.12  5215.4  979.25  5233.2     982  5263.6   984.2
  5271.2  985.74  5276.2  986.01  5283.8  988.14    5294  989.88  5304.1  990.35
#Mann= 3 ,-1 , 0
  4841.9     .12       0  4995.4     .05       0  4999.4     .12       0
Bank Sta=4995.4,4999.4
XS Rating Curve= 0 ,0
Exp/Cntr=0.3,0.1

Type RM Length L Ch R = 1 ,21116   ,479,479,479
BEGIN DESCRIPTION:
Guadalupe Tributary 23 43.0
END DESCRIPTION:
XS GIS Cut Line= 3
      2233724.96     13878724.98        2233625.       13878675.
      2233224.97     13878775.01
#Sta/Elev= 30
  4888.7  983.19  4891.4  983.19  4902.6  981.46  4919.4  980.45    4925  979.23
  4955.7  970.54  4969.7  965.51  4978.1  960.94  4984.4  956.29  4984.7  955.79
  4988.2  955.79  4988.5  956.29  4992.1  956.32  4997.7  958.66    5003  958.66
  5010.8   960.1  5018.5  960.56  5059.7  961.28  5093.2   960.9  5142.2  962.82
  5155.1  962.47  5229.8  964.89  5299.4  968.32  5312.3  969.21  5348.3  972.98
  5353.5   972.6  5389.6  979.42  5394.7  979.48  5402.5  981.02  5412.8  981.81
#Mann= 3 ,-1 , 0
  4888.7     .12       0  4984.4     .05       0  4988.5     .12       0
Bank Sta=4984.4,4988.5
XS Rating Curve= 0 ,0
Exp/Cntr=0.3,0.1

Type RM Length L Ch R = 1 ,20637   ,424,424,424
BEGIN DESCRIPTION:
Guadalupe Tributary 23 42.0
END DESCRIPTION:
XS GIS Cut Line= 3
      2233875.01       13878375.        2233525.       13878225.
        2233125.       13878225.
#Sta/Elev= 30
  4625.5  990.31    4640  989.94    4669  985.31  4692.6  983.74  4701.7  981.51
  4710.7  977.89  4716.2  976.98  4723.4  973.49  4745.2  966.96  4763.3  963.65
  4821.3  959.96  4868.5  958.98  4908.4  956.45  4944.6  956.16  4962.8  953.27
  4995.2  950.44  4995.4  949.94  4999.3  950.44  5003.6  952.31  5046.3  954.11
  5056.3  955.88  5076.3  961.09  5086.3  962.07  5116.3  962.99  5246.3  970.42
  5286.3  973.47  5296.3  975.21  5326.3  976.86  5376.3  984.87  5406.3   987.6
#Mann= 3 ,-1 , 0
  4625.5     .12       0  4995.2     .05       0  4999.3     .12       0
Bank Sta=4995.2,4999.3
XS Rating Curve= 0 ,0
Exp/Cntr=0.3,0.1

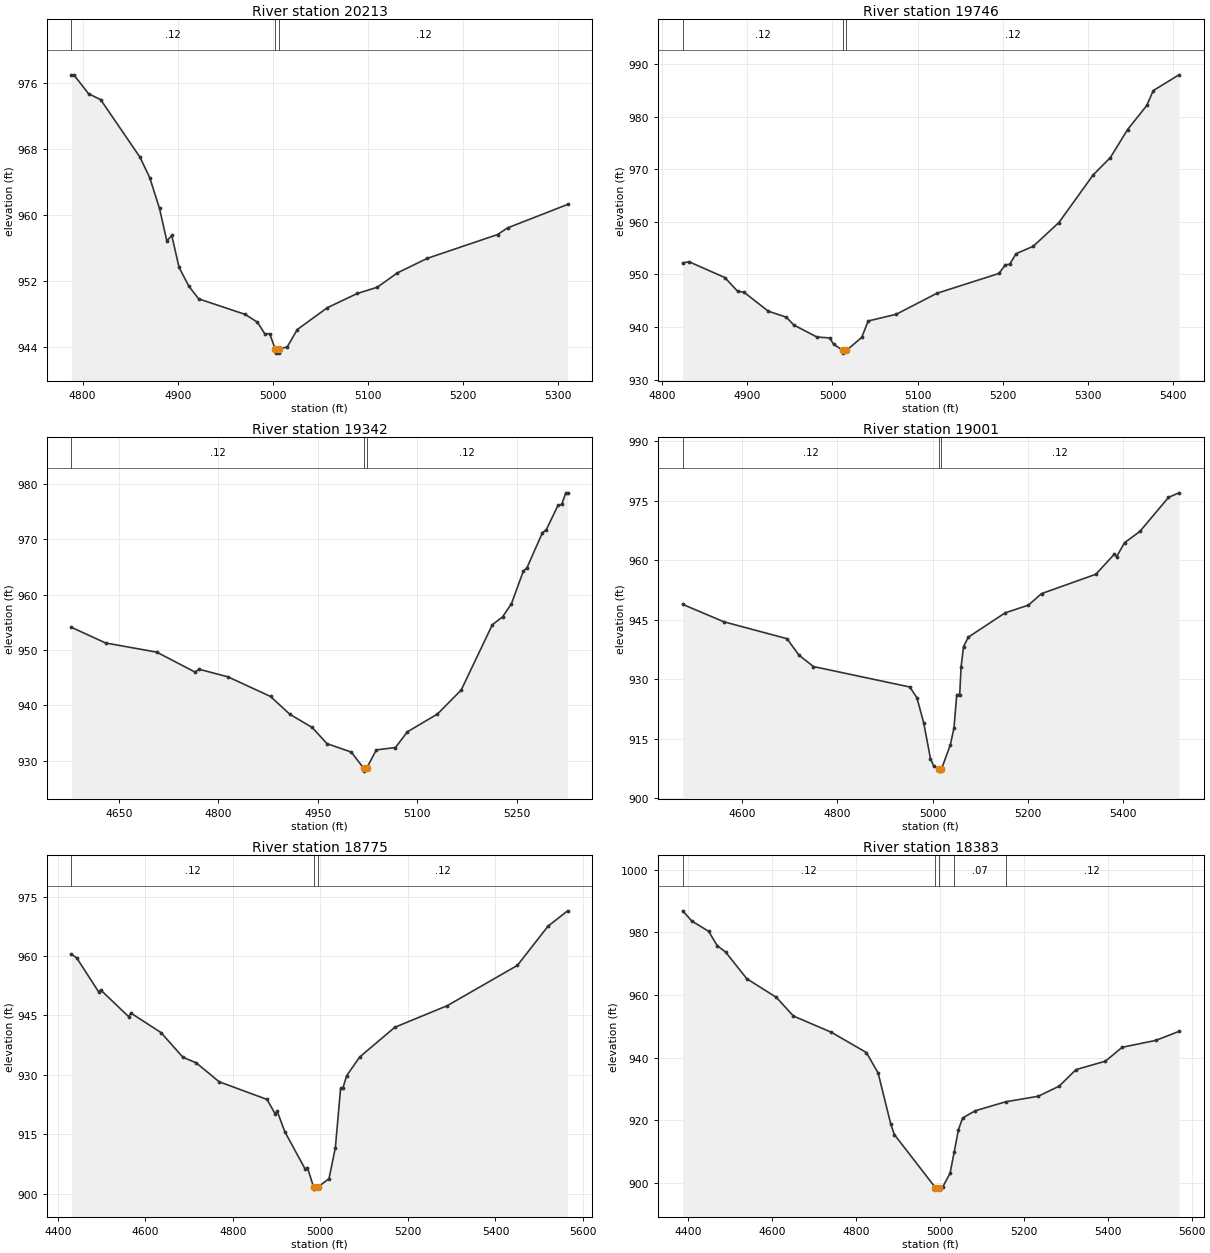
Type RM Length L Ch R = 1 ,20213   ,467,467,467
BEGIN DESCRIPTION:
Guadalupe Tributary 23 41.0
END DESCRIPTION:
XS GIS Cut Line= 3
      2233925.01       13877925.        2233725.       13877875.
        2233425.       13877975.
#Sta/Elev= 30
  4788.1  976.98  4790.7  976.98  4806.2  974.69    4819  973.96  4860.3  966.99
  4870.6   964.5  4880.9  960.77  4888.6  956.82  4893.8  957.48  4901.5   953.6
  4911.8  951.32  4922.1  949.79  4971.1   947.9    4984  946.95  4991.7  945.55
  4996.9  945.55  5002.7   943.7    5003   943.2  5006.6   943.2  5006.9   943.7
  5015.4  943.96  5025.9  946.06  5057.5  948.71  5089.1  950.44  5110.2   951.2
  5131.3  952.94  5162.9  954.71  5236.7  957.59  5247.3   958.4  5310.5  961.25
#Mann= 3 ,-1 , 0
  4788.1     .12       0  5002.7     .05       0  5006.9     .12       0
Bank Sta=5002.7,5006.9
XS Rating Curve= 0 ,0
Exp/Cntr=0.3,0.1

Type RM Length L Ch R = 1 ,19746   ,404,404,404
BEGIN DESCRIPTION:
Guadalupe Tributary 23 40.0
END DESCRIPTION:
XS GIS Cut Line= 3
      2233825.03     13877525.02        2233675.       13877425.
      2233275.03       13877375.
#Sta/Elev= 30
  4823.9   952.2  4831.4  952.41  4873.5  949.41  4888.5   946.8    4896  946.62
  4924.6  943.01  4945.6  941.89  4954.6  940.39  4981.7  938.11  4996.7  937.94
  5001.2  936.77  5012.2  935.55  5012.4  935.05  5016.4  935.55  5034.4  938.05
    5042  941.16  5074.8  942.42  5122.6  946.41  5195.7  950.19  5203.3  951.84
  5208.3  951.93  5215.8  953.94    5236  955.35  5266.2  959.87  5306.5  968.92
  5326.7  972.21  5346.9  977.53  5369.5  982.11  5377.1  984.93  5407.3  987.93
#Mann= 3 ,-1 , 0
  4823.9     .12       0  5012.2     .05       0  5016.4     .12       0
Bank Sta=5012.2,5016.4
XS Rating Curve= 0 ,0
Exp/Cntr=0.3,0.1

Type RM Length L Ch R = 1 ,19342   ,341,341,341
BEGIN DESCRIPTION:
Guadalupe Tributary 23 39.0
END DESCRIPTION:
XS GIS Cut Line= 3
      2234035.11     13877386.57      2233778.34     13877056.99
      2233475.01       13876925.
#Sta/Elev= 30
  4578.4  954.09  4630.1  951.26  4707.2  949.61  4764.9  946.02  4771.3  946.52
  4814.7  945.15  4878.9  941.61  4907.9  938.41  4941.7  936.02    4964  933.11
  5000.7  931.58  5019.5  928.65  5019.8  928.15  5023.8  928.65  5038.4  931.98
  5067.3  932.41  5085.3  935.24  5130.7  938.45  5166.5  942.78  5213.4  954.55
  5228.9  955.97  5242.3  958.35  5260.2  964.22  5265.7  964.83  5289.1  971.17
  5294.6  971.63  5312.6   976.1    5318  976.25  5324.3  978.34    5327  978.34
#Mann= 3 ,-1 , 0
  4578.4     .12       0  5019.5     .05       0  5023.8     .12       0
Bank Sta=5019.5,5023.8
XS Rating Curve= 0 ,0
Exp/Cntr=0.3,0.1

Type RM Length L Ch R = 1 ,19001   ,226,226,226
BEGIN DESCRIPTION:
A19250
END DESCRIPTION:
XS GIS Cut Line= 4
      2234115.58     13877256.26      2233946.96     13876800.23
      2233885.64     13876731.25      2233433.49     13876631.62
#Sta/Elev= 30
  4475.6  948.84  4562.2  944.44  4694.5  940.19  4719.6  936.04    4750  933.17
  4952.2  928.02  4967.2  925.31  4981.4  918.99  4995.6     910  5002.3  908.11
  5014.4  907.32  5014.7  906.82  5018.7  907.32  5037.4  913.48    5045  917.71
  5050.8  926.11    5057  926.11  5059.9  933.08    5065   938.2  5075.2  940.59
  5152.4   946.7  5201.3  948.65  5228.8  951.55  5342.7  956.42  5381.3  961.46
  5386.4  960.88  5402.9  964.37  5435.2  967.22  5495.1  975.78  5517.1  976.94
#Mann= 3 ,-1 , 0
  4475.6     .12       0  5014.4     .05       0  5018.7     .12       0
Bank Sta=5014.4,5018.7
XS Rating Curve= 0 ,0
Exp/Cntr=0.3,0.1

Type RM Length L Ch R = 1 ,18775   ,392,392,392
BEGIN DESCRIPTION:
A19249
END DESCRIPTION:
XS GIS Cut Line= 3
      2234586.94     13876669.93      2233977.62     13876577.96
      2233460.24     13876577.96
#Sta/Elev= 30
  4431.2  960.45  4443.3  959.54  4493.3     951  4498.3  951.43  4562.2  944.69
  4567.2   945.6  4636.1  940.68    4686  934.46  4716.3  933.06  4768.9  928.27
  4878.1  923.82  4896.5  920.23  4901.6   920.8  4918.6  915.72  4965.4  906.22
  4970.5  906.63  4984.6  901.69  4985.1  901.19  4994.2  901.69  5019.7  903.82
  5034.3  911.64  5046.2  926.59  5051.2  926.59    5060   929.8    5090  934.53
    5170  942.02    5290  947.48    5450  957.63    5520  967.52  5564.8   971.4
#Mann= 3 ,-1 , 0
  4431.2     .12       0  4984.6     .05       0  4994.2     .12       0
Bank Sta=4984.6,4994.2
XS Rating Curve= 0 ,0
Exp/Cntr=0.3,0.1

Type RM Length L Ch R = 1 ,18383   ,487,487,487
BEGIN DESCRIPTION:
Guadalupe Tributary 23 38.0
END DESCRIPTION:
XS GIS Cut Line= 3
      2234736.38      13876309.7        2234125.       13876225.
      2233559.97     13876252.22
#Sta/Elev= 30
  4386.9   986.9  4408.5  983.66  4448.9  980.35  4469.1  975.79  4489.2  973.75
  4539.7  965.24  4610.4  959.26  4650.8  953.33  4741.6  948.12  4824.7  941.68
  4852.7  935.17    4883  918.78  4891.4  915.51  4989.2  898.58  4989.7  898.08
  4998.8  898.58  5006.6  898.74  5024.1  903.09  5034.3  910.06  5044.2  917.04
  5054.2  920.78  5084.2  923.09    5157  925.96  5234.4  927.72  5284.4  930.96
  5324.5  936.23  5394.6  938.92  5434.6  943.36  5514.7  945.55  5569.8  948.42
#Mann= 5 ,-1 , 0
  4386.9     .12       0  4989.2     .05       0  4998.8     .12       0
  5034.3     .07       0    5157     .12       0
Bank Sta=4989.2,4998.8
XS Rating Curve= 0 ,0
Exp/Cntr=0.3,0.1

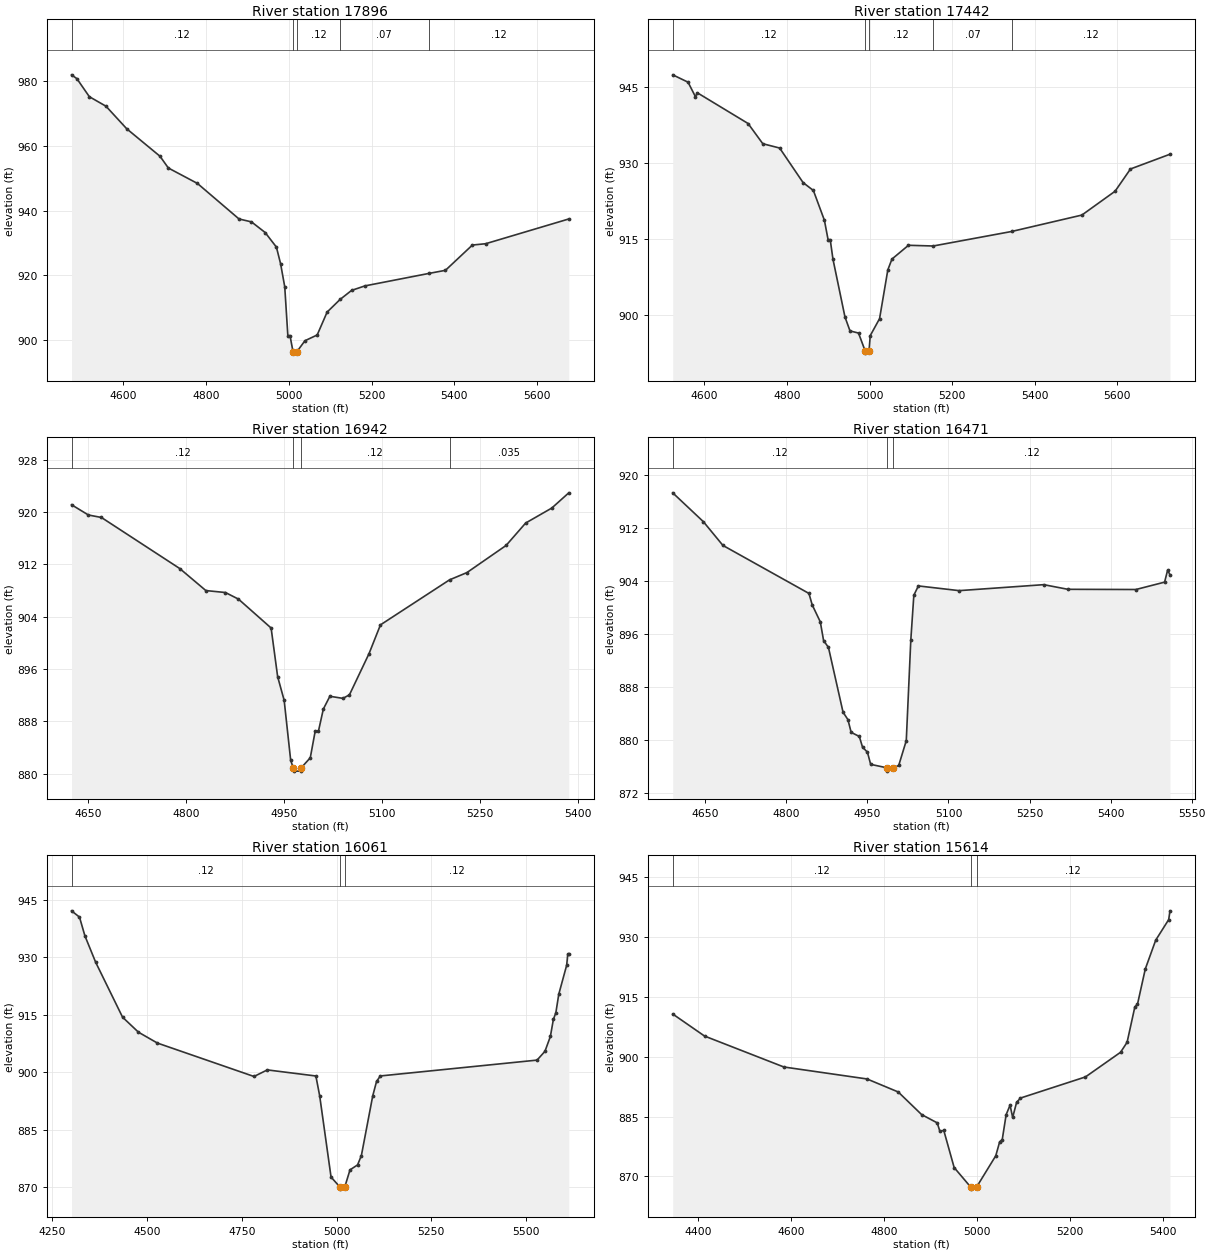
Type RM Length L Ch R = 1 ,17896   ,454,454,454
BEGIN DESCRIPTION:
Guadalupe Tributary 23 37.0
END DESCRIPTION:
XS GIS Cut Line= 3
      2234747.86     13875819.18        2234225.       13875775.
      2233599.12     13876029.59
#Sta/Elev= 30
  4475.7  981.91  4488.6  980.73  4518.7  975.16  4558.9  972.22    4609  965.25
  4689.3  956.77  4709.4  953.15  4779.6  948.39    4880  937.42  4910.1  936.52
  4943.1  933.24  4970.3  928.73  4980.4  923.58  4990.4  916.48  4997.9  901.39
  5003.1  901.39  5010.3  896.51  5010.8  896.01    5020  896.51  5039.2  899.84
  5068.7  901.61  5092.7  908.68  5123.9  912.57  5151.7  915.37  5183.9  916.76
  5337.5  920.59  5378.3  921.57  5443.4  929.37  5475.4  929.78  5676.1  937.42
#Mann= 5 ,-1 , 0
  4475.7     .12       0  5010.3     .05       0    5020     .12       0
  5123.9     .07       0  5337.5     .12       0
Bank Sta=5010.3,5020
XS Rating Curve= 0 ,0
Exp/Cntr=0.3,0.1

Type RM Length L Ch R = 1 ,17442   ,500,500,500
BEGIN DESCRIPTION:
Guadalupe Tributary 23 36.0
END DESCRIPTION:
XS GIS Cut Line= 4
      2234540.98     13875255.84        2234075.       13875375.
        2233975.       13875375.      2233663.39     13875914.96
#Sta/Elev= 30
  4523.2  947.34  4560.3  945.89  4578.1  943.05  4583.2  943.78  4705.7  937.74
  4741.4  933.75  4782.2   932.9    4839  926.08  4863.9  924.53  4890.6  918.65
  4899.5  914.83  4904.7  914.82  4911.3  910.99  4940.4  899.58  4952.6  896.83
  4973.2  896.41    4989  892.95  4989.5  892.45  4998.8  892.95  5001.6   895.9
  5024.2  899.25  5044.2  908.87  5054.2     911  5094.2  913.72  5154.1  913.58
  5343.9  916.44  5514.2  919.68  5594.6  924.38  5631.9  928.77  5727.6  931.68
#Mann= 5 ,-1 , 0
  4523.2     .12       0    4989     .05       0  4998.8     .12       0
  5154.1     .07       0  5343.9     .12       0
Bank Sta=4989,4998.8
XS Rating Curve= 0 ,0
Exp/Cntr=0.3,0.1

Type RM Length L Ch R = 1 ,16942   ,471,471,471
BEGIN DESCRIPTION:
Guadalupe Tributary 23 35.0
END DESCRIPTION:
XS GIS Cut Line= 5
      2234450.81       13874875.        2234175.       13874875.
        2234075.       13874875.        2233975.       13874875.
      2233688.91       13874875.
#Sta/Elev= 30
  4624.1  921.13  4649.9  919.56  4669.9  919.18  4789.9  911.37  4829.9     908
  4859.9   907.7  4879.9  906.69  4929.9  902.27  4939.9  894.83  4949.9   891.2
  4959.9  882.01  4963.9  880.88  4964.4  880.38  4975.4  880.38  4975.9  880.88
  4989.9  882.42  4997.4  886.48  5002.4  886.48  5009.9  889.87  5019.9  891.83
  5039.9  891.51  5049.9  892.05  5079.9  898.35  5097.4  902.75  5203.3  909.64
  5229.9  910.75  5289.9   914.9  5319.9  918.33  5359.9  920.62    5386  922.95
#Mann= 4 ,-1 , 0
  4624.1     .12       0  4963.9     .05       0  4975.9     .12       0
  5203.3    .035       0
Bank Sta=4963.9,4975.9
XS Rating Curve= 0 ,0
Exp/Cntr=0.3,0.1

Type RM Length L Ch R = 1 ,16471   ,410,410,410
BEGIN DESCRIPTION:
Guadalupe Tributary 23 34.0
END DESCRIPTION:
XS GIS Cut Line= 5
      2234616.02     13874702.35        2234425.       13874575.
        2234275.       13874475.        2234225.       13874375.
      2234046.77     13874018.54
#Sta/Elev= 30
  4589.7  917.26  4646.5  912.91  4682.6  909.34  4841.8  902.11  4847.8  900.39
  4862.8  897.83  4868.9  895.01  4877.9  893.98  4904.9  884.22  4913.9  883.11
  4919.9  881.19    4935  880.57    4941  878.95    4950  878.21    4956  876.37
    4986  875.85  4986.5  875.35  4998.1  875.85  5007.9   876.2  5021.9  879.94
  5030.3   895.1  5035.9  901.84  5044.3  903.24  5119.7  902.53  5276.3  903.43
    5321  902.73  5446.8   902.7  5499.9  903.81  5505.5  905.61  5509.9  904.92
#Mann= 3 ,-1 , 0
  4589.7     .12       0    4986     .05       0  4998.1     .12       0
Bank Sta=4986,4998.1
XS Rating Curve= 0 ,0
Exp/Cntr=0.3,0.1

Type RM Length L Ch R = 1 ,16061   ,447,447,447
BEGIN DESCRIPTION:
Guadalupe Tributary 23 33.0
END DESCRIPTION:
XS GIS Cut Line= 5
      2235023.81     13874615.87        2234625.       13874175.
        2234525.       13874175.        2234375.       13874175.
      2234015.92     13873876.24
#Sta/Elev= 30
  4300.9  942.12  4321.9  940.48  4336.1  935.61  4364.5   928.7  4435.5  914.34
  4477.4  910.42  4527.4  907.58  4782.2  898.85  4817.3  900.57  4945.4  898.98
  4955.4  893.81  4985.4  872.58  5009.3  869.93  5009.8  869.43  5021.4  869.93
  5035.4  874.46  5055.4  875.76  5065.4   878.2  5095.4  893.81  5105.4  897.55
  5115.4  898.99  5528.8  903.13  5549.6  905.43  5563.9   909.3  5571.8  913.75
  5578.3  915.48  5586.1  920.36  5606.9  927.92  5609.8  930.84  5612.5  930.84
#Mann= 3 ,-1 , 0
  4300.9     .12       0  5009.3     .05       0  5021.4     .12       0
Bank Sta=5009.3,5021.4
XS Rating Curve= 0 ,0
Exp/Cntr=0.3,0.1

Type RM Length L Ch R = 1 ,15614   ,446,446,446
BEGIN DESCRIPTION:
Guadalupe Tributary 23 32.0
END DESCRIPTION:
XS GIS Cut Line= 5
      2235015.57     13874406.15        2234775.       13873925.
        2234725.       13873825.        2234675.       13873725.
       2234537.5       13873450.
#Sta/Elev= 30
  4345.9  910.68  4414.3  905.16  4584.8  897.41  4763.6  894.41  4830.7  891.15
    4881  885.49  4914.6  883.41  4920.2   881.3  4928.6  881.53  4950.9  872.23
  4986.6  867.32  4987.1  866.82    4999  867.32  5040.4  875.18  5048.7  878.65
  5054.3  879.23  5062.7  885.48  5071.1  887.84  5076.7  884.77  5085.1  888.53
  5093.5  889.63  5233.2  894.92  5308.7   901.1  5322.7   903.6  5339.4  912.48
    5345  913.11  5361.8  921.95  5384.2  929.17  5412.1  934.32  5414.9  936.52
#Mann= 3 ,-1 , 0
  4345.9     .12       0  4986.6     .05       0    4999     .12       0
Bank Sta=4986.6,4999
XS Rating Curve= 0 ,0
Exp/Cntr=0.3,0.1

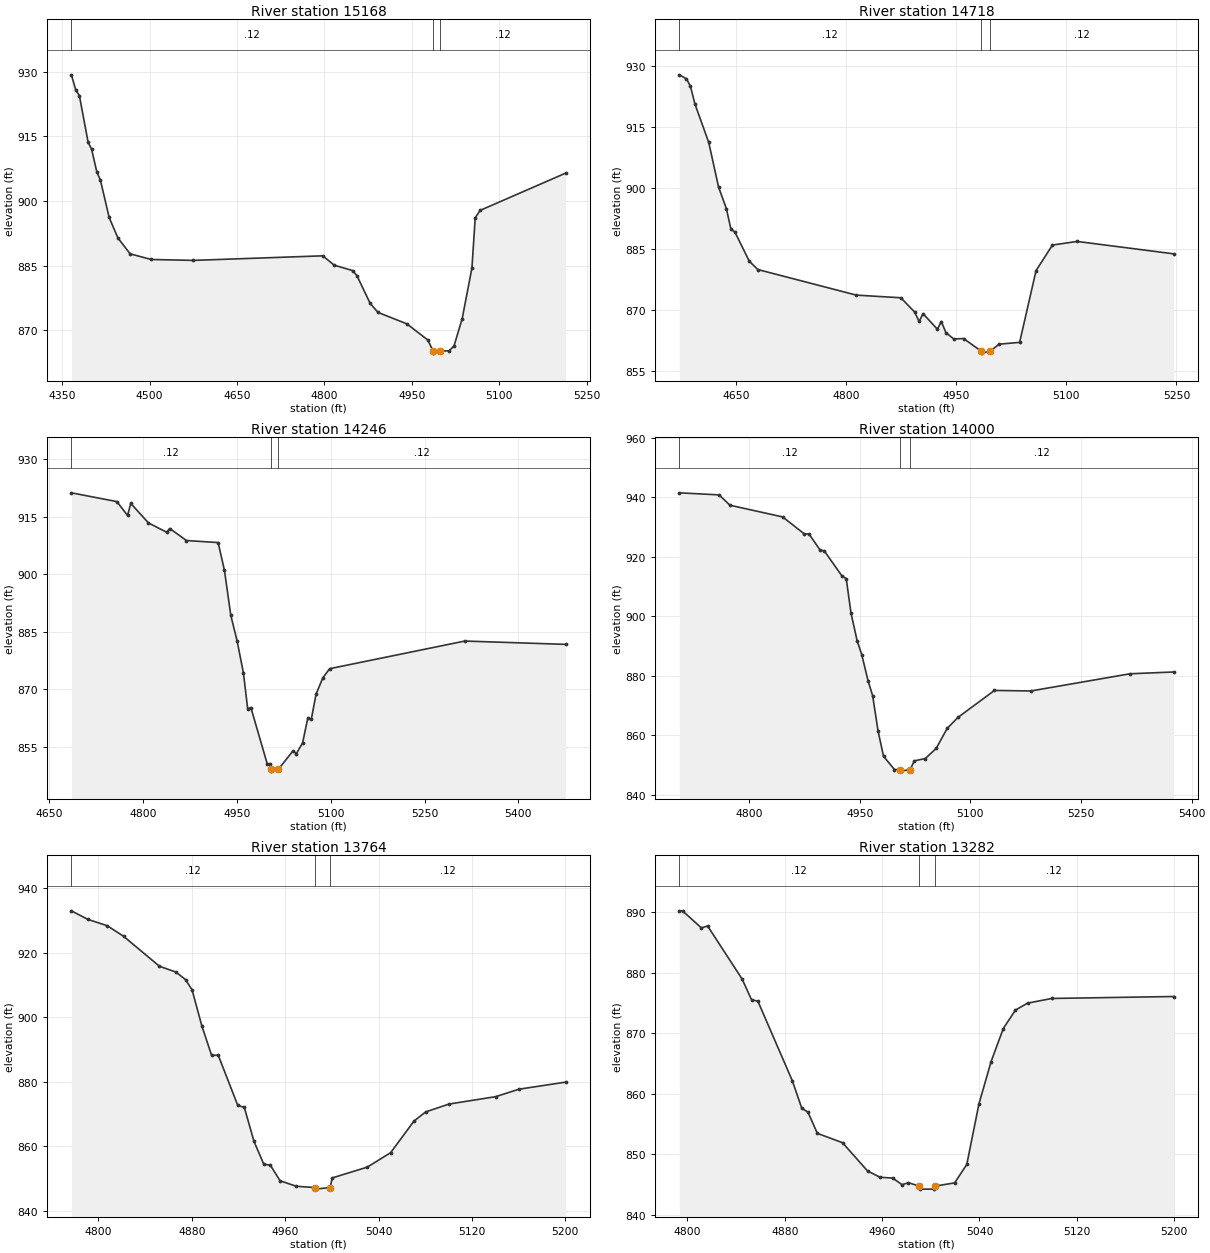
Type RM Length L Ch R = 1 ,15168   ,450,450,450
BEGIN DESCRIPTION:
Guadalupe Tributary 23 31.0
END DESCRIPTION:
XS GIS Cut Line= 5
      2235426.76     13874102.64        2235175.       13873725.
        2235075.       13873575.        2235025.       13873475.
      2234979.36     13873383.72
#Sta/Elev= 30
  4365.8  929.26  4373.5  925.67  4379.5  924.46  4394.5  913.62  4400.5  911.99
  4409.5  906.69  4415.5  904.88  4430.6  896.17  4445.6  891.41  4466.6  887.72
  4502.7  886.41  4574.8   886.2  4797.1  887.26  4816.7  885.09  4848.2  883.84
  4855.7  882.66  4878.3  876.24  4891.8  874.13  4941.4  871.47  4977.4  867.72
  4986.2  865.18  4986.7  864.68  4998.6  865.18  5013.9  865.21  5022.3  866.37
  5036.3  872.69    5053  884.45  5058.6  896.08    5067   897.8  5213.8  906.45
#Mann= 3 ,-1 , 0
  4365.8     .12       0  4986.2     .05       0  4998.6     .12       0
Bank Sta=4986.2,4998.6
XS Rating Curve= 0 ,0
Exp/Cntr=0.3,0.1

Type RM Length L Ch R = 1 ,14718   ,472,472,472
BEGIN DESCRIPTION:
Guadalupe Tributary 23 30.0
END DESCRIPTION:
XS GIS Cut Line= 4
      2235624.98     13874024.96        2235475.       13873625.
        2235525.       13873525.      2235585.08     13873404.84
#Sta/Elev= 30
  4572.9  927.87  4582.6  926.89    4588  925.05  4594.2  920.65  4612.9  911.24
  4626.3  900.25  4636.9  894.98  4643.2  889.86  4648.5  889.21  4668.1  882.03
  4679.7  879.97    4814  873.67  4874.6  873.02  4893.3  869.53  4899.5  867.19
  4904.8  869.12  4924.4  865.28  4929.7  867.18    4936  864.44  4946.7  862.88
    4960  862.99    4984   859.9  4984.5   859.4  4996.5   859.9  5008.4   861.6
  5036.4  862.05  5058.8  879.72  5081.1  885.99  5114.7  886.88  5246.2  883.83
#Mann= 3 ,-1 , 0
  4572.9     .12       0    4984     .05       0  4996.5     .12       0
Bank Sta=4984,4996.5
XS Rating Curve= 0 ,0
Exp/Cntr=0.3,0.1

Type RM Length L Ch R = 1 ,14246   ,246,246,246
BEGIN DESCRIPTION:
Guadalupe Tributary 23 29.0
END DESCRIPTION:
XS GIS Cut Line= 3
      2235924.37     13874136.83        2235875.       13873825.
      2235694.46     13873385.77
#Sta/Elev= 30
  4685.1  921.17  4757.8  918.89    4775  915.28  4780.1  918.41  4808.4  913.33
  4837.4  910.92  4842.4  911.88  4869.2  908.75  4919.8  908.22  4929.9  901.01
  4940.1  889.26  4950.2  882.59  4960.3  874.25  4967.1  864.92  4972.2  865.26
  4998.3  850.64  5003.5  850.64  5003.8  849.21  5004.3  848.71  5016.3  849.21
  5039.5  853.97  5044.9  853.25  5054.9  856.04  5063.4  862.65  5068.8  862.19
  5076.5  868.77  5087.3  872.99  5098.2  875.38  5314.4  882.58  5475.7  881.71
#Mann= 3 ,-1 , 0
  4685.1     .12       0  5003.8     .05       0  5016.3     .12       0
Bank Sta=5003.8,5016.3
XS Rating Curve= 0 ,0
Exp/Cntr=0.3,0.1

Type RM Length L Ch R = 1 ,14000   ,236,236,236
BEGIN DESCRIPTION:
A19248
END DESCRIPTION:
XS GIS Cut Line= 3
      2236315.26     13873880.09      2235978.03     13873642.49
      2235794.06     13873462.36
#Sta/Elev= 30
  4705.6  941.45  4759.4  940.76  4774.2  937.28  4845.6  933.35  4875.2   927.6
  4881.3  927.63  4896.1   922.3  4902.2  921.88  4925.7   913.6  4931.8   912.6
  4938.3  900.95  4946.6   891.7  4952.8  887.08  4961.4  878.24  4967.6  873.24
    4975  861.27  4982.4  852.87  4997.2  848.42  5005.2  848.39  5005.7  847.89
  5018.2  848.39  5024.2  851.34    5039  852.13  5053.8  855.55  5068.6  862.25
  5083.4  865.98  5132.7  875.02  5182.1  874.84  5316.5  880.62  5375.6  881.22
#Mann= 3 ,-1 , 0
  4705.6     .12       0  5005.2     .05       0  5018.2     .12       0
Bank Sta=5005.2,5018.2
XS Rating Curve= 0 ,0
Exp/Cntr=0.3,0.1

Type RM Length L Ch R = 1 ,13764   ,482,482,482
BEGIN DESCRIPTION:
Guadalupe Tributary 23 28.0
END DESCRIPTION:
XS GIS Cut Line= 3
      2236275.02     13873575.01        2236075.       13873475.
      2235875.03       13873475.
#Sta/Elev= 30
  4776.8  932.93  4790.8   930.3  4807.6   928.3  4821.5  925.04  4852.3  915.73
  4866.3  913.96  4874.6  911.62  4880.2  908.44  4888.6  897.26    4897  888.07
  4902.6   888.2  4919.4   872.6    4925  871.98  4933.3  861.44  4941.7  854.34
  4947.3  854.06  4955.7   849.2  4969.7  847.51  4985.5  847.13    4986  846.63
  4998.5  847.13  5000.4  850.11  5030.4  853.45  5050.4  857.94  5070.4  867.73
  5080.4  870.57  5100.4  873.01  5140.4   875.3  5160.4  877.62  5200.4  879.81
#Mann= 3 ,-1 , 0
  4776.8     .12       0  4985.5     .05       0  4998.5     .12       0
Bank Sta=4985.5,4998.5
XS Rating Curve= 0 ,0
Exp/Cntr=0.3,0.1

Type RM Length L Ch R = 1 ,13282   ,455,455,455
BEGIN DESCRIPTION:
Guadalupe Tributary 23 27.0
END DESCRIPTION:
XS GIS Cut Line= 3
      2236275.05     13873075.01        2236075.       13873025.
        2235875.       13873025.
#Sta/Elev= 30
  4793.4  890.23    4796  890.23  4811.5  887.41  4816.6  887.73    4845  878.95
  4852.7  875.54  4857.9  875.31  4886.2  862.17    4894  857.61  4899.1  856.95
  4906.8  853.46  4927.5  851.91  4948.1  847.23  4958.4   846.2  4968.7  846.07
  4976.4  844.97  4981.6   845.3  4990.5  844.74    4991  844.24    5003  844.24
  5003.5  844.74  5019.6  845.27  5029.6  848.31  5039.6  858.33  5049.6  865.33
  5059.6  870.78  5069.6  873.83  5079.6  874.98  5099.6  875.75  5199.6  876.07
#Mann= 3 ,-1 , 0
  4793.4     .12       0  4990.5     .05       0  5003.5     .12       0
Bank Sta=4990.5,5003.5
XS Rating Curve= 0 ,0
Exp/Cntr=0.3,0.1

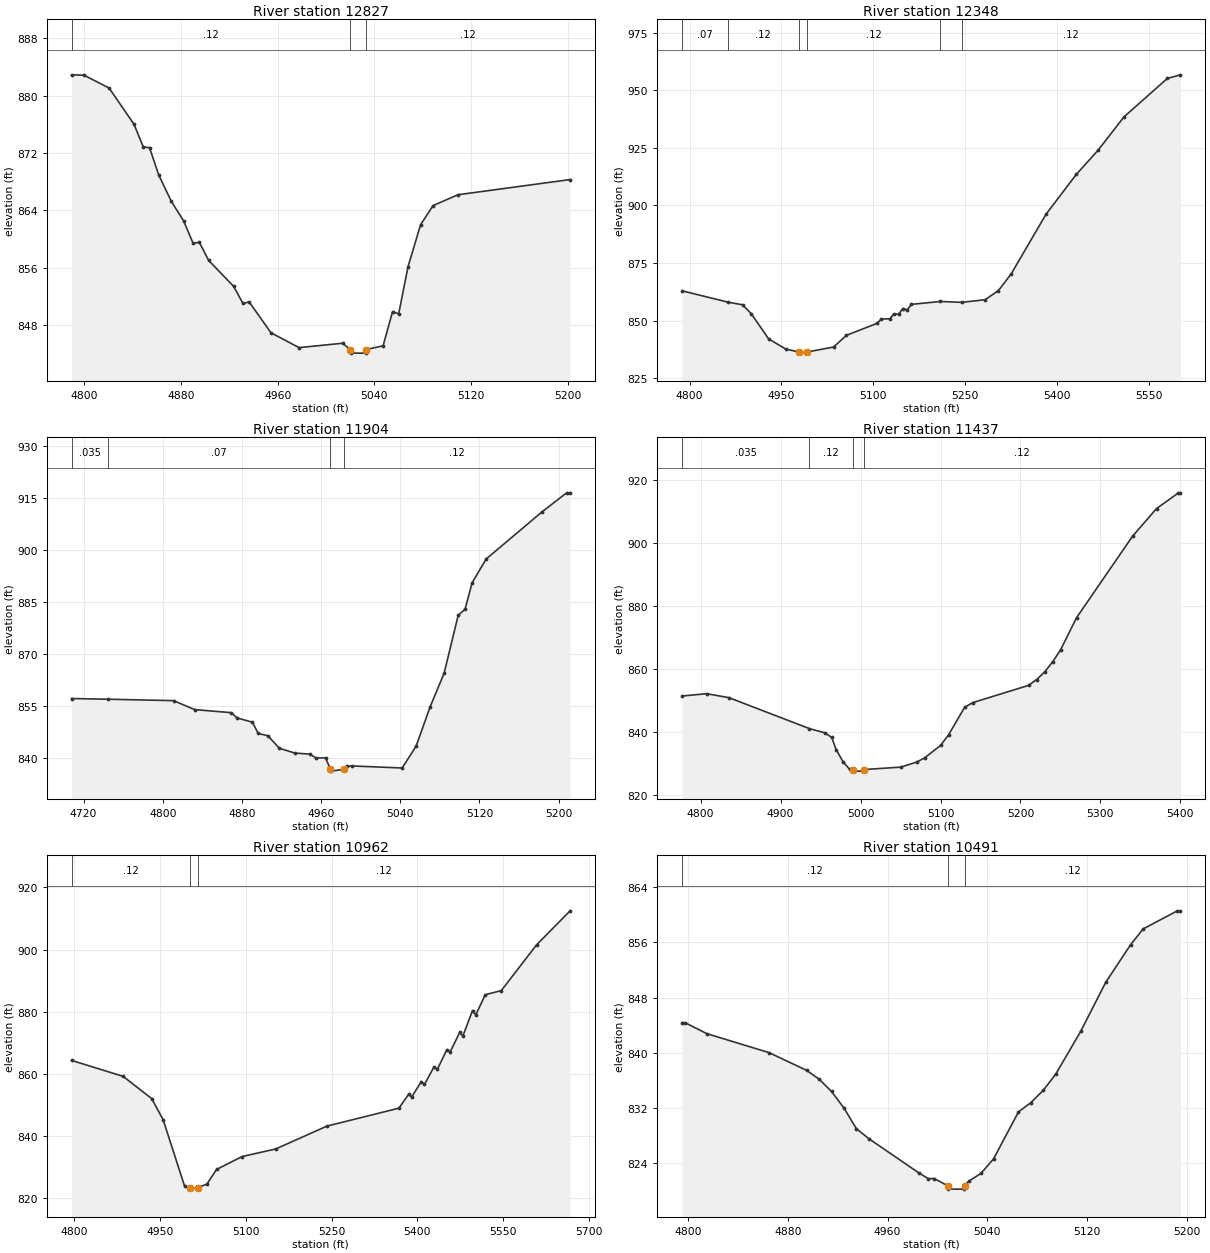
Type RM Length L Ch R = 1 ,12827   ,479,479,479
BEGIN DESCRIPTION:
Guadalupe Tributary 23 26.0
END DESCRIPTION:
XS GIS Cut Line= 3
      2236375.04     13872675.01        2236175.       13872625.
      2235974.95     13872675.01
#Sta/Elev= 30
  4789.5  882.91  4799.8  882.86  4820.5  881.07  4841.1  876.02  4848.8  872.85
    4854  872.73  4861.7  868.88    4872  865.25  4882.3  862.48    4890   859.4
  4895.2  859.52  4902.9     857  4923.5  853.39  4931.3  850.99  4936.4  851.21
  4954.5  846.89  4977.7  844.83  5013.7  845.44    5020  844.56  5020.5  844.06
  5032.7  844.06  5033.2  844.56  5047.2  845.08    5055  849.84  5060.1  849.55
  5067.8  856.11  5078.2  861.98  5088.5  864.65  5109.1  866.17  5201.9  868.29
#Mann= 3 ,-1 , 0
  4789.5     .12       0    5020     .05       0  5033.2     .12       0
Bank Sta=5020,5033.2
XS Rating Curve= 0 ,0
Exp/Cntr=0.3,0.1

Type RM Length L Ch R = 1 ,12348   ,444,444,444
BEGIN DESCRIPTION:
Guadalupe Tributary 23 25.0
END DESCRIPTION:
XS GIS Cut Line= 3
      2236325.03     13872325.03        2236175.       13872175.
      2235774.97     13871724.97
#Sta/Elev= 30
  4787.7  862.92  4862.2  858.04  4886.7  856.85  4900.9     853  4929.2  842.08
  4957.5   837.6  4979.1  836.38  4979.6  835.88  4992.4  836.38  5035.4  838.53
  5056.3  843.61  5106.5  848.82  5113.2  850.64  5127.4  850.81  5134.1  852.93
  5141.6  852.71  5148.3  855.24  5155.8  854.64  5162.5  857.04  5209.8  858.29
  5244.5  857.91  5282.9  859.06  5304.7  863.04  5325.6  870.32  5382.4  896.16
  5431.8  913.43  5467.7  924.02  5509.6  938.36  5580.6  955.09    5602  956.64
#Mann= 6 ,-1 , 0
  4787.7     .07       0  4862.2     .12       0  4979.1     .05       0
  4992.4     .12       0  5209.8     .07       0  5244.5     .12       0
Bank Sta=4979.1,4992.4
XS Rating Curve= 0 ,0
Exp/Cntr=0.3,0.1

Type RM Length L Ch R = 1 ,11904   ,467,467,467
BEGIN DESCRIPTION:
Guadalupe Tributary 23 24.0
END DESCRIPTION:
XS GIS Cut Line= 3
      2236375.02     13872025.03        2236225.       13871775.
      2236075.01     13871625.01
#Sta/Elev= 30
  4707.9  857.04  4744.7  856.84  4810.9  856.43  4832.3  853.84  4869.3  852.96
  4875.1  851.44  4890.6  850.21  4896.5  846.95  4906.2  846.31  4917.8  842.68
  4933.4   841.3  4948.9  840.98  4954.8  839.85  4964.5  839.92  4969.5  836.58
    4970  836.08  4982.9  836.58  4985.9  837.46  4991.7  837.57  5041.9  836.99
    5056  843.29  5070.2  854.67  5084.3  864.34  5098.5  881.02  5105.5  882.87
  5112.6  890.46  5126.8  897.33  5183.3  910.95  5208.1  916.43  5211.6  916.43
#Mann= 4 ,-1 , 0
  4707.9    .035       0  4744.7     .07       0  4969.5     .05       0
  4982.9     .12       0
Bank Sta=4969.5,4982.9
XS Rating Curve= 0 ,0
Exp/Cntr=0.3,0.1

Type RM Length L Ch R = 1 ,11437   ,475,475,475
BEGIN DESCRIPTION:
Guadalupe Tributary 23 23.0
END DESCRIPTION:
XS GIS Cut Line= 3
      2236625.01     13871675.02        2236525.       13871475.
      2236125.03       13871475.
#Sta/Elev= 30
  4776.6   851.3  4807.4  852.04  4835.3  850.79    4936  840.96  4955.5   839.6
  4963.9  838.16  4969.5  834.26  4977.9  830.51  4986.3  828.03  4990.7  827.96
  4991.2  827.46  5003.6  827.46  5004.1  827.96  5050.2  828.73  5070.2  830.33
  5080.2  831.68  5100.2  835.65  5110.2  839.03  5130.2  847.72  5140.2   849.2
  5210.2  854.68  5220.2  856.53  5230.2  858.91  5240.2  862.12  5250.2  865.96
  5270.2  876.17  5340.2  902.02  5370.2   910.8  5397.7   915.8  5400.2   915.8
#Mann= 4 ,-1 , 0
  4776.6    .035       0    4936     .12       0  4990.7     .05       0
  5004.1     .12       0
Bank Sta=4990.7,5004.1
XS Rating Curve= 0 ,0
Exp/Cntr=0.3,0.1

Type RM Length L Ch R = 1 ,10962   ,471,471,471
BEGIN DESCRIPTION:
Guadalupe Tributary 23 22.0
END DESCRIPTION:
XS GIS Cut Line= 3
      2236925.05       13871075.        2236725.       13871075.
      2236124.97     13871375.02
#Sta/Elev= 30
  4795.9  864.33  4885.9   859.2  4935.9  852.03  4955.9  845.22  4993.4  823.82
  5003.1  823.42  5003.6  822.92  5016.7  823.42  5032.3  824.53  5049.1  829.24
  5093.8   833.4  5152.5  835.84  5241.9  843.19  5367.7  848.96  5384.5  853.37
  5390.1  852.61  5406.8  857.48  5412.4  856.58  5429.2  862.32  5434.8  861.41
  5451.5  867.81  5457.1  867.01  5473.9  873.32  5479.5  872.18  5496.3  880.37
  5501.9  878.94  5518.6  885.47  5546.6  886.79  5608.1  901.48  5666.8  912.45
#Mann= 3 ,-1 , 0
  4795.9     .12       0  5003.1     .05       0  5016.7     .12       0
Bank Sta=5003.1,5016.7
XS Rating Curve= 0 ,0
Exp/Cntr=0.3,0.1

Type RM Length L Ch R = 1 ,10491   ,449,449,449
BEGIN DESCRIPTION:
Guadalupe Tributary 23 21.0
END DESCRIPTION:
XS GIS Cut Line= 3
      2236724.99       13870675.        2236525.       13870675.
      2236324.99       13870675.
#Sta/Elev= 30
    4795  844.36  4797.5  844.36    4815  842.77    4865  840.01    4895  837.45
    4905  836.18    4915  834.39    4925  831.98    4935  828.98    4945  827.54
    4985  822.59  4992.5  821.76  4997.5  821.76  5008.1  820.73  5008.6  820.23
  5021.3  820.23  5021.8  820.73    5025  821.36    5035  822.53    5045  824.62
    5065  831.42    5075  832.78    5085  834.58    5095  836.93    5115  843.13
    5135  850.21    5155  855.68    5165  857.95  5192.5  860.58    5195  860.58
#Mann= 3 ,-1 , 0
    4795     .12       0  5008.1     .05       0  5021.8     .12       0
Bank Sta=5008.1,5021.8
XS Rating Curve= 0 ,0
Exp/Cntr=0.3,0.1