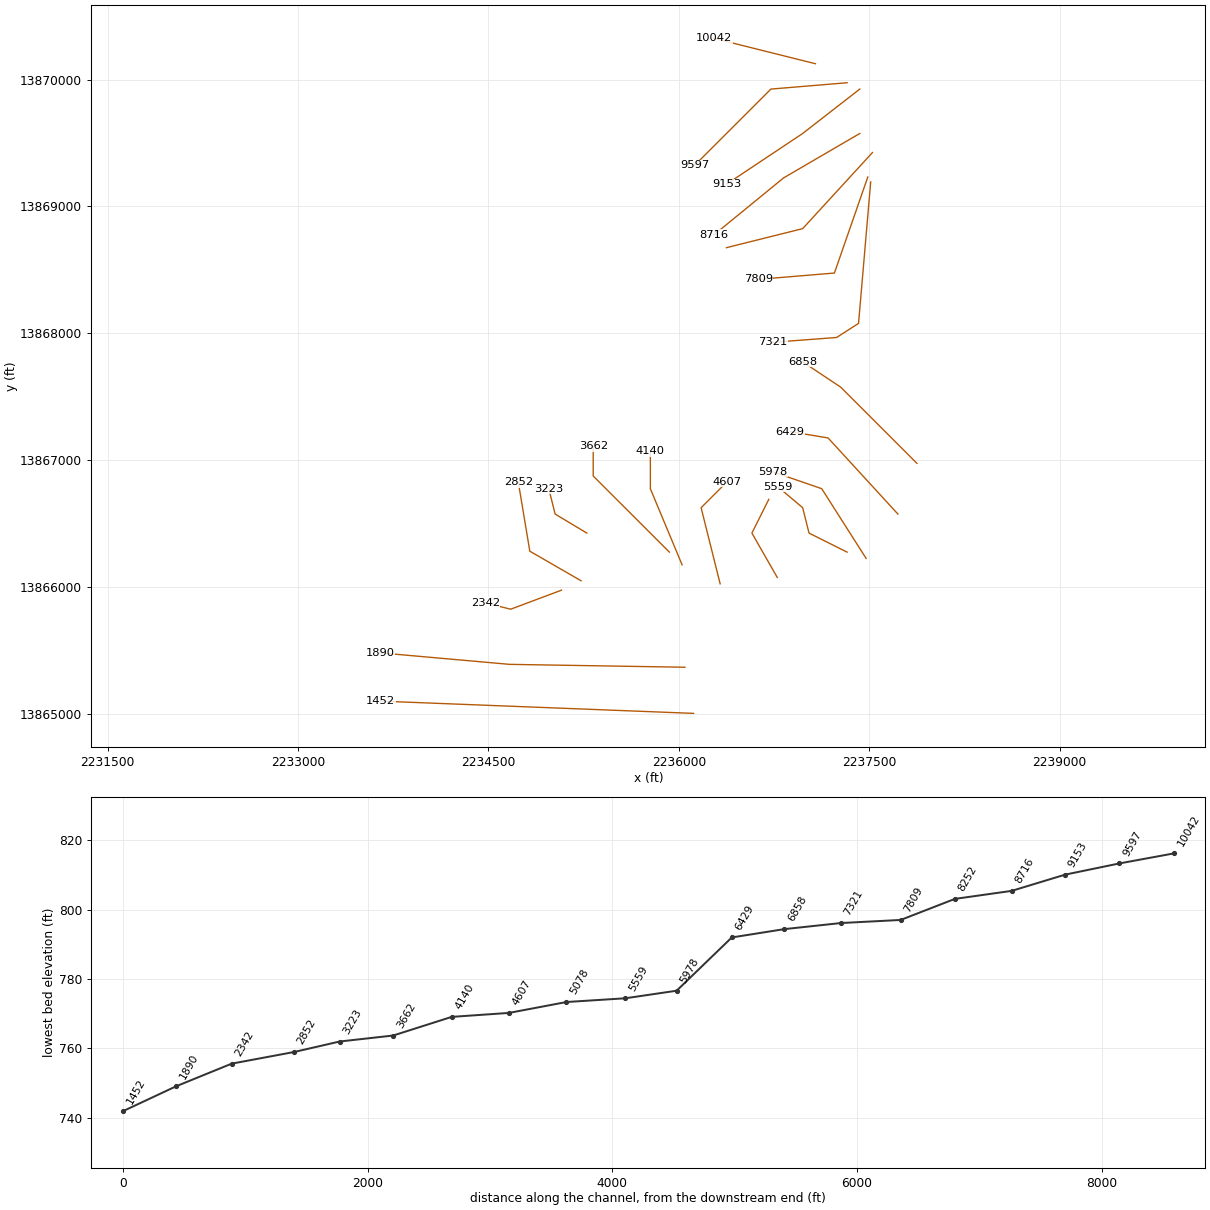
HEC-RAS study Guadalupe Tributary 23.prj: Guadalupe Tributary 23 Base Level Engineering

--- Guadalupe Tributary 23.g01 (geometry) --- (continued)

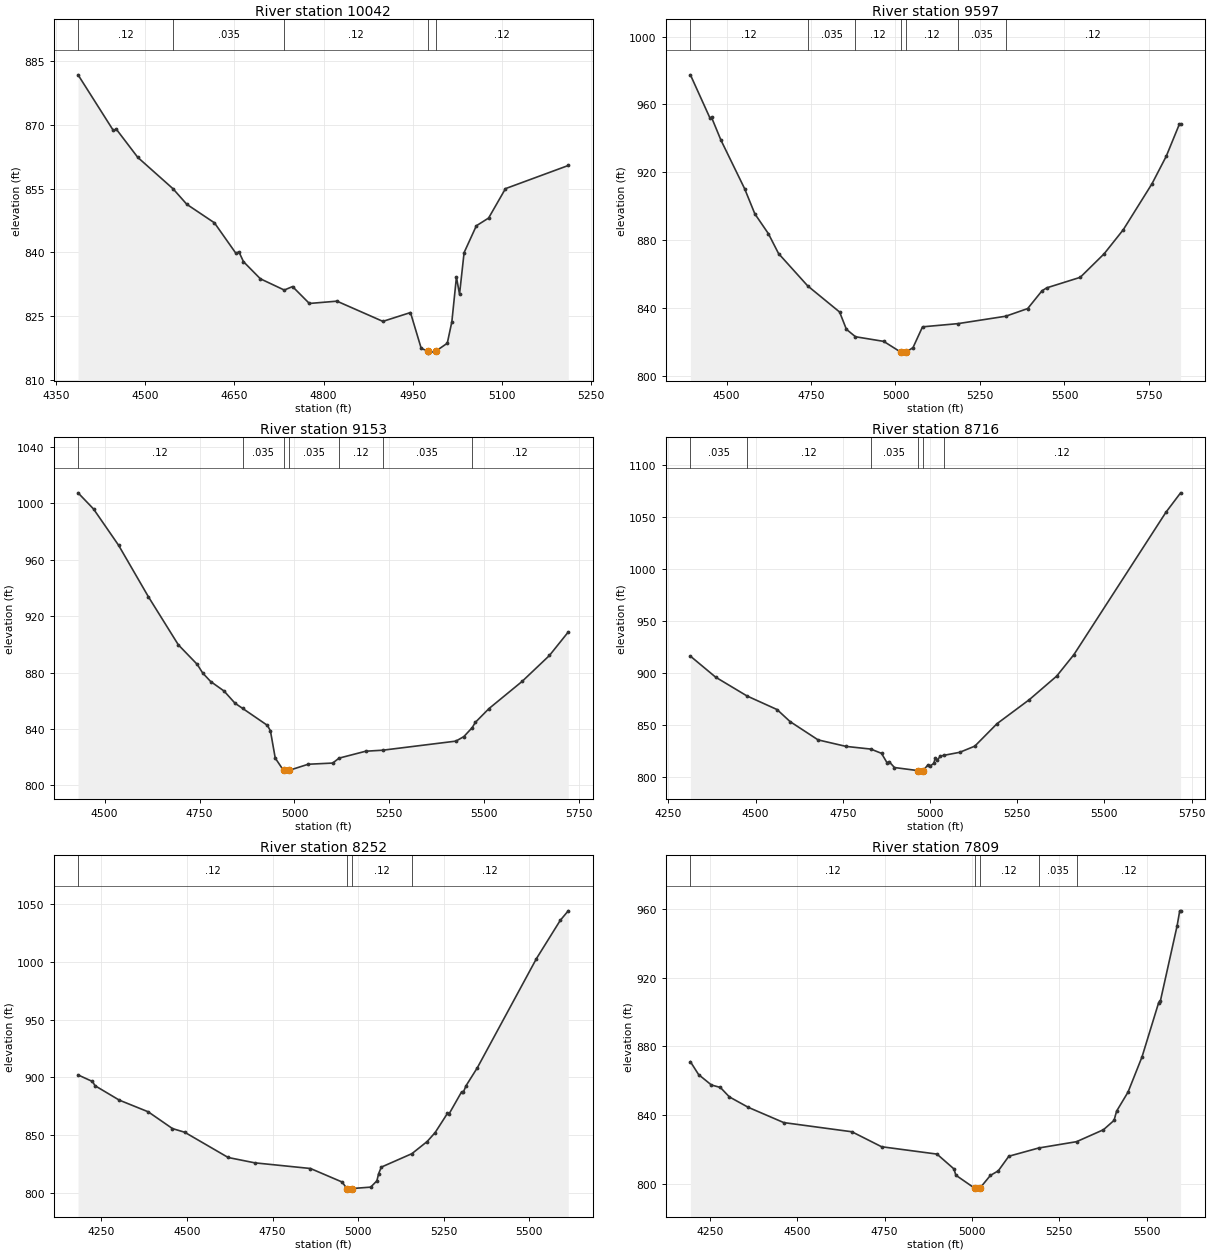
Type RM Length L Ch R = 1 ,10042   ,445,445,445
BEGIN DESCRIPTION:
Guadalupe Tributary 23 20.0
END DESCRIPTION:
XS GIS Cut Line= 3
      2237075.03     13870124.99        2236475.       13870275.
      2236275.05     13870324.99
#Sta/Elev= 30
  4386.9   881.8  4446.2   868.7  4451.4  868.97  4487.4  862.35  4546.6  854.97
  4569.9  851.29  4616.3  846.94  4652.4  839.76  4657.5   840.1  4665.2  837.78
  4693.6  833.75  4733.8   831.1  4747.7  831.92    4776  827.94  4822.4  828.48
  4899.7  823.72  4946.1   825.8  4964.2  817.34  4975.4  816.74  4975.9  816.24
  4989.1  816.74    5008  818.57  5015.7  823.63  5023.4  834.15  5028.6  830.12
  5036.3  839.92  5056.9  846.24  5077.5  848.06  5105.9  854.99  5211.5  860.44
#Mann= 5 ,-1 , 0
  4386.9     .12       0  4546.6    .035       0  4733.8     .12       0
  4975.4     .05       0  4989.1     .12       0
Bank Sta=4975.4,4989.1
XS Rating Curve= 0 ,0
Exp/Cntr=0.3,0.1

Type RM Length L Ch R = 1 ,9597    ,444,444,444
BEGIN DESCRIPTION:
Guadalupe Tributary 23 19.0
END DESCRIPTION:
XS GIS Cut Line= 3
      2237325.01       13869975.        2236725.       13869925.
      2236125.01     13869325.01
#Sta/Elev= 30
  4393.1  977.43  4450.8  952.03  4455.8  952.28  4483.4  938.96  4553.7  910.23
  4583.8  895.47  4623.9  883.78    4654  872.05  4740.4  852.95  4834.6  837.59
  4854.7   827.4  4881.6  823.01  4965.1  820.28  5016.4  813.85  5016.9  813.35
  5030.6  813.85  5051.8   816.6    5080  828.85  5184.8  830.74  5326.3  835.11
  5391.2  839.62  5433.6  850.11  5447.7  851.85  5546.7  858.04  5617.4  871.91
    5674  886.09  5758.9  913.16  5801.3  929.47  5840.2  948.41  5843.7  948.41
#Mann= 7 ,-1 , 0
  4393.1     .12       0  4740.4    .035       0  4881.6     .12       0
  5016.4     .05       0  5030.6     .12       0  5184.8    .035       0
  5326.3     .12       0
Bank Sta=5016.4,5030.6
XS Rating Curve= 0 ,0
Exp/Cntr=0.3,0.1

Type RM Length L Ch R = 1 ,9153    ,437,437,437
BEGIN DESCRIPTION:
Guadalupe Tributary 23 18.0
END DESCRIPTION:
XS GIS Cut Line= 3
      2237424.97     13869924.98        2236975.       13869575.
      2236374.97     13869174.98
#Sta/Elev= 30
    4430 1007.52  4470.7   996.1  4536.7  970.36  4615.5   933.7  4694.2  899.69
    4744  885.81  4758.4  879.68  4779.3  873.67  4814.5  866.95  4843.5  858.26
  4863.6  854.59  4928.6   842.6  4936.7  838.72  4949.4  819.36  4971.2  810.61
  4971.7  810.11  4985.5  810.61  5036.1  814.99  5100.7  815.83  5117.5  819.32
  5187.8  824.24  5232.1  824.94  5425.2  831.39  5446.2   834.6  5468.3  840.99
  5476.3  844.66  5512.3  854.46  5599.5  873.71  5671.6  892.13  5721.2  908.79
#Mann= 7 ,-1 , 0
    4430     .12       0  4863.6    .035       0  4971.2    .035       0
  4985.5    .035       0  5117.5     .12       0  5232.1    .035       0
  5468.3     .12       0
Bank Sta=4971.2,4985.5
XS Rating Curve= 0 ,0
Exp/Cntr=0.3,0.1

Type RM Length L Ch R = 1 ,8716    ,464,464,464
BEGIN DESCRIPTION:
Guadalupe Tributary 23 17.0
END DESCRIPTION:
XS GIS Cut Line= 3
      2237425.04     13869575.02        2236825.       13869225.
        2236275.       13868775.
#Sta/Elev= 30
  4313.1  916.01  4385.5  895.78  4475.5  877.69  4561.6  864.62  4598.8  853.08
  4679.1  835.47  4759.3   829.2  4830.5  826.61    4861  822.51  4876.7  813.53
  4882.5  814.62  4898.2  808.88  4965.5  805.92    4966  805.42  4979.8  805.92
  4994.1  811.37  4999.9  810.27    5011  812.91  5014.9  817.86  5021.4  816.05
  5029.3  819.75  5039.2  820.58  5085.3  823.53  5128.4  829.44  5192.2  851.08
  5284.8  874.18  5363.1   896.8  5412.6  917.49    5676 1054.22  5718.4 1073.07
#Mann= 6 ,-1 , 0
  4313.1    .035       0  4475.5     .12       0  4830.5    .035       0
  4965.5    .035       0  4979.8    .035       0  5039.2     .12       0
Bank Sta=4965.5,4979.8
XS Rating Curve= 0 ,0
Exp/Cntr=0.3,0.1

Type RM Length L Ch R = 1 ,8252    ,443,443,443
BEGIN DESCRIPTION:
Guadalupe Tributary 23 16.0
END DESCRIPTION:
XS GIS Cut Line= 3
      2237524.98     13869424.98        2236975.       13868825.
      2236374.98       13868675.
#Sta/Elev= 30
  4181.7   902.1  4223.9  896.41  4231.3  892.76  4302.2  880.26  4386.7  870.14
  4457.6   855.6  4493.4  852.41  4620.4  830.53  4698.1   825.9  4860.9  820.99
  4953.4  809.26  4967.2  803.61  4967.7  803.11  4981.5  803.61  5036.8  804.84
  5054.9   810.3    5060  816.48  5067.8  822.18  5157.2  833.85  5201.8  844.37
    5225  852.09    5261  868.71  5266.2  868.52  5302.3  887.35  5307.4     887
  5315.2  892.62  5348.7  908.47  5521.3 1003.02  5590.9 1036.17  5614.1 1044.36
#Mann= 4 ,-1 , 0
  4181.7     .12       0  4967.2    .035       0  4981.5     .12       0
  5157.2     .12       0
Bank Sta=4967.2,4981.5
XS Rating Curve= 0 ,0
Exp/Cntr=0.3,0.1

Type RM Length L Ch R = 1 ,7809    ,488,488,488
BEGIN DESCRIPTION:
Guadalupe Tributary 23 15.0
END DESCRIPTION:
XS GIS Cut Line= 3
      2237487.93     13869231.66        2237225.       13868475.
      2236625.02       13868425.
#Sta/Elev= 30
  4194.4  871.14  4217.9  863.63  4254.4   857.6  4280.2  856.14    4306  850.65
  4360.2  844.58  4461.6  835.72  4656.7  830.38  4741.6  821.68  4900.2   817.4
  4948.8  808.77  4954.1  805.14  5008.3  797.53  5008.8  797.03  5022.7  797.53
  5053.1     805  5075.7  807.68  5105.8  816.15  5191.2  820.94  5299.7  824.62
  5376.8  831.58  5406.9  836.98  5414.4  842.41    5447  853.45  5487.1  873.95
  5534.8  905.54  5539.8   906.6  5587.5  950.13    5595  958.85  5597.5  958.85
#Mann= 5 ,-1 , 0
  4194.4     .12       0  5008.3     .05       0  5022.7     .12       0
  5191.2    .035       0  5299.7     .12       0
Bank Sta=5008.3,5022.7
XS Rating Curve= 0 ,0
Exp/Cntr=0.3,0.1

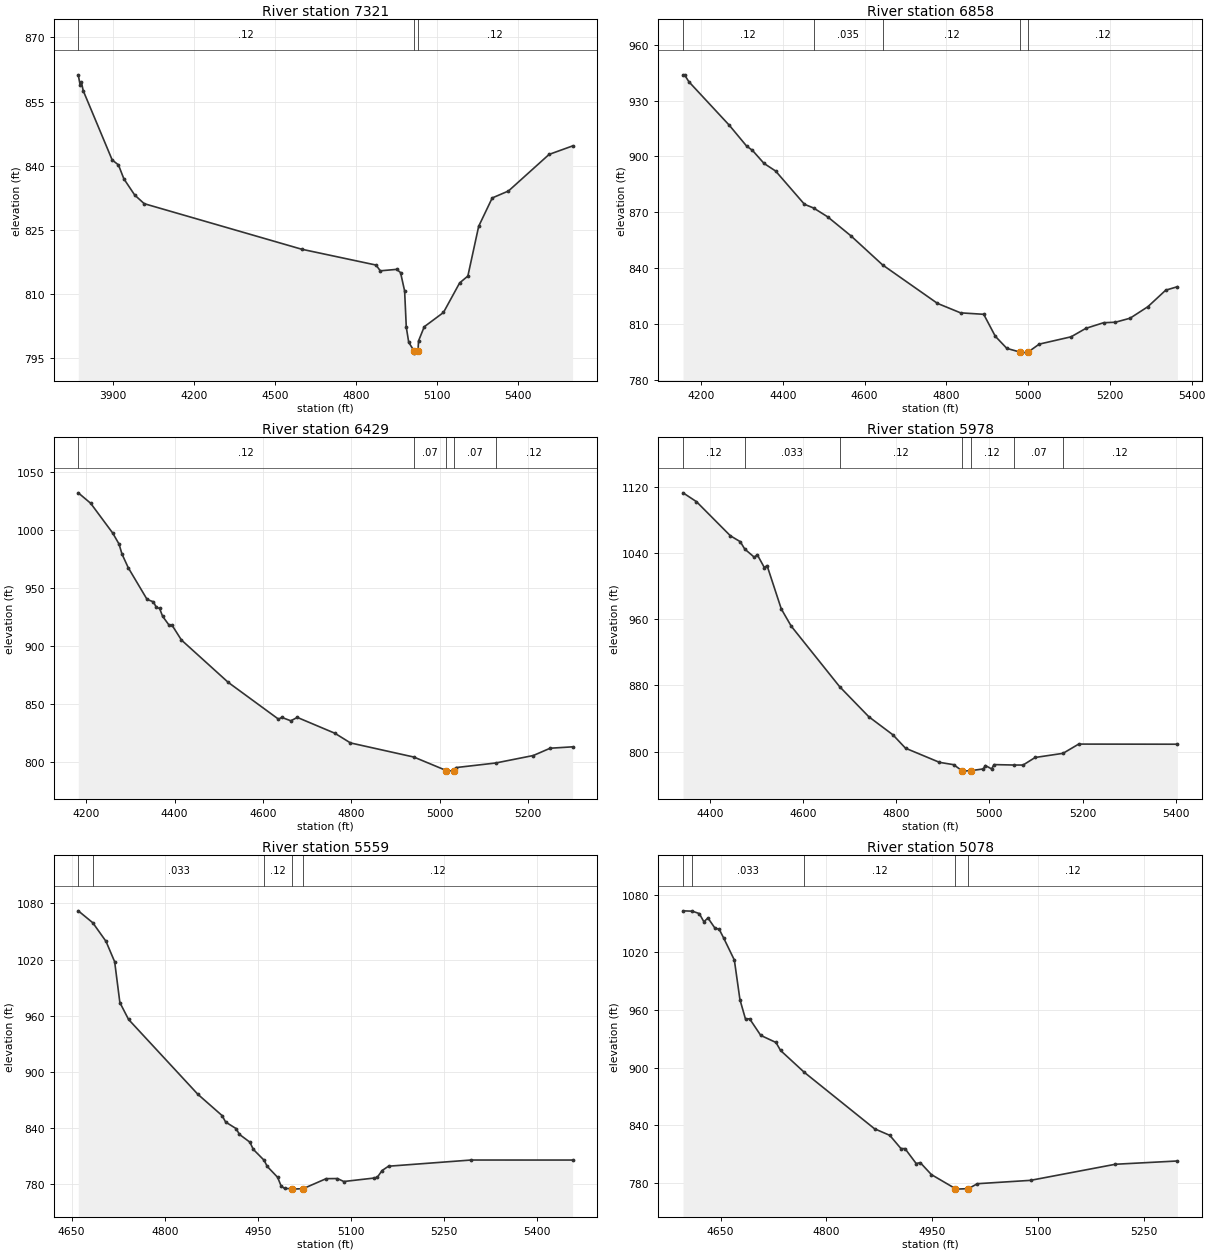
Type RM Length L Ch R = 1 ,7321    ,463,463,463
BEGIN DESCRIPTION:
A19247
END DESCRIPTION:
XS GIS Cut Line= 4
      2237510.91     13869193.25      2237415.11     13868078.13
      2237242.66     13867966.99      2236738.39     13867928.79
#Sta/Elev= 30
    3771  861.26  3777.9  858.87  3782.9  859.47  3789.3  857.56  3896.6  841.34
  3919.8  840.18  3939.9  836.92    3980  833.13  4015.2  831.11  4598.3  820.45
  4873.3  816.75  4889.3   815.4  4949.8  815.74  4964.2  814.99  4979.3  810.69
  4985.5  802.19  4994.5  798.67  5014.4  796.64  5014.9  796.14  5028.8  796.64
  5030.8  798.99  5051.9  802.31  5123.1  805.65  5183.1  812.58  5213.4  814.17
  5253.5  825.82  5303.6  832.45  5363.8  834.08  5514.2  842.64  5601.1  844.62
#Mann= 3 ,-1 , 0
    3771     .12       0  5014.4     .05       0  5028.8     .12       0
Bank Sta=5014.4,5028.8
XS Rating Curve= 0 ,0
Exp/Cntr=0.3,0.1

Type RM Length L Ch R = 1 ,6858    ,429,429,429
BEGIN DESCRIPTION:
Guadalupe Tributary 23 14.0
END DESCRIPTION:
XS GIS Cut Line= 3
      2237875.01     13866974.99        2237275.       13867575.
        2236975.       13867775.
#Sta/Elev= 30
    4156  943.83  4159.6  943.83  4170.2  940.13  4269.2  916.73  4311.6  905.53
  4325.7  903.28    4354  896.26  4382.3  892.19    4453   874.3  4475.2  872.32
  4509.6  867.59  4566.1  857.46  4644.3  841.71  4778.3  821.09  4834.8  816.01
  4891.4  815.23  4919.7  803.45    4948  796.92  4981.3  794.88  4981.8  794.38
  4999.6  794.88  5027.1  799.21  5105.2  803.15  5141.3  807.69  5184.8  810.72
  5213.4  810.97  5249.4  813.13    5293  819.32  5336.6  828.19  5365.1  830.04
#Mann= 5 ,-1 , 0
    4156     .12       0  4475.2    .035       0  4644.3     .12       0
  4981.3     .05       0  4999.6     .12       0
Bank Sta=4981.3,4999.6
XS Rating Curve= 0 ,0
Exp/Cntr=0.3,0.1

Type RM Length L Ch R = 1 ,6429    ,451,451,451
BEGIN DESCRIPTION:
Guadalupe Tributary 23 13.0
END DESCRIPTION:
XS GIS Cut Line= 3
      2237724.98     13866575.02        2237175.       13867175.
      2236874.95     13867225.01
#Sta/Elev= 30
    4182 1031.74    4210 1022.77    4260  997.04  4274.2  987.65  4280.9  979.02
  4295.1   967.2  4337.7  939.89  4351.9  937.86  4358.6  933.07    4366   932.1
  4372.8  925.38    4387  917.96  4394.4  917.52  4415.4  904.93  4521.4  868.39
  4634.9  836.76  4642.3  838.26  4662.9  835.35  4677.4  838.27  4762.5   824.6
  4797.7  816.28  4941.1  804.11  5014.6  792.48  5015.1  791.98    5033  792.48
  5036.5  795.04    5126  798.97  5211.3  805.43  5249.4  811.71  5300.1  812.91
#Mann= 5 ,-1 , 0
    4182     .12       0  4941.1     .07       0  5014.6     .05       0
    5033     .07       0    5126     .12       0
Bank Sta=5014.6,5033
XS Rating Curve= 0 ,0
Exp/Cntr=0.3,0.1

Type RM Length L Ch R = 1 ,5978    ,419,419,419
BEGIN DESCRIPTION:
Guadalupe Tributary 23 12.0
END DESCRIPTION:
XS GIS Cut Line= 3
        2237475.       13866225.        2237125.       13866775.
      2236738.41     13866908.75
#Sta/Elev= 30
  4342.6 1112.54  4371.4 1101.86  4444.2 1060.67  4465.4 1053.56    4475 1044.66
  4495.8 1034.67  4501.8 1037.95    4517 1022.38  4522.9 1024.73  4553.4  972.44
  4574.6  951.74  4678.6   878.6  4741.4   842.2    4793  820.45  4820.1  804.27
  4892.9  787.22  4923.4  784.38  4941.3   777.1  4941.8   776.6  4959.7   777.1
  4986.9  779.26  4991.6  783.39  5004.8  779.25  5010.1  784.48  5052.8  783.96
  5072.4  783.95  5098.3  793.07  5158.1  798.08  5191.8  809.24  5403.6  809.09
#Mann= 7 ,-1 , 0
  4342.6     .12       0    4475    .033       0  4678.6     .12       0
  4941.3     .05       0  4959.7     .12       0  5052.8     .07       0
  5158.1     .12       0
Bank Sta=4941.3,4959.7
XS Rating Curve= 0 ,0
Exp/Cntr=0.3,0.1

Type RM Length L Ch R = 1 ,5559    ,481,481,481
BEGIN DESCRIPTION:
Guadalupe Tributary 23 11.0
END DESCRIPTION:
XS GIS Cut Line= 4
      2237325.01     13866274.99        2237025.       13866425.
        2236975.       13866625.      2236779.76     13866789.84
#Sta/Elev= 30
  4660.6 1072.08    4684 1059.34  4705.3 1039.48  4719.3 1017.62  4727.7  973.96
  4741.7  955.92  4853.5  875.84  4892.6  853.05  4898.2   846.2    4915  839.23
  4920.6  832.92  4937.3  824.67  4942.9  816.92  4960.3  805.27  4965.3  798.72
    4982  787.14  4987.6  777.99  4993.2   775.1  5004.9  774.92  5005.4  774.42
  5023.3  774.92  5060.4  785.63  5078.5  785.73  5088.8  782.57  5137.8  786.28
  5142.9  787.18  5150.6  794.34  5160.9  798.93  5293.9  805.54  5457.7  805.53
#Mann= 5 ,-1 , 0
  4660.6     .12       0    4684    .033       0  4960.3     .12       0
  5004.9     .05       0  5023.3     .12       0
Bank Sta=5004.9,5023.3
XS Rating Curve= 0 ,0
Exp/Cntr=0.3,0.1

Type RM Length L Ch R = 1 ,5078    ,471,471,471
BEGIN DESCRIPTION:
Guadalupe Tributary 23 10.0
END DESCRIPTION:
XS GIS Cut Line= 4
      2236774.99     13866075.01        2236575.       13866425.
        2236675.       13866625.      2236708.05     13866691.09
#Sta/Elev= 30
  4596.9 1063.38  4610.1    1063  4619.9 1060.52  4626.4 1051.99  4632.2  1055.9
  4642.2 1045.25    4648 1044.25  4654.5 1034.99  4669.6 1012.09  4677.5  970.89
  4685.4  950.51  4691.2   950.9    4707  933.58  4728.6  926.17  4735.1  917.85
  4768.6  895.16  4868.3  836.24  4889.9  829.39  4905.7  815.63  4911.5  815.54
  4927.3  800.03  4933.1  800.95  4948.9  788.48  4982.9  773.84  4983.4  773.34
  5001.3  773.84    5014  778.99  5089.4  782.49  5209.6  799.26  5297.5  802.67
#Mann= 5 ,-1 , 0
  4596.9     .12       0  4610.1    .033       0  4768.6     .12       0
  4982.9     .05       0  5001.3     .12       0
Bank Sta=4982.9,5001.3
XS Rating Curve= 0 ,0
Exp/Cntr=0.3,0.1

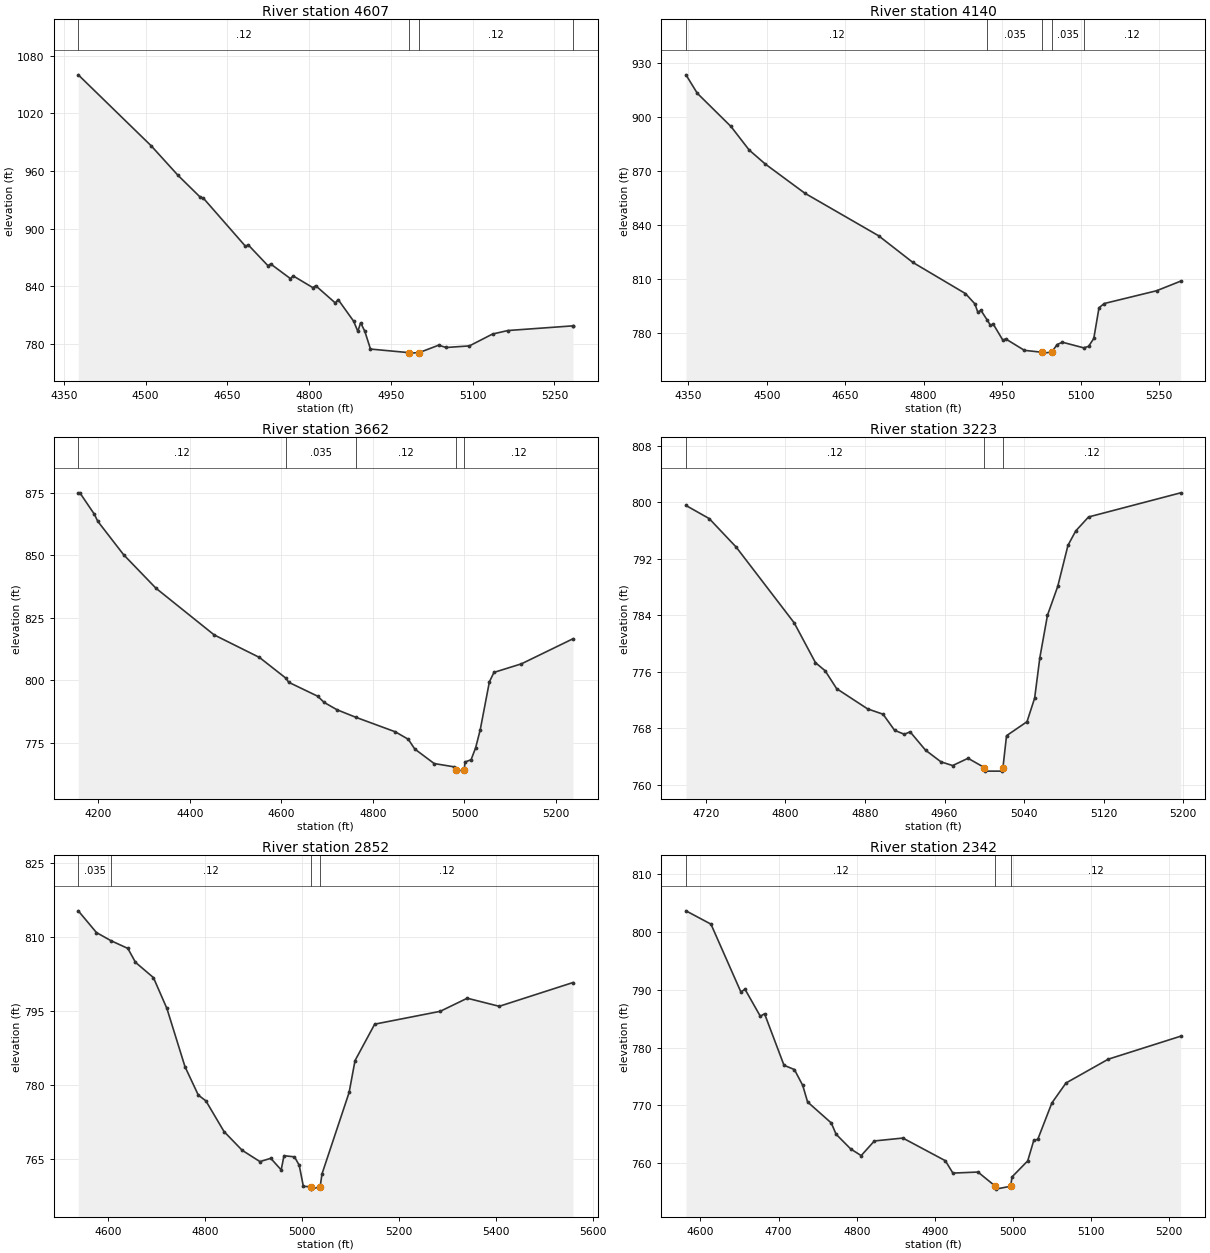
Type RM Length L Ch R = 1 ,4607    ,467,467,467
BEGIN DESCRIPTION:
Guadalupe Tributary 23 9.0
END DESCRIPTION:
XS GIS Cut Line= 4
        2236325.       13866025.        2236175.       13866625.
        2236325.       13866775.      2236379.38     13866829.38
#Sta/Elev= 30
  4376.5 1060.21  4510.5  986.09  4559.5  955.43  4600.7  932.45  4605.8   931.8
  4683.2  881.54  4688.3  882.97  4724.4  861.33  4729.5  863.09  4765.6  847.87
  4770.8  850.65  4806.8  838.44    4812  840.47  4848.1  822.42  4853.2  826.01
  4881.6  803.47  4889.3  792.88  4894.5  801.86  4902.2  792.81  4912.5  774.43
  4983.2  770.69  4983.7  770.19  5001.6  770.69  5037.4  778.43  5051.5  776.07
    5094  777.73  5136.4  790.08  5164.7  793.75  5283.8  798.61    5284  798.61
#Mann= 4 ,-1 , 0
  4376.5     .12       0  4983.2     .05       0  5001.6     .12       0
  5283.8    .035       0
Bank Sta=4983.2,5001.6
XS Rating Curve= 0 ,0
Exp/Cntr=0.3,0.1

Type RM Length L Ch R = 1 ,4140    ,478,478,478
BEGIN DESCRIPTION:
Guadalupe Tributary 23 8.0
END DESCRIPTION:
XS GIS Cut Line= 4
      2236024.99     13866175.01        2235775.       13866775.
        2235775.       13866975.        2235775.     13867071.21
#Sta/Elev= 30
  4345.4  923.68  4367.1  913.42  4431.5  894.97  4466.2  881.93  4497.1  874.12
  4572.9  857.88  4713.7  834.29  4779.3  819.46    4880  802.13  4897.9  796.46
  4903.8  791.64  4909.3  792.93  4921.4  787.51  4927.7  784.54  4933.1   785.2
  4951.5  776.23  4956.9  776.96  4992.7   770.6  5026.1  769.55  5026.6  769.05
  5044.6  769.55  5055.4  773.84  5065.4  775.11  5105.8  772.01  5115.4  772.79
  5125.4  777.19  5135.4  794.26  5145.4  796.61  5245.4   803.7  5291.6  809.05
#Mann= 5 ,-1 , 0
  4345.4     .12       0  4921.4    .035       0  5026.1    .035       0
  5044.6    .035       0  5105.8     .12       0
Bank Sta=5026.1,5044.6
XS Rating Curve= 0 ,0
Exp/Cntr=0.3,0.1

Type RM Length L Ch R = 1 ,3662    ,439,439,439
BEGIN DESCRIPTION:
Guadalupe Tributary 23 7.0
END DESCRIPTION:
XS GIS Cut Line= 4
      2235924.98     13866275.02        2235325.       13866875.
        2235325.       13867075.        2235325.      13867107.7
#Sta/Elev= 30
    4156  874.89  4159.5  874.89  4191.3  866.29  4198.4  863.57    4255  850.18
  4325.7  836.78    4453  818.11    4552   809.1  4610.4  800.72  4615.6   799.2
  4679.2  793.61  4693.4  791.12  4721.7  788.18  4762.7  785.18  4848.9  779.38
  4877.2   776.4  4891.4  772.51  4933.8   766.7  4976.2  765.42  4981.1  764.17
  4981.6  763.67  4999.7  764.17    5001  767.28  5014.5  768.24  5024.5  773.03
  5034.5  780.23  5054.5  799.37  5064.5  803.13  5124.5  806.55  5237.2  816.57
#Mann= 5 ,-1 , 0
    4156     .12       0  4610.4    .035       0  4762.7     .12       0
  4981.1     .05       0  4999.7     .12       0
Bank Sta=4981.1,4999.7
XS Rating Curve= 0 ,0
Exp/Cntr=0.3,0.1

Type RM Length L Ch R = 1 ,3223    ,371,371,371
BEGIN DESCRIPTION:
Guadalupe Tributary 23 6.0
END DESCRIPTION:
XS GIS Cut Line= 3
      2235275.03     13866424.98        2235025.       13866575.
      2234975.01     13866774.97
#Sta/Elev= 30
  4699.9  799.56  4723.3   797.7  4750.5  793.65  4808.8  782.93  4830.2  777.29
  4839.9  776.15  4851.5  773.61  4882.6  770.75  4898.2  769.99  4909.8  767.71
  4919.6  767.15  4925.4   767.5  4940.9   764.9  4956.5  763.24  4968.2  762.72
  4983.7  763.75  5000.2  762.43  5000.7  761.93  5018.3  761.93  5018.8  762.43
  5022.4  766.95    5043  768.93  5050.7  772.28  5055.9  777.99  5063.6  784.02
  5073.9  788.09  5084.2  793.91    5092  795.95  5104.9  797.93  5197.6  801.35
#Mann= 3 ,-1 , 0
  4699.9     .12       0  5000.2     .05       0  5018.8     .12       0
Bank Sta=5000.2,5018.8
XS Rating Curve= 0 ,0
Exp/Cntr=0.3,0.1

Type RM Length L Ch R = 1 ,2852    ,510,510,510
BEGIN DESCRIPTION:
A19246
END DESCRIPTION:
XS GIS Cut Line= 3
      2235229.06     13866049.34      2234825.61     13866282.32
      2234734.69     13866827.81
#Sta/Elev= 30
  4539.3  815.34  4576.7  810.94  4606.5  809.29  4641.4  807.72  4657.1   804.9
  4694.1   801.8  4721.8  795.55  4759.1  783.73  4786.5  777.98  4802.2   776.8
  4839.5  770.58  4876.8  766.79  4913.5  764.49  4935.7  765.16  4957.2  762.81
    4963  765.69  4984.6  765.45  4994.3  763.77  5002.9  759.46  5018.9  759.41
  5019.4  758.91  5037.5  759.41  5041.3  762.01  5097.1  778.51  5109.3  784.98
  5149.8  792.36  5284.6  794.96  5340.4  797.62  5406.3  795.98  5558.2   800.8
#Mann= 4 ,-1 , 0
  4539.3    .035       0  4606.5     .12       0  5018.9     .05       0
  5037.5     .12       0
Bank Sta=5018.9,5037.5
XS Rating Curve= 0 ,0
Exp/Cntr=0.3,0.1

Type RM Length L Ch R = 1 ,2342    ,452,452,452
BEGIN DESCRIPTION:
Guadalupe Tributary 23 5.0
END DESCRIPTION:
XS GIS Cut Line= 3
      2235074.98     13865974.99        2234675.       13865825.
      2234475.04     13865874.99
#Sta/Elev= 30
  4581.4  803.61  4613.4  801.31  4651.7   789.6    4657  790.07  4676.6   785.4
    4682  785.84  4706.9  776.94  4720.2   776.2  4730.9  773.46  4737.1   770.6
  4767.4  766.98  4773.6  765.03  4792.3  762.49  4805.7  761.34  4822.6  763.87
  4859.1  764.37  4913.4  760.46  4923.1  758.32  4955.2   758.5  4977.5  756.05
    4978  755.55    4997  756.05  4998.8  757.66  5018.9  760.43  5026.6  763.95
  5031.8  764.16  5049.8  770.43  5067.9  773.88    5122  777.99  5214.7  781.96
#Mann= 3 ,-1 , 0
  4581.4     .12       0  4977.5     .05       0    4997     .12       0
Bank Sta=4977.5,4997
XS Rating Curve= 0 ,0
Exp/Cntr=0.3,0.1

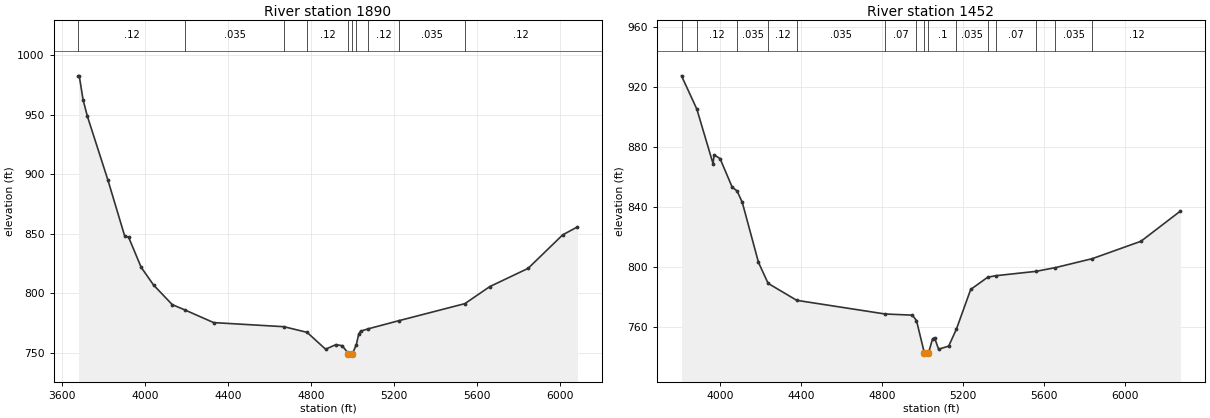
Type RM Length L Ch R = 1 ,1890    ,438,438,438
BEGIN DESCRIPTION:
A19245
END DESCRIPTION:
XS GIS Cut Line= 3
      2236047.25     13865367.52      2234666.51     13865390.25
      2233643.77     13865481.16
#Sta/Elev= 30
    3678  982.61  3681.6  982.61  3700.3  962.39  3720.3  949.02  3820.3  894.96
  3900.3  848.54  3920.3  846.99  3980.3  821.96  4040.3  807.04  4130.3  790.63
  4192.8  786.03  4330.3  775.51  4669.7  772.06  4781.1  767.33  4870.4  753.18
  4920.4  757.04  4950.4  756.12  4980.7  749.55  4981.2  749.05  5000.2  749.55
  5018.5  756.91  5030.4  765.89  5039.6  768.33  5077.1  770.33  5222.7  777.06
  5542.6  791.43  5662.8  805.73  5847.6  821.02  6014.2  849.11  6085.7  855.84
#Mann= 10 ,-1 , 0
    3678     .12       0  4192.8    .035       0  4669.7     .07       0
  4781.1     .12       0  4980.7     .05       0  5000.2     .12       0
  5018.5      .1       0  5077.1     .12       0  5222.7    .035       0
  5542.6     .12       0
Bank Sta=4980.7,5000.2
XS Rating Curve= 0 ,0
Exp/Cntr=0.3,0.1

Type RM Length L Ch R = 1 ,1452    ,516,516,516
BEGIN DESCRIPTION:
A19244
END DESCRIPTION:
XS GIS Cut Line= 2
      2236115.42     13865003.87      2233649.71     13865100.46
#Sta/Elev= 30
  3808.9  927.44  3884.8  905.19  3964.9   868.8  3969.9  874.78  3999.5  872.23
  4059.5  853.18  4083.8  850.63  4109.5     843  4189.6  802.97  4237.2  789.01
  4378.5   777.7  4816.4  768.57  4950.2  767.82  4970.9  764.24  5010.4  742.31
  5010.9  741.81    5030  742.31  5050.3  751.97  5060.3  752.78  5080.3  745.06
  5130.3  747.19  5168.3  758.46  5239.1  784.97  5323.7  793.15  5365.8  794.16
  5560.8     797  5657.7   799.5  5840.5   805.5  6081.1  817.09  6276.5  837.27
#Mann= 15 ,-1 , 0
  3808.9    .035       0  3884.8     .12       0  4083.8    .035       0
  4237.2     .12       0  4378.5    .035       0  4816.4     .07       0
  4970.9      .1       0  5010.4     .05       0    5030      .1       0
  5168.3    .035       0  5323.7     .12       0  5365.8     .07       0
  5560.8     .12       0  5657.7    .035       0  5840.5     .12       0
Bank Sta=5010.4,5030
XS Rating Curve= 0 ,0
Exp/Cntr=0.3,0.1