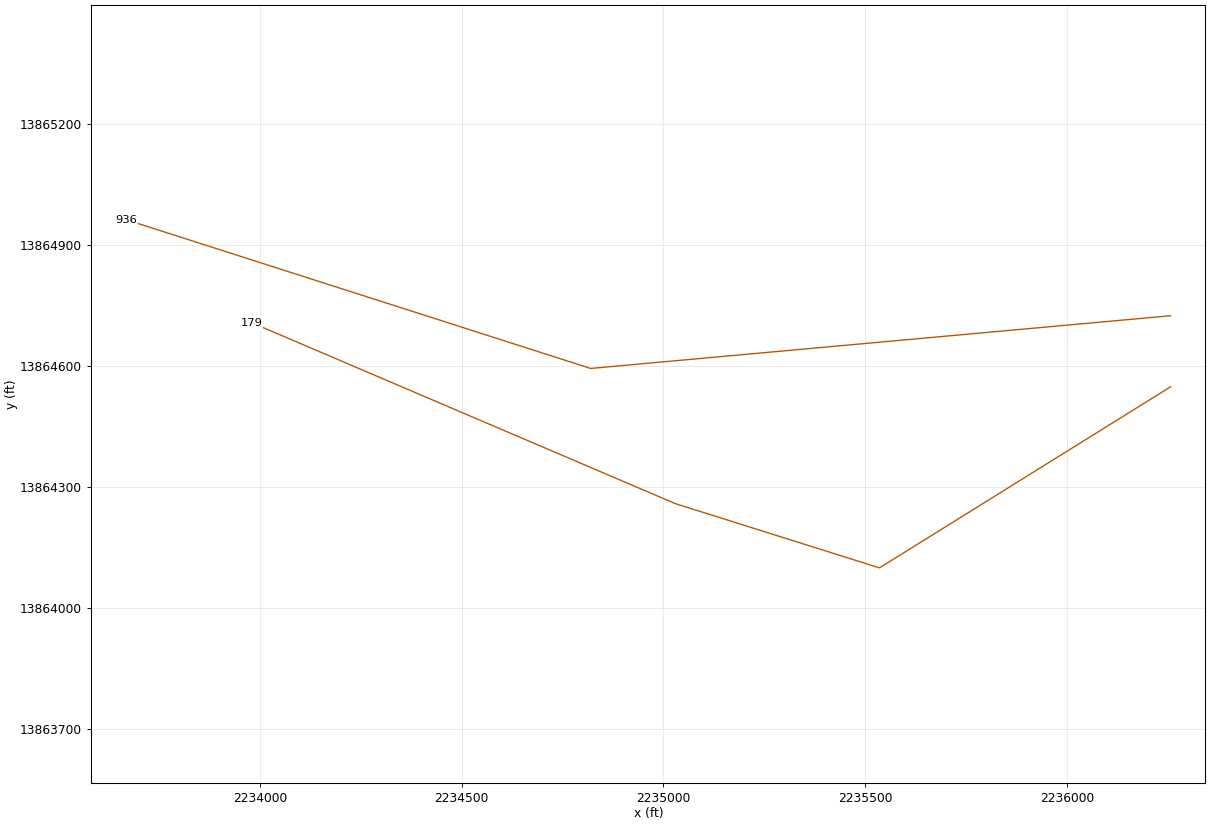
HEC-RAS study Guadalupe Tributary 23.prj: Guadalupe Tributary 23 Base Level Engineering

--- Guadalupe Tributary 23.g01 (geometry) --- (continued)

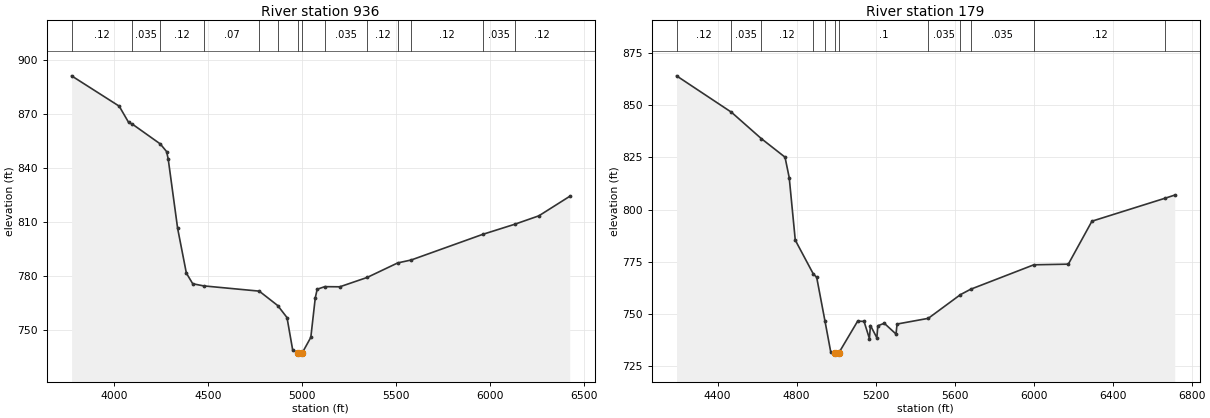
Type RM Length L Ch R = 1 ,936     ,757,757,757
BEGIN DESCRIPTION:
A19243
END DESCRIPTION:
XS GIS Cut Line= 3
      2236257.52     13864725.46      2234819.92     13864594.77
      2233668.25     13864963.53
#Sta/Elev= 30
    3773  891.11  4026.6  874.24  4076.8  865.19  4097.1  864.22  4245.3  853.24
  4278.9     849  4287.6  844.84  4337.8  806.25  4384.3  781.39  4418.2  775.48
  4476.2   774.3  4772.3  771.38  4870.9  763.35  4920.2  756.68  4950.4  738.67
  4980.7  736.85  4981.2  736.35  5000.3  736.85    5047  745.68  5070.8  767.68
  5080.9  772.44  5121.5  773.87  5201.4  773.79  5347.2     779  5509.7  787.07
  5581.9  788.71  5961.5  802.92  6132.8  808.57  6261.2  813.25  6425.8  824.11
#Mann= 14 ,-1 , 0
    3773     .12       0  4097.1    .035       0  4245.3     .12       0
  4476.2     .07       0  4772.3    .035       0  4870.9      .1       0
  4980.7     .05       0  5000.3      .1       0  5121.5    .035       0
  5347.2     .12       0  5509.7     .07       0  5581.9     .12       0
  5961.5    .035       0  6132.8     .12       0
Bank Sta=4980.7,5000.3
XS Rating Curve= 0 ,0
Exp/Cntr=0.3,0.1

Type RM Length L Ch R = 1 ,179     ,0,0,0
BEGIN DESCRIPTION:
A19242
END DESCRIPTION:
XS GIS Cut Line= 4
      2236257.45      13864549.3      2235535.86     13864100.44
      2235030.16     13864259.53      2233979.49      13864708.2
#Sta/Elev= 30
    4192  864.03    4470   846.6  4620.7  834.02  4741.1  825.11  4762.4  815.34
  4793.1  785.38  4883.8  769.32  4901.5   767.6  4943.7  746.56  4972.5  731.96
  4993.3  731.34  4993.8  730.84    5013  731.34  5108.9  746.62  5141.3   746.5
  5168.5  738.29  5173.7  744.53  5206.1   738.7  5211.3   744.4  5243.7  745.61
  5303.2  740.45  5308.5  745.24  5466.4  747.96  5629.4  759.31  5680.8  761.88
  6000.9  773.59  6175.6   773.9  6295.2  794.46  6665.7  805.46  6714.4  806.95
#Mann= 12 ,-1 , 0
    4192     .12       0    4470    .035       0  4620.7     .12       0
  4883.8    .035       0  4943.7      .1       0  4993.3     .05       0
    5013      .1       0  5466.4    .035       0  5629.4      .1       0
  5680.8    .035       0  6000.9     .12       0  6665.7    .035       0
Bank Sta=4993.3,5013
XS Rating Curve= 0 ,0
Exp/Cntr=0.3,0.1

Chan Stop Cuts=-1
Use User Specified Reach Order=0
Composite Channel Slope=5