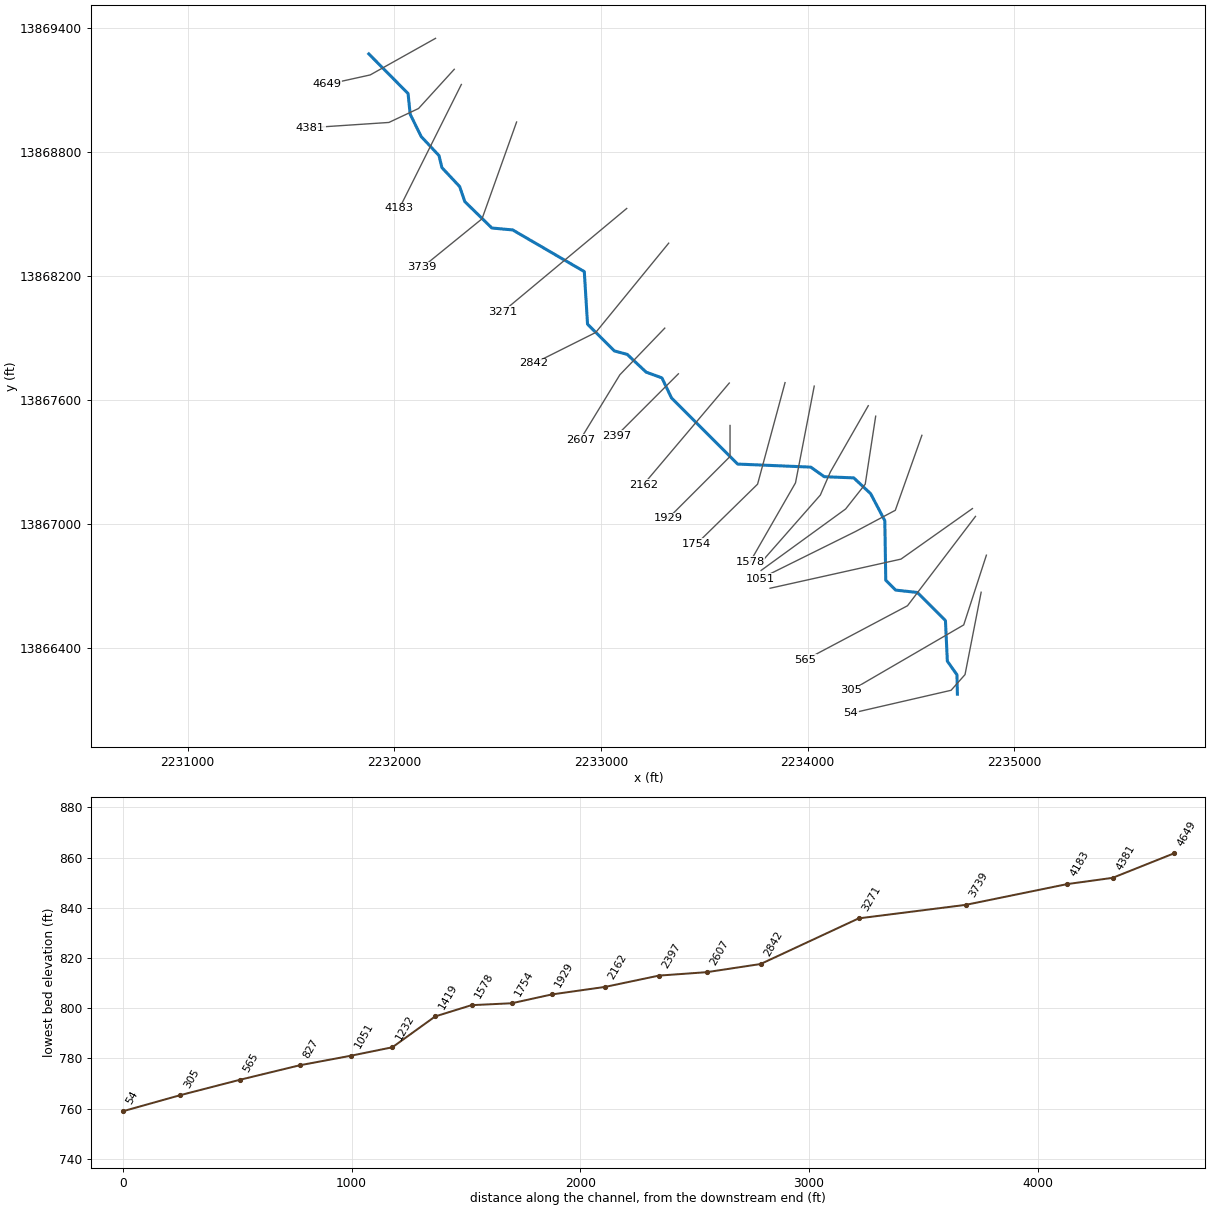
--- Guadalupe Tributary 24.prj (project) ---

Proj Title=Guadalupe Tributary 24 Base Level Engineering
Current Plan=p01
Default Exp/Contr=0.3,0.1
English Units
Geom File=g01
Flow File=f01
Plan File=p01
BEGIN DESCRIPTION:
Guadalupe Tributary 24
END DESCRIPTION:

--- Guadalupe Tributary 24.p01 (plan) ---

Plan Title=Multiple Run
Short Identifier=Multiple
Geom File=g01
Flow File=f01
Subcritical Flow
K Sum by GR= 0
Std Step Tol= 0.01
Critical Tol= 0.01
Num of Std Step Trials= 20
Max Error Tol= 0.3
Flow Tol Ratio= 0.001
Split Flow NTrial= 30
Split Flow Tol= 0.02
Split Flow Ratio= 0.02
Log Output Level= 0
Friction Slope Method= 1
Unsteady Friction Slope Method= 2
Unsteady Bridges Friction Slope Method= 1
Parabolic Critical Depth
Global Vel Dist=  1 , 1 , 1
Global Log Level= 0
CheckData=True
Encroach Param= -1, 0, 0, 0
BEGIN DESCRIPTION:
Multiple Run
END DESCRIPTION:

--- Guadalupe Tributary 24.f01 (steady flow) ---

Flow Title=Multiple
Number of Profiles=7
Profile Names=10-year,25-year,50-year,1pct_min,100-year,1pct_plu,500-year
River Rch & RM= Guadalupe Tribut,Reach-1,4649
    1118    1895    2636    1778    3547    7077    6349
River Rch & RM= Guadalupe Tribut,Reach-1,54
    4993    8977   12978    9039   18034   35983   34492
Boundary for River Rch & Prof#=Guadalupe Tribut,Reach-1,1
Up Type=0
Dn Type=3
Dn Slope=0.005
Boundary for River Rch & Prof#=Guadalupe Tribut,Reach-1,2
Up Type=0
Dn Type=3
Dn Slope=0.005
Boundary for River Rch & Prof#=Guadalupe Tribut,Reach-1,3
Up Type=0
Dn Type=3
Dn Slope=0.005
Boundary for River Rch & Prof#=Guadalupe Tribut,Reach-1,4
Up Type=0
Dn Type=3
Dn Slope=0.005
Boundary for River Rch & Prof#=Guadalupe Tribut,Reach-1,5
Up Type=0
Dn Type=3
Dn Slope=0.005
Boundary for River Rch & Prof#=Guadalupe Tribut,Reach-1,6
Up Type=0
Dn Type=3
Dn Slope=0.005
Boundary for River Rch & Prof#=Guadalupe Tribut,Reach-1,7
Up Type=0
Dn Type=3
Dn Slope=0.005

--- Guadalupe Tributary 24.g01 (geometry) ---

Geom Title=Existing Conditions

River Reach=Guadalupe Tribut,Reach-1
Reach XY= 30
      2231877.19     13869272.81      2232067.14     13869081.17
      2232077.33     13868980.97      2232130.84     13868872.71
      2232216.82     13868781.04      2232230.87     13868722.72
      2232316.82     13868631.04      2232341.65     13868558.33
      2232472.57     13868430.52      2232573.41     13868421.17
      2232919.82     13868219.56      2232935.48     13867965.20
      2233065.32     13867835.78      2233127.28     13867819.13
      2233218.98     13867733.18      2233295.47     13867705.37
      2233341.66     13867608.34      2233661.68     13867288.37
      2234015.34     13867273.62      2234080.94     13867227.27
      2234223.54     13867221.46      2234305.24     13867145.13
      2234373.80     13867014.50      2234378.44     13866726.22
      2234426.25     13866678.51      2234531.17     13866667.14
      2234667.19     13866531.19      2234676.36     13866334.65
      2234722.90     13866269.13      2234725.00     13866175.00

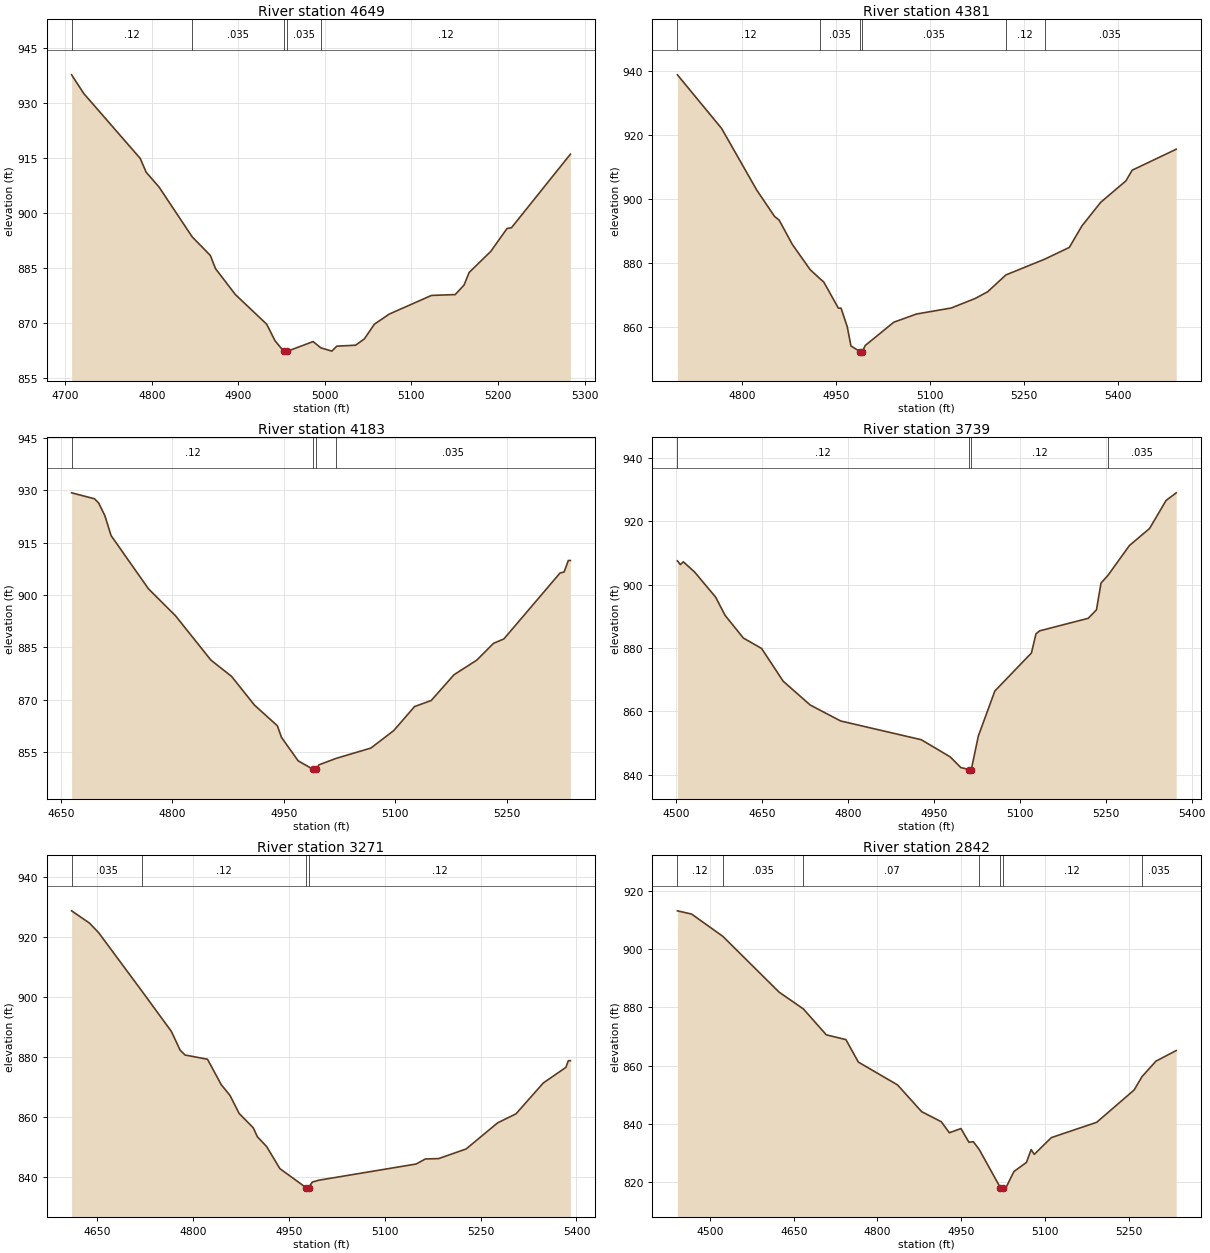
Type RM Length L Ch R = 1,4649,268,268,268
BEGIN DESCRIPTION:
Guadalupe Tributary 24 10.0
END DESCRIPTION:
XS GIS Cut Line= 3
      2232200.08     13869348.21      2231883.76     13869171.07
      2231675.03     13869125.01
#Sta/Elev= 30
  4707.4  937.61  4721.6  932.47  4786.7  914.81  4793.5  911.06  4808.4  907.01
  4846.7  893.42  4867.7  888.33  4873.7  884.73  4896.6  877.67  4932.8  869.58
  4942.5  865.04  4952.5  862.19  4952.7  861.69  4956.5  862.19  4986.4  864.84
  4995.3  863.14  5008.1  862.24  5013.8  863.59  5035.5  863.85  5045.6  865.56
  5057.2  869.57  5074.4  872.34  5123.2  877.43  5150.6  877.66  5160.8  880.25
  5166.8  883.72  5191.6  889.41  5210.5  895.69  5215.6  895.90  5283.7  915.96
#Mann=5,-1,0
  4707.4    0.12       0  4846.7   0.035       0  4952.5    0.05       0
  4956.5   0.035       0  4995.3    0.12       0
Bank Sta=4952.5,4956.5
Exp/Cntr=0.3,0.1

Type RM Length L Ch R = 1,4381,198,198,198
BEGIN DESCRIPTION:
A19265
END DESCRIPTION:
XS GIS Cut Line= 4
      2232290.70     13869198.47      2232117.81     13869008.71
      2231974.43     13868941.24      2231594.85     13868915.94
#Sta/Elev= 30
  4696.9  938.95  4767.3  922.21  4823.4  902.94  4851.8  894.69  4859.2  893.52
  4880.2  885.93  4908.6  878.05  4924.1  875.24  4930.2  874.23  4953.6  866.02
  4957.9  866.02  4967.8  860.18  4973.7  854.20  4987.9  852.45  4988.1  851.95
  4991.9  852.45  4996.5  854.35  5042.1  861.62  5078.3  864.18  5133.6  866.05
  5171.6  869.01  5191.7  871.13  5220.8  876.39  5282.6  881.31  5322.0  885.00
  5342.0  891.69  5372.1  899.11  5412.2  905.78  5422.2  909.13  5492.5  915.69
#Mann=6,-1,0
  4696.9    0.12       0  4924.1   0.035       0  4987.9   0.035       0
  4991.9   0.035       0  5220.8    0.12       0  5282.6   0.035       0
Bank Sta=4987.9,4991.9
Exp/Cntr=0.3,0.1

Type RM Length L Ch R = 1,4183,444,444,444
BEGIN DESCRIPTION:
Guadalupe Tributary 24 9.0
END DESCRIPTION:
XS GIS Cut Line= 3
      2232325.00     13869125.00      2232175.00     13868825.00
      2232025.01     13868525.02
#Sta/Elev= 30
  4664.6  929.26  4695.3  927.56  4700.9  926.38  4709.3  922.74  4717.7  917.00
  4768.0  901.73  4804.4  894.00  4851.9  881.31  4879.8  876.62  4910.6  868.38
  4941.3  862.48  4946.9  859.13  4969.3  852.42  4989.6  849.97  4989.9  849.47
  4993.6  849.97  4997.2  851.27  5020.4  853.13  5067.1  856.08  5097.8  861.09
  5125.8  867.98  5148.2  869.71  5178.9  877.11  5209.6  881.31  5232.0  886.11
  5246.0  887.38  5321.4  906.26  5327.0  906.58  5332.6  909.86  5335.4  909.86
#Mann=4,-1,0
  4664.6    0.12       0  4989.6    0.05       0  4993.6    0.12       0
  5020.4   0.035       0
Bank Sta=4989.6,4993.6
Exp/Cntr=0.3,0.1

Type RM Length L Ch R = 1,3739,468,468,468
BEGIN DESCRIPTION:
Guadalupe Tributary 24 8.0
END DESCRIPTION:
XS GIS Cut Line= 3
      2232592.24     13868943.37      2232425.00     13868475.00
      2232135.23     13868239.55
#Sta/Elev= 30
  4502.4  907.49  4507.5  906.32  4512.8  907.17  4532.5  903.94  4569.1  896.05
  4585.6  890.30  4617.5  883.15  4649.3  879.87  4687.0  869.54  4734.3  862.02
  4787.4  857.00  4928.1  851.09  4978.5  845.69  4997.1  842.32  5011.4  841.69
  5011.6  841.19  5015.4  841.69  5027.7  852.27  5056.5  866.45  5120.4  878.45
  5128.3  884.48  5134.8  885.42  5219.5  889.37  5233.9  892.05  5241.8  900.47
  5253.8  902.88  5291.4  912.31  5326.6  917.69  5355.3  926.50  5373.1  928.93
#Mann=4,-1,0
  4502.4    0.12       0  5011.4    0.05       0  5015.4    0.12       0
  5253.8   0.035       0
Bank Sta=5011.4,5015.4
Exp/Cntr=0.3,0.1

Type RM Length L Ch R = 1,3271,429,429,429
BEGIN DESCRIPTION:
Guadalupe Tributary 24 7.0
END DESCRIPTION:
XS GIS Cut Line= 3
      2233125.01     13868525.01      2232825.00     13868275.00
      2232525.03     13868025.03
#Sta/Elev= 30
  4609.5  928.84  4637.5  924.74  4651.8  921.55  4720.2  901.83  4765.7  888.54
  4779.4  882.28  4787.2  880.64  4822.3  879.22  4843.8  870.73  4857.5  867.14
  4871.8  861.11  4893.9  856.32  4900.4  853.32  4914.8  850.06  4935.6  842.67
  4976.6  836.31  4976.8  835.81  4980.6  836.31  4986.4  838.17  4996.8  838.80
  5149.1  844.21  5163.4  845.89  5184.2  846.02  5227.2  849.23  5276.6  857.97
  5305.3  860.98  5348.2  871.32  5383.4  876.50  5387.3  878.75  5390.5  878.75
#Mann=4,-1,0
  4609.5   0.035       0  4720.2    0.12       0  4976.6    0.05       0
  4980.6    0.12       0
Bank Sta=4976.6,4980.6
Exp/Cntr=0.3,0.1

Type RM Length L Ch R = 1,2842,235,235,235
BEGIN DESCRIPTION:
Guadalupe Tributary 24 6.0
END DESCRIPTION:
XS GIS Cut Line= 3
      2233328.13     13868357.20      2232975.00     13867925.00
      2232675.03     13867775.02
#Sta/Elev= 30
  4441.6  913.19  4467.0  912.08  4523.0  904.42  4623.5  885.31  4667.4  879.47
  4708.3  870.60  4743.4  868.97  4765.7  861.25  4836.0  853.40  4879.1  844.22
  4914.3  840.76  4928.7  836.98  4949.5  838.42  4963.8  833.72  4971.7  833.90
  4982.5  831.14  5020.1  818.12  5020.3  817.62  5024.1  818.12  5030.5  818.28
  5044.4  823.68  5066.8  826.79  5075.2  831.20  5080.8  829.56  5111.5  835.32
  5192.6  840.56  5259.7  851.67  5273.8  856.25  5298.8  861.57  5335.1  865.21
#Mann=7,-1,0
  4441.6    0.12       0  4523.0   0.035       0  4667.4    0.07       0
  4982.5    0.12       0  5020.1    0.05       0  5024.1    0.12       0
  5273.8   0.035       0
Bank Sta=5020.1,5024.1
Exp/Cntr=0.3,0.1

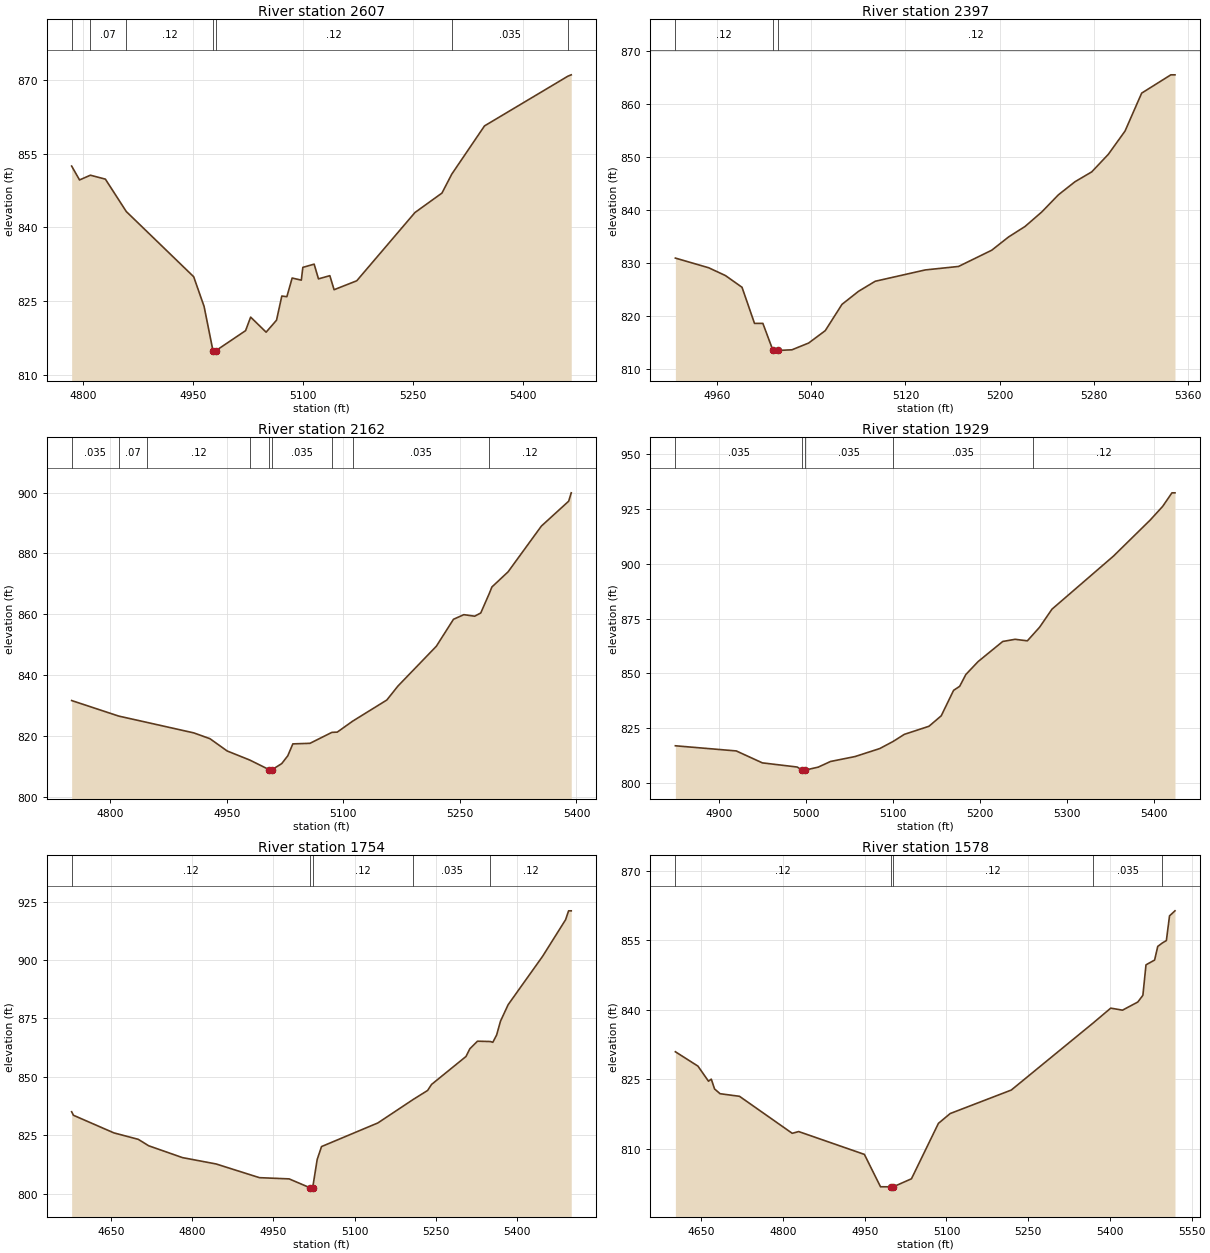
Type RM Length L Ch R = 1,2607,210,210,210
BEGIN DESCRIPTION:
A19264
END DESCRIPTION:
XS GIS Cut Line= 3
      2233309.15     13867946.03      2233091.95     13867720.40
      2232900.09     13867406.24
#Sta/Elev= 30
  4784.4  852.49  4795.2  849.66  4809.9  850.63  4830.4  849.83  4858.9  843.23
  4950.8  829.95  4965.0  823.90  4977.1  814.88  4977.4  814.38  4981.1  814.88
  5021.6  818.96  5028.5  821.72  5049.6  818.65  5063.8  821.09  5071.0  826.01
  5077.9  825.88  5085.1  829.68  5097.6  829.25  5099.7  831.85  5115.1  832.51
  5121.0  829.51  5136.5  830.16  5142.3  827.30  5173.2  829.12  5252.6  843.03
  5289.4  846.99  5302.8  850.85  5347.4  860.67  5461.1  870.80  5465.7  871.08
#Mann=7,-1,0
  4784.4   0.035       0  4809.9    0.07       0  4858.9    0.12       0
  4977.1    0.05       0  4981.1    0.12       0  5302.8   0.035       0
  5461.1    0.12       0
Bank Sta=4977.1,4981.1
Exp/Cntr=0.3,0.1

Type RM Length L Ch R = 1,2397,235,235,235
BEGIN DESCRIPTION:
Guadalupe Tributary 24 5.0
END DESCRIPTION:
XS GIS Cut Line= 3
      2233375.03     13867725.03      2233325.00     13867675.00
      2233075.00     13867425.00
#Sta/Elev= 30
  4924.6  830.96  4952.9  829.13  4967.1  827.66  4981.2  825.44  4991.8  818.62
  4998.9  818.62  5007.5  813.50  5007.7  813.00  5011.2  813.00  5011.5  813.50
  5023.6  813.63  5037.8  814.91  5051.9  817.25  5066.1  822.22  5080.2  824.69
  5094.3  826.58  5136.8  828.72  5165.1  829.38  5193.3  832.45  5207.5  834.94
  5221.6  836.94  5235.8  839.68  5249.9  842.92  5264.0  845.39  5278.2  847.25
  5292.3  850.57  5306.5  854.97  5320.6  862.13  5345.4  865.59  5348.9  865.59
#Mann=3,-1,0
  4924.6    0.12       0  5007.5    0.05       0  5011.5    0.12       0
Bank Sta=5007.5,5011.5
Exp/Cntr=0.3,0.1

Type RM Length L Ch R = 1,2162,233,233,233
BEGIN DESCRIPTION:
A19263
END DESCRIPTION:
XS GIS Cut Line= 2
      2233621.22     13867680.36      2233206.20     13867189.49
#Sta/Elev= 30
  4750.5  831.69  4811.1  826.58  4847.6  824.50  4907.7  821.06  4928.5  819.15
  4950.6  815.12  4979.7  812.14  5004.5  809.00  5004.8  808.50  5008.5  809.00
  5020.8  810.97  5028.6  813.54  5035.1  817.45  5057.2  817.64  5085.3  821.23
  5092.3  821.32  5111.9  824.89  5156.0  831.86  5170.3  836.44  5219.7  849.52
  5241.8  858.39  5255.1  859.90  5269.1  859.40  5276.9  860.46  5287.8  866.82
  5291.2  868.99  5312.0  873.96  5354.9  889.01  5390.0  897.18  5393.3  899.93
#Mann=9,-1,0
  4750.5   0.035       0  4811.1    0.07       0  4847.6    0.12       0
  4979.7   0.035       0  5004.5   0.035       0  5008.5   0.035       0
  5085.3    0.12       0  5111.9   0.035       0  5287.8    0.12       0
Bank Sta=5004.5,5008.5
Exp/Cntr=0.3,0.1

Type RM Length L Ch R = 1,1929,175,175,175
BEGIN DESCRIPTION:
Guadalupe Tributary 24 4.0
END DESCRIPTION:
XS GIS Cut Line= 3
      2233625.00     13867475.05      2233625.00     13867325.00
      2233325.01     13867025.01
#Sta/Elev= 30
  4849.7  817.05  4919.7  814.70  4949.7  809.26  4989.7  807.37  4995.2  806.00
  4995.5  805.50  4999.2  806.00  5013.9  807.32  5028.0  809.89  5056.3  812.15
  5084.6  815.78  5099.9  819.00  5112.9  822.26  5141.2  825.94  5155.3  830.71
  5169.5  842.31  5176.5  844.15  5183.6  849.53  5197.7  855.42  5226.0  864.58
  5240.2  865.57  5254.3  864.87  5260.7  867.69  5268.4  871.09  5282.6  879.30
  5353.3  903.49  5395.7  919.99  5409.9  926.17  5420.5  932.32  5424.0  932.32
#Mann=5,-1,0
  4849.7   0.035       0  4995.2    0.05       0  4999.2   0.035       0
  5099.9   0.035       0  5260.7    0.12       0
Bank Sta=4995.2,4999.2
Exp/Cntr=0.3,0.1

Type RM Length L Ch R = 1,1754,176,176,176
BEGIN DESCRIPTION:
A19262
END DESCRIPTION:
XS GIS Cut Line= 3
      2233891.08     13867682.39      2233758.25     13867191.15
      2233463.06     13866902.28
#Sta/Elev= 30
  4577.9  835.08  4581.2  833.58  4655.8  826.05  4700.8  823.29  4720.2  820.52
  4782.4  815.47  4844.5  812.75  4924.5  806.89  4979.2  806.37  5018.6  802.49
  5018.9  801.99  5022.6  802.49  5031.0  814.66  5039.0  820.19  5143.0  830.30
  5208.5  840.39  5234.8  844.20  5242.0  846.76  5305.6  858.72  5312.7  862.02
  5326.8  865.26  5350.7  865.12  5355.1  864.78  5362.1  867.91  5369.3  873.86
  5383.4  880.89  5447.0  901.58  5489.4  917.23  5494.9  921.02  5499.8  921.02
#Mann=5,-1,0
  4577.9    0.12       0  5018.6    0.05       0  5022.6    0.12       0
  5208.5   0.035       0  5350.7    0.12       0
Bank Sta=5018.6,5022.6
Exp/Cntr=0.3,0.1

Type RM Length L Ch R = 1,1578,159,159,159
BEGIN DESCRIPTION:
A19261
END DESCRIPTION:
XS GIS Cut Line= 3
      2234032.37     13867665.61      2233941.70     13867197.48
      2233722.40     13866815.82
#Sta/Elev= 30
  4602.4  830.89  4643.8  827.79  4663.2  824.53  4668.3  824.98  4674.3  822.86
  4684.5  821.83  4720.1  821.27  4816.9  813.28  4828.7  813.66  4949.3  808.73
  4978.9  801.74  4998.3  801.73  4998.5  801.23  5002.3  801.73  5035.7  803.46
  5085.2  815.43  5106.8  817.55  5218.9  822.62  5368.8  837.06  5401.5  840.31
  5423.1  839.87  5451.2  841.63  5460.5  843.08  5466.2  849.66  5482.0  850.69
  5487.8  853.64  5496.1  854.37  5503.6  854.90  5509.4  860.23  5519.4  861.32
#Mann=5,-1,0
  4602.4    0.12       0  4998.3    0.05       0  5002.3    0.12       0
  5368.8   0.035       0  5496.1    0.12       0
Bank Sta=4998.3,5002.3
Exp/Cntr=0.3,0.1

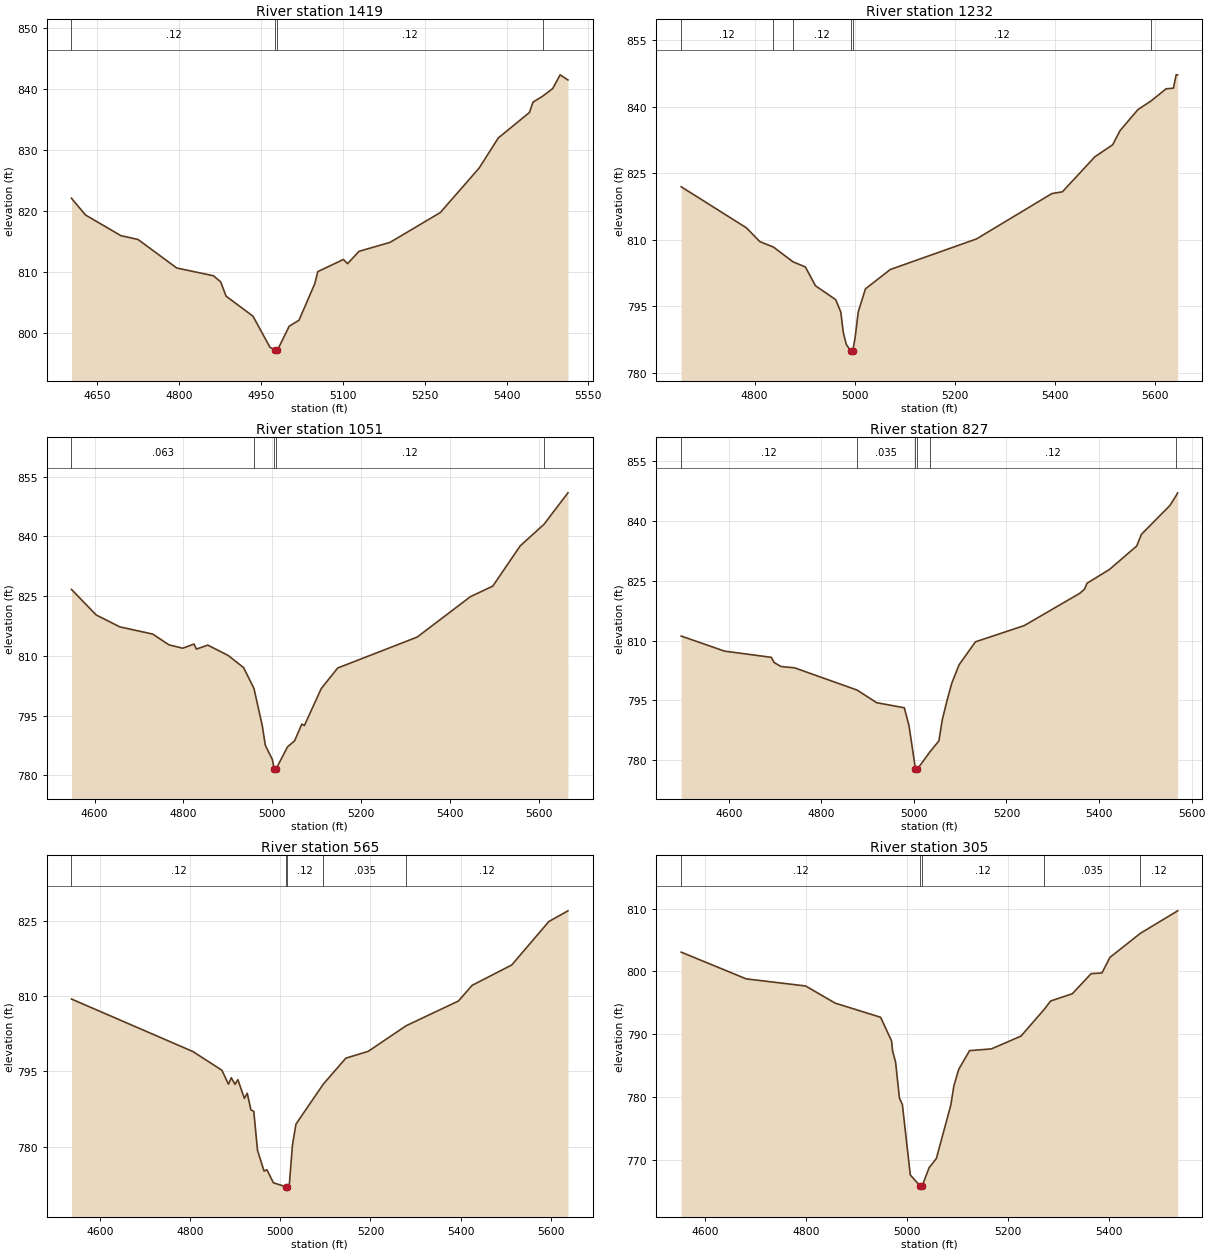
Type RM Length L Ch R = 1,1419,187,187,187
BEGIN DESCRIPTION:
A19260
END DESCRIPTION:
XS GIS Cut Line= 4
      2234293.82     13867570.69      2234110.38     13867250.19
      2234061.88     13867138.44      2233785.69     13866824.29
#Sta/Elev= 30
  4603.1  822.11  4628.9  819.36  4693.7  815.98  4724.9  815.36  4795.9  810.68
  4863.1  809.41  4876.5  808.40  4886.2  806.07  4935.5  802.79  4966.7  797.69
  4976.4  797.23  4976.7  796.73  4980.4  797.23  5001.9  801.14  5019.9  802.13
  5048.8  808.12  5054.3  810.09  5101.2  812.08  5108.8  811.39  5129.7  813.41
  5186.6  814.88  5278.7  819.77  5349.8  827.06  5384.9  831.99  5441.9  836.16
  5448.5  837.87  5466.3  838.85  5484.5  840.08  5498.2  842.34  5512.5  841.50
#Mann=4,-1,0
  4603.1    0.12       0  4976.4    0.05       0  4980.4    0.12       0
  5466.3   0.035       0
Bank Sta=4976.4,4980.4
Exp/Cntr=0.3,0.1

Type RM Length L Ch R = 1,1232,181,181,181
BEGIN DESCRIPTION:
A19259
END DESCRIPTION:
XS GIS Cut Line= 4
      2234329.67     13867520.08      2234279.06     13867191.15
      2234184.18     13867070.97      2233775.13     13866773.67
#Sta/Elev= 30
  4653.3  821.97  4783.8  812.69  4810.2  809.61  4837.5  808.37  4876.7  805.04
  4901.3  803.89  4921.5  799.64  4962.0  796.50  4972.1  793.71  4977.1  789.10
  4983.0  786.44  4991.9  784.95  4992.2  784.45  4995.9  784.95  5000.5  787.78
  5006.9  793.73  5021.3  798.94  5071.0  803.31  5243.1  810.20  5393.8  820.44
  5414.7  820.83  5479.6  828.73  5515.2  831.45  5529.8  834.62  5565.4  839.35
  5592.1  841.35  5621.8  844.05  5636.5  844.21  5641.9  847.21  5644.9  847.21
#Mann=6,-1,0
  4653.3    0.12       0  4837.5   0.063       0  4876.7    0.12       0
  4991.9    0.05       0  4995.9    0.12       0  5592.1   0.035       0
Bank Sta=4991.9,4995.9
Exp/Cntr=0.3,0.1

Type RM Length L Ch R = 1,1051,224,224,224
BEGIN DESCRIPTION:
A19258
END DESCRIPTION:
XS GIS Cut Line= 4
      2234553.19     13867427.35      2234424.55     13867064.64
      2234230.57     13866961.32      2233770.91     13866733.60
#Sta/Elev= 30
  4548.1  826.68  4603.6  820.28  4656.7  817.29  4731.0  815.47  4767.6  812.76
  4798.5  811.93  4824.0  812.97  4829.3  811.71  4854.9  812.71  4900.7  810.12
  4935.5  807.07  4958.9  801.83  4977.8  792.38  4984.4  787.58  5000.4  783.99
  5004.4  781.59  5004.6  781.09  5008.4  781.59  5034.4  787.18  5050.3  788.69
  5066.6  792.90  5072.3  792.51  5110.5  801.84  5147.4  806.96  5326.3  814.72
  5446.0  824.85  5496.5  827.51  5558.2  837.60  5611.8  843.02  5665.7  850.91
#Mann=5,-1,0
  4548.1   0.063       0  4958.9    0.12       0  5004.4    0.05       0
  5008.4    0.12       0  5611.8   0.035       0
Bank Sta=5004.4,5008.4
Exp/Cntr=0.3,0.1

Type RM Length L Ch R = 1,827,262,262,262
BEGIN DESCRIPTION:
A19257
END DESCRIPTION:
XS GIS Cut Line= 3
      2234797.79     13867073.09      2234451.96     13866828.48
      2233818.66     13866687.51
#Sta/Elev= 30
  4497.4  811.16  4591.0  807.38  4692.0  805.82  4698.1  804.53  4712.9  803.52
  4742.4  803.19  4877.4  797.61  4919.7  794.44  4979.4  793.17  4989.6  788.62
  5003.5  777.78  5003.8  777.28  5007.5  777.78  5034.8  782.13  5054.1  784.87
  5061.3  790.13  5071.6  794.97  5081.8  799.29  5097.6  803.95  5133.0  809.71
  5238.4  813.78  5358.4  821.88  5368.7  822.93  5374.0  824.40  5422.6  827.86
  5481.3  833.74  5491.6  836.67  5553.1  843.91  5567.1  846.49  5569.8  847.08
#Mann=6,-1,0
  4497.4    0.12       0  4877.4   0.035       0  5003.5   0.035       0
  5007.5   0.035       0  5034.8    0.12       0  5567.1   0.035       0
Bank Sta=5003.5,5007.5
Exp/Cntr=0.3,0.1

Type RM Length L Ch R = 1,565,260,260,260
BEGIN DESCRIPTION:
A19256
END DESCRIPTION:
XS GIS Cut Line= 3
      2234812.52     13867035.12      2234483.59     13866602.87
      2233990.16     13866341.39
#Sta/Elev= 30
  4536.8  809.44  4806.2  798.96  4870.6  795.22  4885.1  792.44  4891.4  793.72
  4899.7  792.41  4906.0  793.34  4920.5  789.60  4926.8  790.63  4935.0  787.31
  4941.3  787.01  4949.6  779.23  4964.1  775.09  4970.4  775.36  4984.9  772.75
  5012.0  771.99  5012.3  771.49  5016.0  771.99  5020.3  772.55  5027.0  780.21
  5034.8  784.45  5095.2  792.41  5145.4  797.63  5195.0  798.99  5279.4  804.11
  5395.3  809.04  5425.7  812.17  5513.7  816.24  5596.0  824.91  5638.4  827.05
#Mann=5,-1,0
  4536.8    0.12       0  5012.0    0.05       0  5016.0    0.12       0
  5095.2   0.035       0  5279.4    0.12       0
Bank Sta=5012,5016
Exp/Cntr=0.3,0.1

Type RM Length L Ch R = 1,305,251,251,251
BEGIN DESCRIPTION:
A19255
END DESCRIPTION:
XS GIS Cut Line= 3
      2234865.25     13866847.48      2234755.59     13866510.09
      2234211.61     13866193.83
#Sta/Elev= 30
  4552.4  803.07  4681.2  798.82  4799.0  797.69  4857.6  794.96  4947.7  792.71
  4969.3  788.96  4971.5  787.29  4977.3  785.62  4985.0  779.86  4990.8  778.84
  5006.5  767.64  5026.0  765.88  5026.3  765.38  5030.0  765.88  5043.7  768.78
  5058.2  770.26  5086.8  778.75  5092.9  781.81  5102.5  784.43  5124.0  787.41
  5167.1  787.68  5225.8  789.71  5271.8  793.96  5284.6  795.30  5327.6  796.45
  5364.9  799.65  5386.4  799.76  5402.1  802.23  5462.3  806.05  5536.4  809.64
#Mann=5,-1,0
  4552.4    0.12       0  5026.0    0.05       0  5030.0    0.12       0
  5271.8   0.035       0  5462.3    0.12       0
Bank Sta=5026,5030
Exp/Cntr=0.3,0.1

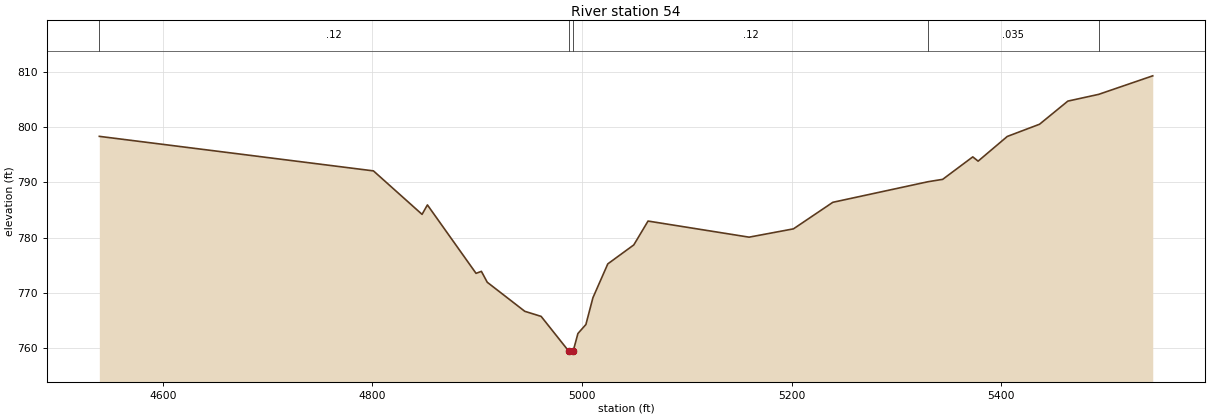
Type RM Length L Ch R = 1,54,0,0,0
BEGIN DESCRIPTION:
A19254
END DESCRIPTION:
XS GIS Cut Line= 4
      2234839.93     13866668.21      2234761.92     13866269.72
      2234694.45     13866193.81      2234209.76     13866082.12
#Sta/Elev= 30
  4539.4  798.33  4800.9  792.09  4847.3  784.23  4852.4  785.94  4898.8  773.57
  4903.9  773.93  4909.5  771.96  4945.3  766.71  4960.9  765.79  4987.4  759.47
  4987.6  758.97  4991.4  759.47  4996.0  762.70  5003.6  764.32  5010.3  769.16
  5024.5  775.28  5049.3  778.71  5062.9  783.02  5159.3  780.11  5201.6  781.61
  5239.2  786.41  5330.0  790.13  5344.0  790.56  5372.7  794.62  5377.8  793.85
  5405.6  798.31  5436.4  800.52  5463.4  804.70  5492.8  805.92  5544.4  809.27
#Mann=5,-1,0
  4539.4    0.12       0  4987.4    0.05       0  4991.4    0.12       0
  5330.0   0.035       0  5492.8    0.12       0
Bank Sta=4987.4,4991.4
Exp/Cntr=0.3,0.1

Chan Stop Cuts=-1