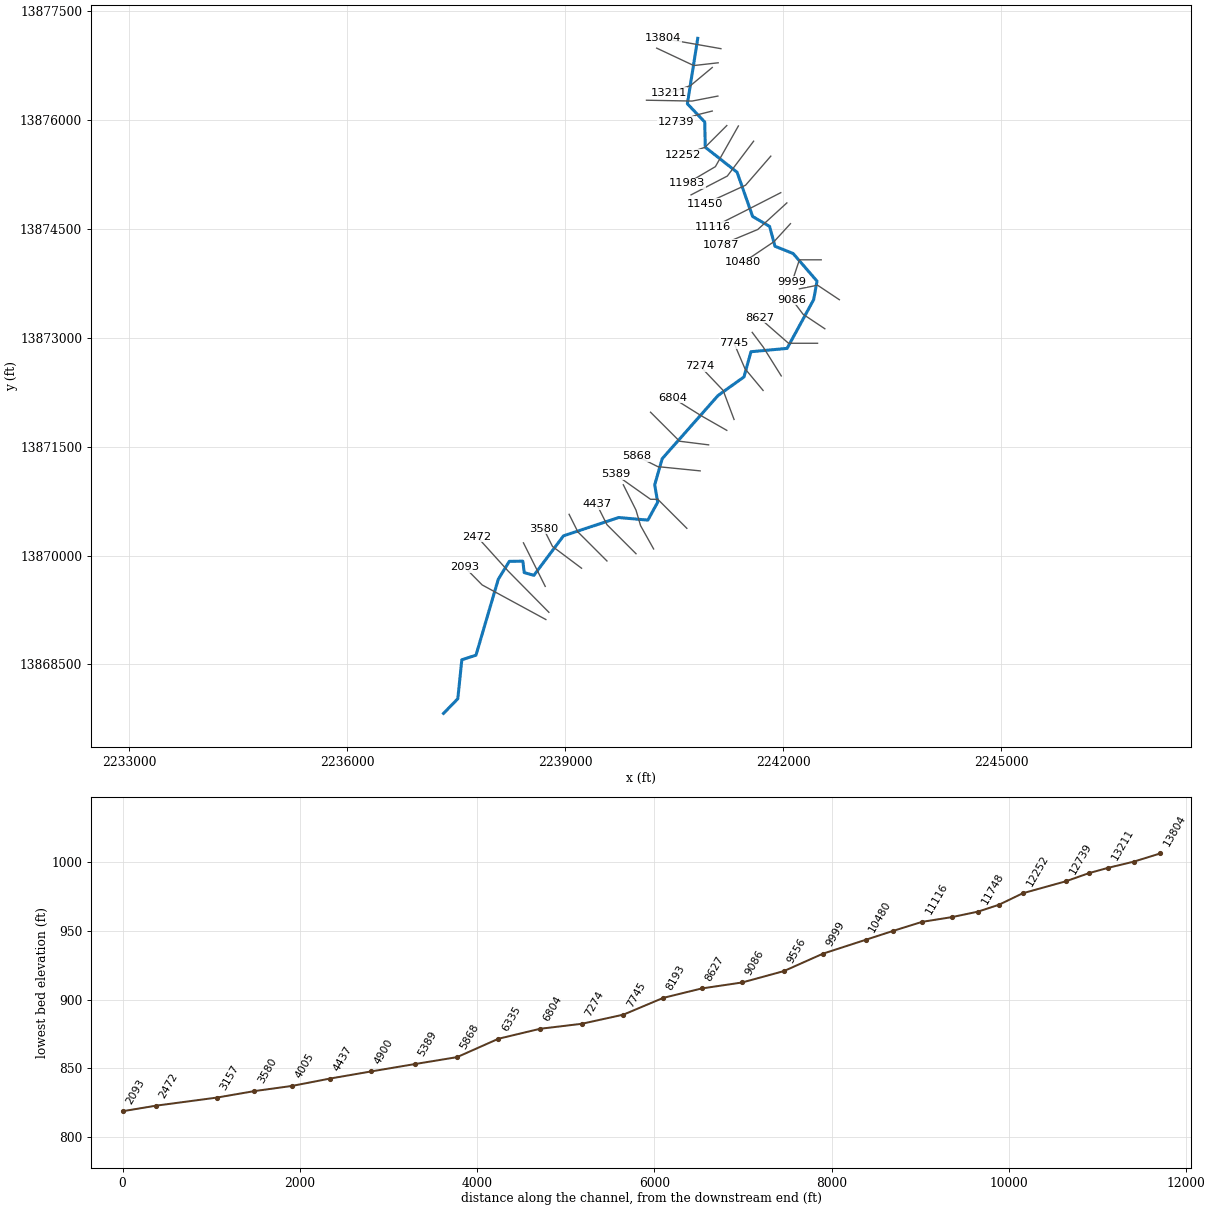
--- Guadalupe Tributary 25.prj (project) ---

Proj Title=Guadalupe Tributary 25 Base Level Engineering
Current Plan=p01
Default Exp/Contr=0.3,0.1
English Units
Geom File=g01
Flow File=f01
Plan File=p01
BEGIN DESCRIPTION:
Guadalupe Tributary 25
END DESCRIPTION:

--- Guadalupe Tributary 25.p01 (plan) ---

Plan Title=Multiple Run
Short Identifier=Multiple
Geom File=g01
Flow File=f01
Subcritical Flow
K Sum by GR= 0
Std Step Tol= 0.01
Critical Tol= 0.01
Num of Std Step Trials= 20
Max Error Tol= 0.3
Flow Tol Ratio= 0.001
Split Flow NTrial= 30
Split Flow Tol= 0.02
Split Flow Ratio= 0.02
Log Output Level= 0
Friction Slope Method= 1
Unsteady Friction Slope Method= 2
Unsteady Bridges Friction Slope Method= 1
Parabolic Critical Depth
Global Vel Dist=  1 , 1 , 1
Global Log Level= 0
CheckData=True
Encroach Param= -1, 0, 0, 0
BEGIN DESCRIPTION:
Multiple Run
END DESCRIPTION:

--- Guadalupe Tributary 25.f01 (steady flow) ---

Flow Title=Multiple
Number of Profiles=7
Profile Names=10-year,25-year,50-year,1pct_min,100-year,1pct_plu,500-year
River Rch & RM= Guadalupe Tribut,Reach-1,13804
    1088    1842    2561    1727    3445    6874    6162
River Rch & RM= Guadalupe Tribut,Reach-1,9556
    1871    3255    4605    3151    6288   12545   11604
River Rch & RM= Guadalupe Tribut,Reach-1,4437
    2068    3604    5103    3493    6969   13905   12866
Boundary for River Rch & Prof#=Guadalupe Tribut,Reach-1,1
Up Type=0
Dn Type=3
Dn Slope=0.005
Boundary for River Rch & Prof#=Guadalupe Tribut,Reach-1,2
Up Type=0
Dn Type=3
Dn Slope=0.005
Boundary for River Rch & Prof#=Guadalupe Tribut,Reach-1,3
Up Type=0
Dn Type=3
Dn Slope=0.005
Boundary for River Rch & Prof#=Guadalupe Tribut,Reach-1,4
Up Type=0
Dn Type=3
Dn Slope=0.005
Boundary for River Rch & Prof#=Guadalupe Tribut,Reach-1,5
Up Type=0
Dn Type=3
Dn Slope=0.005
Boundary for River Rch & Prof#=Guadalupe Tribut,Reach-1,6
Up Type=0
Dn Type=3
Dn Slope=0.005
Boundary for River Rch & Prof#=Guadalupe Tribut,Reach-1,7
Up Type=0
Dn Type=3
Dn Slope=0.005

--- Guadalupe Tributary 25.g01 (geometry) ---

Geom Title=Existing Conditions

River Reach=Guadalupe Tribut,Reach-1
Reach XY= 30
      2240825.00     13877126.84      2240682.32     13876224.90
      2240921.46     13875973.54      2240928.54     13875626.46
      2241366.86     13875281.06      2241580.71     13874672.42
      2241814.49     13874534.81      2241888.39     13874261.67
      2242138.34     13874161.64      2242467.24     13873781.17
      2242421.38     13873526.50      2242055.42     13872854.41
      2241557.94     13872808.52      2241461.77     13872461.33
      2241104.61     13872205.16      2240335.76     13871334.68
      2240232.56     13870975.00      2240273.62     13870734.66
      2240138.24     13870488.11      2239735.50     13870523.80
      2238976.50     13870271.39      2238569.11     13869726.95
      2238435.33     13869764.82      2238417.08     13869922.09
      2238230.41     13869919.83      2238078.55     13869673.53
      2237771.39     13868626.47      2237576.62     13868563.82
      2237521.18     13868026.58      2237325.00     13867825.00

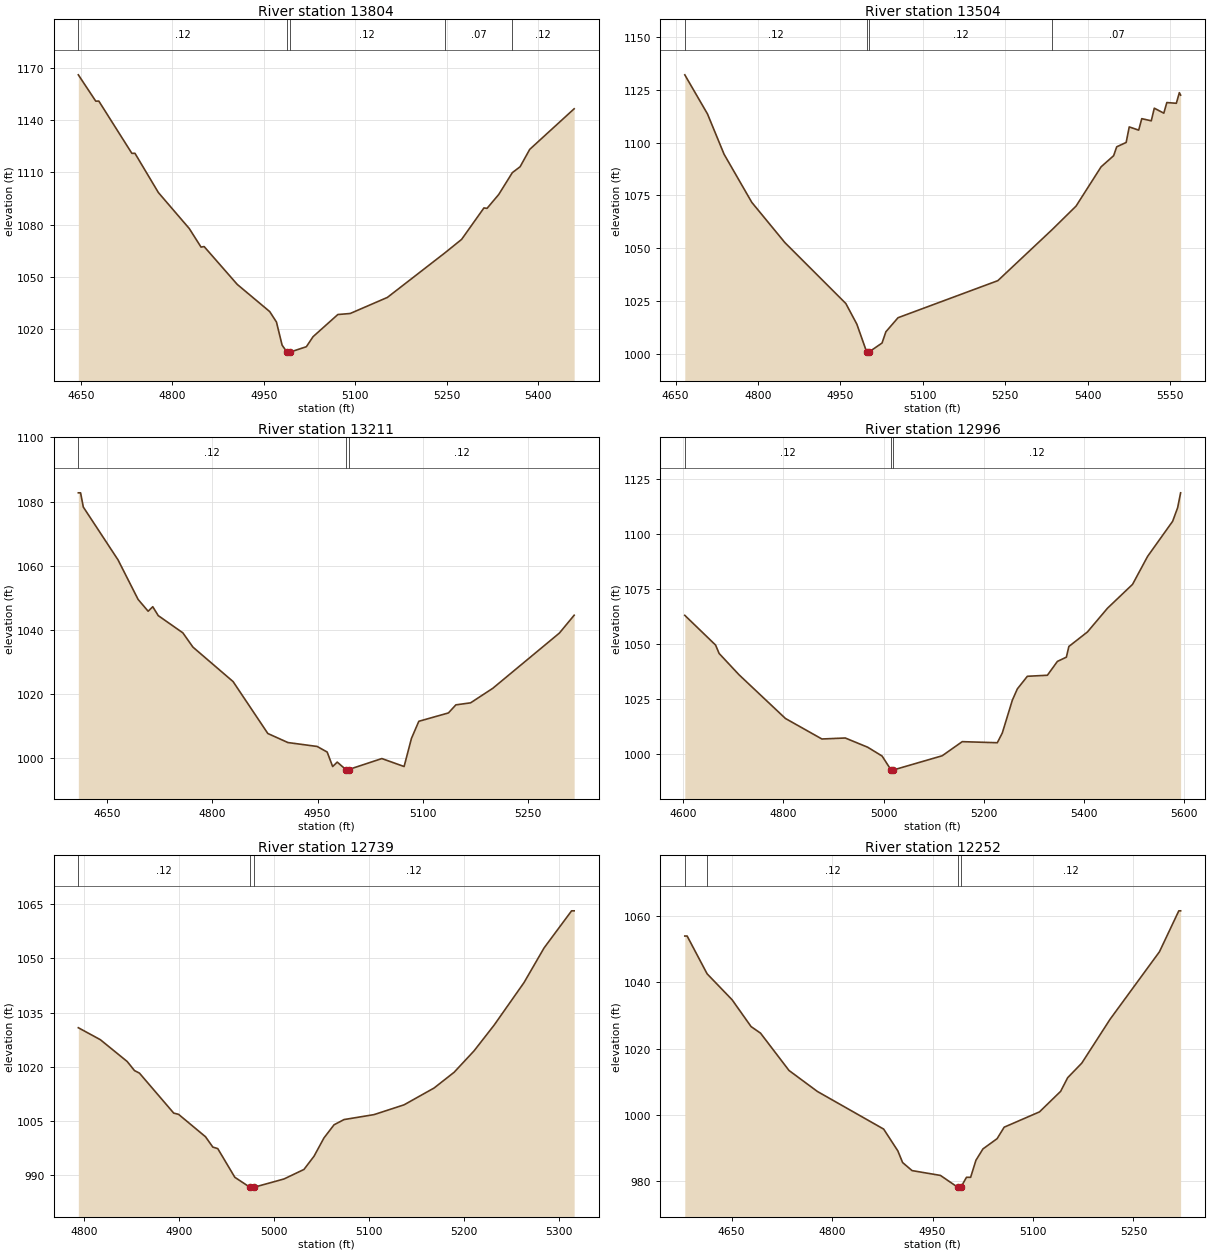
Type RM Length L Ch R = 1,13804,300,300,300
BEGIN DESCRIPTION:
A19280
END DESCRIPTION:
XS GIS Cut Line= 2
      2241144.28     13876984.36      2240343.22     13877125.50
#Sta/Elev= 30
  4645.8 1165.91  4674.4 1150.82  4679.4 1150.87  4733.6 1120.93  4738.7 1120.93
  4777.1 1098.46  4827.8 1077.83  4847.1 1067.20  4852.2 1067.50  4906.4 1045.85
  4959.8 1030.23  4970.8 1024.27  4980.1 1011.01  4988.3 1006.94  4988.6 1006.44
  4992.3 1006.94  5019.9 1010.11  5030.9 1015.87  5071.5 1028.55  5091.8 1029.15
  5152.8 1038.36  5247.2 1063.90  5274.6 1071.62  5311.2 1089.64  5316.3 1089.40
  5335.5 1097.36  5357.8 1109.87  5370.5 1113.23  5386.3 1123.19  5459.2 1146.45
#Mann=5,-1,0
  4645.8    0.12       0  4988.3    0.05       0  4992.3    0.12       0
  5247.2    0.07       0  5357.8    0.12       0
Bank Sta=4988.3,4992.3
Exp/Cntr=0.3,0.1

Type RM Length L Ch R = 1,13504,293,293,293
BEGIN DESCRIPTION:
A19279
END DESCRIPTION:
XS GIS Cut Line= 3
      2241106.08     13876789.82      2240770.45     13876751.68
      2240259.68     13876991.82
#Sta/Elev= 30
  4666.8 1132.08  4708.1 1113.57  4738.3 1094.50  4788.7 1071.76  4849.0 1052.69
  4959.8 1023.91  4979.9 1014.11  4997.8 1000.93  4998.0 1000.43  5001.8 1000.93
  5025.7 1005.21  5032.7 1010.53  5054.8 1017.18  5236.4 1034.71  5335.6 1058.95
  5378.7 1069.97  5424.3 1088.56  5447.1 1093.82  5452.7 1098.03  5469.9 1100.08
  5475.5 1107.44  5492.7 1105.92  5498.3 1111.35  5515.6 1110.32  5521.1 1116.30
  5538.4 1113.94  5543.9 1118.96  5561.2 1118.62  5566.7 1123.65  5569.0 1122.48
#Mann=4,-1,0
  4666.8    0.12       0  4997.8    0.05       0  5001.8    0.12       0
  5335.6    0.07       0
Bank Sta=4997.8,5001.8
Exp/Cntr=0.3,0.1

Type RM Length L Ch R = 1,13211,215,215,215
BEGIN DESCRIPTION:
Guadalupe Tributary 25 29.0
END DESCRIPTION:
XS GIS Cut Line= 3
      2241024.97     13876724.98      2240725.00     13876475.00
      2240425.01     13876375.00
#Sta/Elev= 30
  4609.1 1082.73  4612.3 1082.73  4616.2 1078.29  4665.7 1061.80  4694.3 1049.46
  4708.6 1045.78  4715.2 1047.19  4723.0 1044.41  4758.1 1039.03  4772.4 1034.59
  4829.7 1023.82  4879.2 1007.62  4907.8 1004.80  4949.5 1003.58  4963.8 1001.83
  4971.6  997.30  4978.1  998.70  4990.4  996.38  4990.7  995.88  4994.4  996.38
  5041.7  999.80  5073.4  997.32  5083.9 1006.09  5094.4 1011.43  5136.6 1014.04
  5147.2 1016.56  5168.2 1017.19  5199.9 1021.74  5294.7 1038.95  5315.8 1044.53
#Mann=3,-1,0
  4609.1    0.12       0  4990.4    0.05       0  4994.4    0.12       0
Bank Sta=4990.4,4994.4
Exp/Cntr=0.3,0.1

Type RM Length L Ch R = 1,12996,257,257,257
BEGIN DESCRIPTION:
A19278
END DESCRIPTION:
XS GIS Cut Line= 3
      2241102.28     13876331.32      2240747.57     13876262.67
      2240119.07     13876274.10
#Sta/Elev= 30
  4603.3 1062.91  4664.8 1049.38  4671.8 1045.58  4711.5 1035.89  4804.2 1015.99
  4877.0 1006.65  4923.7 1007.10  4968.4 1002.91  4997.2  998.89  5015.2  992.53
  5015.4  992.03  5019.2  992.53  5117.2  999.02  5157.2 1005.44  5227.2 1004.95
  5237.2 1009.39  5257.2 1024.29  5267.2 1029.43  5287.2 1035.18  5327.2 1035.65
  5347.2 1041.95  5365.1 1043.88  5370.1 1048.74  5407.2 1055.36  5447.2 1066.15
  5497.2 1077.00  5527.3 1089.74  5577.3 1105.71  5587.3 1111.92  5593.2 1118.65
#Mann=3,-1,0
  4603.3    0.12       0  5015.2    0.05       0  5019.2    0.12       0
Bank Sta=5015.2,5019.2
Exp/Cntr=0.3,0.1

Type RM Length L Ch R = 1,12739,487,487,487
BEGIN DESCRIPTION:
Guadalupe Tributary 25 28.0
END DESCRIPTION:
XS GIS Cut Line= 3
      2241024.97     13876124.99      2240825.00     13876075.00
      2240524.95     13875974.98
#Sta/Elev= 30
  4793.9 1030.81  4817.1 1027.50  4845.4 1021.46  4853.1 1018.95  4858.3 1018.25
  4894.4 1007.19  4899.5 1006.85  4927.9 1000.65  4935.6  997.79  4940.8  997.37
  4958.8  989.43  4974.8  986.66  4975.1  986.16  4978.8  986.66  5010.6  988.97
  5031.6  991.60  5042.2  995.25  5052.7 1000.32  5063.3 1003.95  5073.8 1005.40
  5105.4 1006.77  5137.1 1009.48  5168.7 1014.13  5189.8 1018.48  5210.8 1024.40
  5231.9 1031.50  5263.5 1043.31  5284.6 1052.88  5313.6 1063.15  5316.3 1063.15
#Mann=3,-1,0
  4793.9    0.12       0  4974.8    0.05       0  4978.8    0.12       0
Bank Sta=4974.8,4978.8
Exp/Cntr=0.3,0.1

Type RM Length L Ch R = 1,12252,269,269,269
BEGIN DESCRIPTION:
Guadalupe Tributary 25 27.0
END DESCRIPTION:
XS GIS Cut Line= 3
      2241224.99     13875924.99      2240925.00     13875625.00
      2240624.98     13875524.99
#Sta/Elev= 30
  4580.0 1054.07  4583.5 1054.07  4613.3 1042.63  4650.7 1034.75  4679.0 1026.64
  4693.1 1024.66  4735.6 1013.36  4778.0 1007.00  4877.0  995.60  4898.2  988.99
  4905.3  985.47  4919.4  983.03  4961.8  981.57  4988.1  977.92  4988.4  977.42
  4992.1  977.92  5000.7  981.00  5006.9  981.00  5014.8  986.16  5025.3  989.60
  5046.4  992.70  5057.0  996.18  5109.7 1000.81  5141.3 1007.03  5151.8 1011.16
  5172.9 1015.58  5215.1 1028.85  5288.9 1049.31  5317.8 1061.70  5320.5 1061.70
#Mann=4,-1,0
  4580.0   0.035       0  4613.3    0.12       0  4988.1    0.05       0
  4992.1    0.12       0
Bank Sta=4988.1,4992.1
Exp/Cntr=0.3,0.1

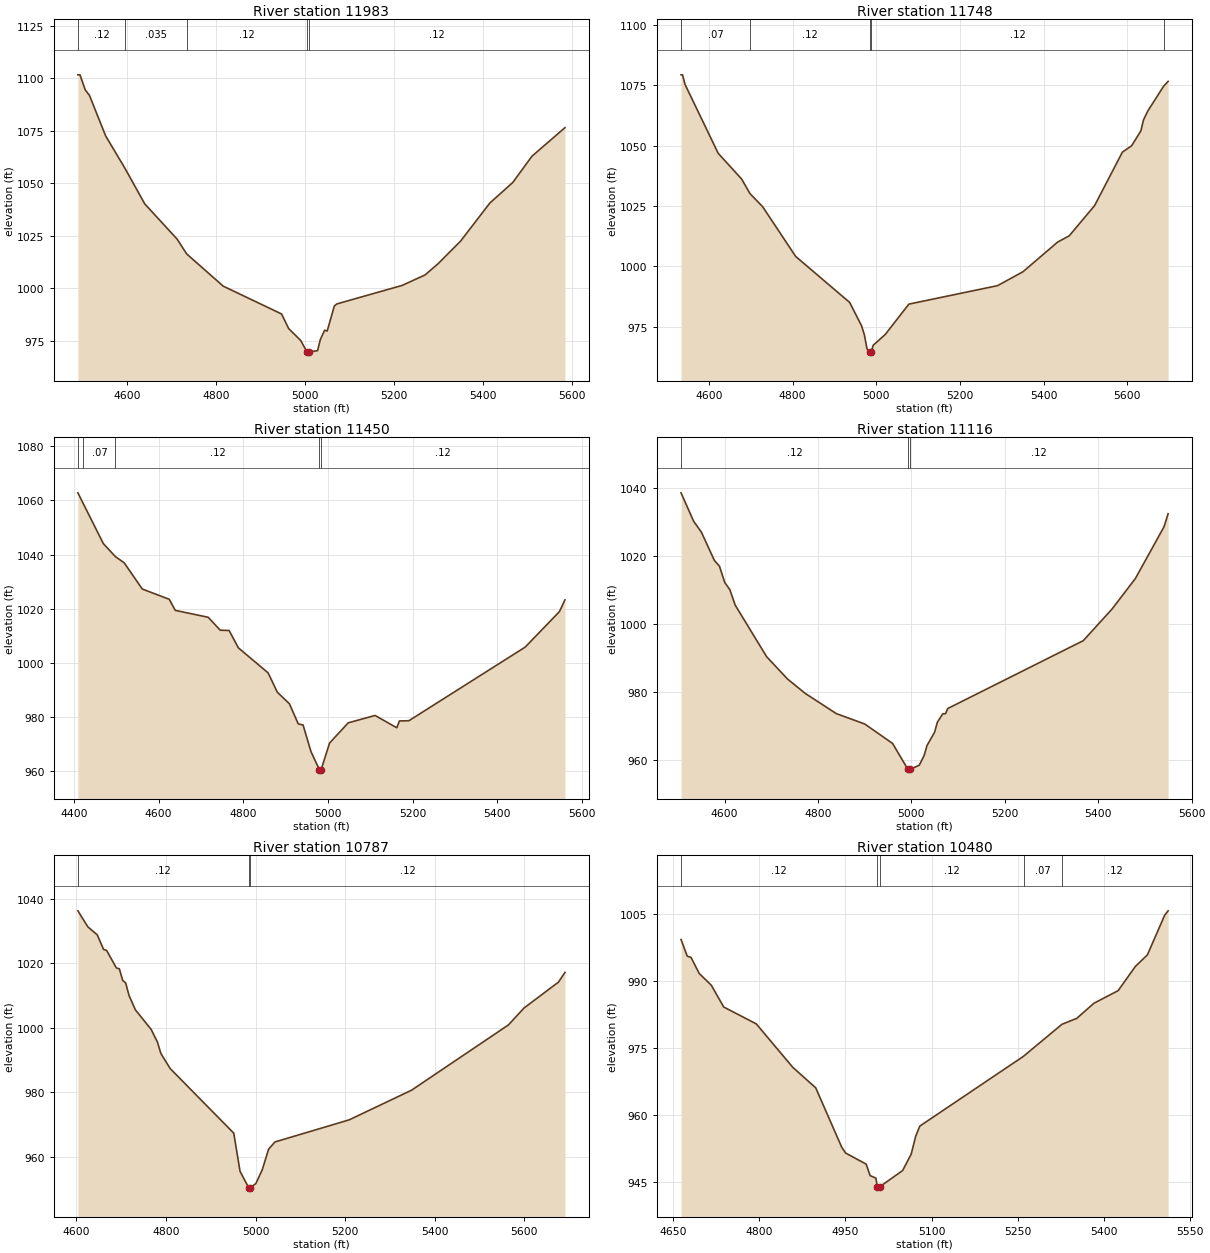
Type RM Length L Ch R = 1,11983,235,235,235
BEGIN DESCRIPTION:
A19277
END DESCRIPTION:
XS GIS Cut Line= 3
      2241384.59     13875919.38      2241067.98     13875358.64
      2240679.63     13875130.20
#Sta/Elev= 30
  4489.8 1101.53  4494.5 1101.53  4506.3 1094.38  4515.8 1091.76  4552.2 1072.45
  4595.7 1056.99  4639.9 1040.14  4713.0 1023.27  4734.2 1016.28  4816.4 1000.93
  4947.5  987.69  4963.4  980.77  4990.8  974.98  5004.7  969.55  5005.0  969.05
  5008.7  969.55  5028.4  970.24  5034.6  975.52  5044.3  979.97  5050.0  979.56
  5066.0  991.45  5071.7  992.47  5218.4 1001.28  5269.9 1006.26  5299.6 1011.69
  5349.9 1022.40  5415.6 1040.52  5467.1 1050.29  5510.0 1062.76  5584.3 1076.38
#Mann=5,-1,0
  4489.8    0.12       0  4595.7   0.035       0  4734.2    0.12       0
  5004.7    0.05       0  5008.7    0.12       0
Bank Sta=5004.7,5008.7
Exp/Cntr=0.3,0.1

Type RM Length L Ch R = 1,11748,298,298,298
BEGIN DESCRIPTION:
A19276
END DESCRIPTION:
XS GIS Cut Line= 3
      2241594.37     13875709.57      2241232.00     13875228.95
      2240732.68     13874969.76
#Sta/Elev= 30
  4533.2 1079.42  4536.8 1079.42  4542.8 1075.42  4621.9 1046.91  4678.1 1036.21
  4698.0 1030.18  4728.1 1024.79  4807.2 1004.14  4936.3  985.07  4964.7  975.41
  4971.7  971.52  4977.9  965.75  4984.2  964.55  4984.5  964.05  4988.2  964.55
  4992.5  967.30  5021.6  971.83  5077.9  984.37  5289.9  992.02  5350.7  997.79
  5433.5 1010.08  5461.3 1012.68  5522.0 1025.23  5588.4 1047.38  5610.5 1050.02
  5632.6 1056.20  5638.8 1060.71  5649.1 1064.42  5687.0 1074.71  5697.7 1076.69
#Mann=5,-1,0
  4533.2    0.07       0  4698.0    0.12       0  4984.2    0.05       0
  4988.2    0.12       0  5687.0   0.035       0
Bank Sta=4984.2,4988.2
Exp/Cntr=0.3,0.1

Type RM Length L Ch R = 1,11450,334,334,334
BEGIN DESCRIPTION:
A19275
END DESCRIPTION:
XS GIS Cut Line= 3
      2241830.89     13875503.62      2241483.76     13875103.07
      2240919.59     13874843.86
#Sta/Elev= 30
  4409.1 1062.78  4421.9 1058.78  4469.2 1044.04  4497.6 1039.24  4518.5 1036.93
  4561.3 1027.25  4624.9 1023.46  4639.2 1019.37  4717.0 1016.82  4745.5 1012.04
  4766.4 1011.94  4788.3 1005.53  4858.5  996.30  4880.4  989.14  4908.9  984.88
  4929.8  977.45  4941.2  977.04  4959.8  967.24  4979.8  960.50  4980.0  960.00
  4983.8  960.50  5003.8  970.37  5047.8  977.83  5111.3  980.56  5162.7  976.01
  5168.9  978.54  5191.2  978.61  5466.0 1005.80  5546.9 1018.90  5560.0 1023.25
#Mann=5,-1,0
  4409.1    0.12       0  4421.9    0.07       0  4497.6    0.12       0
  4979.8    0.05       0  4983.8    0.12       0
Bank Sta=4979.8,4983.8
Exp/Cntr=0.3,0.1

Type RM Length L Ch R = 1,11116,329,329,329
BEGIN DESCRIPTION:
A19274
END DESCRIPTION:
XS GIS Cut Line= 3
      2241968.17     13875000.07      2241468.50     13874744.51
      2241038.71     13874527.72
#Sta/Elev= 30
  4507.0 1038.71  4533.9 1030.33  4550.5 1027.11  4578.3 1018.78  4589.2 1017.07
  4600.5 1012.28  4611.5 1010.13  4622.9 1005.57  4690.3  990.34  4735.2  983.73
  4772.6  979.55  4839.2  973.57  4900.3  970.49  4959.8  964.76  4992.7  957.09
  4993.0  956.59  4996.7  957.09  5016.9  958.34  5027.2  961.15  5033.5  964.14
  5049.7  968.08  5055.7  971.04  5067.4  973.53  5073.0  973.53  5078.0  975.08
  5367.9  995.08  5429.2 1004.36  5479.4 1013.40  5540.7 1028.65  5549.6 1032.54
#Mann=3,-1,0
  4507.0    0.12       0  4992.7    0.05       0  4996.7    0.12       0
Bank Sta=4992.7,4996.7
Exp/Cntr=0.3,0.1

Type RM Length L Ch R = 1,10787,307,307,307
BEGIN DESCRIPTION:
A19273
END DESCRIPTION:
XS GIS Cut Line= 3
      2242052.13     13874858.96      2241651.59     13874492.76
      2241149.08     13874283.38
#Sta/Elev= 30
  4603.4 1036.23  4625.7 1031.26  4646.6 1028.79  4660.8 1024.26  4667.6 1023.94
  4689.2 1018.55  4696.0 1018.24  4703.4 1014.67  4710.1 1013.86  4717.5 1010.02
  4731.7 1005.55  4766.9  999.48  4781.1  995.50  4788.5  992.05  4809.4  987.34
  4951.3  967.32  4965.3  955.49  4984.4  950.47  4984.7  949.97  4988.4  950.47
  5000.6  951.70  5014.8  955.93  5029.0  962.34  5043.2  964.59  5209.1  971.45
  5348.2  980.64  5564.4 1000.87  5599.1 1006.10  5676.0 1014.13  5690.5 1017.14
#Mann=3,-1,0
  4603.4    0.12       0  4984.4    0.05       0  4988.4    0.12       0
Bank Sta=4984.4,4988.4
Exp/Cntr=0.3,0.1

Type RM Length L Ch R = 1,10480,481,481,481
BEGIN DESCRIPTION:
Guadalupe Tributary 25 23.0
END DESCRIPTION:
XS GIS Cut Line= 3
      2242101.73     13874572.90      2241875.00     13874325.00
      2241450.57     13874039.61
#Sta/Elev= 30
  4664.0  999.20  4674.7  995.50  4681.4  995.20  4695.6  991.62  4716.6  989.01
  4738.2  984.15  4794.9  980.38  4858.4  970.69  4898.3  966.12  4943.5  952.88
  4950.3  951.57  4986.1  949.10  4992.9  946.53  5003.0  945.98  5005.4  944.02
  5005.7  943.52  5009.4  944.02  5049.5  947.67  5064.4  951.33  5072.2  955.31
  5079.4  957.58  5259.8  973.15  5326.7  980.29  5352.4  981.61  5382.4  984.99
  5424.4  987.79  5454.4  993.19  5475.4  995.79  5505.4 1004.62  5511.4 1005.60
#Mann=5,-1,0
  4664.0    0.12       0  5005.4    0.05       0  5009.4    0.12       0
  5259.8    0.07       0  5326.7    0.12       0
Bank Sta=5005.4,5009.4
Exp/Cntr=0.3,0.1

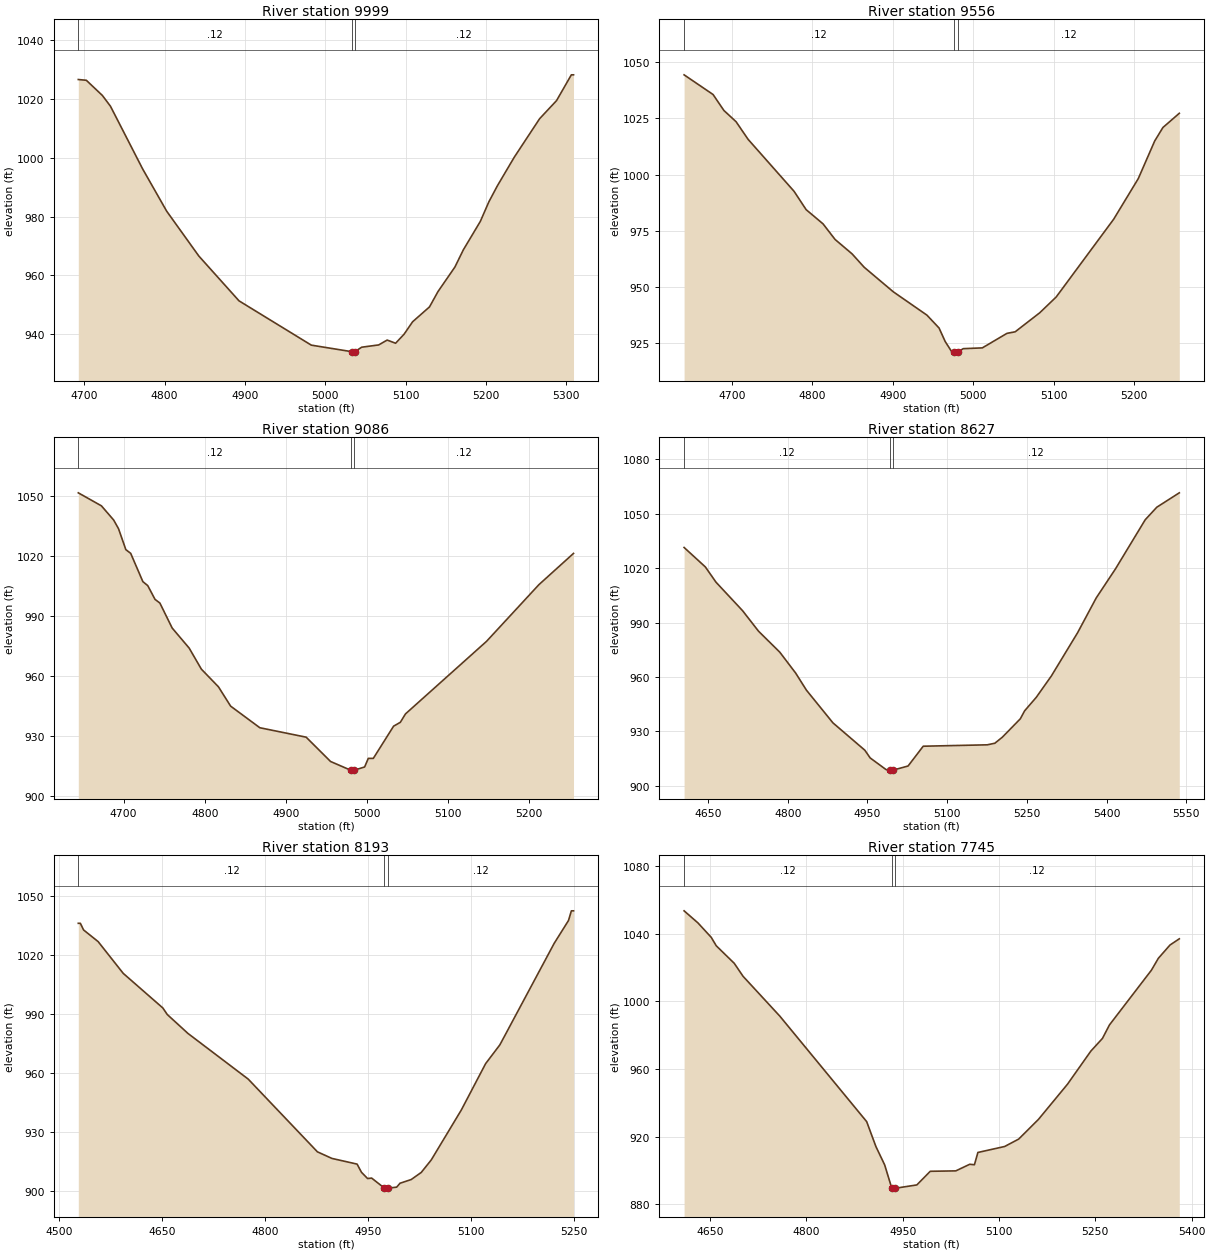
Type RM Length L Ch R = 1,9999,443,443,443
BEGIN DESCRIPTION:
Guadalupe Tributary 25 22.0
END DESCRIPTION:
XS GIS Cut Line= 3
      2242525.04     13874075.00      2242225.00     13874075.00
      2242124.99     13873774.97
#Sta/Elev= 30
  4692.6 1026.70  4702.6 1026.44  4722.6 1021.26  4732.6 1017.61  4772.6  996.27
  4802.6  981.83  4842.6  966.55  4892.6  951.28  4982.6  936.18  5032.8  933.96
  5033.1  933.46  5036.8  933.96  5045.3  935.48  5066.4  936.25  5077.0  937.91
  5087.5  936.83  5098.0  939.90  5108.6  944.13  5129.7  949.22  5140.2  954.42
  5161.3  962.80  5171.8  968.67  5192.9  978.33  5203.5  984.98  5214.0  990.41
  5235.1 1000.20  5266.7 1013.34  5287.8 1019.52  5306.2 1028.30  5308.9 1028.30
#Mann=3,-1,0
  4692.6    0.12       0  5032.8    0.05       0  5036.8    0.12       0
Bank Sta=5032.8,5036.8
Exp/Cntr=0.3,0.1

Type RM Length L Ch R = 1,9556,470,470,470
BEGIN DESCRIPTION:
Guadalupe Tributary 25 21.0
END DESCRIPTION:
XS GIS Cut Line= 3
      2242774.97     13873525.02      2242475.00     13873725.00
      2242224.97     13873674.99
#Sta/Elev= 30
  4640.5 1044.32  4676.5 1035.58  4690.0 1028.48  4705.1 1023.50  4720.1 1015.65
  4777.2  992.58  4792.2  984.44  4813.2  978.13  4828.2  971.19  4849.3  964.80
  4864.3  958.87  4900.4  947.99  4942.4  937.57  4957.4  931.87  4965.0  925.89
  4972.5  921.69  4976.5  921.22  4976.7  920.72  4980.5  921.22  4987.5  922.70
  5011.2  923.05  5041.8  929.50  5052.0  930.19  5082.6  938.66  5103.0  945.66
  5174.4  980.18  5205.0  998.22  5225.4 1014.92  5235.6 1020.91  5256.0 1027.24
#Mann=3,-1,0
  4640.5    0.12       0  4976.5    0.05       0  4980.5    0.12       0
Bank Sta=4976.5,4980.5
Exp/Cntr=0.3,0.1

Type RM Length L Ch R = 1,9086,459,459,459
BEGIN DESCRIPTION:
Guadalupe Tributary 25 20.0
END DESCRIPTION:
XS GIS Cut Line= 3
      2242574.99     13873125.00      2242275.00     13873325.00
      2242125.03     13873524.96
#Sta/Elev= 30
  4644.1 1051.69  4672.6 1045.18  4687.7 1038.08  4693.7 1033.73  4702.7 1023.27
  4708.7 1021.40  4723.7 1007.25  4729.7 1005.27  4738.7  998.37  4744.7  996.52
  4759.8  984.05  4780.8  973.99  4795.8  963.47  4816.9  954.61  4831.9  944.95
  4867.9  934.14  4925.0  929.42  4955.1  917.25  4979.7  912.93  4980.1  912.43
  4984.5  912.93  4997.1  914.51  5001.6  918.81  5007.8  918.81  5032.8  934.93
  5041.1  936.86  5047.4  941.04  5147.4  977.38  5211.9 1005.72  5254.6 1021.38
#Mann=3,-1,0
  4644.1    0.12       0  4979.7    0.05       0  4984.5    0.12       0
Bank Sta=4979.7,4984.5
Exp/Cntr=0.3,0.1

Type RM Length L Ch R = 1,8627,434,434,434
BEGIN DESCRIPTION:
Guadalupe Tributary 25 19.0
END DESCRIPTION:
XS GIS Cut Line= 3
      2242474.96     13872925.00      2242075.00     13872925.00
      2241674.98     13873275.02
#Sta/Elev= 30
  4605.1 1031.41  4645.1 1020.67  4665.1 1012.26  4715.1  996.54  4745.1  985.23
  4785.1  973.66  4815.1  962.07  4835.1  952.75  4885.1  934.66  4945.1  919.57
  4955.1  915.32  4985.1  908.87  4992.7  908.54  4993.0  908.04  4997.5  908.54
  5026.4  910.86  5054.9  921.78  5175.4  922.55  5189.7  923.43  5203.9  926.81
  5237.6  936.92  5245.7  941.32  5267.5  948.73  5296.0  960.55  5345.3  984.39
  5380.4 1003.61  5416.5 1019.58  5472.5 1046.70  5494.3 1053.62  5536.6 1061.55
#Mann=3,-1,0
  4605.1    0.12       0  4992.7    0.05       0  4997.5    0.12       0
Bank Sta=4992.7,4997.5
Exp/Cntr=0.3,0.1

Type RM Length L Ch R = 1,8193,448,448,448
BEGIN DESCRIPTION:
Guadalupe Tributary 25 18.0
END DESCRIPTION:
XS GIS Cut Line= 3
      2241975.00     13872474.99      2241725.00     13872875.00
      2241575.00     13873075.00
#Sta/Elev= 30
  4527.8 1036.21  4530.8 1036.21  4535.5 1032.83  4556.7 1026.92  4593.3 1010.77
  4651.0  993.20  4657.5  989.86  4687.6  980.27  4775.4  957.07  4876.3  920.11
  4897.5  916.76  4934.1  913.88  4940.5  909.72  4949.4  906.55  4955.3  906.78
  4974.0  901.67  4974.4  901.17  4979.1  901.67  4991.8  902.18  4996.6  904.15
  5013.0  906.05  5027.6  909.65  5042.2  916.01  5086.0  941.37  5121.4  964.91
  5142.2  974.48  5221.4 1026.07  5242.2 1037.63  5246.4 1042.55  5249.5 1042.55
#Mann=3,-1,0
  4527.8    0.12       0  4974.0    0.05       0  4979.1    0.12       0
Bank Sta=4974,4979.1
Exp/Cntr=0.3,0.1

Type RM Length L Ch R = 1,7745,471,471,471
BEGIN DESCRIPTION:
Guadalupe Tributary 25 17.0
END DESCRIPTION:
XS GIS Cut Line= 3
      2241725.01     13872274.99      2241475.00     13872575.00
      2241325.01     13872924.99
#Sta/Elev= 30
  4609.5 1053.47  4631.0 1046.36  4651.8 1037.78  4659.6 1032.81  4687.6 1022.46
  4701.3 1014.80  4758.6  991.23  4893.9  928.86  4908.3  914.11  4921.9  903.32
  4933.0  889.48  4933.4  888.98  4938.1  889.48  4972.0  891.46  4992.9  899.52
  5032.7  899.77  5054.4  903.67  5061.7  903.39  5067.1  910.65  5108.8  914.18
  5130.6  918.55  5161.4  930.19  5206.7  951.02  5243.0  970.55  5261.1  978.06
  5272.0  986.02  5337.3 1018.35  5348.2 1025.43  5366.3 1033.26  5380.8 1036.93
#Mann=3,-1,0
  4609.5    0.12       0  4933.0    0.05       0  4938.1    0.12       0
Bank Sta=4933,4938.1
Exp/Cntr=0.3,0.1

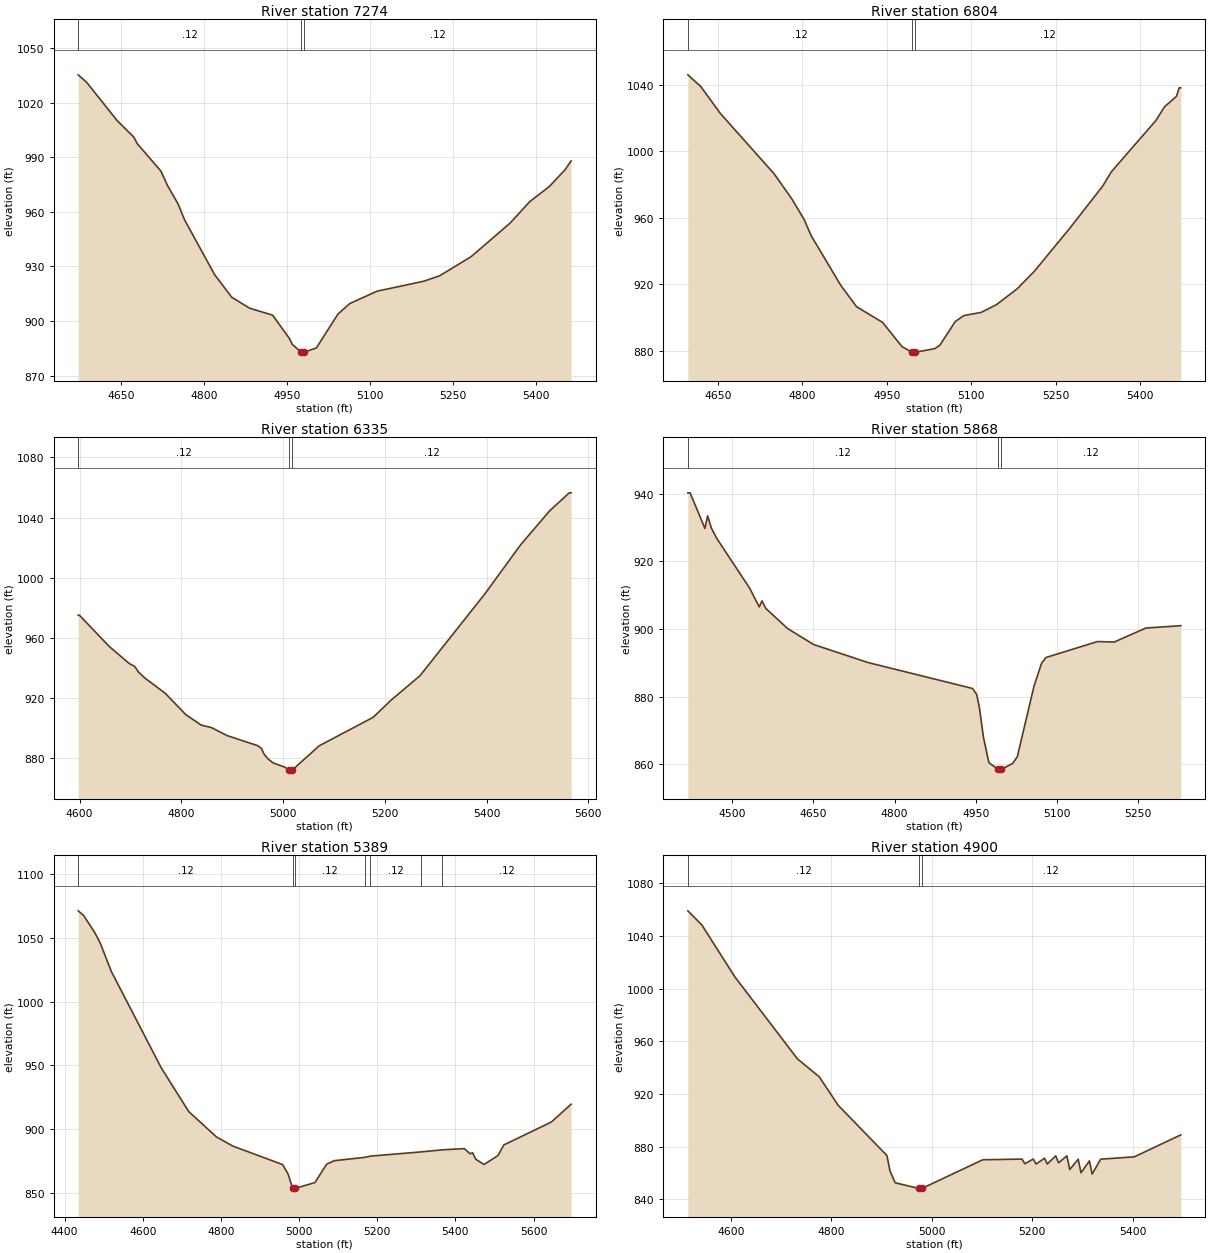
Type RM Length L Ch R = 1,7274,470,470,470
BEGIN DESCRIPTION:
Guadalupe Tributary 25 16.0
END DESCRIPTION:
XS GIS Cut Line= 3
      2241324.99     13871875.03      2241175.00     13872275.00
      2240855.40     13872611.15
#Sta/Elev= 30
  4572.6 1035.32  4587.7 1031.29  4642.9 1010.18  4673.1 1001.09  4679.4  997.46
  4722.1  982.42  4733.7  974.67  4753.2  964.32  4764.8  955.66  4819.1  925.51
  4850.2  913.04  4882.3  907.05  4924.1  903.18  4954.4  890.37  4959.7  887.08
  4975.8  882.81  4976.2  882.31  4981.0  882.81  5003.2  885.17  5042.1  903.77
  5063.5  909.56  5112.8  916.36  5197.8  921.87  5226.1  924.86  5282.7  935.30
  5353.5  953.84  5388.7  965.57  5424.3  973.93  5452.6  983.10  5463.6  987.97
#Mann=3,-1,0
  4572.6    0.12       0  4975.8    0.05       0  4981.0    0.12       0
Bank Sta=4975.8,4981
Exp/Cntr=0.3,0.1

Type RM Length L Ch R = 1,6804,469,469,469
BEGIN DESCRIPTION:
Guadalupe Tributary 25 15.0
END DESCRIPTION:
XS GIS Cut Line= 3
      2241224.99     13871725.00      2240875.00     13871925.00
      2240475.00     13872175.00
#Sta/Elev= 30
  4596.9 1045.84  4619.9 1038.79  4654.5 1022.68  4750.2  986.32  4781.2  971.41
  4803.5  958.77  4815.7  949.24  4868.3  919.38  4896.3  906.57  4942.4  897.15
  4977.0  882.59  4994.4  879.17  4994.8  878.67  4999.8  879.17  5035.4  881.38
  5044.2  883.44  5071.4  897.60  5086.7  901.23  5117.3  903.12  5144.5  907.76
  5181.0  917.20  5211.7  927.78  5275.4  953.98  5333.1  978.97  5348.5  987.60
  5427.5 1018.36  5442.8 1026.60  5464.0 1032.89  5468.8 1038.03  5471.7 1038.03
#Mann=3,-1,0
  4596.9    0.12       0  4994.4    0.05       0  4999.8    0.12       0
Bank Sta=4994.4,4999.8
Exp/Cntr=0.3,0.1

Type RM Length L Ch R = 1,6335,467,467,467
BEGIN DESCRIPTION:
Guadalupe Tributary 25 14.0
END DESCRIPTION:
XS GIS Cut Line= 3
      2240974.96     13871525.01      2240575.00     13871575.00
      2240174.97     13871975.03
#Sta/Elev= 30
  4597.2  975.03  4599.7  975.03  4657.6  954.51  4697.9  942.85  4708.0  941.15
  4715.6  937.38  4728.2  933.32  4768.5  923.09  4808.8  908.96  4839.0  902.03
  4859.2  900.36  4889.4  895.12  4949.9  888.36  4957.4  886.51  4962.5  882.78
  4970.0  879.64  4980.1  876.95  5003.8  874.00  5011.7  871.93  5012.1  871.43
  5017.2  871.93  5071.0  888.27  5177.0  907.20  5212.4  918.67  5269.0  934.83
  5396.3  989.15  5467.0 1021.95  5523.5 1044.32  5562.4 1056.41  5566.0 1056.41
#Mann=3,-1,0
  4597.2    0.12       0  5011.7    0.05       0  5017.2    0.12       0
Bank Sta=5011.7,5017.2
Exp/Cntr=0.3,0.1

Type RM Length L Ch R = 1,5868,479,479,479
BEGIN DESCRIPTION:
Guadalupe Tributary 25 13.0
END DESCRIPTION:
XS GIS Cut Line= 4
      2240858.21     13871166.55      2240275.00     13871225.00
      2240175.00     13871275.00      2239985.06     13871369.97
#Sta/Elev= 30
  4418.2  940.29  4422.3  940.29  4449.7  929.78  4454.7  933.48  4461.6  929.88
  4471.7  926.78  4532.0  912.19  4550.1  906.57  4555.1  908.35  4562.1  906.13
  4602.3  900.19  4650.5  895.45  4750.8  890.13  4944.0  882.46  4951.6  880.69
  4956.7  876.74  4964.1  868.06  4974.2  860.51  4991.5  858.53  4992.0  858.03
  4997.0  858.53  5018.3  860.34  5026.7  862.31  5057.4  883.12  5071.4  889.92
  5079.8  891.63  5174.8  896.33  5205.6  896.19  5264.3  900.33  5328.5  901.02
#Mann=3,-1,0
  4418.2    0.12       0  4991.5    0.05       0  4997.0    0.12       0
Bank Sta=4991.5,4997
Exp/Cntr=0.3,0.1

Type RM Length L Ch R = 1,5389,489,489,489
BEGIN DESCRIPTION:
Guadalupe Tributary 25 12.0
END DESCRIPTION:
XS GIS Cut Line= 4
      2240674.98     13870375.02      2240275.00     13870775.00
      2240175.00     13870775.00      2239689.13     13871119.37
#Sta/Elev= 30
  4434.9 1071.12  4449.0 1067.42  4477.3 1054.07  4491.4 1045.82  4519.7 1023.60
  4647.0  948.26  4717.7  913.79  4788.4  893.92  4830.9  886.66  4958.1  872.18
  4972.3  864.54  4983.6  853.45  4984.0  852.95  4989.3  853.45  5040.6  858.10
  5070.6  872.50  5090.6  875.27  5167.8  877.83  5182.7  878.83  5312.8  882.14
  5366.5  883.76  5422.9  884.71  5437.7  880.62  5443.8  881.53  5452.5  876.31
  5473.4  872.28  5509.1  879.28  5523.8  887.58  5645.7  905.55  5696.1  919.54
#Mann=7,-1,0
  4434.9    0.12       0  4983.6    0.05       0  4989.3    0.12       0
  5167.8    0.07       0  5182.7    0.12       0  5312.8    0.07       0
  5366.5    0.12       0
Bank Sta=4983.6,4989.3
Exp/Cntr=0.3,0.1

Type RM Length L Ch R = 1,4900,463,463,463
BEGIN DESCRIPTION:
Guadalupe Tributary 25 11.0
END DESCRIPTION:
XS GIS Cut Line= 4
      2240217.38     13870090.84      2240038.08     13870411.29
      2239975.00     13870625.00      2239799.88     13870975.23
#Sta/Elev= 30
  4514.3 1059.01  4542.0 1048.36  4608.2 1008.68  4732.6  946.55  4776.0  932.91
  4813.7  911.29  4910.7  873.16  4916.7  861.64  4927.1  852.48  4974.4  848.13
  4974.9  847.63  4980.2  848.13  5101.7  869.93  5179.8  870.45  5185.4  866.89
  5202.2  870.47  5207.7  866.70  5224.5  871.08  5230.1  866.74  5246.9  872.89
  5252.5  867.63  5269.2  872.90  5274.8  862.51  5291.6  870.36  5297.2  860.06
  5314.0  869.07  5319.5  859.04  5336.3  870.37  5403.4  872.17  5495.9  888.82
#Mann=3,-1,0
  4514.3    0.12       0  4974.4    0.05       0  4980.2    0.12       0
Bank Sta=4974.4,4980.2
Exp/Cntr=0.3,0.1

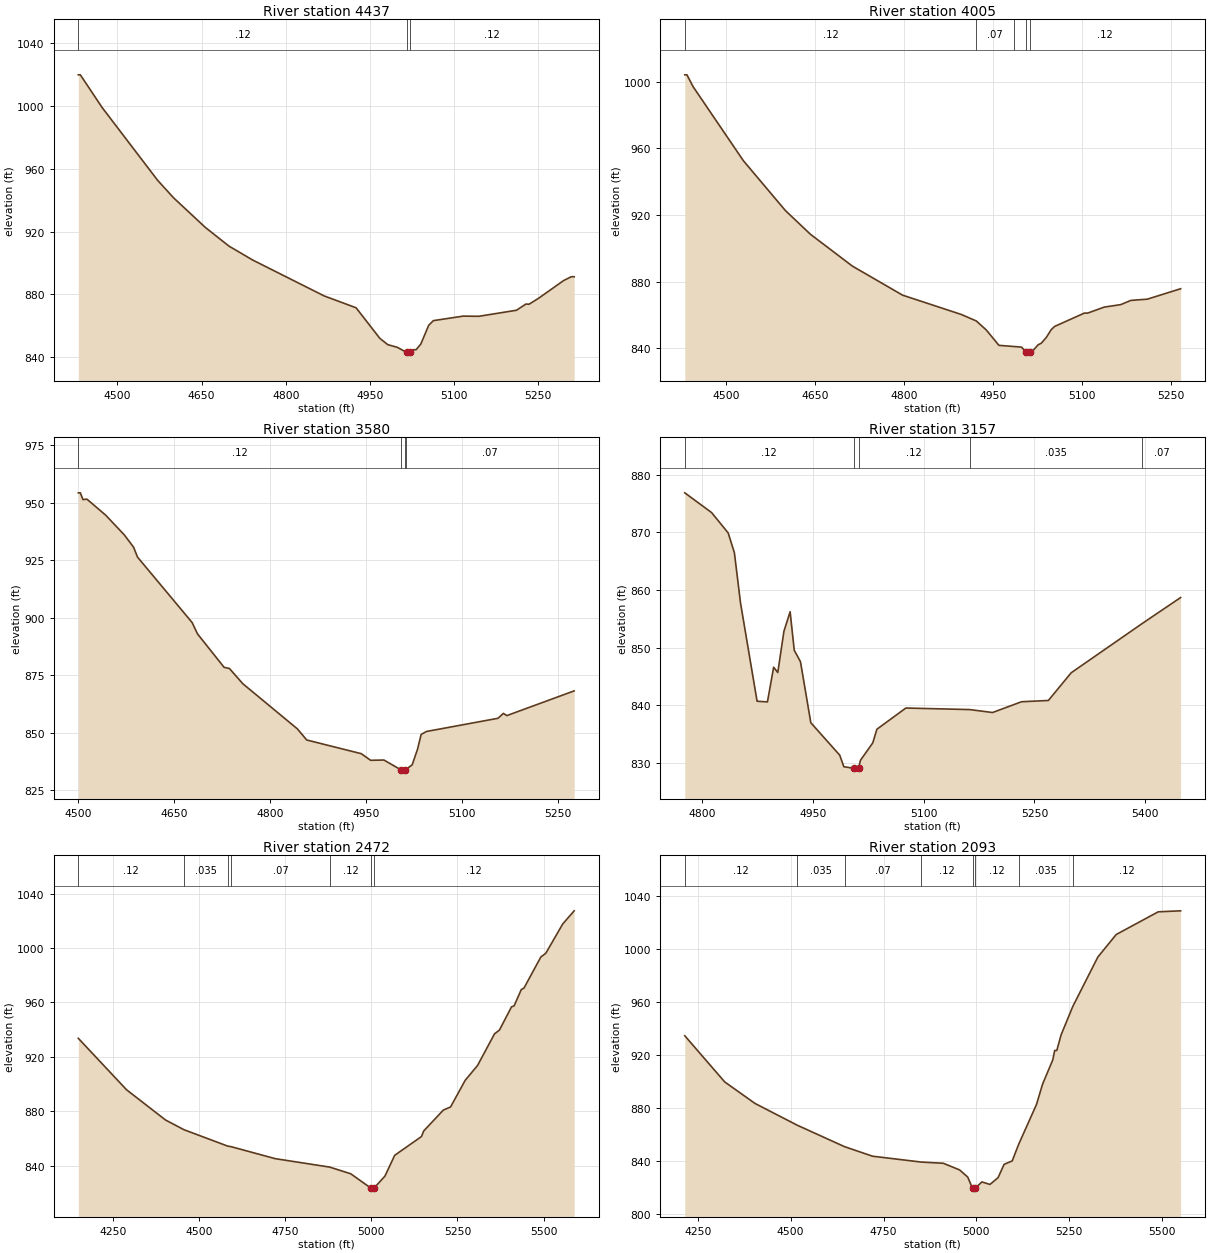
Type RM Length L Ch R = 1,4437,432,432,432
BEGIN DESCRIPTION:
Guadalupe Tributary 25 10.0
END DESCRIPTION:
XS GIS Cut Line= 4
      2239975.01     13870024.99      2239575.00     13870425.00
      2239525.00     13870525.00      2239432.79     13870709.42
#Sta/Elev= 30
  4430.2 1020.00  4433.8 1020.00  4472.6  999.15  4571.6  952.68  4599.9  941.56
  4656.5  922.67  4698.9  910.68  4741.3  901.79  4868.6  878.91  4925.2  871.40
  4967.6  851.88  4981.8  847.86  4998.7  846.17  5015.1  842.96  5015.6  842.46
  5021.4  842.96  5026.7  844.62  5032.2  844.64  5040.6  848.23  5054.6  860.18
  5063.0  863.19  5116.1  866.07  5144.0  865.96  5211.1  869.81  5227.9  873.77
  5233.5  873.66  5250.3  877.40  5295.0  888.73  5308.6  891.19  5313.9  891.19
#Mann=3,-1,0
  4430.2    0.12       0  5015.1    0.05       0  5021.4    0.12       0
Bank Sta=5015.1,5021.4
Exp/Cntr=0.3,0.1

Type RM Length L Ch R = 1,4005,425,425,425
BEGIN DESCRIPTION:
Guadalupe Tributary 25 9.0
END DESCRIPTION:
XS GIS Cut Line= 4
      2239575.03     13869924.97      2239175.00     13870325.00
      2239125.00     13870425.00      2239053.60     13870567.81
#Sta/Elev= 30
  4429.7 1004.18  4433.3 1004.18  4443.9  996.97  4528.7  952.56  4599.5  922.70
  4641.9  908.41  4712.6  889.33  4797.4  871.87  4896.4  860.29  4921.9  856.37
  4938.9  850.91  4960.1  841.72  4985.8  841.02  4998.2  840.65  5006.2  837.55
  5006.7  837.05  5012.6  837.55  5017.8  838.64  5026.2  842.03  5031.8  843.05
  5040.2  846.53  5048.5  851.20  5054.1  853.07  5104.4  861.10  5110.0  861.10
  5138.0  864.70  5165.9  866.19  5182.7  868.70  5210.7  869.46  5266.9  875.72
#Mann=5,-1,0
  4429.7    0.12       0  4921.9    0.07       0  4985.8    0.12       0
  5006.2    0.05       0  5012.6    0.12       0
Bank Sta=5006.2,5012.6
Exp/Cntr=0.3,0.1

Type RM Length L Ch R = 1,3580,423,423,423
BEGIN DESCRIPTION:
Guadalupe Tributary 25 8.0
END DESCRIPTION:
XS GIS Cut Line= 4
      2239224.97     13869825.02      2238825.00     13870125.00
      2238775.00     13870225.00      2238701.69     13870371.63
#Sta/Elev= 30
  4500.0  954.38  4503.1  954.38  4507.3  951.46  4513.5  951.62  4542.7  944.69
  4571.8  936.12  4586.4  930.74  4592.7  926.38  4678.1  897.92  4686.4  893.02
  4728.1  878.43  4736.4  877.95  4757.3  871.32  4842.7  851.67  4857.3  846.83
  4942.7  840.87  4957.3  837.99  4978.1  838.11  5005.1  833.78  5005.6  833.28
  5011.5  833.78  5011.9  833.86  5022.3  836.03  5030.7  842.84  5036.3  849.24
  5044.7  850.54  5156.5  856.27  5164.9  858.40  5170.5  857.45  5275.7  868.20
#Mann=4,-1,0
  4500.0    0.12       0  5005.1    0.05       0  5011.5    0.12       0
  5011.9    0.07       0
Bank Sta=5005.1,5011.5
Exp/Cntr=0.3,0.1

Type RM Length L Ch R = 1,3157,685,685,685
BEGIN DESCRIPTION:
Guadalupe Tributary 25 7.0
END DESCRIPTION:
XS GIS Cut Line= 3
      2238724.99     13869575.02      2238625.00     13869775.00
      2238425.00     13870175.00
#Sta/Elev= 30
  4776.9  876.85  4813.2  873.42  4835.6  869.89  4844.0  866.45  4852.3  857.73
  4874.7  840.69  4888.7  840.57  4897.1  846.59  4902.7  845.67  4911.0  852.82
  4919.4  856.22  4925.0  849.52  4933.4  847.55  4947.4  836.96  4986.5  831.33
  4992.1  829.32  5005.6  829.06  5006.1  828.56  5012.1  829.06  5014.5  830.43
  5031.2  833.46  5036.8  835.83  5076.0  839.51  5162.3  839.24  5193.3  838.73
  5232.5  840.60  5268.8  840.82  5299.6  845.62  5395.8  854.18  5447.7  858.68
#Mann=5,-1,0
  4776.9    0.12       0  5005.6    0.05       0  5012.1    0.12       0
  5162.3   0.035       0  5395.8    0.07       0
Bank Sta=5005.6,5012.1
Exp/Cntr=0.3,0.1

Type RM Length L Ch R = 1,2472,379,379,379
BEGIN DESCRIPTION:
A19272
END DESCRIPTION:
XS GIS Cut Line= 3
      2238775.47     13869217.39      2238210.95     13869789.53
      2237784.89     13870261.24
#Sta/Elev= 30
  4149.5  933.58  4289.5  895.75  4402.7  873.51  4456.3  866.37  4583.2  854.31
  4592.7  853.93  4721.0  845.09  4879.3  838.88  4940.1  833.99  5000.3  823.18
  5000.8  822.68  5006.9  823.18  5039.5  832.21  5067.9  847.54  5145.6  861.34
  5152.3  865.49  5209.1  880.81  5230.1  883.10  5272.6  902.72  5308.5  913.64
  5357.8  936.90  5372.0  939.65  5407.1  956.72  5414.6  957.45  5435.5  969.49
  5443.0  970.44  5492.3  993.42  5506.5  996.10  5555.9 1017.74  5588.9 1027.34
#Mann=7,-1,0
  4149.5    0.12       0  4456.3   0.035       0  4583.2    0.12       0
  4592.7    0.07       0  4879.3    0.12       0  5000.3    0.05       0
  5006.9    0.12       0
Bank Sta=5000.3,5006.9
Exp/Cntr=0.3,0.1

Type RM Length L Ch R = 1,2093,382,382,382
BEGIN DESCRIPTION:
A19271
END DESCRIPTION:
XS GIS Cut Line= 3
      2238733.53     13869118.19      2237856.21     13869594.99
      2237619.84     13869835.17
#Sta/Elev= 30
  4214.8  934.33  4322.3  899.52  4404.0  883.26  4518.0  866.81  4645.0  850.67
  4720.4  843.47  4851.9  839.03  4911.4  838.11  4955.1  833.10  4976.9  827.71
  4989.8  819.12  4990.3  818.62  4996.5  819.12  5015.0  824.05  5036.8  822.15
  5058.7  827.32  5074.8  837.29  5096.7  839.91  5114.0  852.38  5162.2  882.59
  5178.4  897.79  5205.9  916.11  5211.2  923.26  5216.8  923.26  5228.3  934.96
  5259.8  956.42  5327.3  993.71  5376.8 1010.74  5490.0 1027.87  5550.3 1028.61
#Mann=8,-1,0
  4214.8    0.12       0  4518.0   0.035       0  4645.0    0.07       0
  4851.9    0.12       0  4989.8    0.05       0  4996.5    0.12       0
  5114.0   0.035       0  5259.8    0.12       0
Bank Sta=4989.8,4996.5
Exp/Cntr=0.3,0.1