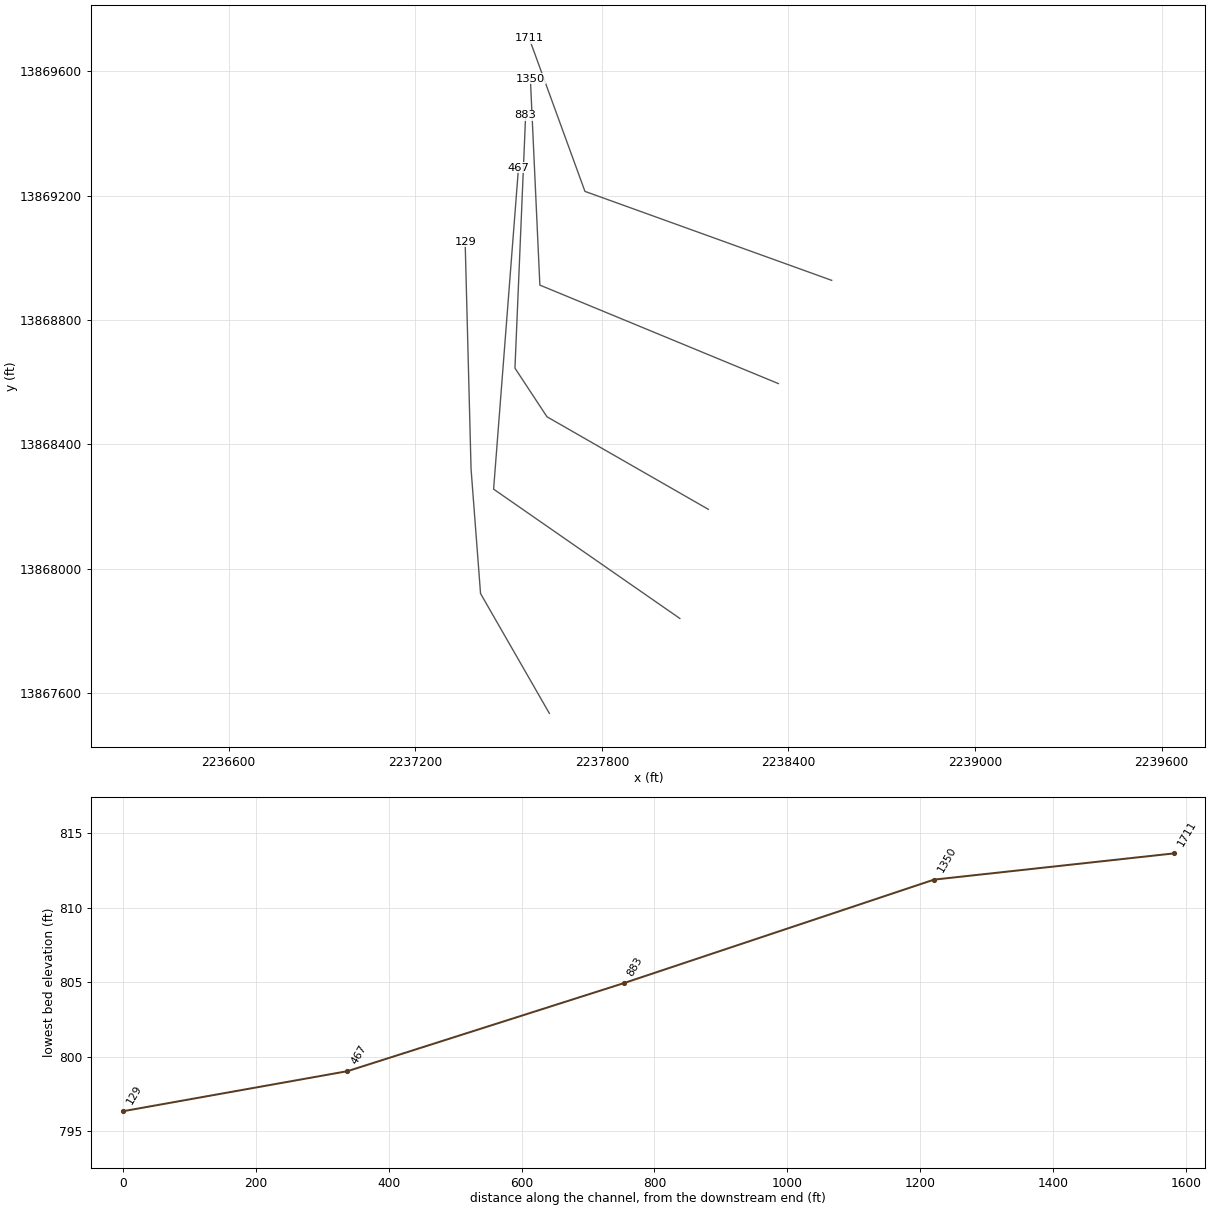
HEC-RAS study Guadalupe Tributary 25.prj: Guadalupe Tributary 25 Base Level Engineering

--- Guadalupe Tributary 25.g01 (geometry) --- (continued)

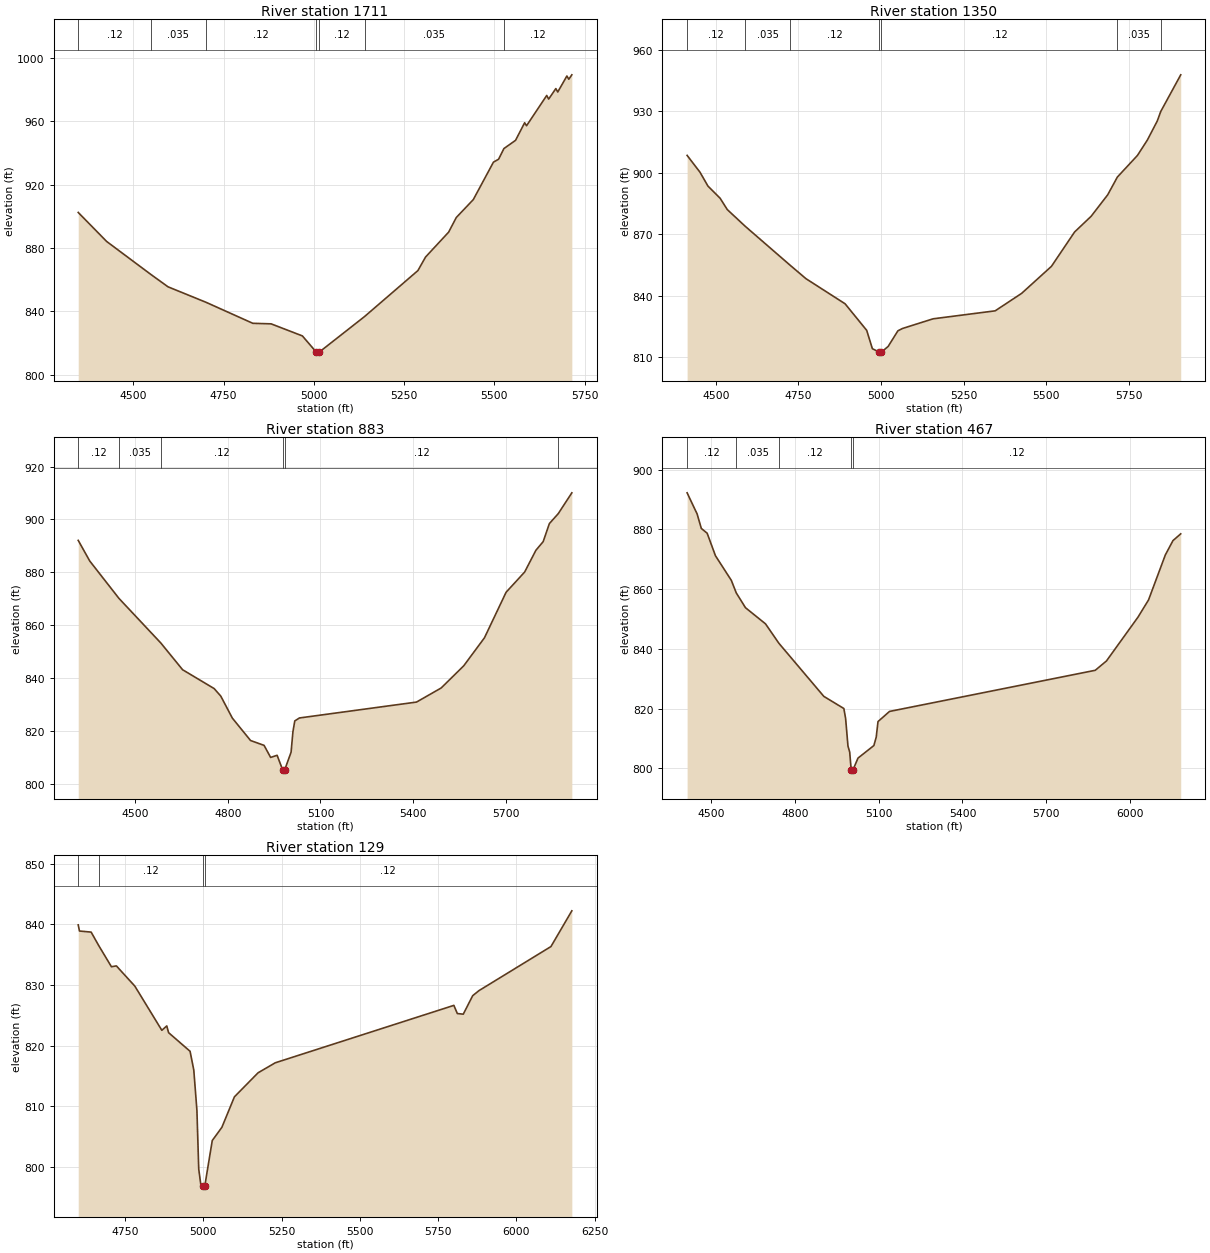
Type RM Length L Ch R = 1,1711,361,361,361
BEGIN DESCRIPTION:
A19270
END DESCRIPTION:
XS GIS Cut Line= 3
      2238538.95     13868927.48      2237745.59     13869213.55
      2237566.30     13869705.64
#Sta/Elev= 30
  4347.3  902.45  4425.9  884.16  4547.8  863.44  4596.0  855.51  4701.5  845.72
  4830.8  832.48  4881.5  832.14  4968.1  824.53  5007.2  814.16  5007.7  813.66
  5014.0  814.16  5140.2  836.72  5288.0  865.74  5309.3  874.32  5373.1  889.99
  5394.4  899.25  5441.5  910.56  5497.3  934.19  5511.5  936.03  5526.3  942.76
  5558.5  947.96  5583.7  959.06  5589.0  957.16  5644.8  976.27  5650.2  973.98
  5670.1  980.62  5675.4  978.46  5700.7  988.55  5706.0  986.51  5714.4  989.30
#Mann=7,-1,0
  4347.3    0.12       0  4547.8   0.035       0  4701.5    0.12       0
  5007.2    0.05       0  5014.0    0.12       0  5140.2   0.035       0
  5526.3    0.12       0
Bank Sta=5007.2,5014
Exp/Cntr=0.3,0.1

Type RM Length L Ch R = 1,1350,467,467,467
BEGIN DESCRIPTION:
A19269
END DESCRIPTION:
XS GIS Cut Line= 3
      2238367.34     13868595.61      2237600.64     13868912.21
      2237570.12     13869575.91
#Sta/Elev= 30
  4413.3  908.50  4452.3  900.27  4476.3  893.51  4513.2  887.56  4534.9  882.02
  4588.9  873.90  4724.9  854.86  4772.9  848.28  4891.4  836.00  4956.8  823.03
  4974.0  814.07  4994.5  812.40  4995.0  811.90  5001.3  812.40  5021.7  815.16
  5051.2  822.79  5065.0  823.93  5157.7  828.66  5345.7  832.56  5425.8  841.11
  5515.9  854.29  5585.9  871.06  5636.0  878.74  5686.1  889.22  5715.5  897.92
  5776.1  908.45  5806.2  915.99  5836.2  925.30  5846.7  929.94  5907.2  947.85
#Mann=7,-1,0
  4413.3    0.12       0  4588.9   0.035       0  4724.9    0.12       0
  4994.5    0.05       0  5001.3    0.12       0  5715.5   0.035       0
  5846.7    0.12       0
Bank Sta=4994.5,5001.3
Exp/Cntr=0.3,0.1

Type RM Length L Ch R = 1,883,416,416,416
BEGIN DESCRIPTION:
A19268
END DESCRIPTION:
XS GIS Cut Line= 4
      2238142.29     13868191.28      2237623.52     13868488.80
      2237520.53     13868645.19      2237554.86     13869457.68
#Sta/Elev= 30
  4315.5  892.11  4352.9  884.31  4447.4  870.20  4583.2  853.32  4653.5  843.25
  4755.7  836.13  4777.2  833.28  4814.6  824.98  4873.6  816.51  4917.4  814.68
  4938.5  810.13  4959.6  810.93  4977.4  805.45  4977.9  804.95  4984.2  805.45
  5004.8  812.09  5010.8  819.82  5016.8  823.91  5031.9  825.03  5410.9  831.03
  5490.9  836.36  5563.9  844.73  5631.1  855.32  5701.1  872.51  5761.2  880.15
  5797.5  888.34  5821.2  891.64  5841.3  898.46  5870.0  902.20  5914.0  910.07
#Mann=6,-1,0
  4315.5    0.12       0  4447.4   0.035       0  4583.2    0.12       0
  4977.4    0.05       0  4984.2    0.12       0  5870.0   0.035       0
Bank Sta=4977.4,4984.2
Exp/Cntr=0.3,0.1

Type RM Length L Ch R = 1,467,338,338,338
BEGIN DESCRIPTION:
A19267
END DESCRIPTION:
XS GIS Cut Line= 3
      2238050.73     13867840.35      2237451.87     13868256.12
      2237531.98     13869289.89
#Sta/Elev= 30
  4415.0  892.28  4450.9  885.18  4465.8  880.35  4486.7  878.75  4516.4  871.20
  4573.2  862.95  4590.8  858.76  4623.8  853.79  4695.4  848.39  4743.2  841.89
  4904.1  824.08  4975.7  820.02  4982.0  816.70  4990.5  807.43  4996.6  805.44
  5001.9  799.54  5002.4  799.04  5008.8  799.54  5026.3  803.40  5083.1  807.61
  5091.5  810.41  5097.9  815.64  5139.1  819.04  5875.1  832.82  5915.2  835.95
  6028.2  850.66  6065.7  856.39  6125.8  871.47  6153.1  876.27  6180.9  878.54
#Mann=5,-1,0
  4415.0    0.12       0  4590.8   0.035       0  4743.2    0.12       0
  5001.9    0.05       0  5008.8    0.12       0
Bank Sta=5001.9,5008.8
Exp/Cntr=0.3,0.1

Type RM Length L Ch R = 1,129,0,0,0
BEGIN DESCRIPTION:
A19266
END DESCRIPTION:
XS GIS Cut Line= 4
      2237631.17     13867535.16      2237409.91     13867920.45
      2237379.40     13868320.97      2237360.37     13869051.64
#Sta/Elev= 30
  4600.5  839.92  4604.5  838.91  4641.8  838.73  4665.7  836.54  4706.6  833.02
  4722.4  833.16  4781.3  829.83  4867.6  822.54  4883.4  823.26  4889.2  822.15
  4957.8  819.08  4969.7  815.99  4979.7  809.33  4985.5  799.66  4992.4  796.99
  4997.9  796.85  4998.4  796.35  5004.8  796.85  5028.7  804.36  5059.4  806.54
  5099.5  811.57  5175.0  815.53  5229.9  817.18  5800.6  826.65  5811.6  825.30
  5830.6  825.20  5860.7  828.25  5880.7  829.08  6110.7  836.35  6177.4  842.24
#Mann=4,-1,0
  4600.5   0.035       0  4665.7    0.12       0  4997.9    0.05       0
  5004.8    0.12       0
Bank Sta=4997.9,5004.8
Exp/Cntr=0.3,0.1

Chan Stop Cuts=-1