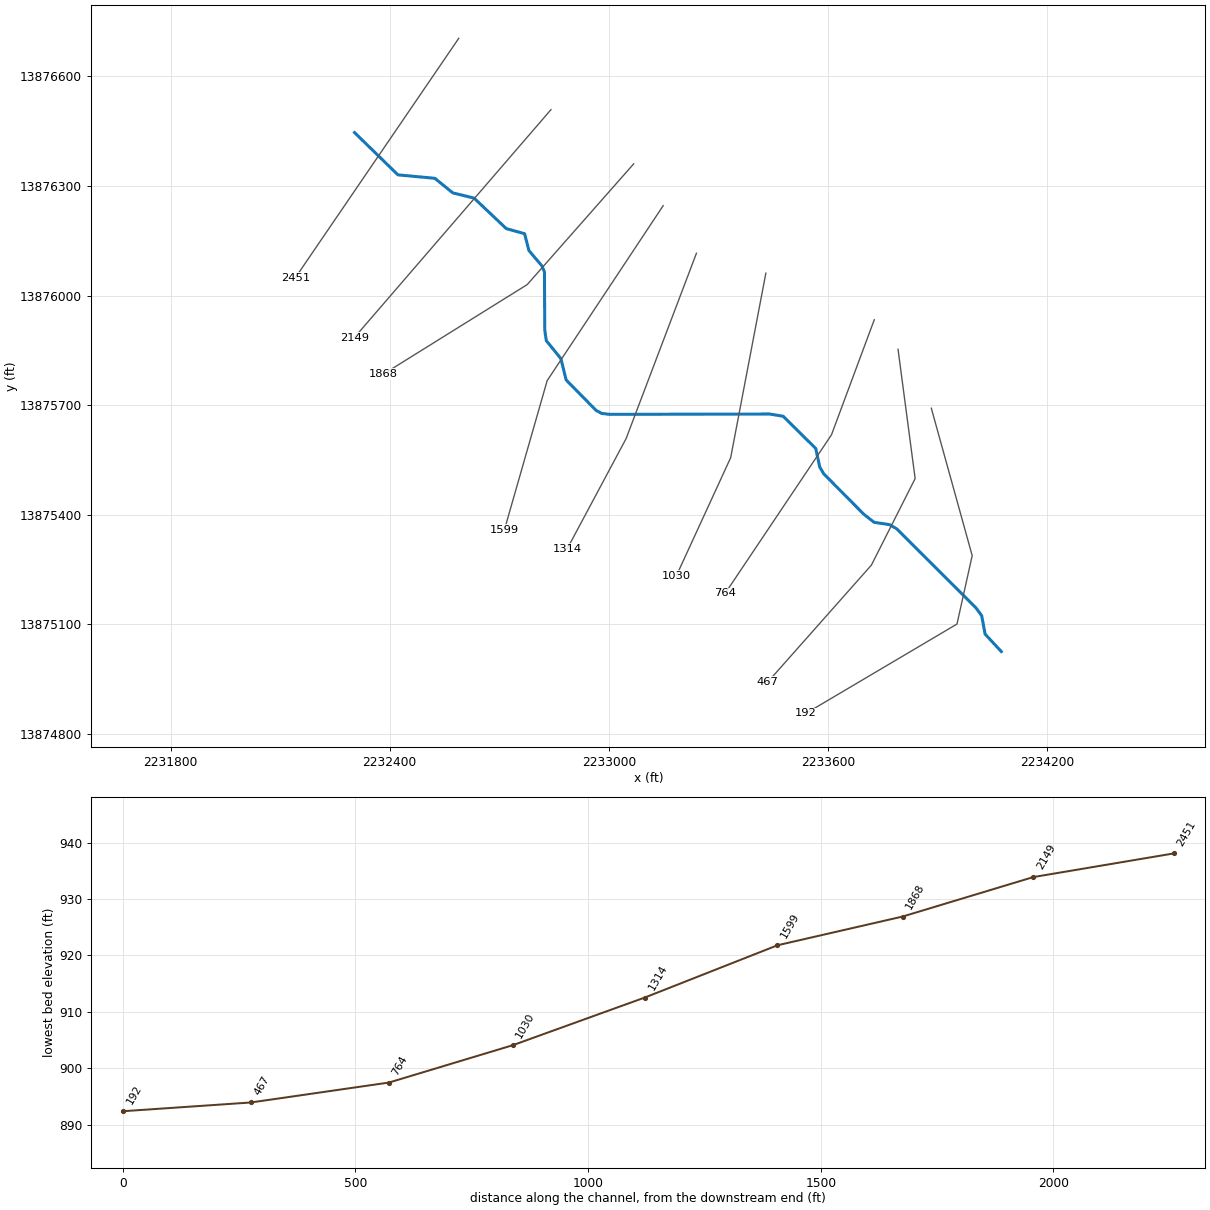
--- Guadalupe Tributary 27.prj (project) ---

Proj Title=Guadalupe Tributary 27 Base Level Engineering
Current Plan=p01
Default Exp/Contr=0.3,0.1
English Units
Geom File=g01
Flow File=f01
Plan File=p01
BEGIN DESCRIPTION:
Guadalupe Tributary 27
END DESCRIPTION:

--- Guadalupe Tributary 27.p01 (plan) ---

Plan Title=Multiple Run
Short Identifier=Multiple
Geom File=g01
Flow File=f01
Subcritical Flow
K Sum by GR= 0
Std Step Tol= 0.01
Critical Tol= 0.01
Num of Std Step Trials= 20
Max Error Tol= 0.3
Flow Tol Ratio= 0.001
Split Flow NTrial= 30
Split Flow Tol= 0.02
Split Flow Ratio= 0.02
Log Output Level= 0
Friction Slope Method= 1
Unsteady Friction Slope Method= 2
Unsteady Bridges Friction Slope Method= 1
Parabolic Critical Depth
Global Vel Dist=  1 , 1 , 1
Global Log Level= 0
CheckData=True
Encroach Param= -1, 0, 0, 0
BEGIN DESCRIPTION:
Multiple Run
END DESCRIPTION:

--- Guadalupe Tributary 27.f01 (steady flow) ---

Flow Title=Multiple
Number of Profiles=7
Profile Names=10-year,25-year,50-year,1pct_min,100-year,1pct_plu,500-year
River Rch & RM= Guadalupe Tribut,Reach-1,2451
    1257    2144    2994    2026    4042    8066    7287
Boundary for River Rch & Prof#=Guadalupe Tribut,Reach-1,1
Up Type=0
Dn Type=3
Dn Slope=0.005
Boundary for River Rch & Prof#=Guadalupe Tribut,Reach-1,2
Up Type=0
Dn Type=3
Dn Slope=0.005
Boundary for River Rch & Prof#=Guadalupe Tribut,Reach-1,3
Up Type=0
Dn Type=3
Dn Slope=0.005
Boundary for River Rch & Prof#=Guadalupe Tribut,Reach-1,4
Up Type=0
Dn Type=3
Dn Slope=0.005
Boundary for River Rch & Prof#=Guadalupe Tribut,Reach-1,5
Up Type=0
Dn Type=3
Dn Slope=0.005
Boundary for River Rch & Prof#=Guadalupe Tribut,Reach-1,6
Up Type=0
Dn Type=3
Dn Slope=0.005
Boundary for River Rch & Prof#=Guadalupe Tribut,Reach-1,7
Up Type=0
Dn Type=3
Dn Slope=0.005

--- Guadalupe Tributary 27.g01 (geometry) ---

Geom Title=Existing Conditions

River Reach=Guadalupe Tribut,Reach-1
Reach XY= 30
      2232303.58     13876446.42      2232422.56     13876330.50
      2232523.41     13876321.17      2232572.83     13876281.14
      2232631.05     13876266.84      2232719.26     13876183.30
      2232769.41     13876169.39      2232781.28     13876123.16
      2232816.92     13876081.12      2232823.81     13876064.52
      2232824.64     13875904.85      2232828.75     13875876.55
      2232868.86     13875827.17      2232883.13     13875768.92
      2232965.18     13875685.47      2232980.43     13875677.17
      2233002.12     13875674.63      2233440.21     13875675.49
      2233477.47     13875669.55      2233566.85     13875581.07
      2233577.65     13875530.64      2233588.63     13875511.79
      2233698.18     13875401.30      2233726.65     13875378.98
      2233768.95     13875372.47      2233788.21     13875361.37
      2234005.24     13875145.10      2234021.19     13875123.42
      2234030.71     13875072.65      2234075.00     13875025.00

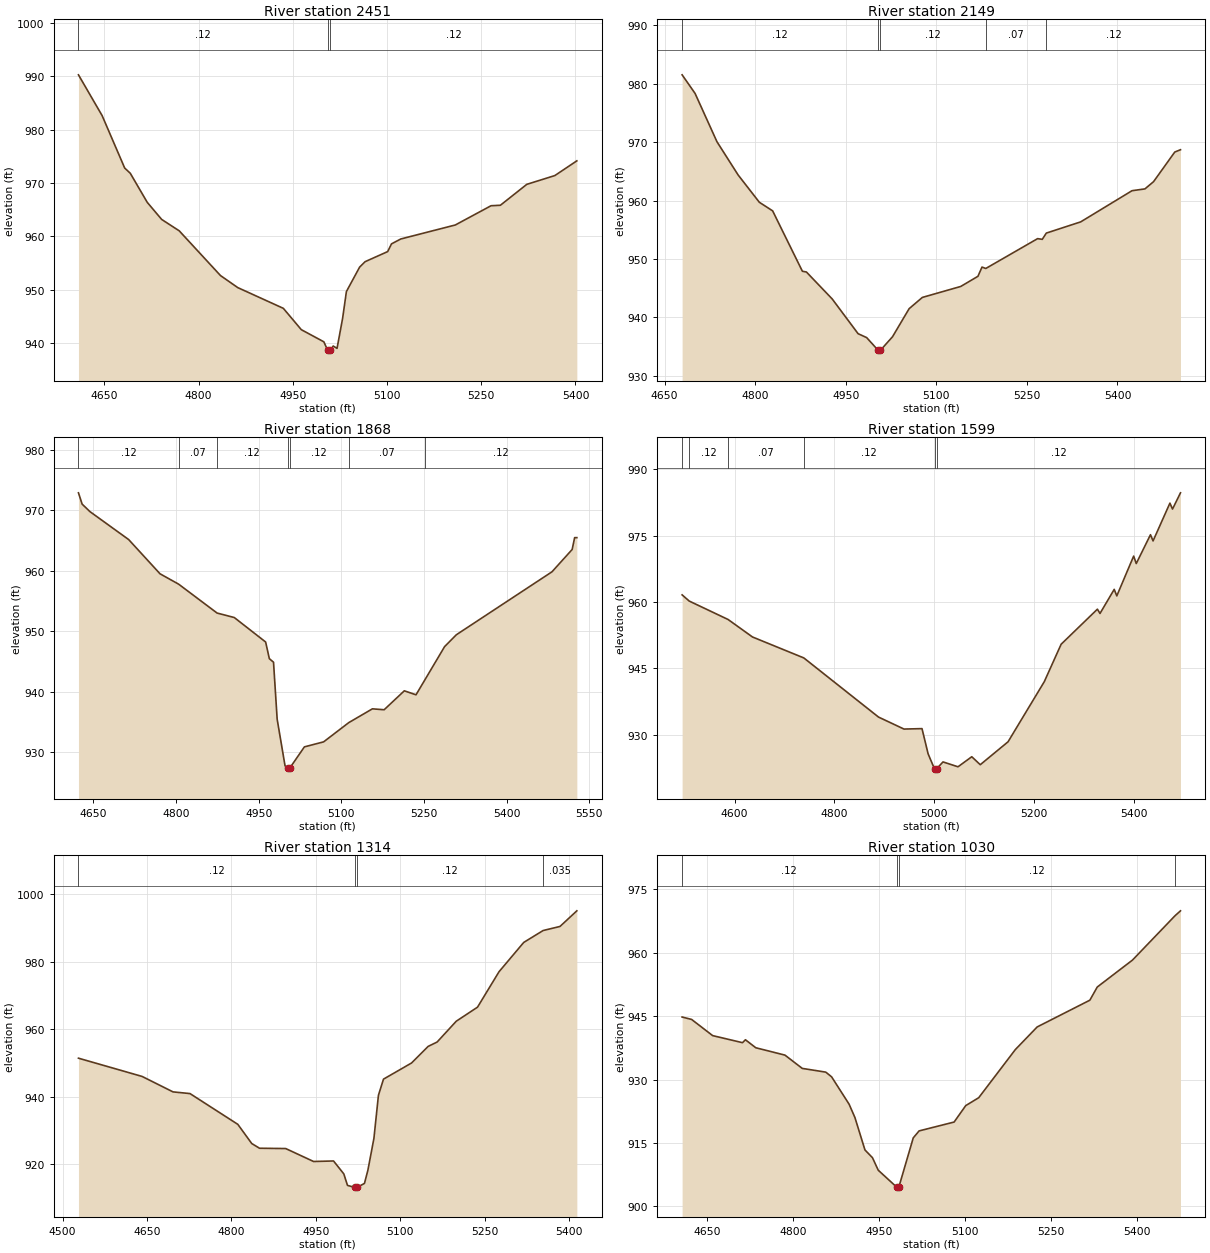
Type RM Length L Ch R = 1,2451,302,302,302
BEGIN DESCRIPTION:
A19289
END DESCRIPTION:
XS GIS Cut Line= 2
      2232589.03     13876704.46      2232141.70     13876049.07
#Sta/Elev= 30
  4608.7  990.26  4646.4  982.61  4682.3  972.78  4691.2  971.80  4718.2  966.35
  4741.2  963.14  4769.1  961.01  4834.8  952.62  4862.3  950.36  4934.9  946.47
  4963.5  942.47  4999.4  940.19  5005.6  938.57  5005.8  938.07  5009.6  938.57
  5014.3  939.40  5020.4  938.96  5029.2  944.54  5035.3  949.61  5056.3  954.19
  5065.1  955.22  5101.0  957.11  5107.1  958.56  5122.0  959.48  5208.7  962.10
  5265.6  965.71  5280.5  965.80  5322.5  969.72  5367.2  971.37  5402.2  974.13
#Mann=3,-1,0
  4608.7    0.12       0  5005.6    0.05       0  5009.6    0.12       0
Bank Sta=5005.6,5009.6
Exp/Cntr=0.3,0.1

Type RM Length L Ch R = 1,2149,281,281,281
BEGIN DESCRIPTION:
A19288
END DESCRIPTION:
XS GIS Cut Line= 2
      2232841.62     13876509.13      2232302.59     13875884.18
#Sta/Elev= 30
  4679.1  981.55  4700.6  978.36  4736.8  970.09  4771.9  964.39  4807.0  959.72
  4829.0  958.25  4878.3  947.90  4884.9  947.78  4927.7  943.15  4970.5  937.21
  4984.7  936.54  5003.6  934.38  5003.9  933.88  5007.6  934.38  5027.5  936.68
  5055.0  941.49  5076.9  943.42  5140.5  945.30  5169.0  947.04  5175.7  948.62
  5182.0  948.38  5267.8  953.49  5275.5  953.37  5282.2  954.44  5339.1  956.36
  5424.1  961.70  5445.5  962.01  5459.8  963.25  5494.9  968.32  5504.4  968.72
#Mann=5,-1,0
  4679.1    0.12       0  5003.6    0.05       0  5007.6    0.12       0
  5182.0    0.07       0  5282.2    0.12       0
Bank Sta=5003.6,5007.6
Exp/Cntr=0.3,0.1

Type RM Length L Ch R = 1,1868,269,269,269
BEGIN DESCRIPTION:
A19287
END DESCRIPTION:
XS GIS Cut Line= 3
      2233068.19     13876360.71      2232776.53     13876029.98
      2232383.26     13875785.17
#Sta/Elev= 30
  4623.1  972.91  4629.8  971.04  4644.0  969.80  4714.2  965.18  4771.1  959.52
  4804.8  957.81  4874.6  953.03  4905.8  952.29  4962.7  948.24  4969.4  945.49
  4977.0  944.90  4983.6  935.48  4997.9  927.77  5002.5  927.39  5002.8  926.89
  5006.5  927.39  5033.0  930.90  5067.9  931.73  5113.5  934.91  5156.4  937.19
  5177.7  937.04  5214.3  940.17  5235.5  939.51  5251.0  941.89  5287.4  947.48
  5308.7  949.44  5482.2  959.85  5518.8  963.54  5523.3  965.50  5527.3  965.50
#Mann=7,-1,0
  4623.1    0.12       0  4804.8    0.07       0  4874.6    0.12       0
  5002.5    0.05       0  5006.5    0.12       0  5113.5    0.07       0
  5251.0    0.12       0
Bank Sta=5002.5,5006.5
Exp/Cntr=0.3,0.1

Type RM Length L Ch R = 1,1599,285,285,285
BEGIN DESCRIPTION:
A19286
END DESCRIPTION:
XS GIS Cut Line= 3
      2233148.95     13876246.16      2232831.22     13875766.96
      2232714.30     13875359.06
#Sta/Elev= 30
  4494.9  961.61  4509.2  960.21  4587.1  956.05  4636.0  952.10  4738.9  947.37
  4888.7  934.01  4939.8  931.30  4975.9  931.40  4988.2  925.69  5001.0  922.30
  5001.2  921.80  5005.0  922.30  5018.0  923.88  5048.1  922.78  5075.7  925.05
  5092.7  923.25  5148.4  928.42  5221.1  942.00  5254.9  950.46  5327.6  958.38
  5332.8  957.41  5361.3  962.85  5366.5  961.38  5400.3  970.37  5405.5  968.68
  5434.0  975.20  5439.2  973.80  5473.0  982.33  5478.2  980.99  5494.2  984.66
#Mann=6,-1,0
  4494.9    0.07       0  4509.2    0.12       0  4587.1    0.07       0
  4738.9    0.12       0  5001.0    0.05       0  5005.0    0.12       0
Bank Sta=5001,5005
Exp/Cntr=0.3,0.1

Type RM Length L Ch R = 1,1314,284,284,284
BEGIN DESCRIPTION:
A19285
END DESCRIPTION:
XS GIS Cut Line= 3
      2233240.06     13876115.91      2233047.36     13875608.11
      2232885.88     13875305.99
#Sta/Elev= 30
  4528.3  951.37  4641.4  945.96  4696.3  941.38  4726.5  940.88  4811.5  931.76
  4836.3  926.06  4850.1  924.67  4896.6  924.58  4946.2  920.74  4981.6  920.90
  4999.9  917.06  5006.4  913.66  5019.3  913.05  5019.5  912.55  5023.3  913.05
  5036.6  914.25  5042.7  918.19  5053.4  927.62  5061.4  940.37  5070.4  945.16
  5120.3  949.95  5149.7  954.86  5165.7  956.16  5199.7  962.33  5237.5  966.50
  5275.7  977.00  5319.6  985.69  5354.1  989.22  5384.1  990.43  5414.0  995.06
#Mann=4,-1,0
  4528.3    0.12       0  5019.3    0.05       0  5023.3    0.12       0
  5354.1   0.035       0
Bank Sta=5019.3,5023.3
Exp/Cntr=0.3,0.1

Type RM Length L Ch R = 1,1030,266,266,266
BEGIN DESCRIPTION:
A19284
END DESCRIPTION:
XS GIS Cut Line= 3
      2233430.18     13876061.28      2233333.82     13875556.02
      2233185.37     13875233.07
#Sta/Elev= 30
  4606.8  944.77  4623.4  944.20  4660.1  940.38  4712.2  938.71  4717.3  939.40
  4735.4  937.51  4786.3  935.77  4816.5  932.63  4857.5  931.75  4867.7  930.64
  4898.2  924.18  4908.4  921.02  4925.9  913.36  4939.0  911.53  4949.1  908.57
  4981.1  904.60  4981.3  904.10  4985.1  904.60  5010.2  916.21  5020.4  917.86
  5081.5  919.95  5101.8  923.84  5124.5  925.71  5188.3  937.07  5226.5  942.43
  5318.4  948.75  5331.4  951.87  5392.8  958.23  5467.0  968.70  5476.6  969.87
#Mann=4,-1,0
  4606.8    0.12       0  4981.1    0.05       0  4985.1    0.12       0
  5467.0   0.035       0
Bank Sta=4981.1,4985.1
Exp/Cntr=0.3,0.1

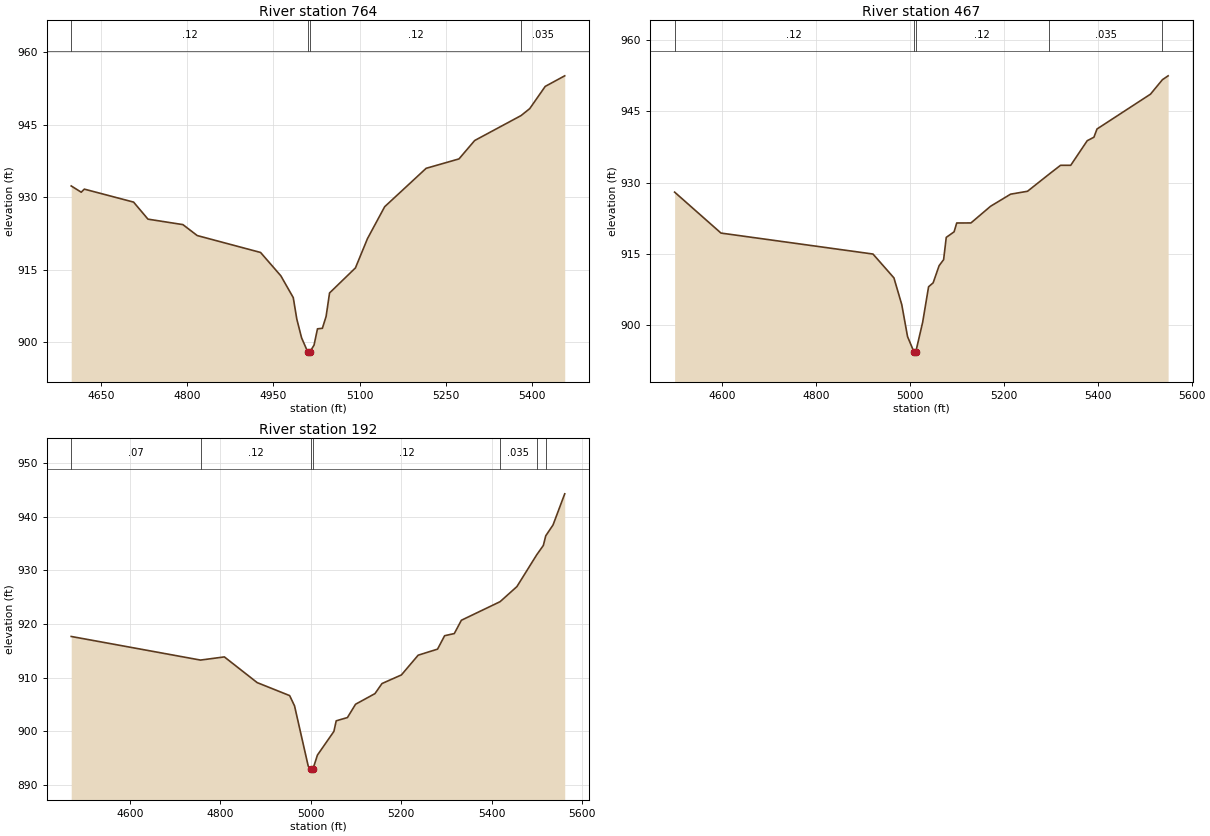
Type RM Length L Ch R = 1,764,297,297,297
BEGIN DESCRIPTION:
A19283
END DESCRIPTION:
XS GIS Cut Line= 3
      2233727.07     13875933.67      2233609.86     13875618.52
      2233319.08     13875184.94
#Sta/Elev= 30
  4598.4  932.33  4615.8  931.03  4621.2  931.67  4706.9  928.98  4731.9  925.45
  4792.6  924.32  4817.6  922.05  4927.7  918.55  4963.0  913.71  4984.6  909.19
  4990.7  904.77  4999.1  900.85  5009.6  897.99  5009.9  897.49  5013.7  897.99
  5020.7  899.35  5026.7  902.73  5035.2  902.84  5041.7  905.30  5047.7  910.16
  5092.7  915.35  5113.7  921.43  5143.6  928.03  5215.7  935.98  5272.8  937.93
  5300.1  941.74  5380.7  946.90  5395.8  948.34  5422.8  952.95  5456.7  955.14
#Mann=4,-1,0
  4598.4    0.12       0  5009.6    0.05       0  5013.7    0.12       0
  5380.7   0.035       0
Bank Sta=5009.6,5013.7
Exp/Cntr=0.3,0.1

Type RM Length L Ch R = 1,467,275,275,275
BEGIN DESCRIPTION:
A19282
END DESCRIPTION:
XS GIS Cut Line= 4
      2233792.16     13875852.86      2233839.03     13875498.73
      2233719.24     13875261.75      2233435.41     13874941.47
#Sta/Elev= 30
  4499.2  928.03  4597.9  919.42  4921.5  915.01  4966.1  910.00  4982.8  904.37
  4995.1  897.65  5008.6  894.46  5008.9  893.96  5012.7  894.46  5027.3  900.67
  5039.9  908.13  5049.6  908.95  5062.3  912.56  5071.9  913.83  5077.5  918.51
  5094.2  919.68  5099.8  921.54  5130.1  921.55  5171.9  925.06  5214.5  927.60
  5250.5  928.21  5295.6  931.74  5320.8  933.67  5342.5  933.67  5377.6  938.84
  5391.9  939.58  5398.5  941.31  5512.3  948.63  5537.8  951.68  5549.9  952.49
#Mann=5,-1,0
  4499.2    0.12       0  5008.6    0.05       0  5012.7    0.12       0
  5295.6   0.035       0  5537.8    0.12       0
Bank Sta=5008.6,5012.7
Exp/Cntr=0.3,0.1

Type RM Length L Ch R = 1,192,0,0,0
BEGIN DESCRIPTION:
A19281
END DESCRIPTION:
XS GIS Cut Line= 4
      2233883.29     13875691.47      2233995.28     13875287.79
      2233953.61     13875100.29      2233539.81     13874855.66
#Sta/Elev= 30
  4469.8  917.69  4755.8  913.29  4808.6  913.88  4881.2  909.09  4953.0  906.67
  4963.8  904.76  4994.0  893.57  5000.1  892.91  5000.4  892.41  5004.2  892.91
  5014.5  895.59  5050.9  900.00  5056.0  901.97  5080.8  902.58  5098.8  905.06
  5141.7  907.04  5157.3  908.92  5200.2  910.52  5237.3  914.20  5280.2  915.33
  5295.8  917.83  5317.2  918.23  5332.9  920.71  5418.5  924.17  5455.7  926.98
  5499.5  932.90  5514.2  934.65  5519.5  936.44  5535.7  938.48  5561.5  944.27
#Mann=7,-1,0
  4469.8    0.07       0  4755.8    0.12       0  5000.1    0.05       0
  5004.2    0.12       0  5418.5   0.035       0  5499.5    0.12       0
  5519.5   0.035       0
Bank Sta=5000.1,5004.2
Exp/Cntr=0.3,0.1

Chan Stop Cuts=-1