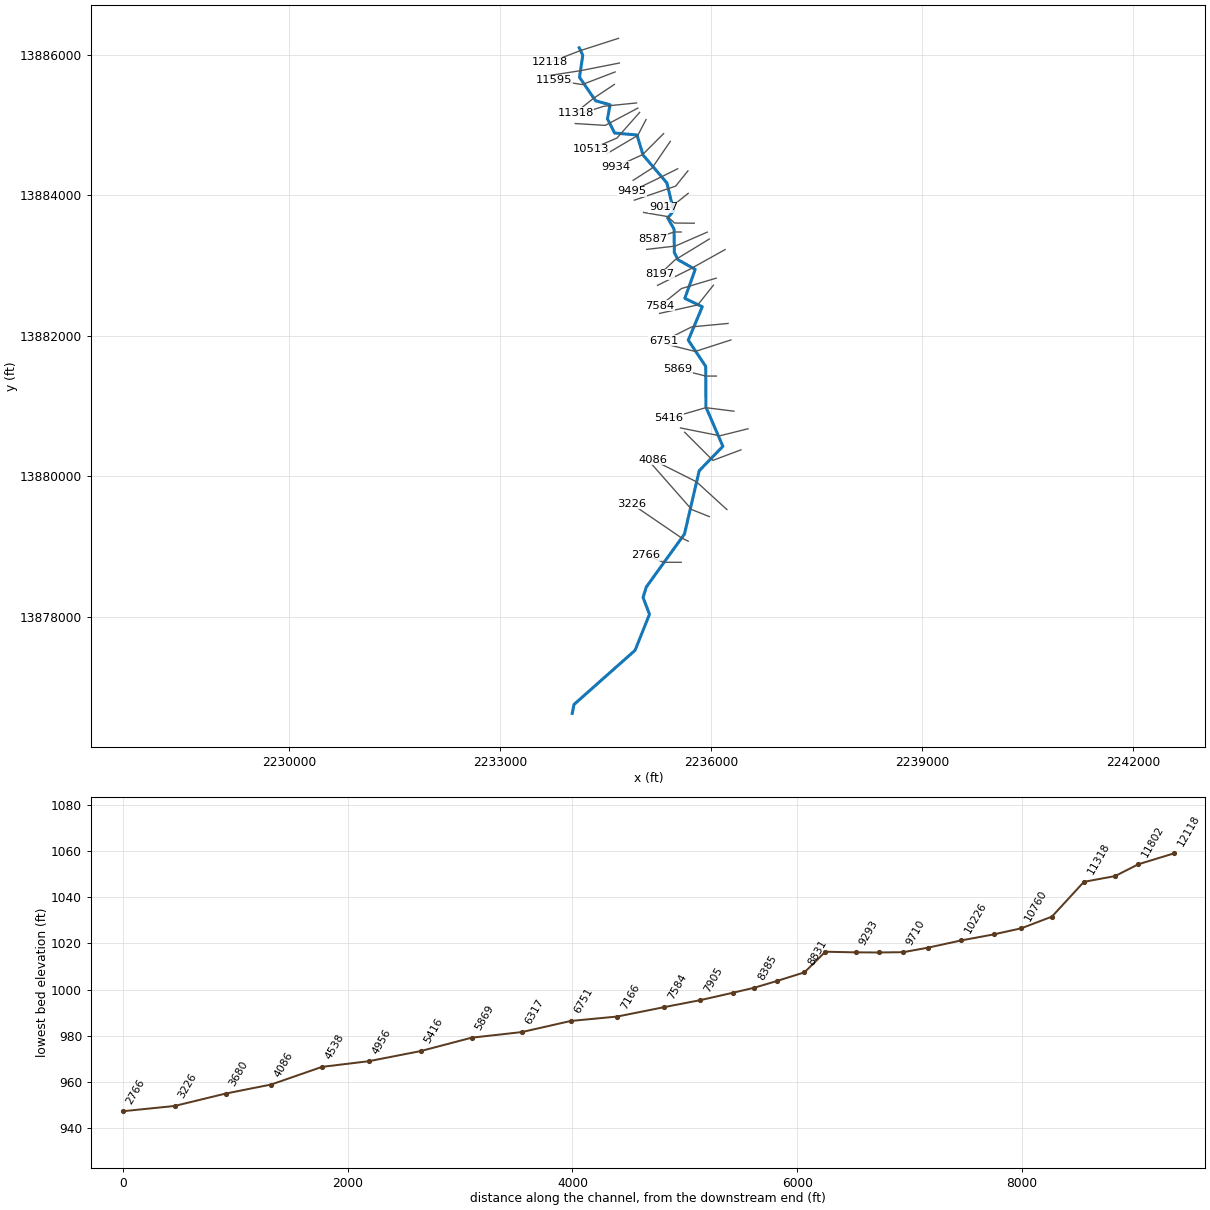
--- Guadalupe Tributary 28.prj (project) ---

Proj Title=Guadalupe Tributary 28 Base Level Engineering
Current Plan=p01
Default Exp/Contr=0.3,0.1
English Units
Geom File=g01
Flow File=f01
Plan File=p01
BEGIN DESCRIPTION:
Guadalupe Tributary 28
END DESCRIPTION:

--- Guadalupe Tributary 28.p01 (plan) ---

Plan Title=Multiple Run
Short Identifier=Multiple
Geom File=g01
Flow File=f01
Subcritical Flow
K Sum by GR= 0
Std Step Tol= 0.01
Critical Tol= 0.01
Num of Std Step Trials= 20
Max Error Tol= 0.3
Flow Tol Ratio= 0.001
Split Flow NTrial= 30
Split Flow Tol= 0.02
Split Flow Ratio= 0.02
Log Output Level= 0
Friction Slope Method= 1
Unsteady Friction Slope Method= 2
Unsteady Bridges Friction Slope Method= 1
Parabolic Critical Depth
Global Vel Dist=  1 , 1 , 1
Global Log Level= 0
CheckData=True
Encroach Param= -1, 0, 0, 0
BEGIN DESCRIPTION:
Multiple Run
END DESCRIPTION:

--- Guadalupe Tributary 28.f01 (steady flow) ---

Flow Title=Multiple
Number of Profiles=7
Profile Names=10-year,25-year,50-year,1pct_min,100-year,1pct_plu,500-year
River Rch & RM= Guadalupe Tribut,Reach-1,12118
    1119    1890    2621    1762    3515    7014    6252
River Rch & RM= Guadalupe Tribut,Reach-1,8197
    1432    2448    3423    2316    4621    9220    8332
River Rch & RM= Guadalupe Tribut,Reach-1,5416
    1768    3050    4290    2918    5822   11615   10609
River Rch & RM= Guadalupe Tribut,Reach-1,2326
    1849    3189    4482    3045    6076   12123   11050
Boundary for River Rch & Prof#=Guadalupe Tribut,Reach-1,1
Up Type=0
Dn Type=3
Dn Slope=0.005
Boundary for River Rch & Prof#=Guadalupe Tribut,Reach-1,2
Up Type=0
Dn Type=3
Dn Slope=0.005
Boundary for River Rch & Prof#=Guadalupe Tribut,Reach-1,3
Up Type=0
Dn Type=3
Dn Slope=0.005
Boundary for River Rch & Prof#=Guadalupe Tribut,Reach-1,4
Up Type=0
Dn Type=3
Dn Slope=0.005
Boundary for River Rch & Prof#=Guadalupe Tribut,Reach-1,5
Up Type=0
Dn Type=3
Dn Slope=0.005
Boundary for River Rch & Prof#=Guadalupe Tribut,Reach-1,6
Up Type=0
Dn Type=3
Dn Slope=0.005
Boundary for River Rch & Prof#=Guadalupe Tribut,Reach-1,7
Up Type=0
Dn Type=3
Dn Slope=0.005

--- Guadalupe Tributary 28.g01 (geometry) ---

Geom Title=Existing Conditions

River Reach=Guadalupe Tribut,Reach-1
Reach XY= 30
      2234125.00     13886095.71      2234175.49     13885990.17
      2234128.73     13885676.53      2234358.20     13885341.42
      2234564.06     13885285.44      2234526.20     13885084.60
      2234628.17     13884883.29      2234945.65     13884855.60
      2235033.14     13884568.94      2235371.17     13884173.42
      2235467.66     13883774.90      2235382.31     13883675.09
      2235473.80     13883514.50      2235477.34     13883180.49
      2235530.41     13883080.18      2235774.29     13882942.12
      2235626.53     13882530.83      2235874.66     13882411.23
      2235675.70     13881935.70      2235923.44     13881562.83
      2235926.36     13880984.65      2236167.47     13880424.99
      2235830.80     13880077.30      2235621.38     13879176.50
      2235078.62     13878423.50      2235032.56     13878275.00
      2235124.07     13878034.85      2234919.17     13877522.70
      2234051.19     13876751.86      2234025.00     13876625.00

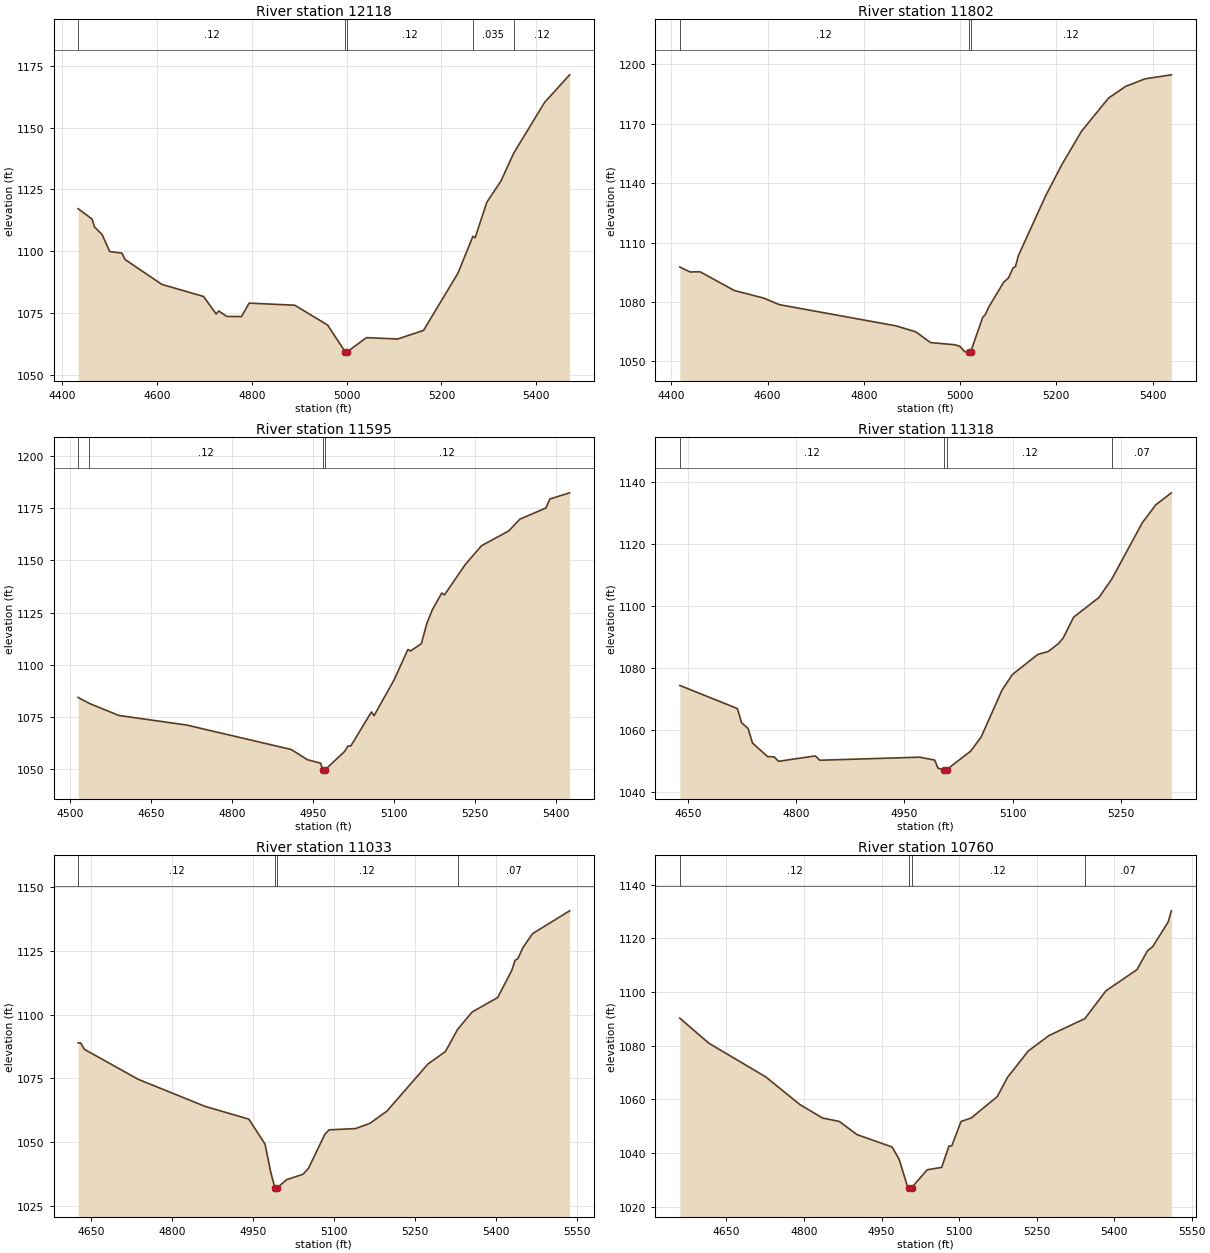
Type RM Length L Ch R = 1,12118,316,316,316
BEGIN DESCRIPTION:
A19305
END DESCRIPTION:
XS GIS Cut Line= 3
      2234682.97     13886230.64      2234133.55     13886053.67
      2233705.68     13885887.27
#Sta/Elev= 30
  4434.0 1117.24  4463.4 1113.06  4468.7 1109.83  4484.4 1106.84  4500.7 1099.90
  4526.4 1099.31  4532.8 1096.75  4610.5 1086.67  4698.4 1081.80  4725.2 1074.69
  4730.5 1075.97  4747.0 1073.74  4778.6 1073.67  4794.6 1079.10  4890.8 1078.26
  4960.2 1070.22  4997.2 1059.41  4997.4 1058.91  5001.2 1059.41  5041.8 1065.17
  5107.8 1064.62  5162.3 1068.08  5235.0 1091.25  5266.3 1106.05  5271.1 1105.50
  5295.6 1119.79  5325.5 1128.43  5352.5 1139.68  5417.4 1160.12  5470.3 1171.29
#Mann=5,-1,0
  4434.0    0.12       0  4997.2    0.05       0  5001.2    0.12       0
  5266.3   0.035       0  5352.5    0.12       0
Bank Sta=4997.2,5001.2
Exp/Cntr=0.3,0.1

Type RM Length L Ch R = 1,11802,207,207,207
BEGIN DESCRIPTION:
A19304
END DESCRIPTION:
XS GIS Cut Line= 3
      2234696.13     13885879.33      2234146.76     13885771.04
      2233690.82     13885699.88
#Sta/Elev= 30
  4417.6 1097.62  4439.1 1095.14  4459.5 1095.26  4530.9 1085.79  4592.0 1081.98
  4624.3 1078.67  4867.2 1067.95  4908.0 1064.94  4938.6 1059.54  4989.4 1058.43
  4999.6 1057.63  5009.7 1054.95  5017.8 1054.72  5018.1 1054.22  5021.8 1054.72
  5047.1 1072.34  5052.2 1073.53  5060.3 1077.81  5090.7 1089.98  5100.8 1092.22
  5109.9 1097.13  5115.0 1097.83  5121.0 1103.30  5177.7 1133.53  5212.1 1149.55
  5252.6 1166.21  5308.4 1182.82  5343.7 1188.70  5384.2 1192.53  5439.0 1194.56
#Mann=3,-1,0
  4417.6    0.12       0  5017.8    0.05       0  5021.8    0.12       0
Bank Sta=5017.8,5021.8
Exp/Cntr=0.3,0.1

Type RM Length L Ch R = 1,11595,277,277,277
BEGIN DESCRIPTION:
A19303
END DESCRIPTION:
XS GIS Cut Line= 3
      2234635.44     13885752.56      2234167.89     13885572.93
      2233763.80     13885636.32
#Sta/Elev= 30
  4515.5 1084.37  4536.5 1081.48  4591.0 1075.74  4716.0 1071.19  4910.0 1059.46
  4940.0 1054.58  4964.7 1052.89  4968.0 1049.61  4968.3 1049.11  4972.0 1049.61
  5008.8 1058.50  5015.2 1061.18  5020.4 1061.18  5058.4 1077.42  5063.4 1075.68
  5100.3 1092.71  5126.0 1107.29  5131.1 1106.63  5150.9 1110.10  5161.0 1119.74
  5171.1 1126.24  5188.7 1134.34  5193.7 1133.45  5231.9 1147.87  5262.2 1156.95
  5312.8 1164.07  5333.1 1169.64  5381.6 1175.03  5388.8 1179.33  5425.4 1182.28
#Mann=4,-1,0
  4515.5   0.035       0  4536.5    0.12       0  4968.0    0.05       0
  4972.0    0.12       0
Bank Sta=4968,4972
Exp/Cntr=0.3,0.1

Type RM Length L Ch R = 1,11318,285,285,285
BEGIN DESCRIPTION:
Guadalupe Tributary 28 25.0
END DESCRIPTION:
XS GIS Cut Line= 3
      2234624.96     13885574.97      2234325.00     13885375.00
      2234074.97     13885174.98
#Sta/Elev= 30
  4639.0 1074.27  4718.6 1066.82  4724.6 1062.23  4733.6 1060.36  4739.6 1055.68
  4760.6 1051.31  4769.7 1051.21  4775.7 1049.79  4826.7 1051.53  4832.8 1050.13
  4971.0 1051.12  4992.0 1050.18  4996.5 1047.56  5004.7 1047.12  5005.0 1046.62
  5008.7 1047.12  5041.9 1053.10  5056.3 1057.64  5085.2 1072.76  5099.6 1077.81
  5134.8 1084.28  5149.2 1085.22  5163.6 1087.80  5170.0 1089.62  5184.4 1096.31
  5219.6 1102.67  5237.5 1108.71  5279.6 1126.81  5298.1 1132.53  5319.7 1136.42
#Mann=4,-1,0
  4639.0    0.12       0  5004.7    0.05       0  5008.7    0.12       0
  5237.5    0.07       0
Bank Sta=5004.7,5008.7
Exp/Cntr=0.3,0.1

Type RM Length L Ch R = 1,11033,273,273,273
BEGIN DESCRIPTION:
A19302
END DESCRIPTION:
XS GIS Cut Line= 3
      2234939.22     13885311.44      2234474.29     13885263.89
      2234052.93     13885129.58
#Sta/Elev= 30
  4626.3 1088.89  4631.0 1088.89  4638.0 1086.39  4737.4 1074.64  4861.7 1063.99
  4942.2 1059.02  4972.3 1049.22  4982.4 1038.56  4990.4 1032.08  4990.7 1031.58
  4994.4 1032.08  5012.5 1035.31  5042.7 1037.43  5052.7 1039.77  5082.9 1053.08
  5090.8 1054.82  5139.8 1055.33  5166.4 1057.37  5197.9 1062.19  5273.8 1080.65
  5306.0 1085.50  5328.7 1094.23  5355.3 1101.00  5402.7 1106.69  5428.8 1117.31
  5434.9 1121.27  5440.1 1121.95  5449.8 1126.37  5467.1 1131.72  5535.9 1140.69
#Mann=4,-1,0
  4626.3    0.12       0  4990.4    0.05       0  4994.4    0.12       0
  5328.7    0.07       0
Bank Sta=4990.4,4994.4
Exp/Cntr=0.3,0.1

Type RM Length L Ch R = 1,10760,247,247,247
BEGIN DESCRIPTION:
Guadalupe Tributary 28 24.0
END DESCRIPTION:
XS GIS Cut Line= 3
      2234957.64     13885237.45      2234495.42     13884991.82
      2234068.76     13885018.16
#Sta/Elev= 30
  4559.8 1090.23  4616.0 1080.89  4725.9 1068.37  4791.9 1058.06  4835.8 1053.03
  4868.4 1051.74  4902.5 1046.84  4970.5 1042.22  4984.0 1037.65  5000.3 1027.49
  5004.0 1027.02  5004.2 1026.52  5008.0 1027.02  5038.4 1033.73  5066.3 1034.62
  5080.6 1042.63  5085.9 1042.63  5103.7 1051.71  5123.7 1053.05  5173.8 1060.98
  5193.9 1068.21  5233.9 1078.00  5274.0 1083.77  5343.4 1090.07  5384.2 1100.43
  5444.3 1108.34  5464.4 1115.32  5474.4 1116.84  5504.5 1126.04  5510.7 1130.24
#Mann=4,-1,0
  4559.8    0.12       0  5004.0    0.05       0  5008.0    0.12       0
  5343.4    0.07       0
Bank Sta=5004,5008
Exp/Cntr=0.3,0.1

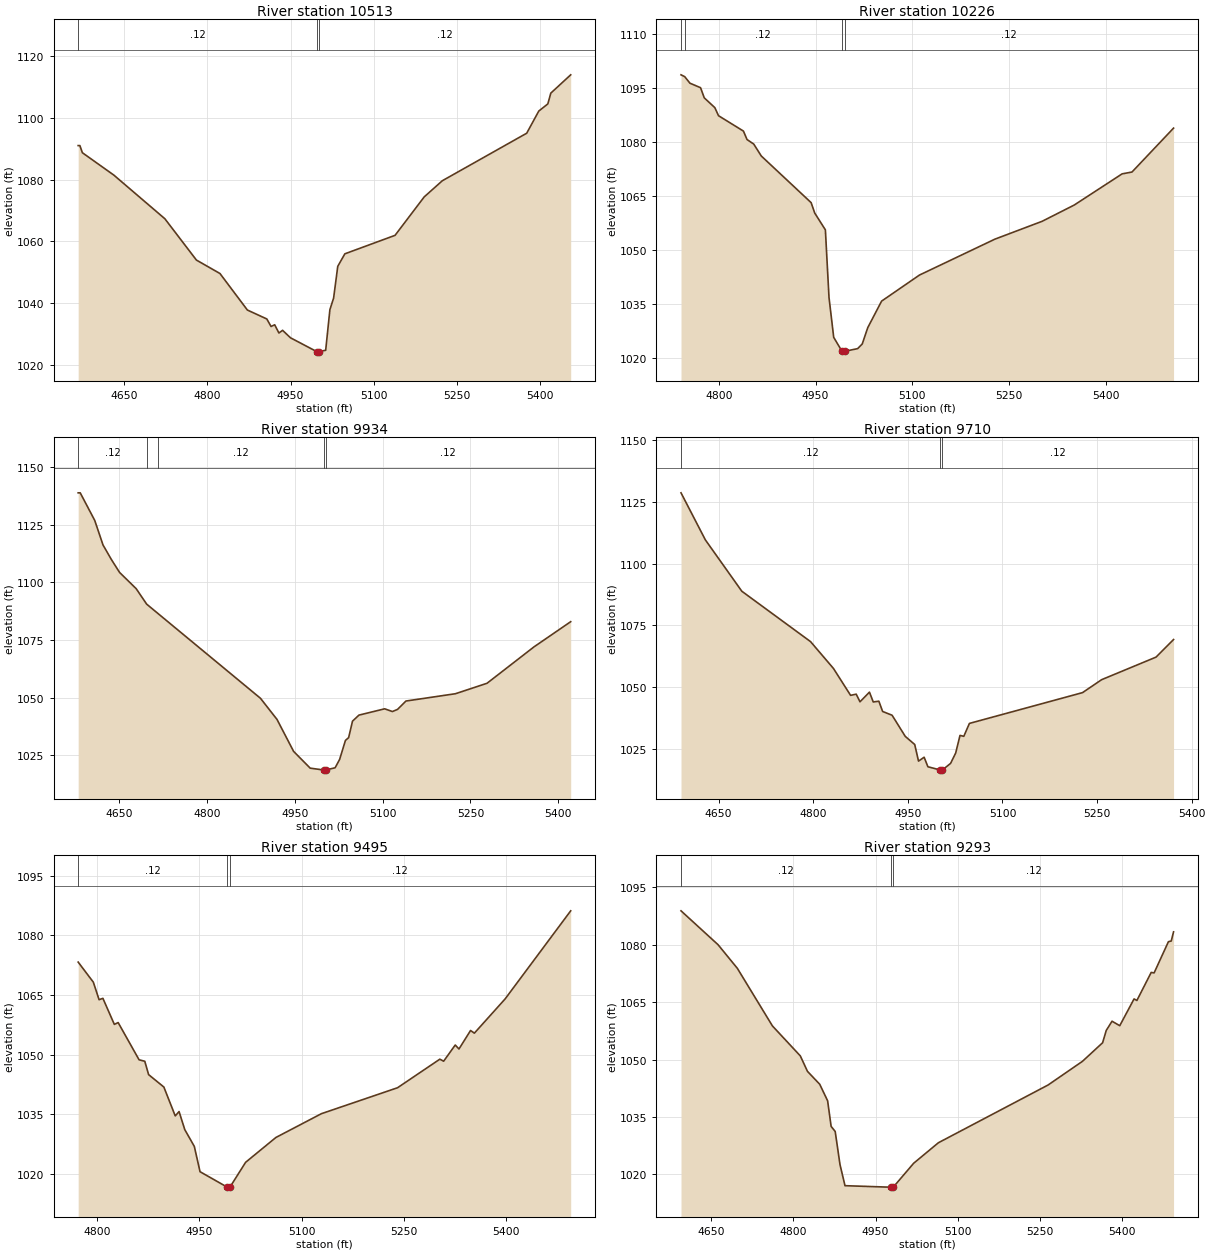
Type RM Length L Ch R = 1,10513,287,287,287
BEGIN DESCRIPTION:
A19301
END DESCRIPTION:
XS GIS Cut Line= 3
      2234984.09     13885176.73      2234661.83     13884812.21
      2234292.01     13884653.71
#Sta/Elev= 30
  4566.7 1091.02  4569.8 1091.02  4574.3 1088.71  4631.2 1081.45  4723.2 1067.34
  4780.1 1053.98  4822.6 1049.63  4872.1 1037.81  4907.2 1034.92  4914.8 1032.49
  4921.4 1033.04  4929.0 1030.38  4935.6 1031.25  4949.9 1028.83  4997.2 1024.37
  4997.5 1023.87  5001.2 1024.37  5013.4 1024.79  5021.0 1037.93  5027.7 1041.67
  5035.2 1051.95  5048.0 1056.00  5138.6 1061.98  5191.2 1074.41  5223.9 1079.64
  5376.2 1095.02  5398.0 1102.19  5414.3 1104.50  5419.7 1107.99  5455.6 1113.91
#Mann=3,-1,0
  4566.7    0.12       0  4997.2    0.05       0  5001.2    0.12       0
Bank Sta=4997.2,5001.2
Exp/Cntr=0.3,0.1

Type RM Length L Ch R = 1,10226,292,292,292
BEGIN DESCRIPTION:
Guadalupe Tributary 28 23.0
END DESCRIPTION:
XS GIS Cut Line= 3
      2235074.99     13885074.98      2234957.67     13884849.18
      2234519.57     13884590.55
#Sta/Elev= 30
  4741.5 1098.56  4747.2 1098.06  4755.3 1096.24  4771.8 1094.98  4777.5 1092.17
  4793.9 1089.45  4799.6 1087.21  4838.2 1082.94  4843.8 1080.59  4854.2 1079.33
  4865.9 1076.02  4943.1 1063.07  4948.7 1060.18  4965.2 1055.51  4970.8 1036.76
  4978.1 1025.66  4991.0 1021.78  4991.2 1021.28  4995.0 1021.78  5015.2 1022.53
  5022.3 1023.82  5030.9 1028.37  5052.3 1035.72  5110.9 1042.95  5227.9 1052.93
  5301.0 1057.88  5350.8 1062.40  5425.0 1071.06  5440.3 1071.57  5504.7 1083.76
#Mann=4,-1,0
  4741.5   0.035       0  4747.2    0.12       0  4991.0    0.05       0
  4995.0    0.12       0
Bank Sta=4991,4995
Exp/Cntr=0.3,0.1

Type RM Length L Ch R = 1,9934,224,224,224
BEGIN DESCRIPTION:
Guadalupe Tributary 28 22.0
END DESCRIPTION:
XS GIS Cut Line= 3
      2235324.99     13884874.99      2235025.00     13884575.00
      2234645.95     13884402.77
#Sta/Elev= 30
  4580.5 1138.77  4584.0 1138.77  4608.8 1126.80  4622.9 1116.18  4637.1 1109.91
  4651.2 1104.27  4679.5 1097.24  4697.4 1090.54  4715.9 1086.65  4891.6 1049.75
  4919.9 1040.57  4948.2 1026.73  4976.5 1019.47  4999.2 1018.68  4999.5 1018.18
  5003.2 1018.68  5019.0 1019.63  5026.7 1023.23  5036.6 1031.46  5042.1 1032.70
  5048.7 1039.82  5059.7 1042.45  5103.6 1045.18  5116.8 1044.00  5125.6 1044.93
  5139.9 1048.55  5224.4 1051.72  5278.3 1056.25  5358.5 1072.03  5421.1 1082.93
#Mann=5,-1,0
  4580.5    0.12       0  4697.4   0.035       0  4715.9    0.12       0
  4999.2    0.05       0  5003.2    0.12       0
Bank Sta=4999.2,5003.2
Exp/Cntr=0.3,0.1

Type RM Length L Ch R = 1,9710,215,215,215
BEGIN DESCRIPTION:
A19300
END DESCRIPTION:
XS GIS Cut Line= 3
      2235419.90     13884764.64      2235158.42     13884381.66
      2234891.63     13884209.96
#Sta/Elev= 30
  4590.3 1128.53  4628.9 1109.54  4686.7 1088.81  4795.7 1068.47  4832.0 1057.64
  4859.2 1046.78  4868.1 1047.26  4874.1 1044.17  4889.1 1048.08  4895.1 1044.11
  4904.0 1044.42  4910.0 1040.27  4925.0 1038.75  4945.9 1030.21  4960.9 1026.93
  4966.9 1020.23  4975.8 1021.80  4981.8 1017.95  5000.8 1016.69  5001.1 1016.19
  5004.8 1016.69  5017.7 1019.29  5025.8 1023.48  5032.7 1030.61  5038.7 1030.24
  5047.6 1035.45  5227.0 1047.88  5257.3 1053.11  5343.5 1062.21  5371.3 1069.31
#Mann=3,-1,0
  4590.3    0.12       0  5000.8    0.05       0  5004.8    0.12       0
Bank Sta=5000.8,5004.8
Exp/Cntr=0.3,0.1

Type RM Length L Ch R = 1,9495,202,202,202
BEGIN DESCRIPTION:
Guadalupe Tributary 28 21.0
END DESCRIPTION:
XS GIS Cut Line= 3
      2235524.99     13884374.99      2235325.00     13884275.00
      2234875.80     13884056.77
#Sta/Elev= 30
  4772.1 1073.29  4794.4 1068.22  4802.8 1063.81  4808.4 1064.16  4825.2 1057.59
  4830.8 1058.05  4861.5 1048.67  4869.9 1048.29  4875.5 1044.93  4897.9 1041.80
  4914.6 1034.52  4920.2 1035.62  4928.6 1031.07  4942.6 1026.84  4951.0 1020.46
  4990.9 1016.57  4991.1 1016.07  4994.9 1016.57  5017.9 1022.83  5062.4 1029.09
  5129.1 1035.08  5240.9 1041.62  5303.0 1048.82  5308.6 1048.31  5325.6 1052.39
  5331.1 1051.39  5348.1 1056.05  5353.7 1055.38  5398.8 1064.00  5495.1 1086.21
#Mann=3,-1,0
  4772.1    0.12       0  4990.9    0.05       0  4994.9    0.12       0
Bank Sta=4990.9,4994.9
Exp/Cntr=0.3,0.1

Type RM Length L Ch R = 1,9293,276,276,276
BEGIN DESCRIPTION:
A19299
END DESCRIPTION:
XS GIS Cut Line= 3
      2235670.83     13884344.65      2235496.52     13884128.08
      2234908.72     13883927.75
#Sta/Elev= 30
  4594.8 1088.89  4662.4 1080.03  4697.6 1073.86  4761.6 1058.80  4812.6 1050.94
  4825.6 1046.91  4848.0 1043.53  4862.4 1039.21  4868.8 1032.52  4876.2 1031.19
  4885.0 1022.52  4894.1 1017.01  4978.1 1016.61  4978.3 1016.11  4982.1 1016.61
  5019.4 1022.87  5064.6 1028.24  5264.9 1043.35  5327.6 1049.54  5364.3 1054.39
  5371.0 1057.62  5381.5 1060.02  5395.6 1058.85  5421.7 1065.85  5426.9 1065.45
  5453.0 1072.78  5458.3 1072.65  5484.4 1080.81  5489.6 1081.00  5493.8 1083.39
#Mann=3,-1,0
  4594.8    0.12       0  4978.1    0.05       0  4982.1    0.12       0
Bank Sta=4978.1,4982.1
Exp/Cntr=0.3,0.1

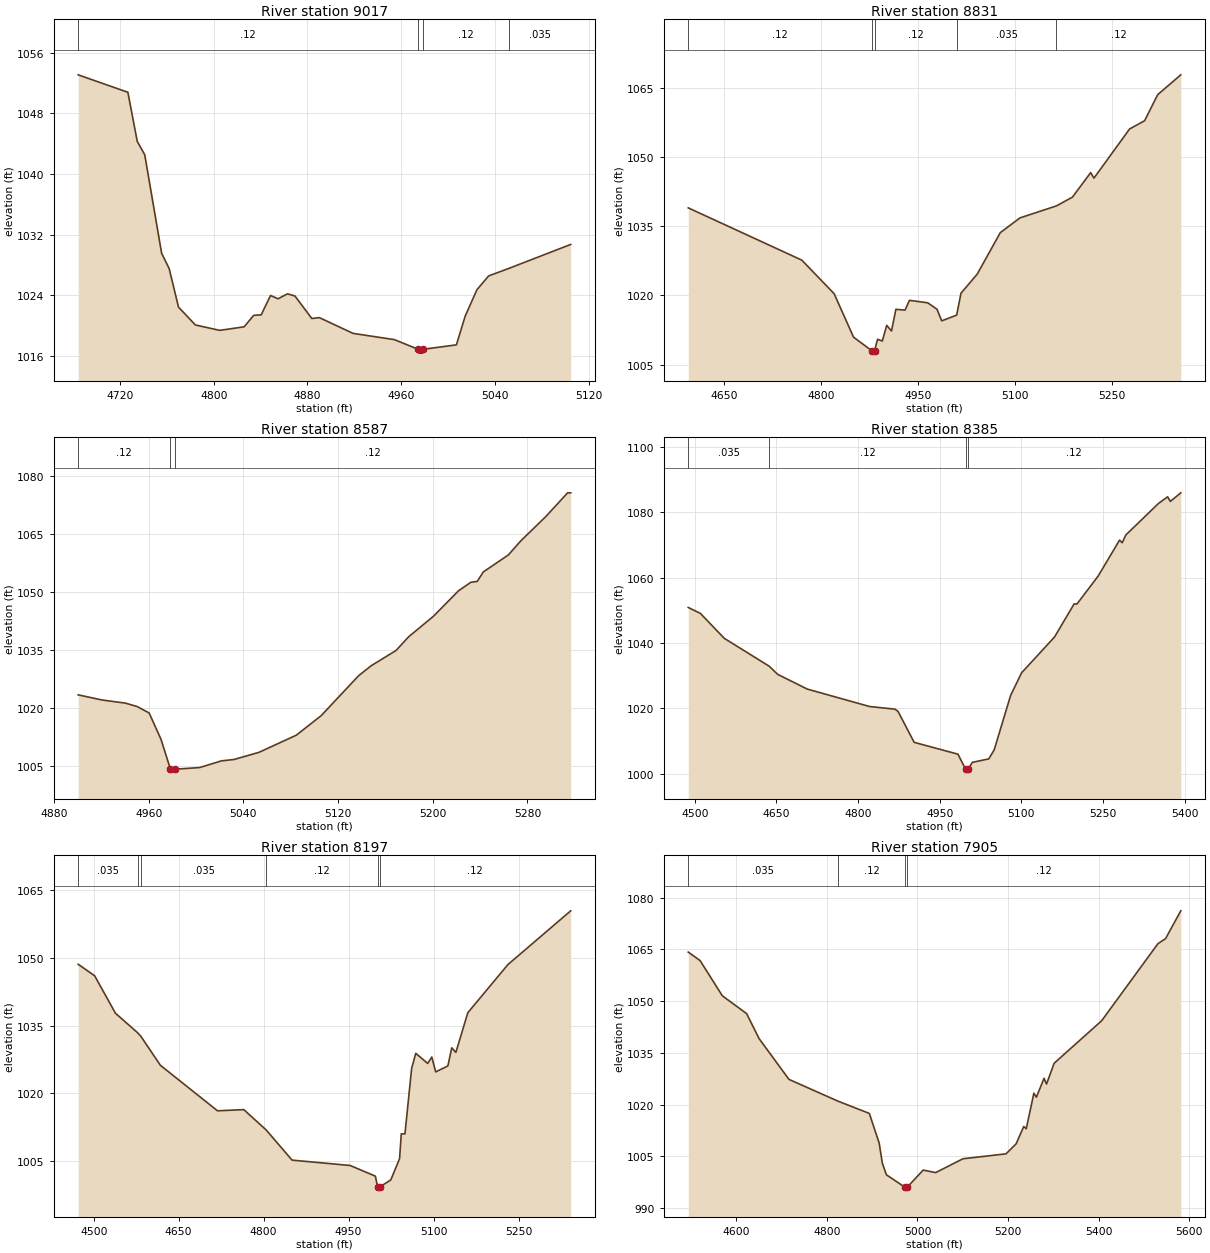
Type RM Length L Ch R = 1,9017,186,186,186
BEGIN DESCRIPTION:
Guadalupe Tributary 28 20.0
END DESCRIPTION:
XS GIS Cut Line= 3
      2235674.98     13884024.99      2235425.00     13883825.00
      2235325.03     13883825.00
#Sta/Elev= 30
  4684.4 1053.06  4726.8 1050.76  4734.8 1044.29  4741.2 1042.52  4755.6 1029.54
  4762.0 1027.54  4770.0 1022.45  4784.4 1020.10  4805.2 1019.39  4826.0 1019.86
  4834.1 1021.37  4840.5 1021.43  4848.5 1023.99  4854.9 1023.55  4862.9 1024.20
  4869.3 1023.92  4883.7 1020.95  4890.1 1021.07  4918.9 1018.99  4954.1 1018.17
  4974.5 1016.89  4974.8 1016.39  4978.3 1016.39  4978.5 1016.89  5007.0 1017.48
  5014.5 1021.26  5024.5 1024.74  5034.5 1026.56  5052.2 1027.58  5104.5 1030.71
#Mann=4,-1,0
  4684.4    0.12       0  4974.5    0.05       0  4978.5    0.12       0
  5052.2   0.035       0
Bank Sta=4974.5,4978.5
Exp/Cntr=0.3,0.1

Type RM Length L Ch R = 1,8831,244,244,244
BEGIN DESCRIPTION:
A19298
END DESCRIPTION:
XS GIS Cut Line= 4
      2235760.69     13883599.80      2235480.67     13883602.44
      2235380.29     13883694.89      2235039.80     13883752.96
#Sta/Elev= 30
  4594.1 1038.97  4769.8 1027.63  4819.8 1020.35  4849.8 1010.93  4878.2 1007.97
  4878.4 1007.47  4882.2 1007.97  4887.0 1010.48  4894.3 1010.09  4901.1 1013.50
  4908.5 1012.27  4915.3 1016.97  4929.5 1016.80  4936.3 1018.92  4964.6 1018.38
  4978.8 1017.00  4986.2 1014.47  5009.3 1015.71  5016.0 1020.46  5041.2 1024.62
  5076.8 1033.60  5107.3 1036.80  5163.7 1039.40  5188.4 1041.30  5216.6 1046.61
  5221.7 1045.42  5276.8 1056.08  5300.0 1057.86  5320.3 1063.52  5356.0 1067.82
#Mann=5,-1,0
  4594.1    0.12       0  4878.2    0.05       0  4882.2    0.12       0
  5009.3   0.035       0  5163.7    0.12       0
Bank Sta=4878.2,4882.2
Exp/Cntr=0.3,0.1

Type RM Length L Ch R = 1,8587,202,202,202
BEGIN DESCRIPTION:
Guadalupe Tributary 28 19.0
END DESCRIPTION:
XS GIS Cut Line= 3
      2235574.99     13883475.00      2235475.00     13883475.00
      2235175.02     13883375.01
#Sta/Elev= 30
  4900.4 1023.44  4920.4 1022.12  4940.4 1021.30  4950.4 1020.40  4960.4 1018.75
  4970.4 1011.96  4978.4 1004.25  4978.6 1003.75  4982.1 1003.75  4982.4 1004.25
  5003.0 1004.67  5021.5 1006.40  5032.0 1006.75  5053.1 1008.59  5084.7 1013.02
  5105.8 1018.08  5137.4 1028.38  5148.0 1030.95  5169.0 1034.88  5179.6 1038.41
  5200.7 1043.74  5221.8 1050.30  5232.3 1052.50  5237.6 1052.71  5242.8 1055.17
  5263.9 1059.54  5274.5 1063.20  5295.5 1069.43  5314.0 1075.58  5316.6 1075.58
#Mann=3,-1,0
  4900.4    0.12       0  4978.4    0.05       0  4982.4    0.12       0
Bank Sta=4978.4,4982.4
Exp/Cntr=0.3,0.1

Type RM Length L Ch R = 1,8385,188,188,188
BEGIN DESCRIPTION:
A19297
END DESCRIPTION:
XS GIS Cut Line= 3
      2235945.58     13883473.02      2235491.23     13883274.91
      2235084.46     13883227.36
#Sta/Elev= 30
  4487.9 1050.86  4510.3 1049.04  4554.0 1041.44  4636.7 1032.90  4652.2 1030.42
  4706.7 1025.91  4821.0 1020.59  4867.8 1019.77  4873.3 1019.13  4903.1 1009.63
  4983.6 1006.01  4997.9 1001.33  4998.2 1000.83  5001.9 1001.33  5010.0 1003.51
  5040.2 1004.57  5050.2 1007.34  5080.4 1024.00  5100.6 1030.90  5161.0 1041.82
  5197.2 1051.98  5202.2 1051.90  5241.5 1060.53  5280.5 1071.44  5285.5 1070.65
  5291.9 1072.99  5352.3 1082.69  5368.9 1084.69  5373.9 1083.29  5393.1 1085.91
#Mann=4,-1,0
  4487.9   0.035       0  4636.7    0.12       0  4997.9    0.05       0
  5001.9    0.12       0
Bank Sta=4997.9,5001.9
Exp/Cntr=0.3,0.1

Type RM Length L Ch R = 1,8197,292,292,292
BEGIN DESCRIPTION:
Guadalupe Tributary 28 18.0
END DESCRIPTION:
XS GIS Cut Line= 3
      2235975.01     13883375.01      2235485.95     13883076.80
      2235269.67     13882873.70
#Sta/Elev= 30
  4472.6 1048.61  4501.7 1046.05  4538.4 1037.74  4577.8 1033.37  4583.4 1032.59
  4617.8 1026.17  4718.6 1016.07  4765.0 1016.33  4804.5 1011.82  4850.2 1005.12
  4952.8 1003.93  4997.3 1001.56  5001.2  999.18  5001.4  998.68  5005.2  999.18
  5024.5 1000.72  5040.0 1005.44  5043.0 1010.95  5049.5 1010.95  5061.3 1025.48
  5068.6 1028.84  5089.6 1026.59  5096.9 1028.01  5103.8 1024.71  5125.3 1026.04
  5132.1 1030.05  5139.4 1029.04  5160.5 1037.85  5231.3 1048.54  5342.1 1060.47
#Mann=6,-1,0
  4472.6   0.035       0  4577.8    0.12       0  4583.4   0.035       0
  4804.5    0.12       0  5001.2    0.05       0  5005.2    0.12       0
Bank Sta=5001.2,5005.2
Exp/Cntr=0.3,0.1

Type RM Length L Ch R = 1,7905,321,321,321
BEGIN DESCRIPTION:
A19296
END DESCRIPTION:
XS GIS Cut Line= 3
      2236199.13     13883224.72      2235697.26     13882944.73
      2235238.85     13882715.52
#Sta/Elev= 30
  4494.1 1064.21  4520.2 1061.76  4569.3 1051.54  4623.0 1046.36  4650.4 1039.13
  4716.4 1027.29  4825.1 1020.95  4893.8 1017.42  4915.5 1008.84  4922.5 1003.01
  4931.5  999.62  4973.0  995.96  4973.2  995.46  4977.0  995.96  5012.7 1000.99
  5040.1 1000.25  5100.5 1004.27  5195.5 1005.69  5217.9 1008.61  5234.7 1013.64
  5240.2 1012.97  5257.0 1023.29  5262.6 1022.13  5279.4 1027.60  5285.0 1025.94
  5301.7 1031.96  5406.7 1044.31  5530.9 1066.66  5547.7 1068.11  5581.3 1076.18
#Mann=4,-1,0
  4494.1   0.035       0  4825.1    0.12       0  4973.0    0.05       0
  4977.0    0.12       0
Bank Sta=4973,4977
Exp/Cntr=0.3,0.1

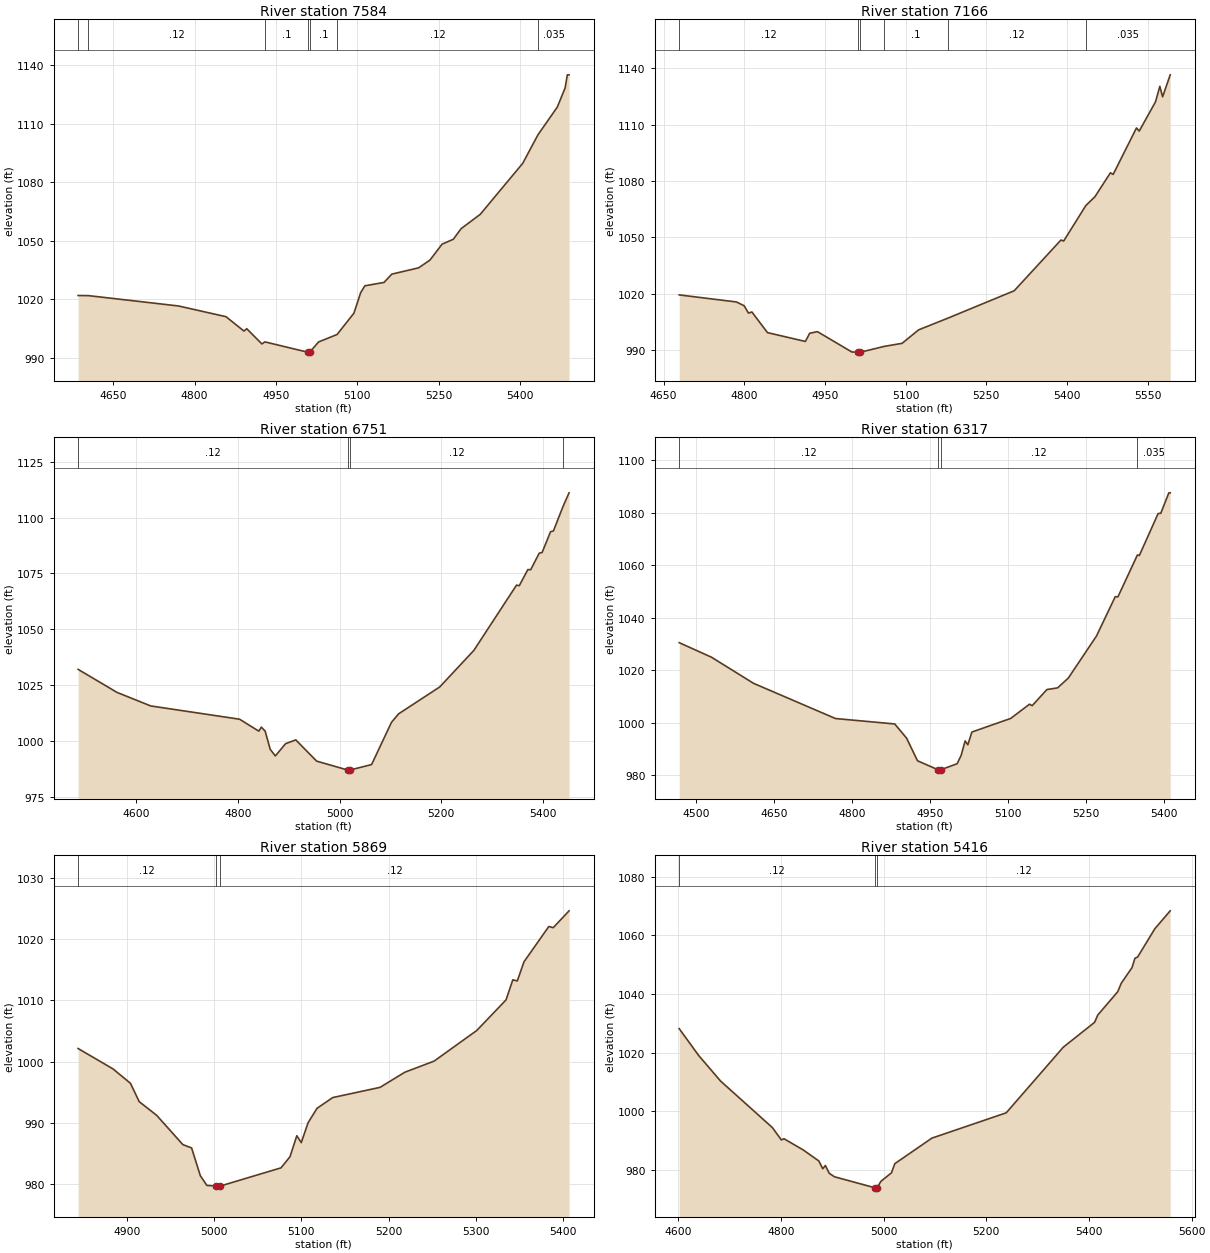
Type RM Length L Ch R = 1,7584,418,418,418
BEGIN DESCRIPTION:
Guadalupe Tributary 28 17.0
END DESCRIPTION:
XS GIS Cut Line= 3
      2236072.37     13882817.95      2235578.40     13882670.02
      2235275.02     13882425.02
#Sta/Elev= 30
  4585.2 1021.96  4604.2 1021.90  4770.4 1016.60  4858.0 1011.11  4891.1 1003.75
  4896.3 1004.95  4924.2  997.16  4929.9  998.19  5008.4  992.94  5008.6  992.44
  5012.5  992.94  5028.7  998.15  5062.9 1001.99  5094.0 1012.92  5106.3 1023.35
  5114.2 1026.94  5149.4 1028.65  5163.8 1032.90  5213.4 1036.15  5234.2 1040.09
  5256.5 1048.25  5277.3 1050.78  5291.7 1056.21  5326.9 1063.53  5405.3 1089.67
  5433.4 1104.28  5469.2 1118.54  5483.6 1128.38  5487.6 1135.02  5490.8 1135.02
#Mann=7,-1,0
  4585.2   0.035       0  4604.2    0.12       0  4929.9     0.1       0
  5008.4    0.05       0  5012.5     0.1       0  5062.9    0.12       0
  5433.4   0.035       0
Bank Sta=5008.4,5012.5
Exp/Cntr=0.3,0.1

Type RM Length L Ch R = 1,7166,415,415,415
BEGIN DESCRIPTION:
Guadalupe Tributary 28 16.0
END DESCRIPTION:
XS GIS Cut Line= 3
      2236032.73     13882717.58      2235810.84     13882437.58
      2235268.36     13882316.44
#Sta/Elev= 30
  4679.0 1019.35  4785.4 1015.60  4799.8 1013.57  4807.8 1009.68  4814.2 1010.26
  4843.1  999.29  4913.6  994.58  4921.6  998.92  4936.0  999.81  5000.1  988.96
  5012.0  988.87  5012.2  988.37  5016.1  988.87  5060.0  991.94  5093.5  993.59
  5124.2 1000.75  5178.7 1006.99  5302.0 1021.56  5388.9 1048.56  5394.0 1048.03
  5435.2 1066.91  5452.1 1071.59  5480.9 1084.34  5486.0 1083.48  5529.4 1108.21
  5534.5 1106.53  5564.8 1122.12  5572.8 1130.34  5578.0 1124.78  5592.1 1136.47
#Mann=6,-1,0
  4679.0    0.12       0  5012.0    0.05       0  5016.1    0.12       0
  5060.0     0.1       0  5178.7    0.12       0  5435.2   0.035       0
Bank Sta=5012,5016.1
Exp/Cntr=0.3,0.1

Type RM Length L Ch R = 1,6751,434,434,434
BEGIN DESCRIPTION:
Guadalupe Tributary 28 15.0
END DESCRIPTION:
XS GIS Cut Line= 3
      2236241.39     13882173.44      2235725.00     13882125.00
      2235324.97     13881924.99
#Sta/Elev= 30
  4485.6 1032.01  4562.3 1021.68  4628.5 1015.63  4803.4 1009.68  4841.1 1004.35
  4846.1 1006.13  4853.6 1004.36  4863.6  996.18  4873.7  993.25  4893.8  998.73
  4913.9 1000.43  4954.9  990.92  5015.9  986.94  5016.2  986.44  5020.6  986.94
  5063.0  989.38  5102.1 1008.27  5116.1 1012.08  5197.1 1024.14  5264.2 1040.50
  5348.1 1069.71  5353.6 1069.49  5370.4 1076.68  5376.0 1076.62  5392.8 1084.03
  5398.4 1084.31  5415.1 1093.65  5420.7 1093.98  5439.7 1104.98  5451.5 1111.05
#Mann=4,-1,0
  4485.6    0.12       0  5015.9    0.05       0  5020.6    0.12       0
  5439.7   0.035       0
Bank Sta=5015.9,5020.6
Exp/Cntr=0.3,0.1

Type RM Length L Ch R = 1,6317,448,448,448
BEGIN DESCRIPTION:
Guadalupe Tributary 28 14.0
END DESCRIPTION:
XS GIS Cut Line= 3
      2236281.06     13881938.37      2235775.00     13881775.00
      2235374.99     13881875.00
#Sta/Elev= 30
  4467.8 1030.53  4529.8 1025.00  4610.8 1015.05  4768.4 1001.66  4882.2  999.60
  4905.0  994.20  4926.0  985.59  4965.7  982.15  4966.1  981.65  4970.4  982.15
  5002.2  984.47  5009.9  987.66  5017.6  993.14  5022.8  991.68  5030.5  996.52
  5105.2 1001.70  5141.3 1007.11  5146.5 1006.56  5174.8 1012.69  5195.4 1013.33
  5216.0 1017.07  5270.2 1033.08  5306.2 1048.03  5311.4 1047.97  5348.8 1063.88
  5352.6 1063.73  5388.7 1079.67  5393.8 1079.77  5409.3 1087.55  5411.9 1087.55
#Mann=4,-1,0
  4467.8    0.12       0  4965.7    0.05       0  4970.4    0.12       0
  5348.8   0.035       0
Bank Sta=4965.7,4970.4
Exp/Cntr=0.3,0.1

Type RM Length L Ch R = 1,5869,453,453,453
BEGIN DESCRIPTION:
Guadalupe Tributary 28 13.0
END DESCRIPTION:
XS GIS Cut Line= 3
      2236074.97     13881425.00      2235925.00     13881425.00
      2235524.98     13881525.00
#Sta/Elev= 30
  4844.4 1002.15  4884.4  998.82  4904.4  996.47  4914.4  993.48  4934.4  991.25
  4964.4  986.47  4974.4  985.93  4984.4  981.40  4991.9  979.82  5002.2  979.71
  5002.6  979.21  5007.1  979.71  5076.8  982.68  5087.1  984.50  5094.9  987.92
  5100.0  986.80  5107.8  990.04  5118.1  992.40  5136.1  994.15  5190.2  995.81
  5218.6  998.28  5252.1 1000.09  5301.0 1005.09  5334.5 1010.08  5342.3 1013.36
  5347.4 1013.17  5355.1 1016.30  5383.5 1022.05  5388.6 1021.87  5406.7 1024.61
#Mann=3,-1,0
  4844.4    0.12       0  5002.2    0.05       0  5007.1    0.12       0
Bank Sta=5002.2,5007.1
Exp/Cntr=0.3,0.1

Type RM Length L Ch R = 1,5416,460,460,460
BEGIN DESCRIPTION:
Guadalupe Tributary 28 12.0
END DESCRIPTION:
XS GIS Cut Line= 3
      2236324.96     13880925.01      2235925.00     13880975.00
      2235393.52     13880821.04
#Sta/Elev= 30
  4601.8 1028.14  4639.5 1019.04  4682.4 1010.27  4783.2  994.43  4800.8  990.19
  4805.8  990.62  4843.6  986.76  4873.9  983.02  4881.4  980.37  4886.5  981.50
  4894.0  978.83  4904.1  977.65  4982.2  973.93  4982.6  973.43  4987.2  973.93
  4994.8  976.11  5015.3  979.00  5021.7  982.10  5094.0  990.82  5238.8  999.45
  5350.0 1021.83  5410.9 1030.30  5417.1 1032.79  5455.9 1040.72  5463.0 1043.68
  5483.8 1048.95  5489.5 1052.15  5494.7 1052.56  5528.3 1062.22  5558.2 1068.32
#Mann=3,-1,0
  4601.8    0.12       0  4982.2    0.05       0  4987.2    0.12       0
Bank Sta=4982.2,4987.2
Exp/Cntr=0.3,0.1

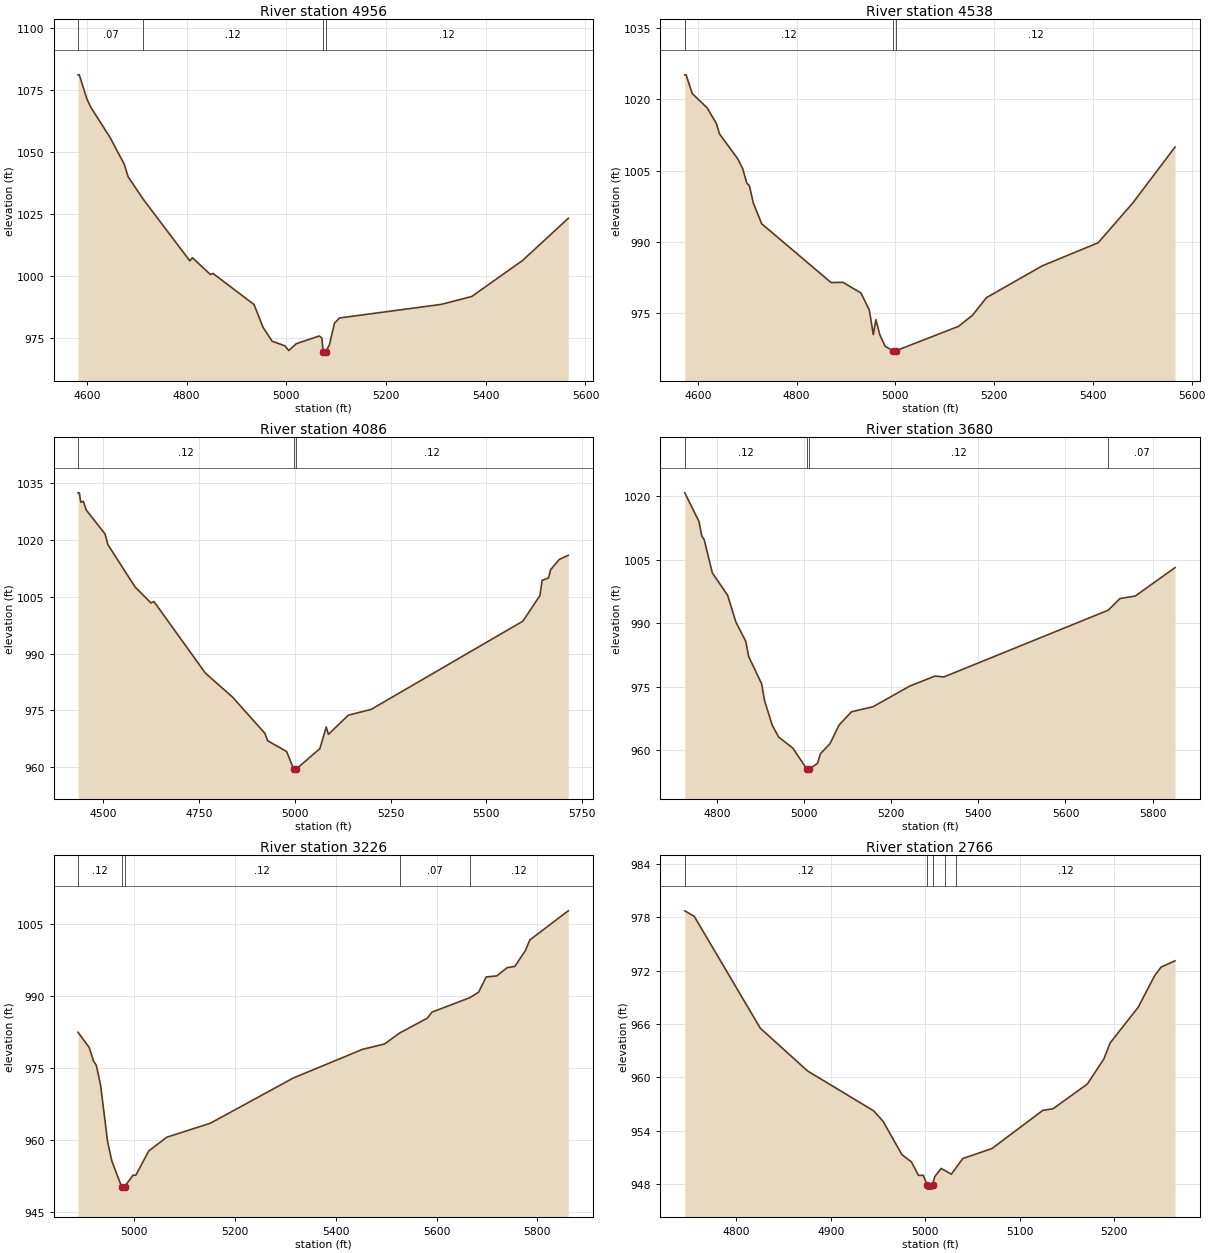
Type RM Length L Ch R = 1,4956,418,418,418
BEGIN DESCRIPTION:
Guadalupe Tributary 28 11.0
END DESCRIPTION:
XS GIS Cut Line= 3
      2236524.97     13880674.99      2236125.00     13880575.00
      2235565.24     13880686.31
#Sta/Elev= 30
  4582.5 1081.24  4585.0 1081.24  4600.5 1071.40  4608.2 1068.13  4646.9 1055.92
  4675.2 1045.18  4683.0 1040.12  4713.2 1031.09  4806.7 1006.24  4811.8 1007.52
  4847.9 1000.75  4853.0 1001.20  4935.5  988.64  4953.5  979.44  4971.6  973.89
  4997.3  972.00  5005.0  970.11  5020.3  972.88  5066.2  975.97  5071.5  975.13
  5074.0  969.56  5074.4  969.06  5079.1  969.56  5086.5  972.40  5096.7  981.12
  5106.9  983.24  5310.9  988.71  5372.0  991.89  5474.0 1006.43  5565.5 1023.40
#Mann=4,-1,0
  4582.5    0.07       0  4713.2    0.12       0  5074.0    0.05       0
  5079.1    0.12       0
Bank Sta=5074,5079.1
Exp/Cntr=0.3,0.1

Type RM Length L Ch R = 1,4538,452,452,452
BEGIN DESCRIPTION:
Guadalupe Tributary 28 10.0
END DESCRIPTION:
XS GIS Cut Line= 3
      2236424.98     13880374.99      2236025.00     13880225.00
      2235624.97     13880625.03
#Sta/Elev= 30
  4573.4 1025.16  4576.0 1025.16  4588.5 1021.23  4618.8 1018.19  4637.5 1014.88
  4643.7 1012.71  4680.2 1007.55  4690.9 1005.35  4698.9 1002.39  4704.2 1001.82
  4712.2  998.20  4729.1  993.82  4869.7  981.44  4893.8  981.49  4930.3  979.24
  4947.2  975.62  4955.2  970.50  4960.5  973.65  4968.5  970.43  4979.2  968.02
  4995.1  967.09  4995.5  966.59  5000.8  967.09  5127.9  972.23  5156.1  974.56
  5184.4  978.27  5297.6  984.97  5410.7  989.82  5481.4  998.27  5566.3 1009.96
#Mann=3,-1,0
  4573.4    0.12       0  4995.1    0.05       0  5000.8    0.12       0
Bank Sta=4995.1,5000.8
Exp/Cntr=0.3,0.1

Type RM Length L Ch R = 1,4086,406,406,406
BEGIN DESCRIPTION:
Guadalupe Tributary 28 9.0
END DESCRIPTION:
XS GIS Cut Line= 3
      2236224.98     13879525.02      2235792.35     13879920.32
      2235171.63     13880232.00
#Sta/Elev= 30
  4433.6 1032.47  4437.0 1032.47  4440.7 1029.98  4447.4 1030.23  4454.8 1027.96
  4504.2 1021.59  4511.6 1018.78  4582.5 1007.61  4624.4 1003.35  4631.8 1003.77
  4766.3  984.84  4837.2  978.52  4921.7  968.94  4929.1  966.98  4978.4  964.15
  4997.1  959.46  4997.6  958.96  5002.9  959.46  5065.3  964.89  5082.0  970.63
  5087.6  968.67  5139.7  973.74  5199.2  975.26  5595.6  998.57  5640.3 1005.34
  5645.9 1009.35  5662.6 1009.99  5668.2 1012.16  5690.6 1014.87  5714.2 1015.97
#Mann=3,-1,0
  4433.6    0.12       0  4997.1    0.05       0  5002.9    0.12       0
Bank Sta=4997.1,5002.9
Exp/Cntr=0.3,0.1

Type RM Length L Ch R = 1,3680,454,454,454
BEGIN DESCRIPTION:
Guadalupe Tributary 28 8.0
END DESCRIPTION:
XS GIS Cut Line= 3
      2235975.04     13879424.98      2235725.00     13879525.00
      2235159.19     13880167.73
#Sta/Elev= 30
  4725.9 1020.75  4758.3 1014.01  4765.0 1010.54  4770.4 1009.70  4789.2 1001.83
  4824.2  996.58  4843.1  990.27  4866.0  985.65  4872.7  982.07  4902.3  975.66
  4909.0  971.70  4926.5  965.94  4941.4  963.08  4973.7  960.50  5006.1  955.54
  5006.5  955.04  5011.9  955.54  5030.8  956.88  5037.4  959.17  5059.2  961.50
  5080.1  965.91  5108.6  969.05  5157.9  970.24  5243.3  975.16  5300.2  977.48
  5321.1  977.29  5698.0  993.03  5725.2  995.79  5760.4  996.39  5851.5 1003.09
#Mann=4,-1,0
  4725.9    0.12       0  5006.1    0.05       0  5011.9    0.12       0
  5698.0    0.07       0
Bank Sta=5006.1,5011.9
Exp/Cntr=0.3,0.1

Type RM Length L Ch R = 1,3226,460,460,460
BEGIN DESCRIPTION:
Guadalupe Tributary 28 7.0
END DESCRIPTION:
XS GIS Cut Line= 3
      2235674.98     13879075.01      2235575.00     13879125.00
      2234863.52     13879610.63
#Sta/Elev= 30
  4888.3  982.44  4910.6  979.24  4919.0  976.43  4924.6  975.54  4933.0  971.42
  4947.0  959.58  4955.4  955.55  4974.8  950.18  4975.3  949.68  4980.7  950.18
  4997.3  952.59  5003.1  952.59  5028.5  957.64  5064.4  960.52  5151.1  963.45
  5315.7  972.89  5453.3  978.88  5496.5  979.99  5527.0  982.29  5581.9  985.40
  5590.8  986.64  5666.1  989.66  5683.6  990.82  5698.5  993.99  5719.5  994.21
  5740.4  995.94  5755.4  996.19  5776.3  999.48  5785.2 1001.72  5861.5 1007.80
#Mann=5,-1,0
  4888.3    0.12       0  4974.8    0.05       0  4980.7    0.12       0
  5527.0    0.07       0  5666.1    0.12       0
Bank Sta=4974.8,4980.7
Exp/Cntr=0.3,0.1

Type RM Length L Ch R = 1,2766,440,440,440
BEGIN DESCRIPTION:
Guadalupe Tributary 28 6.0
END DESCRIPTION:
XS GIS Cut Line= 3
      2235574.96     13878775.00      2235325.00     13878775.00
      2235075.02     13878874.99
#Sta/Elev= 30
  4745.5  978.75  4755.5  978.13  4825.5  965.53  4875.5  960.72  4945.5  956.23
  4955.5  955.05  4975.5  951.29  4985.5  950.48  4993.0  948.96  4998.2  948.96
  5001.9  947.91  5002.4  947.41  5007.4  947.41  5007.9  947.91  5010.3  948.82
  5017.0  949.74  5021.5  949.47  5027.8  949.09  5033.0  949.85  5039.9  950.85
  5070.9  951.99  5124.7  956.28  5135.5  956.46  5171.8  959.24  5189.3  962.06
  5196.1  963.89  5225.7  967.89  5243.2  971.46  5249.9  972.41  5264.7  973.12
#Mann=5,-1,0
  4745.5    0.12       0  5001.9    0.05       0  5007.9    0.12       0
  5021.5    0.07       0  5033.0    0.12       0
Bank Sta=5001.9,5007.9
Exp/Cntr=0.3,0.1