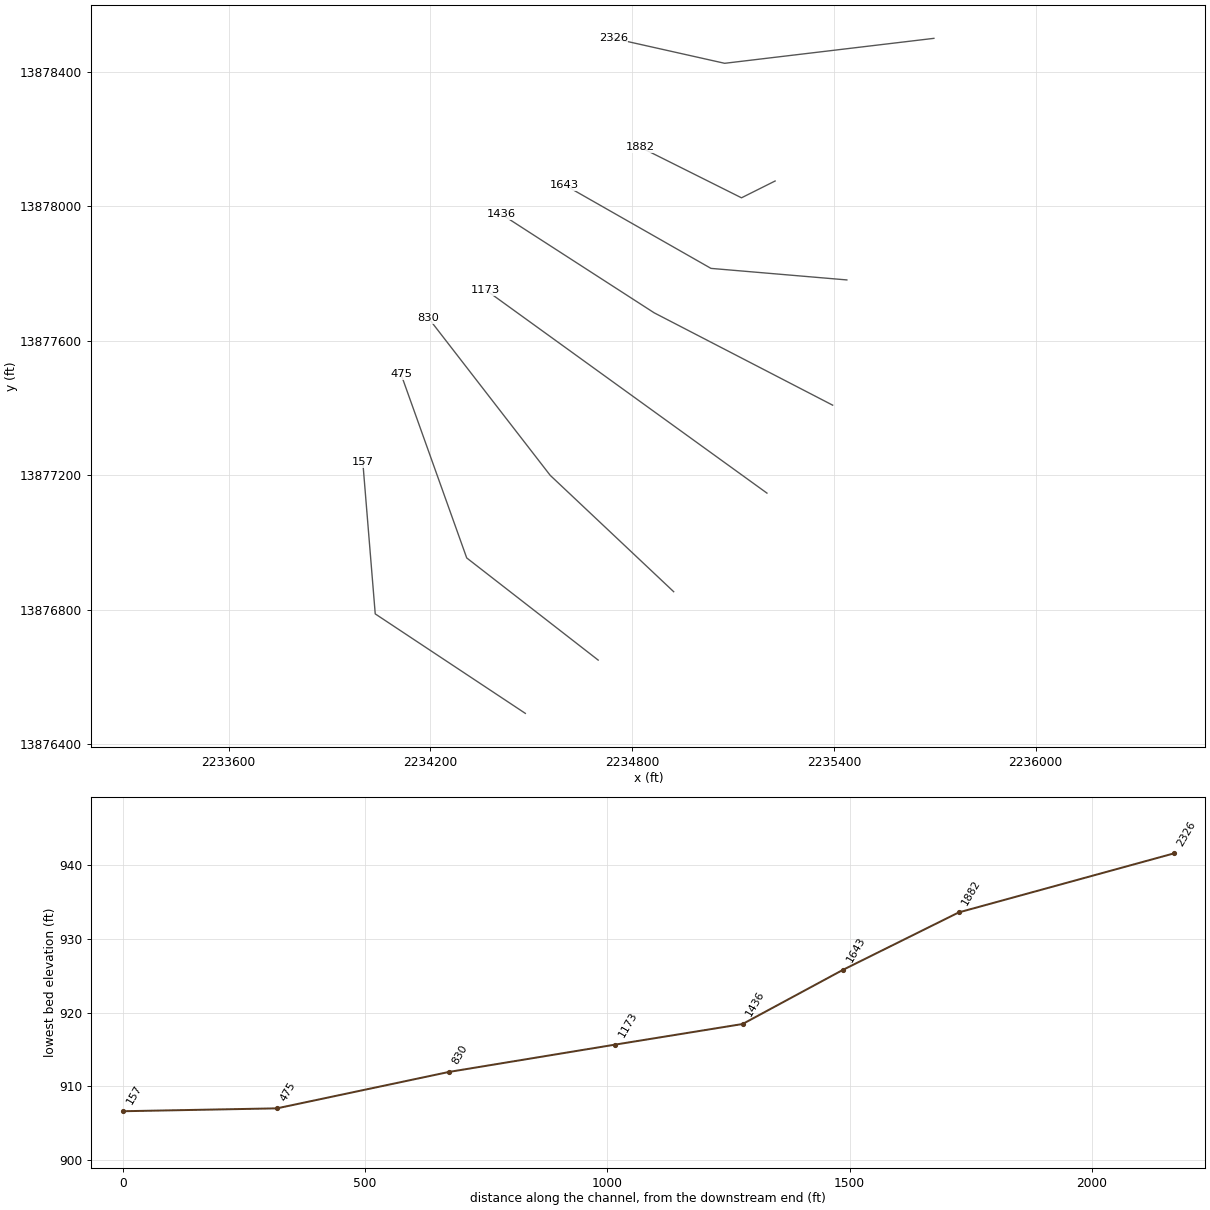
HEC-RAS study Guadalupe Tributary 28.prj: Guadalupe Tributary 28 Base Level Engineering

--- Guadalupe Tributary 28.g01 (geometry) --- (continued)

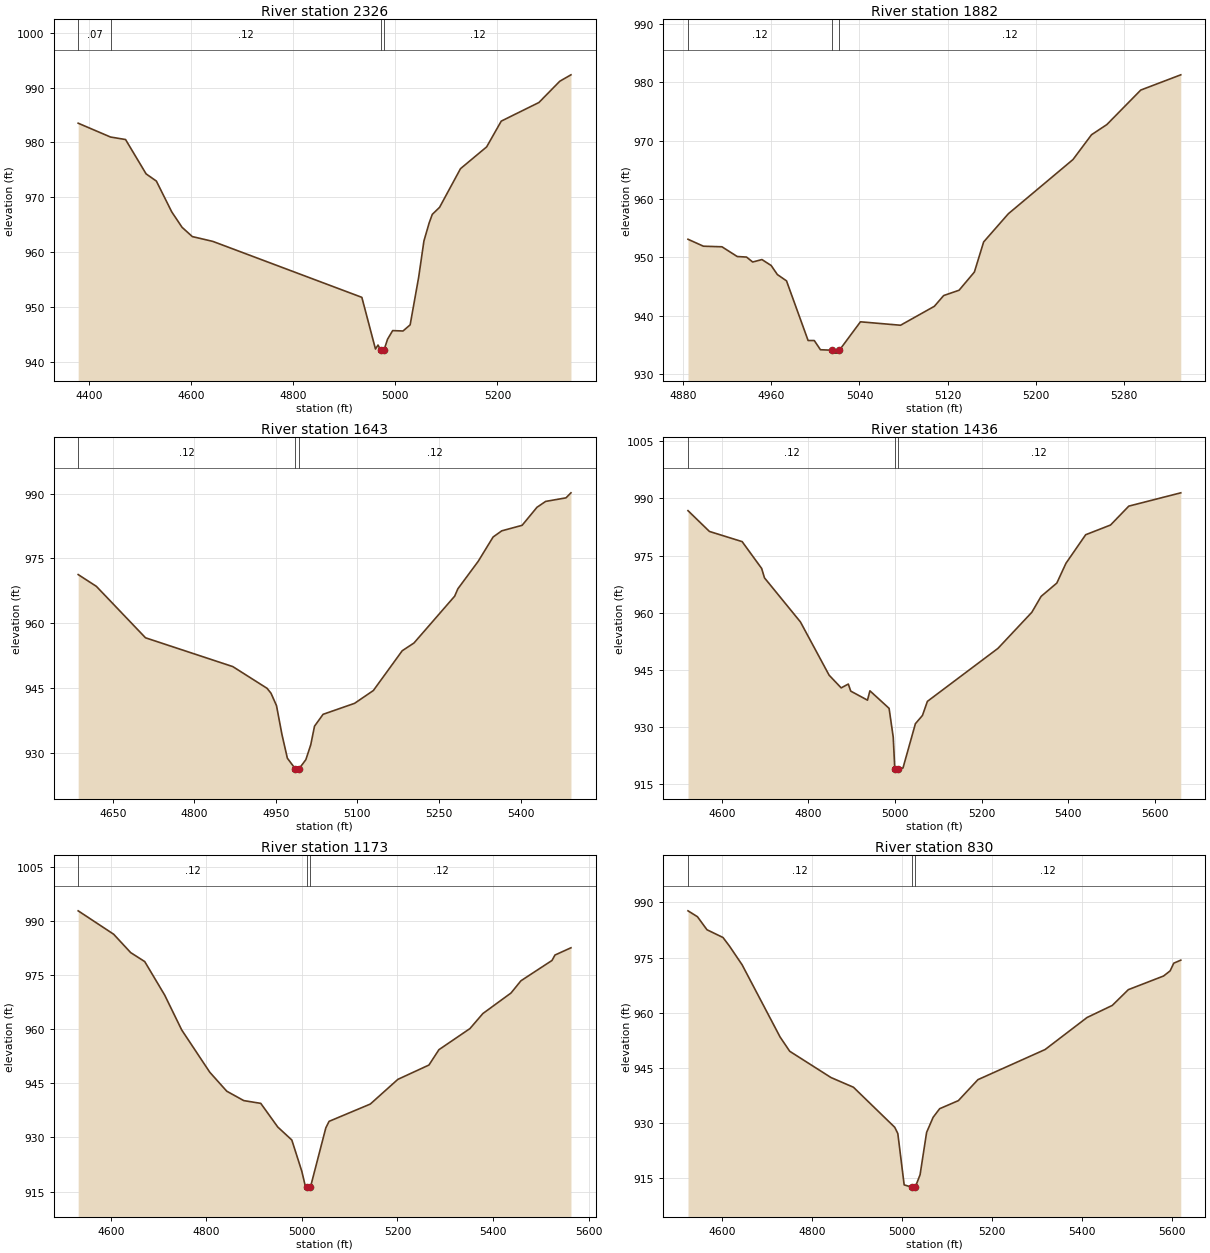
Type RM Length L Ch R = 1,2326,444,444,444
BEGIN DESCRIPTION:
Guadalupe Tributary 28 5.0
END DESCRIPTION:
XS GIS Cut Line= 3
      2235697.24     13878499.23      2235075.00     13878425.00
      2234743.67     13878499.25
#Sta/Elev= 30
  4378.0  983.51  4441.4  980.99  4470.9  980.53  4511.2  974.26  4531.3  972.95
  4561.5  967.32  4581.7  964.51  4601.8  962.82  4642.1  961.94  4934.2  951.73
  4960.9  942.30  4965.9  943.02  4971.4  942.05  4971.9  941.55  4977.5  942.05
  4984.5  944.07  4994.6  945.66  5014.9  945.59  5028.9  946.71  5045.6  955.40
  5055.9  962.01  5066.1  965.29  5072.3  966.87  5086.6  968.16  5127.6  975.21
  5178.9  979.19  5207.5  983.89  5281.4  987.29  5322.3  991.17  5344.2  992.34
#Mann=4,-1,0
  4378.0    0.07       0  4441.4    0.12       0  4971.4    0.05       0
  4977.5    0.12       0
Bank Sta=4971.4,4977.5
Exp/Cntr=0.3,0.1

Type RM Length L Ch R = 1,1882,239,239,239
BEGIN DESCRIPTION:
Guadalupe Tributary 28 4.0
END DESCRIPTION:
XS GIS Cut Line= 3
      2235225.01     13878075.00      2235125.00     13878025.00
      2234825.02     13878174.99
#Sta/Elev= 30
  4884.4  953.08  4898.4  951.89  4915.2  951.79  4929.1  950.12  4937.5  950.03
  4943.1  949.18  4951.5  949.60  4959.9  948.58  4965.5  947.03  4973.8  945.95
  4993.4  935.72  4999.0  935.72  5004.6  934.14  5015.4  934.06  5015.9  933.56
  5021.3  933.56  5021.8  934.06  5040.9  938.93  5077.3  938.34  5108.0  941.59
  5116.4  943.43  5130.4  944.34  5144.3  947.46  5152.7  952.62  5175.1  957.45
  5233.8  966.75  5250.6  971.00  5264.5  972.74  5295.3  978.66  5331.6  981.27
#Mann=3,-1,0
  4884.4    0.12       0  5015.4    0.05       0  5021.8    0.12       0
Bank Sta=5015.4,5021.8
Exp/Cntr=0.3,0.1

Type RM Length L Ch R = 1,1643,207,207,207
BEGIN DESCRIPTION:
A19295
END DESCRIPTION:
XS GIS Cut Line= 3
      2235438.36     13877780.78      2235034.27     13877815.11
      2234599.26     13878062.94
#Sta/Elev= 30
  4586.5  971.27  4620.0  968.54  4710.3  956.64  4870.9  949.97  4933.9  944.94
  4941.1  943.81  4951.2  940.94  4961.2  934.28  4971.2  928.77  4986.0  926.28
  4986.5  925.78  4992.4  926.28  5005.2  928.44  5014.2  931.88  5021.1  936.18
  5036.9  938.93  5094.8  941.47  5129.3  944.43  5182.4  953.64  5204.0  955.43
  5278.9  966.28  5284.7  967.97  5322.2  974.35  5349.5  979.96  5365.4  981.39
  5402.9  982.67  5430.2  986.84  5446.1  988.20  5483.6  989.03  5492.7  990.19
#Mann=3,-1,0
  4586.5    0.12       0  4986.0    0.05       0  4992.4    0.12       0
Bank Sta=4986,4992.4
Exp/Cntr=0.3,0.1

Type RM Length L Ch R = 1,1436,263,263,263
BEGIN DESCRIPTION:
A19294
END DESCRIPTION:
XS GIS Cut Line= 3
      2235396.13     13877408.34      2234865.22     13877683.04
      2234410.89     13877976.24
#Sta/Elev= 30
  4521.7  986.78  4571.2  981.33  4646.8  978.66  4691.9  971.62  4698.4  969.16
  4781.4  957.60  4847.8  943.61  4875.6  940.29  4892.1  941.29  4897.7  939.44
  4936.4  937.07  4942.0  939.52  4986.3  934.92  4995.9  927.34  4999.5  918.95
  5000.0  918.45  5006.0  918.95  5018.4  919.27  5047.1  930.89  5063.4  933.06
  5074.8  936.75  5237.9  950.66  5316.1  960.12  5337.5  964.29  5373.8  967.78
  5395.0  972.99  5440.5  980.47  5497.9  983.01  5540.1  987.97  5660.2  991.46
#Mann=3,-1,0
  4521.7    0.12       0  4999.5    0.05       0  5006.0    0.12       0
Bank Sta=4999.5,5006
Exp/Cntr=0.3,0.1

Type RM Length L Ch R = 1,1173,343,343,343
BEGIN DESCRIPTION:
A19293
END DESCRIPTION:
XS GIS Cut Line= 2
      2235200.70     13877146.82      2234364.55     13877750.85
#Sta/Elev= 30
  4531.7  992.93  4606.0  986.43  4641.6  981.33  4671.0  978.84  4712.8  969.53
  4748.4  959.86  4807.2  948.11  4842.7  942.85  4878.3  940.24  4913.9  939.47
  4949.5  932.90  4978.9  929.30  4999.8  920.62  5007.5  916.30  5011.2  916.16
  5011.7  915.66  5017.8  916.16  5050.1  932.68  5056.9  934.48  5143.2  939.28
  5200.9  946.14  5265.9  950.11  5286.8  954.37  5351.8  960.24  5378.8  964.41
  5437.7  970.11  5458.5  973.51  5523.5  979.15  5529.7  980.65  5563.2  982.67
#Mann=3,-1,0
  4531.7    0.12       0  5011.2    0.05       0  5017.8    0.12       0
Bank Sta=5011.2,5017.8
Exp/Cntr=0.3,0.1

Type RM Length L Ch R = 1,830,355,355,355
BEGIN DESCRIPTION:
A19292
END DESCRIPTION:
XS GIS Cut Line= 3
      2234923.36     13876853.61      2234556.17     13877199.66
      2234194.28     13877667.21
#Sta/Elev= 30
  4523.4  987.72  4544.5  986.11  4565.6  982.57  4601.2  980.46  4615.3  978.18
  4643.7  973.04  4728.2  953.37  4749.6  949.49  4841.5  942.33  4891.3  939.70
  4983.1  928.80  4990.0  927.10  5004.1  913.12  5022.0  912.46  5022.5  911.96
  5028.7  912.46  5039.5  915.89  5054.0  927.40  5068.5  931.51  5083.0  933.85
  5124.6  936.05  5168.1  941.76  5317.5  949.96  5410.8  958.68  5466.9  961.97
  5502.6  966.26  5581.0  969.98  5595.5  971.37  5603.6  973.47  5619.2  974.29
#Mann=3,-1,0
  4523.4    0.12       0  5022.0    0.05       0  5028.7    0.12       0
Bank Sta=5022,5028.7
Exp/Cntr=0.3,0.1

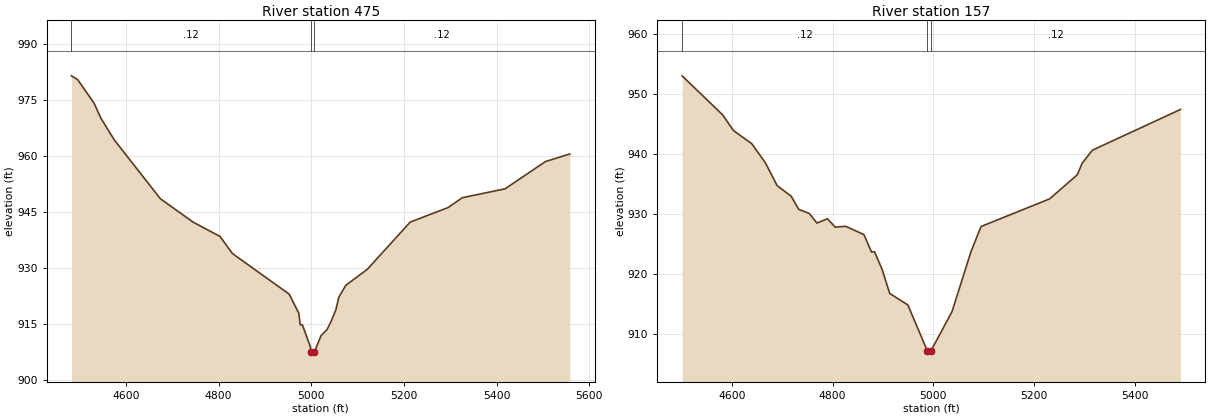
Type RM Length L Ch R = 1,475,318,318,318
BEGIN DESCRIPTION:
A19291
END DESCRIPTION:
XS GIS Cut Line= 3
      2234698.81     13876650.25      2234307.88     13876954.01
      2234112.56     13877500.37
#Sta/Elev= 30
  4482.6  981.42  4496.1  980.39  4531.4  974.10  4545.9  970.15  4574.9  964.31
  4674.4  948.57  4745.0  942.32  4802.9  938.51  4830.1  933.90  4952.3  923.07
  4973.1  917.96  4976.3  914.85  4980.9  914.85  4997.9  909.04  4999.8  907.53
  5000.3  907.03  5006.5  907.53  5021.2  912.00  5034.0  913.59  5042.4  915.68
  5053.1  918.88  5059.4  922.24  5074.3  925.39  5121.0  929.71  5213.4  942.32
  5295.1  946.20  5325.9  948.84  5418.2  951.22  5505.3  958.51  5557.9  960.53
#Mann=3,-1,0
  4482.6    0.12       0  4999.8    0.05       0  5006.5    0.12       0
Bank Sta=4999.8,5006.5
Exp/Cntr=0.3,0.1

Type RM Length L Ch R = 1,157,0,0,0
BEGIN DESCRIPTION:
A19290
END DESCRIPTION:
XS GIS Cut Line= 3
      2234482.21     13876491.77      2234035.82     13876787.60
      2233998.84     13877239.27
#Sta/Elev= 30
  4501.5  953.08  4582.1  946.55  4603.5  943.94  4639.6  941.76  4666.7  938.57
  4690.1  934.75  4717.8  933.00  4732.9  930.79  4753.9  930.11  4769.0  928.51
  4790.0  929.23  4805.1  927.83  4826.1  927.97  4862.2  926.59  4877.2  923.69
  4883.2  923.72  4898.3  920.78  4913.3  916.77  4949.4  914.84  4988.2  907.14
  4988.7  906.64  4994.9  907.14  5037.0  913.74  5074.5  923.72  5094.6  927.94
  5230.5  932.54  5285.3  936.55  5295.3  938.51  5315.4  940.67  5490.2  947.47
#Mann=3,-1,0
  4501.5    0.12       0  4988.2    0.05       0  4994.9    0.12       0
Bank Sta=4988.2,4994.9
Exp/Cntr=0.3,0.1

Chan Stop Cuts=-1