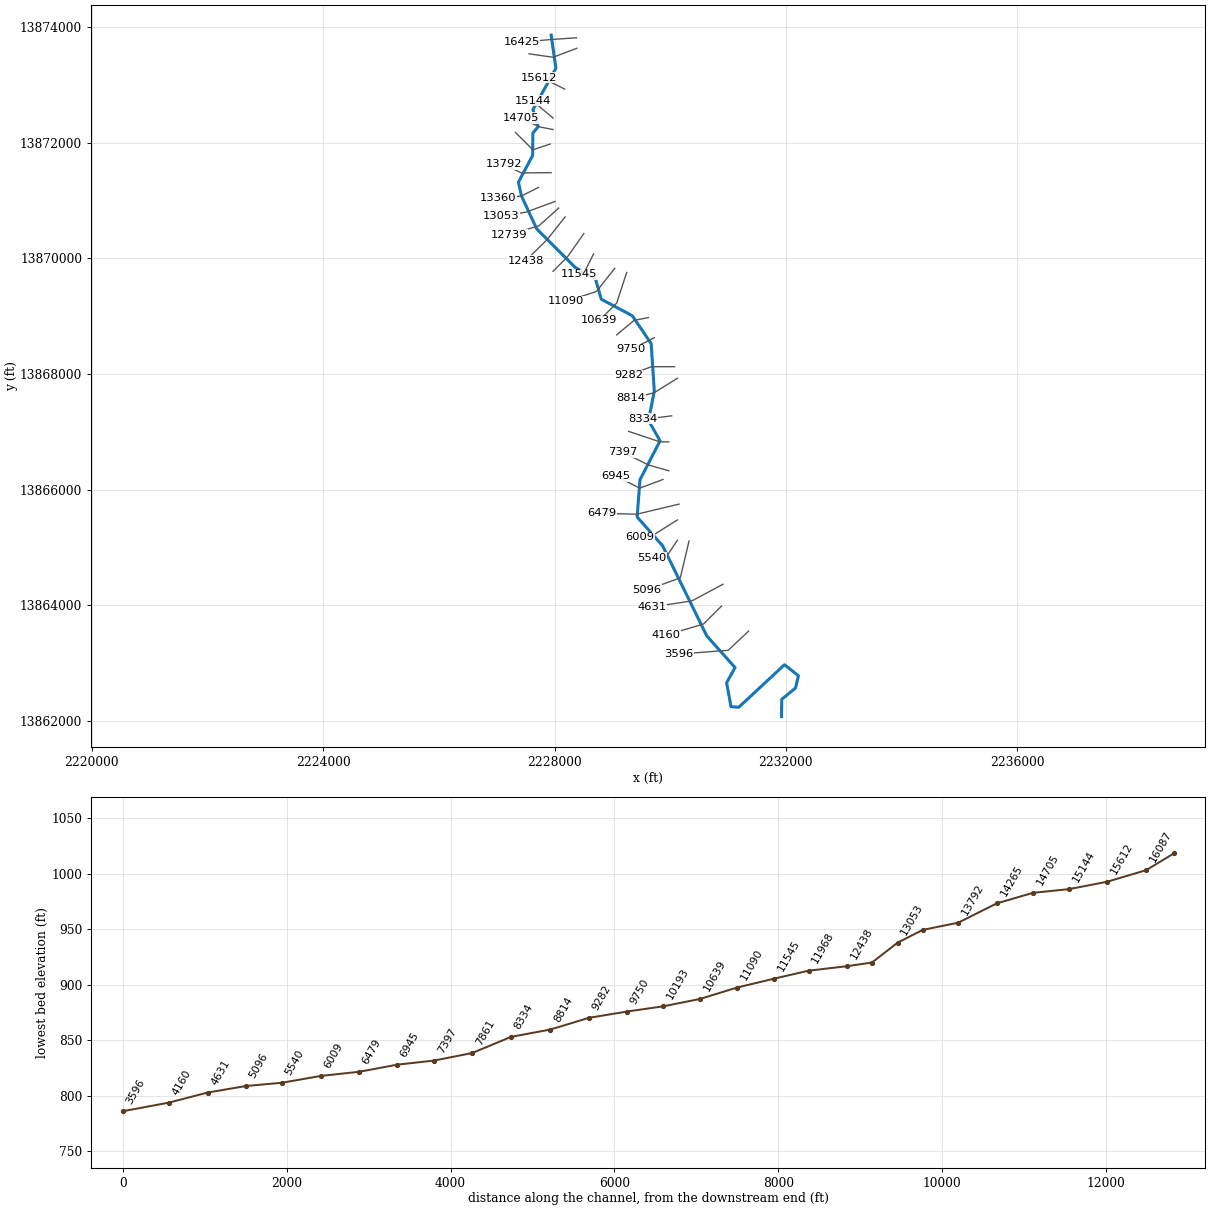
--- Guadalupe Tributary 29.prj (project) ---

Proj Title=Guadalupe Tributary 29 Base Level Engineering
Current Plan=p01
Default Exp/Contr=0.3,0.1
English Units
Geom File=g01
Flow File=f01
Plan File=p01
Y Axis Title=Elevation
X Axis Title(PF)=Main Channel Distance
X Axis Title(XS)=Station
BEGIN DESCRIPTION:
Guadalupe Tributary 29
END DESCRIPTION:
DSS Export Rating Curves= 0
DSS Export Rating Curve Sorted= 0
DSS Export Volume Flow Curves= 0
DXF OffsetX= 0
DXF OffsetY= 0
DXF ScaleX= 1
DXF ScaleY= 10

--- Guadalupe Tributary 29.p01 (plan) ---

Plan Title=Multiple Run
Short Identifier=Multiple
Geom File=g01
Flow File=f01
Subcritical Flow
K Sum by GR= 0
Std Step Tol= 0.01
Critical Tol= 0.01
Num of Std Step Trials= 20
Max Error Tol= 0.3
Flow Tol Ratio= 0.001
Split Flow NTrial= 30
Split Flow Tol= 0.02
Split Flow Ratio= 0.02
Log Output Level= 0
Friction Slope Method= 1
Unsteady Friction Slope Method= 2
Unsteady Bridges Friction Slope Method= 1
Parabolic Critical Depth
Global Vel Dist=  1 , 1 , 1
Global Log Level= 0
CheckData=True
Encroach Param= -1, 0, 0, 0
BEGIN DESCRIPTION:
Multiple Run
END DESCRIPTION:

--- Guadalupe Tributary 29.f01 (steady flow) ---

Flow Title=Multiple
Number of Profiles=7
Profile Names=10-year,25-year,50-year,1pct_min,100-year,1pct_plu,500-year
River Rch & RM= Guadalupe Tribut,Reach-1,16425
    1153    1956    2720    1833    3658    7299    6543
River Rch & RM= Guadalupe Tribut,Reach-1,9282
    1858    3240    4592    3150    6284   12539   11647
Boundary for River Rch & Prof#=Guadalupe Tribut,Reach-1,1
Up Type=0
Dn Type=3
Dn Slope=0.005
Boundary for River Rch & Prof#=Guadalupe Tribut,Reach-1,2
Up Type=0
Dn Type=3
Dn Slope=0.005
Boundary for River Rch & Prof#=Guadalupe Tribut,Reach-1,3
Up Type=0
Dn Type=3
Dn Slope=0.005
Boundary for River Rch & Prof#=Guadalupe Tribut,Reach-1,4
Up Type=0
Dn Type=3
Dn Slope=0.005
Boundary for River Rch & Prof#=Guadalupe Tribut,Reach-1,5
Up Type=0
Dn Type=3
Dn Slope=0.005
Boundary for River Rch & Prof#=Guadalupe Tribut,Reach-1,6
Up Type=0
Dn Type=3
Dn Slope=0.005
Boundary for River Rch & Prof#=Guadalupe Tribut,Reach-1,7
Up Type=0
Dn Type=3
Dn Slope=0.005

--- Guadalupe Tributary 29.g01 (geometry) ---

Geom Title=Existing Conditions
Program Version=4.10

River Reach=Guadalupe Tribut,Reach-1
Reach XY= 30
      2227942.09     13873857.91      2228024.09     13873284.84
      2227627.14     13872569.03      2227717.67      13872274.9
      2227626.06     13872164.57      2227621.46     13871776.46
      2227375.93     13871315.15      2227428.55     13871076.47
      2227691.65     13870508.33       2228361.7      13869838.4
      2228708.58      13869641.8      2228808.21     13869291.44
      2229345.42     13869005.23      2229671.25     13868523.45
       2229725.2     13867699.92      2229625.04     13867195.03
      2229824.96     13866843.33      2229477.24     13866169.07
      2229428.46      13865526.5      2229869.48     13865027.43
      2230633.14     13863468.94       2231121.9     13862923.35
      2230975.51     13862659.79      2231051.42     13862247.82
      2231184.79     13862235.43      2231976.65      13862971.9
      2232217.24     13862781.17      2232166.87     13862568.93
      2231928.54     13862373.54        2231925.       13862075.

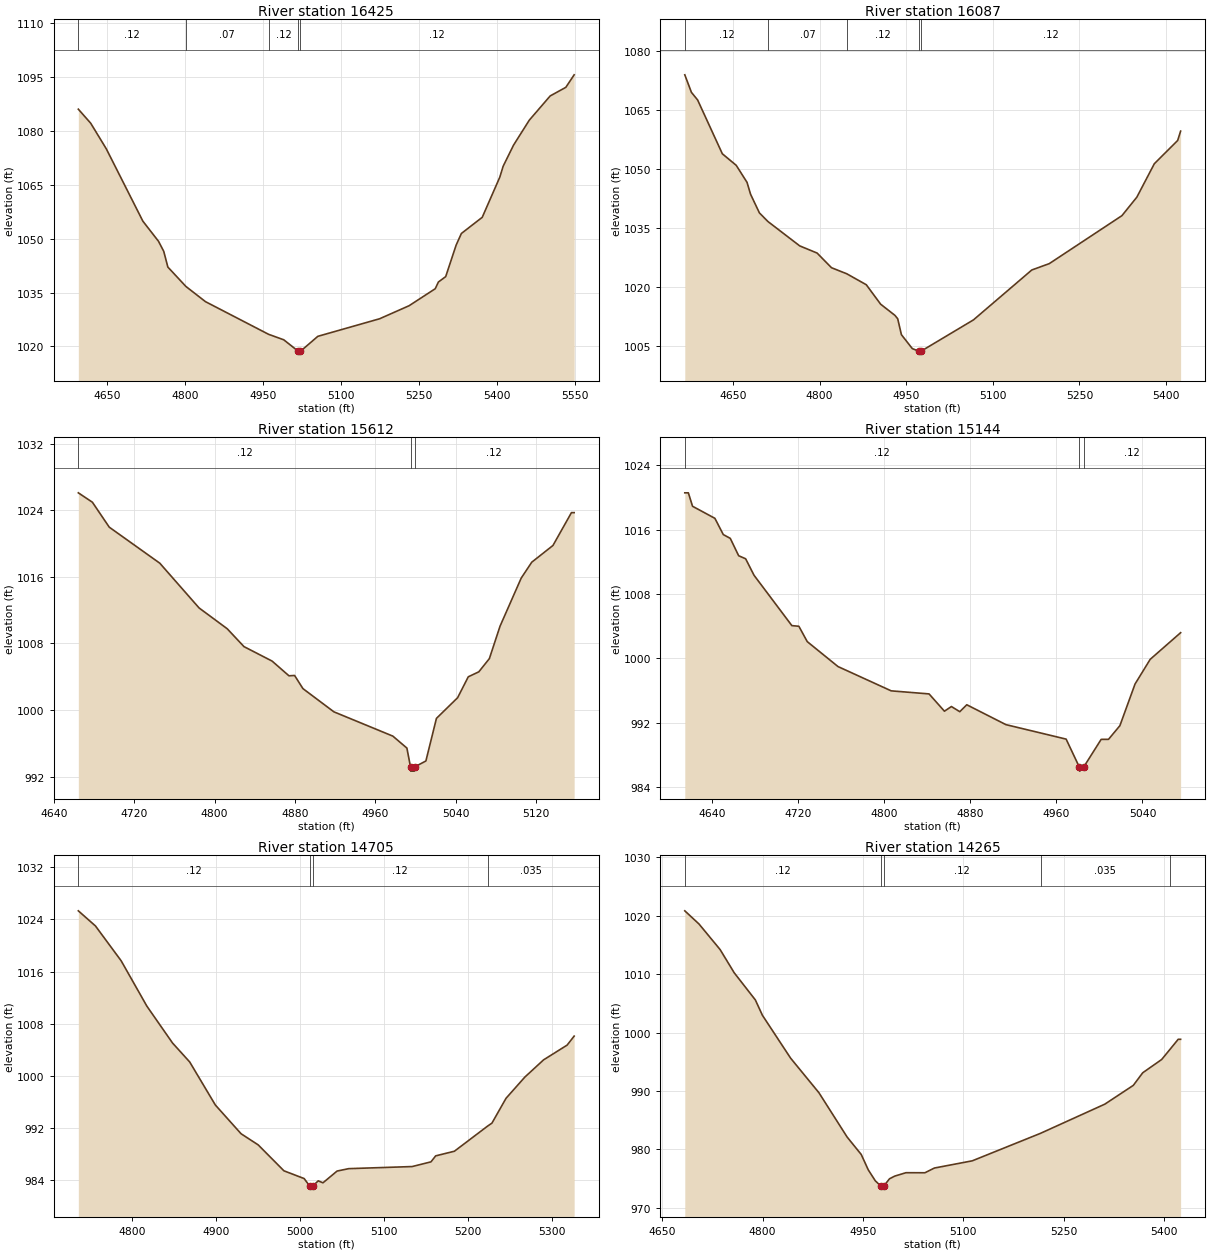
Type RM Length L Ch R = 1 ,16425   ,338,338,338
BEGIN DESCRIPTION:
A19317
END DESCRIPTION:
XS GIS Cut Line= 3
      2228378.71     13873812.18      2227919.46     13873780.14
      2227429.08     13873737.49
#Sta/Elev= 30
  4595.5 1086.03  4619.3 1082.12  4649.3 1074.98  4719.5 1054.87  4749.6 1049.26
  4759.6 1046.47  4767.5  1042.1  4802.1 1036.71  4839.8 1032.47  4961.1 1023.38
  4990.2 1021.86  5018.2 1018.65  5018.5 1018.15  5022.2 1018.65  5055.6 1022.82
  5174.3 1027.71    5231 1031.34  5281.2 1036.07  5287.3 1037.94  5301.3 1039.44
  5321.3 1048.18  5331.4 1051.44  5371.5 1055.94  5405.2  1067.1  5411.7 1070.16
  5431.7 1076.04  5461.9 1082.97    5502 1089.71  5532.1 1092.11  5548.1 1095.59
#Mann= 5 ,-1 , 0
  4595.5     .12       0  4802.1     .07       0  4961.1     .12       0
  5018.2     .05       0  5022.2     .12       0
Bank Sta=5018.2,5022.2
XS Rating Curve= 0 ,0
Exp/Cntr=0.3,0.1

Type RM Length L Ch R = 1 ,16087   ,475,475,475
BEGIN DESCRIPTION:
Guadalupe Tributary 29 35.0
END DESCRIPTION:
XS GIS Cut Line= 3
       2228385.8     13873630.59        2227975.       13873475.
      2227559.92     13873534.48
#Sta/Elev= 30
  4566.7 1073.98  4578.2 1069.51  4588.9 1067.58  4631.7 1053.87  4655.8 1050.92
  4674.5 1046.58  4680.6 1043.56  4695.9 1038.81  4710.7 1036.61  4765.7 1030.41
  4795.8 1028.58  4820.7 1024.85  4847.2  1023.3    4881 1020.51  4905.8 1015.56
  4930.6 1012.71  4935.4 1011.84  4941.8 1007.79  4960.7 1004.24  4971.9 1003.59
  4972.1 1003.09  4975.9 1003.59  5066.6 1011.56  5167.6 1024.27  5197.9 1025.89
  5323.7 1038.11  5349.5 1042.82  5379.8 1051.34  5420.2 1057.26  5425.3 1059.64
#Mann= 5 ,-1 , 0
  4566.7     .12       0  4710.7     .07       0  4847.2     .12       0
  4971.9     .05       0  4975.9     .12       0
Bank Sta=4971.9,4975.9
XS Rating Curve= 0 ,0
Exp/Cntr=0.3,0.1

Type RM Length L Ch R = 1 ,15612   ,468,468,468
BEGIN DESCRIPTION:
Guadalupe Tributary 29 34.0
END DESCRIPTION:
XS GIS Cut Line= 3
      2228175.04     13872924.98        2227875.       13873075.
      2227724.97     13873125.01
#Sta/Elev= 30
  4664.3 1026.11  4678.3 1024.98  4695.1 1021.98  4745.4 1017.65  4784.5 1012.27
  4812.5 1009.77  4829.2 1007.62  4857.2 1005.88    4874 1004.11  4879.6 1004.15
  4887.9 1002.57  4918.7  999.78  4977.4  996.86  4991.4  995.42    4995  993.15
  4995.2  992.65  4998.7  992.65    4999  993.15  5010.3  993.87  5020.8  998.99
  5041.9 1001.48  5052.5 1003.99    5063 1004.59  5073.5 1006.18  5084.1 1010.07
  5105.2 1015.86  5115.7 1017.77  5136.8 1019.78  5155.2 1023.73  5157.9 1023.73
#Mann= 3 ,-1 , 0
  4664.3     .12       0    4995     .05       0    4999     .12       0
Bank Sta=4995,4999
XS Rating Curve= 0 ,0
Exp/Cntr=0.3,0.1

Type RM Length L Ch R = 1 ,15144   ,439,439,439
BEGIN DESCRIPTION:
Guadalupe Tributary 29 33.0
END DESCRIPTION:
XS GIS Cut Line= 3
        2227975.       13872425.        2227675.       13872675.
      2227625.02     13872724.98
#Sta/Elev= 30
  4614.3 1020.56  4617.6 1020.56  4621.5 1018.89  4642.3 1017.39  4650.1 1015.37
  4656.6  1014.9  4664.4 1012.74  4670.9 1012.36  4678.7 1010.31  4713.9 1004.05
  4720.4 1003.97  4728.2 1002.06  4756.8  998.96  4806.3  995.94  4841.5  995.56
  4855.8  993.41  4862.3  993.99  4870.1  993.35  4876.6  994.21    4913  991.74
    4969  989.94  4981.3  986.46  4981.6  985.96  4985.3  986.46  5001.6  989.91
  5008.4  989.91    5019  991.61  5033.1  996.79  5047.2  999.86  5075.5 1003.17
#Mann= 3 ,-1 , 0
  4614.3     .12       0  4981.3     .05       0  4985.3     .12       0
Bank Sta=4981.3,4985.3
XS Rating Curve= 0 ,0
Exp/Cntr=0.3,0.1

Type RM Length L Ch R = 1 ,14705   ,440,440,440
BEGIN DESCRIPTION:
Guadalupe Tributary 29 32.0
END DESCRIPTION:
XS GIS Cut Line= 3
      2227975.01       13872225.        2227725.       13872275.
      2227424.97     13872425.02
#Sta/Elev= 30
  4735.8 1025.32  4756.2    1023  4786.8 1017.66  4817.4 1010.71    4848 1005.05
  4868.4 1002.15    4899  995.54  4929.6  991.14    4950  989.43  4980.6  985.46
  5004.7  984.27  5011.1  983.15  5011.4  982.65  5014.9  982.65  5015.1  983.15
  5021.5  983.92  5027.1  983.62  5043.9  985.42  5057.8  985.79  5133.3  986.11
  5155.7  986.83  5161.3  987.75  5183.6  988.46  5223.3  992.33  5228.3  992.77
  5245.1  996.58  5267.5  999.83  5289.8 1002.47  5317.8 1004.73  5326.2 1006.11
#Mann= 4 ,-1 , 0
  4735.8     .12       0  5011.1     .05       0  5015.1     .12       0
  5223.3    .035       0
Bank Sta=5011.1,5015.1
XS Rating Curve= 0 ,0
Exp/Cntr=0.3,0.1

Type RM Length L Ch R = 1 ,14265   ,473,473,473
BEGIN DESCRIPTION:
Guadalupe Tributary 29 31.0
END DESCRIPTION:
XS GIS Cut Line= 3
      2227924.98     13871974.99        2227625.       13871875.
      2227324.98     13872175.02
#Sta/Elev= 30
  4683.9 1020.82    4705 1018.58  4736.6  1014.2  4757.7 1010.22  4789.3 1005.57
  4799.8 1002.95    4842   995.6  4884.2   989.7  4926.3  982.12  4947.4  979.13
  4957.9   976.5  4968.5  974.61    4977   973.7  4977.3   973.2  4980.8   973.2
    4981   973.7  4989.6  974.97  4997.5  975.43  5014.2  976.01  5042.5     976
  5056.7  976.81  5113.2  978.04  5215.2  982.75  5311.2  987.74  5353.7  990.95
  5367.8  993.11  5396.1  995.38  5408.9  997.17  5420.8  998.84  5424.4  998.84
#Mann= 5 ,-1 , 0
  4683.9     .12       0    4977     .05       0    4981     .12       0
  5215.2    .035       0  5408.9     .12       0
Bank Sta=4977,4981
XS Rating Curve= 0 ,0
Exp/Cntr=0.3,0.1

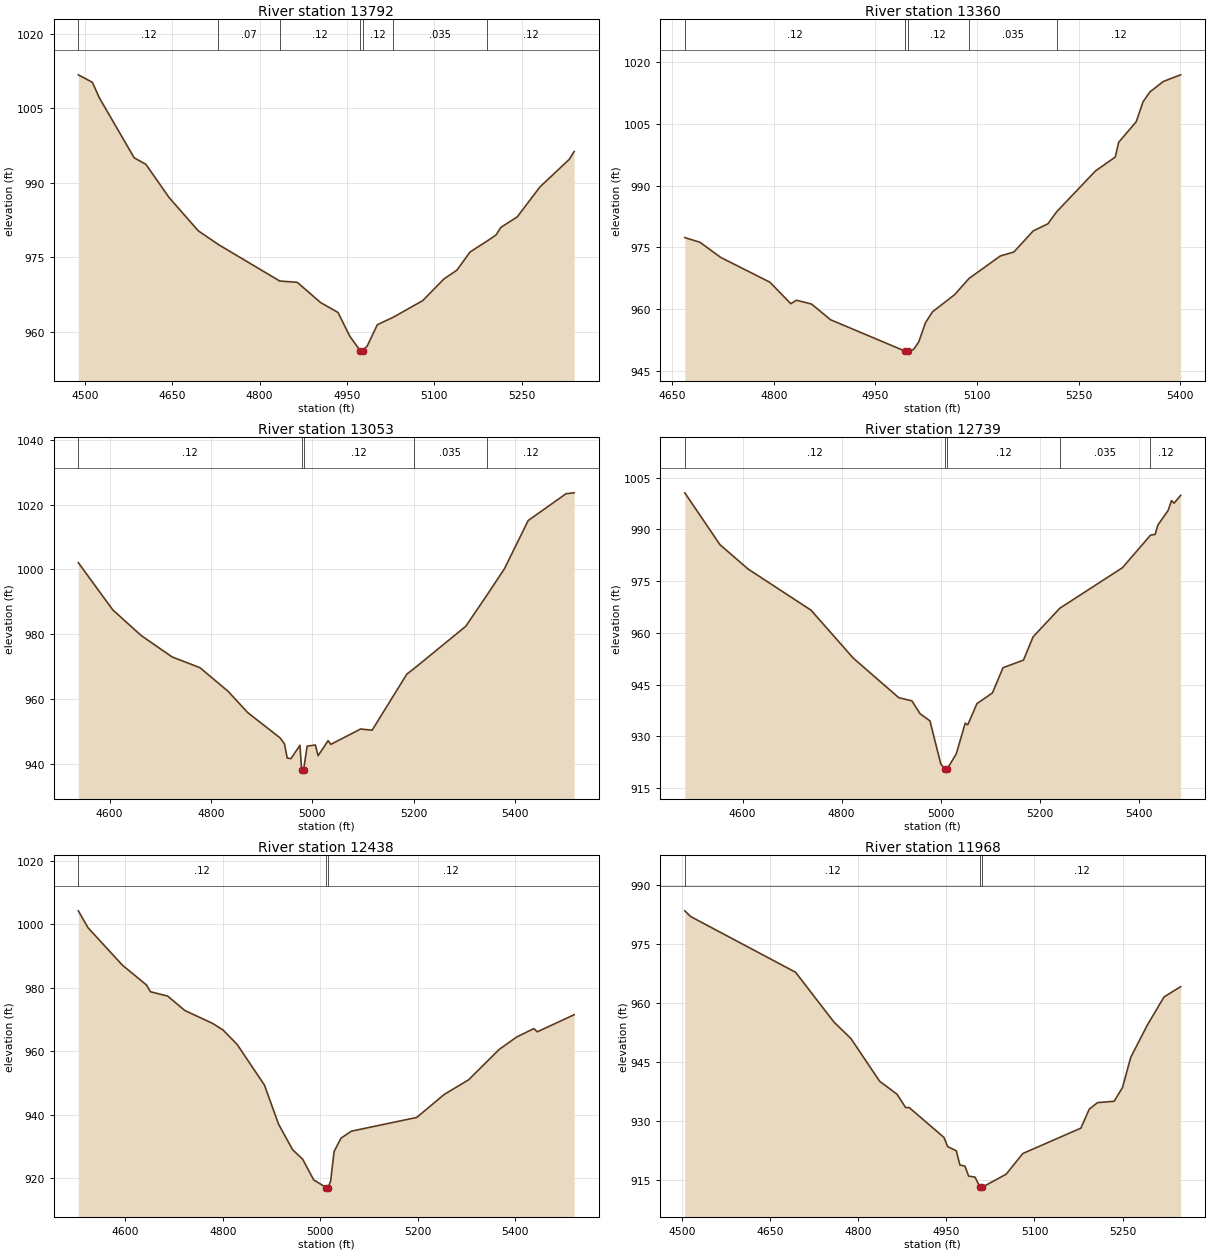
Type RM Length L Ch R = 1 ,13792   ,432,432,432
BEGIN DESCRIPTION:
Guadalupe Tributary 29 30.0
END DESCRIPTION:
XS GIS Cut Line= 3
      2227940.85     13871480.28        2227425.       13871475.
      2227124.99     13871625.01
#Sta/Elev= 30
  4488.8 1011.75    4513 1010.24  4524.7 1007.16  4584.7  995.05  4604.7  993.75
  4644.7  987.05  4694.7  980.36  4729.4  977.59  4834.6  970.25  4864.7  969.99
  4904.7  965.92  4934.7  963.92  4954.7  959.18  4972.7  956.24  4972.9  955.74
  4976.7  956.24  4984.7  957.15  5002.2  961.46  5029.8  962.98  5080.1  966.31
  5116.5  970.67  5138.8  972.44  5161.2  976.08  5191.2  978.34  5205.9  979.52
  5214.3  981.05  5242.3  983.15  5281.4  989.19  5331.7  994.74  5340.1  996.31
#Mann= 7 ,-1 , 0
  4488.8     .12       0  4729.4     .07       0  4834.6     .12       0
  4972.7     .05       0  4976.7     .12       0  5029.8    .035       0
  5191.2     .12       0
Bank Sta=4972.7,4976.7
XS Rating Curve= 0 ,0
Exp/Cntr=0.3,0.1

Type RM Length L Ch R = 1 ,13360   ,307,307,307
BEGIN DESCRIPTION:
Guadalupe Tributary 29 29.0
END DESCRIPTION:
XS GIS Cut Line= 3
      2227724.97     13871224.98        2227425.       13871075.
      2227029.72     13871042.41
#Sta/Elev= 30
  4668.5  977.35  4690.8  976.22  4721.6  972.53  4794.2  966.51    4825  961.29
  4833.4  962.14  4855.7   961.2  4883.7  957.39  4993.5  949.78  4993.7  949.28
  4997.5  949.78  5006.4  950.18  5013.9  952.02  5023.9  956.68    5034  959.29
  5066.9  963.49  5088.2  967.44  5134.3  972.88  5154.4  973.86  5182.9  978.98
  5204.6  980.71  5217.3  983.59  5274.8  993.55    5304  996.92    5309  1000.5
    5335 1005.52    5345 1010.34  5355.1 1012.74  5375.1  1015.3  5400.5  1016.9
#Mann= 5 ,-1 , 0
  4668.5     .12       0  4993.5     .05       0  4997.5     .12       0
  5088.2    .035       0  5217.3     .12       0
Bank Sta=4993.5,4997.5
XS Rating Curve= 0 ,0
Exp/Cntr=0.3,0.1

Type RM Length L Ch R = 1 ,13053   ,314,314,314
BEGIN DESCRIPTION:
A19316
END DESCRIPTION:
XS GIS Cut Line= 3
      2228008.46     13870981.86      2227506.48     13870796.73
      2227069.25     13870725.64
#Sta/Elev= 30
  4538.4 1002.09  4606.5  987.51    4662  979.67  4723.3  973.02  4778.4  969.69
    4834  962.38  4872.5  955.85  4936.4  948.03  4945.1  946.19  4950.4  941.82
  4957.8  941.64  4975.5  945.76  4978.8  938.28  4979.1  937.78  4982.8  938.28
  4989.7   945.5    5006  945.84  5011.3  942.54  5031.1  947.19  5036.4  946.03
  5095.2  950.78  5117.9  950.41  5186.4  967.73    5200  969.35  5302.6  982.47
  5343.8  991.96  5378.9 1000.23  5425.7  1015.1  5500.4 1023.38  5516.4 1023.65
#Mann= 5 ,-1 , 0
  4538.4     .12       0  4978.8     .05       0  4982.8     .12       0
    5200    .035       0  5343.8     .12       0
Bank Sta=4978.8,4982.8
XS Rating Curve= 0 ,0
Exp/Cntr=0.3,0.1

Type RM Length L Ch R = 1 ,12739   ,301,301,301
BEGIN DESCRIPTION:
Guadalupe Tributary 29 28.0
END DESCRIPTION:
XS GIS Cut Line= 3
      2228072.51      13870867.9      2227730.77     13870561.76
      2227210.98     13870405.11
#Sta/Elev= 30
  4483.4 1000.63  4554.5  985.58  4611.4  978.51  4738.4  966.58  4823.7  952.68
  4915.6   941.2  4942.2  940.27  4958.7  936.56  4978.7  934.45  5000.5  922.01
  5008.9  920.38  5009.2  919.88  5012.9  920.38  5031.8  924.88  5049.9  933.79
  5055.1  933.32  5073.6  939.47  5104.9  942.57  5126.3  949.89  5167.6  952.09
  5187.1  958.86  5241.2  967.16  5367.7  978.92  5424.2  988.34  5433.7  988.59
  5439.1  991.27    5460  995.55  5466.7  998.39  5471.9  997.62  5485.1  999.89
#Mann= 5 ,-1 , 0
  4483.4     .12       0  5008.9     .05       0  5012.9     .12       0
  5241.2    .035       0  5424.2     .12       0
Bank Sta=5008.9,5012.9
XS Rating Curve= 0 ,0
Exp/Cntr=0.3,0.1

Type RM Length L Ch R = 1 ,12438   ,470,470,470
BEGIN DESCRIPTION:
Guadalupe Tributary 29 27.0
END DESCRIPTION:
XS GIS Cut Line= 3
      2228182.92     13870714.86        2227875.       13870325.
      2227502.95     13869960.12
#Sta/Elev= 30
  4503.2 1004.26  4523.1  998.94  4593.6  987.16  4643.3  980.88  4651.3  978.77
  4686.6  977.41  4721.8  972.87  4779.6  968.74  4800.4  966.71  4829.3  962.16
  4885.3  949.36  4914.2  937.08  4943.1  929.02  4963.9  925.99  4986.4  919.49
  5012.1  917.09  5012.3  916.59  5016.1  917.09  5021.2  919.17  5028.2  928.42
  5042.4  932.63  5063.6  934.84  5197.9  939.17  5254.5  946.44  5304.1  950.99
  5367.7  960.66  5403.1  964.51  5438.4  967.16  5445.5  966.15  5521.1  971.53
#Mann= 3 ,-1 , 0
  4503.2     .12       0  5012.1     .05       0  5016.1     .12       0
Bank Sta=5012.1,5016.1
XS Rating Curve= 0 ,0
Exp/Cntr=0.3,0.1

Type RM Length L Ch R = 1 ,11968   ,423,423,423
BEGIN DESCRIPTION:
Guadalupe Tributary 29 26.0
END DESCRIPTION:
XS GIS Cut Line= 3
      2228506.91     13870426.52        2228225.       13870025.
      2227974.97     13869774.97
#Sta/Elev= 30
  4504.6  983.47  4514.6  982.01  4693.2  967.82  4758.6  955.12  4787.5  950.92
  4836.4  940.04  4865.8  936.77  4880.6  933.35  4886.7  933.34    4946  925.72
  4952.1   923.4  4966.9  922.32    4973  918.71  4981.7  918.42  4987.8  915.88
  4998.7  915.63  5007.3  913.06  5007.6  912.56  5011.3  913.06  5051.8  916.37
  5080.1  921.63    5179   928.1  5193.2  932.93  5207.3   934.6  5235.6  934.95
  5249.8  938.44  5263.9  946.16  5292.2  954.38  5320.5  961.52  5348.8  964.15
#Mann= 3 ,-1 , 0
  4504.6     .12       0  5007.3     .05       0  5011.3     .12       0
Bank Sta=5007.3,5011.3
XS Rating Curve= 0 ,0
Exp/Cntr=0.3,0.1

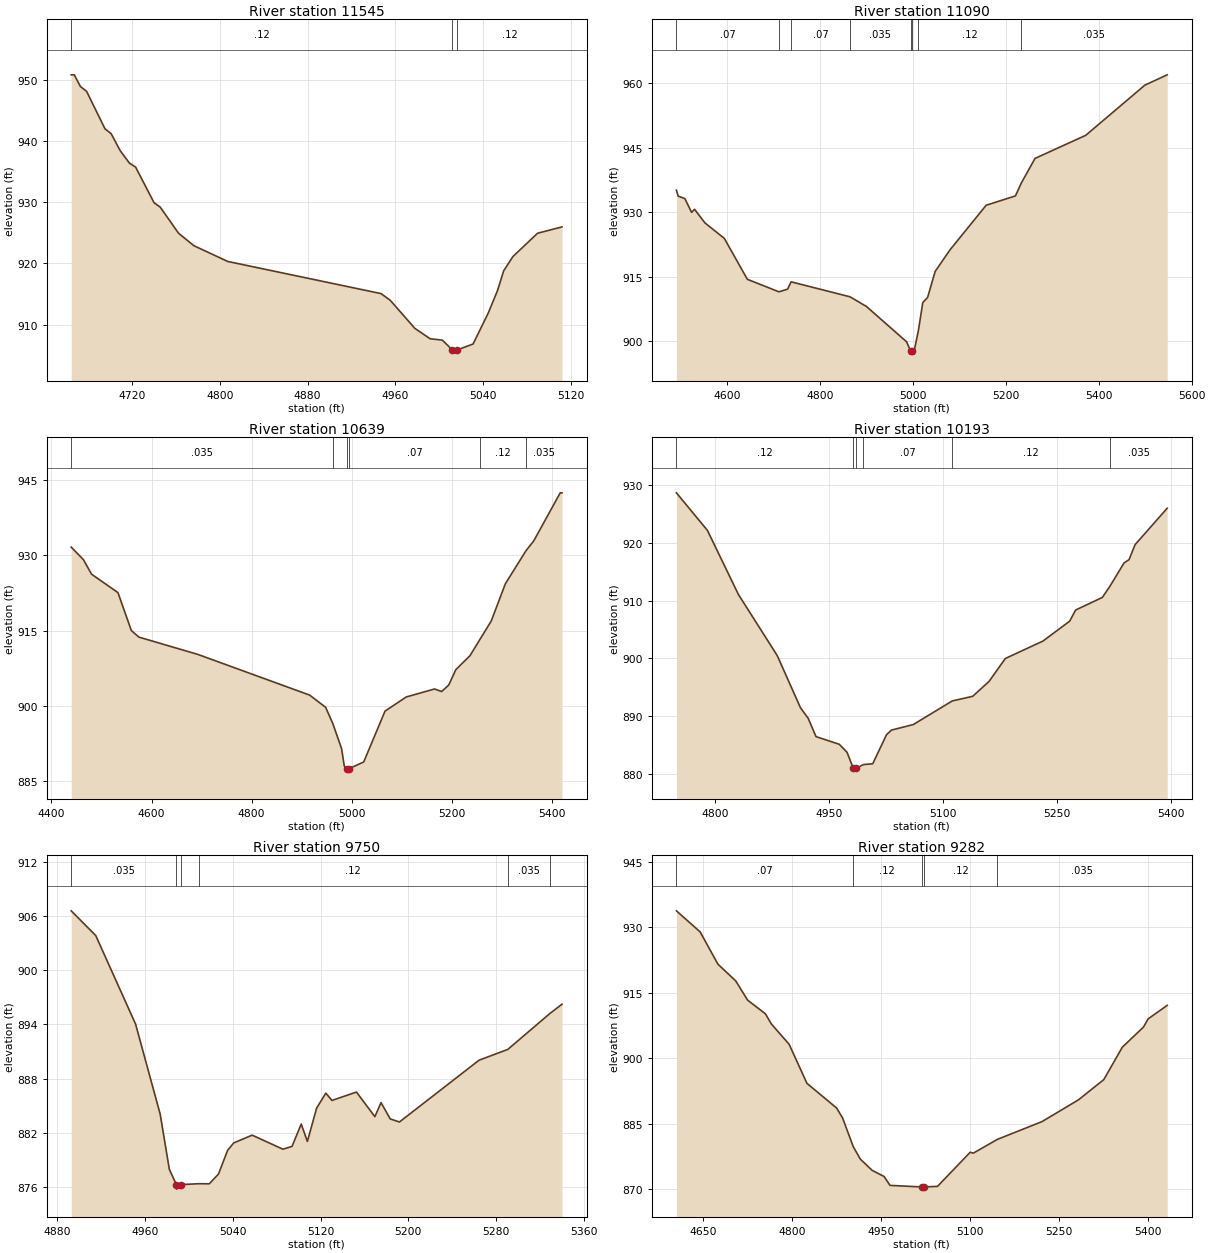
Type RM Length L Ch R = 1 ,11545   ,455,455,455
BEGIN DESCRIPTION:
Guadalupe Tributary 29 25.0
END DESCRIPTION:
XS GIS Cut Line= 3
      2228675.01     13870075.01        2228525.       13869775.
      2228425.03     13869725.01
#Sta/Elev= 30
  4664.6  950.79  4667.4  950.79    4673  948.88  4678.6   948.1  4695.4  941.97
    4701  941.18  4709.3  938.39  4717.7  936.36  4723.3  935.72  4740.1  929.91
  4745.7  929.19  4762.4  924.93  4776.4  922.89  4807.2  920.32  4946.9  915.07
  4955.3  913.98  4977.7   909.4  4991.6   907.7  5002.8  907.47    5012  905.85
  5012.3  905.35  5015.8  905.35    5016  905.85  5030.8  906.84  5044.7  911.93
  5053.1  915.59  5058.7   918.8  5067.1  921.12  5089.5  924.92  5111.8  925.96
#Mann= 3 ,-1 , 0
  4664.6     .12       0    5012     .05       0    5016     .12       0
Bank Sta=5012,5016
XS Rating Curve= 0 ,0
Exp/Cntr=0.3,0.1

Type RM Length L Ch R = 1 ,11090   ,451,451,451
BEGIN DESCRIPTION:
Guadalupe Tributary 29 24.0
END DESCRIPTION:
XS GIS Cut Line= 3
       2229040.9      13869824.8        2228725.       13869425.
      2228204.23     13869255.18
#Sta/Elev= 30
    4490  935.17  4493.8  933.78  4508.2  933.21  4522.7     930    4529  930.73
  4551.5  927.55  4593.2  923.96  4642.8  914.45  4710.9  911.54  4729.5  912.16
  4737.1  913.86    4864  910.38  4899.3  908.14  4985.9  899.92  4994.4  897.79
  4994.6  897.29  4998.4  897.79  5002.2  897.79  5011.3  902.54  5020.8  909.05
  5031.1  910.22  5047.4  916.28  5079.3  921.28  5157.3  931.66  5220.4  933.83
  5232.7  936.76  5262.5  942.54  5371.7   947.9  5499.3  959.58  5547.3  961.97
#Mann= 8 ,-1 , 0
    4490     .07       0  4710.9    .035       0  4737.1     .07       0
    4864    .035       0  4994.4    .035       0  4998.4    .035       0
  5011.3     .12       0  5232.7    .035       0
Bank Sta=4994.4,4998.4
XS Rating Curve= 0 ,0
Exp/Cntr=0.3,0.1

Type RM Length L Ch R = 1 ,10639   ,446,446,446
BEGIN DESCRIPTION:
Guadalupe Tributary 29 23.0
END DESCRIPTION:
XS GIS Cut Line= 3
      2229247.41     13869753.65        2229075.       13869225.
      2228775.01     13868925.01
#Sta/Elev= 30
  4439.6  931.63    4464  929.13  4480.2  926.24    4533  922.57  4559.7  915.02
  4574.9  913.71  4692.6  910.27  4915.9  902.17  4947.8  899.74  4962.1  896.52
  4979.7   891.5  4985.1  888.04    4991  887.54  4991.3  887.04    4995  887.54
  5023.9  888.87  5066.4  898.98  5108.8   901.8  5165.4  903.39  5179.5  902.88
  5193.6  904.16  5207.8  907.23  5236.1  910.01  5256.3   913.3  5278.5   916.9
  5306.8  924.33  5348.2  930.94  5363.3  932.83  5416.4  942.43  5419.9  942.43
#Mann= 6 ,-1 , 0
  4439.6    .035       0  4962.1     .07       0    4991     .05       0
    4995     .07       0  5256.3     .12       0  5348.2    .035       0
Bank Sta=4991,4995
XS Rating Curve= 0 ,0
Exp/Cntr=0.3,0.1

Type RM Length L Ch R = 1 ,10193   ,443,443,443
BEGIN DESCRIPTION:
Guadalupe Tributary 29 22.0
END DESCRIPTION:
XS GIS Cut Line= 3
        2229625.       13868975.        2229375.       13868925.
      2229074.97     13868674.97
#Sta/Elev= 30
  4749.5  928.66  4790.3  922.15  4831.1  911.04  4882.1  900.47  4912.7  891.42
  4922.9  889.58  4933.1  886.43  4963.7   885.1  4973.9  883.72  4982.1  880.95
  4982.3  880.45  4986.1  880.95  4995.3  881.58  5007.7  881.73  5025.9  886.77
  5032.4  887.56  5061.1  888.52  5112.3  892.61  5139.2  893.41  5160.7  895.99
  5182.1  899.96  5231.6  902.98  5266.7  906.43  5274.6  908.36  5309.7  910.54
  5319.9  912.52  5338.3  916.53  5344.8  917.08  5352.7  919.67    5395  925.99
#Mann= 6 ,-1 , 0
  4749.5     .12       0  4982.1     .05       0  4986.1     .12       0
  4995.3     .07       0  5112.3     .12       0  5319.9    .035       0
Bank Sta=4982.1,4986.1
XS Rating Curve= 0 ,0
Exp/Cntr=0.3,0.1

Type RM Length L Ch R = 1 ,9750    ,468,468,468
BEGIN DESCRIPTION:
Guadalupe Tributary 29 21.0
END DESCRIPTION:
XS GIS Cut Line= 3
        2229725.       13868625.        2229625.       13868575.
      2229325.01       13868425.
#Sta/Elev= 30
  4892.8  906.61  4915.2  903.86  4951.5  894.03  4973.9  884.04  4982.2  877.94
  4988.6  876.23  4988.9  875.73  4992.6  876.23  5008.8  876.33  5018.6  876.32
    5027   877.4  5035.3  880.03  5040.9  880.86  5057.7  881.72  5085.7  880.16
    5094  880.47  5102.4  882.95    5108  881.02  5116.4  884.71  5124.8  886.38
  5130.4  885.57  5152.7   886.5  5169.5  883.77  5175.1  885.33  5183.5  883.52
  5191.9  883.18  5264.5  890.04  5290.6  891.23  5329.1  895.23    5340  896.25
#Mann= 6 ,-1 , 0
  4892.8    .035       0  4988.6    .035       0  4992.6    .035       0
  5008.8     .12       0  5290.6    .035       0  5329.1     .12       0
Bank Sta=4988.6,4992.6
XS Rating Curve= 0 ,0
Exp/Cntr=0.3,0.1

Type RM Length L Ch R = 1 ,9282    ,468,468,468
BEGIN DESCRIPTION:
Guadalupe Tributary 29 20.0
END DESCRIPTION:
XS GIS Cut Line= 3
      2230074.97       13868125.        2229675.       13868125.
      2229274.97     13867974.99
#Sta/Elev= 30
  4604.6  933.78  4644.6  928.95  4674.6  921.55  4704.6  917.72  4724.6  913.32
  4754.6  910.19  4764.6  907.87  4794.6   903.2  4824.6  894.26  4874.6   888.6
  4884.6  886.35  4902.6  879.77  4914.6  876.89  4934.6  874.31  4954.6  872.92
  4964.6  870.88  5017.7  870.52    5018  870.02  5021.7  870.52  5044.6  870.65
  5099.8  878.47  5105.1  878.27  5145.6  881.42  5220.8  885.49  5282.3  890.48
    5325  895.12  5356.1  902.53  5391.7  907.13  5399.7  909.03  5431.8  912.12
#Mann= 5 ,-1 , 0
  4604.6     .07       0  4902.6     .12       0  5017.7     .05       0
  5021.7     .12       0  5145.6    .035       0
Bank Sta=5017.7,5021.7
XS Rating Curve= 0 ,0
Exp/Cntr=0.3,0.1

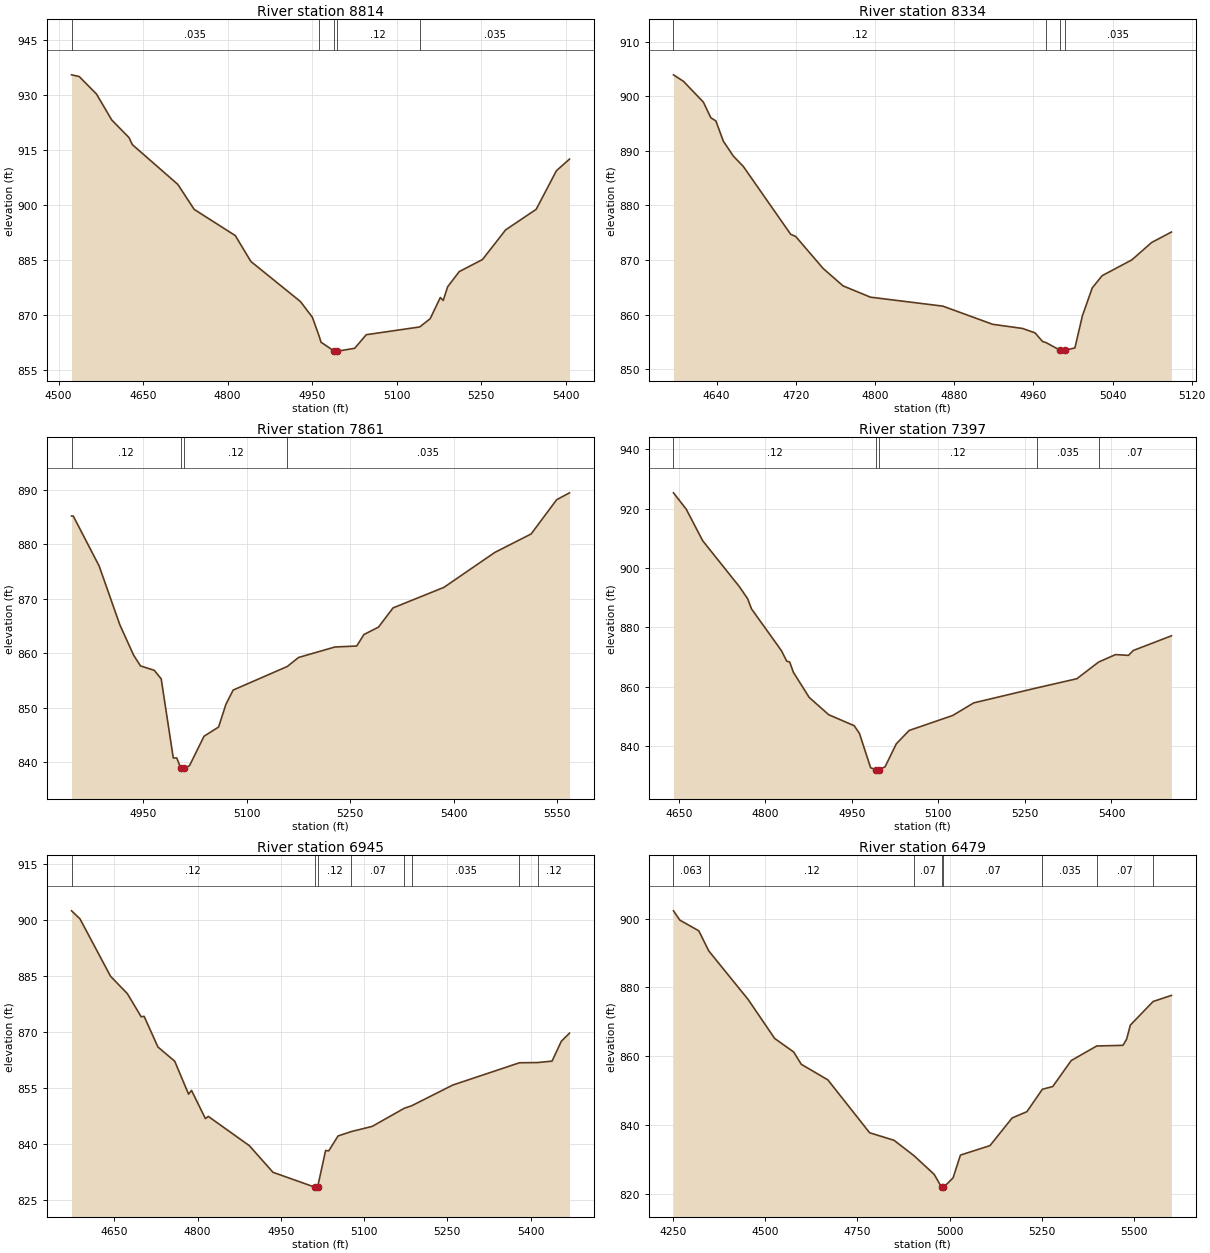
Type RM Length L Ch R = 1 ,8814    ,480,480,480
BEGIN DESCRIPTION:
Guadalupe Tributary 29 19.0
END DESCRIPTION:
XS GIS Cut Line= 3
      2230125.01     13867925.01        2229725.       13867675.
      2229325.02       13867575.
#Sta/Elev= 30
  4522.9  935.52  4536.5  935.05  4567.1  930.29  4594.3  923.18  4624.9  918.39
  4630.8  916.46  4711.6   905.6  4740.5  898.79  4813.6  891.62  4841.3  884.55
  4929.2  873.62  4950.4  869.33  4962.5  864.14  4965.7  862.52  4989.6  860.03
  4989.9  859.53  4993.7  860.03  5025.5  860.85  5046.1  864.56    5141  866.68
  5159.5  868.92  5177.6  874.73  5182.7  873.91  5190.5  877.63  5211.1  881.79
  5252.3  885.07  5293.5  893.18  5347.7  898.79  5383.7  909.35  5406.9  912.51
#Mann= 5 ,-1 , 0
  4522.9    .035       0  4962.5     .12       0  4989.6     .05       0
  4993.7     .12       0    5141    .035       0
Bank Sta=4989.6,4993.7
XS Rating Curve= 0 ,0
Exp/Cntr=0.3,0.1

Type RM Length L Ch R = 1 ,8334    ,473,473,473
BEGIN DESCRIPTION:
Guadalupe Tributary 29 18.0
END DESCRIPTION:
XS GIS Cut Line= 3
      2230025.01       13867275.        2229625.       13867225.
      2229525.02       13867225.
#Sta/Elev= 30
  4596.4  903.91  4606.5  902.72  4626.6  898.91  4634.2  896.03  4639.2  895.48
  4646.8  891.75  4656.9  889.02    4667  887.12  4714.8   874.7  4719.9   874.3
  4747.6  868.44  4767.7  865.25  4795.4  863.18  4868.5  861.54  4918.9  858.21
  4949.1  857.45  4961.7  856.64  4969.3  855.06  4972.7  854.87  4987.3  853.43
  4987.6  852.93  4991.3  852.93  4991.5  853.43    5002  853.89  5009.5  859.74
  5019.5  864.88  5029.5  867.12  5059.5  870.01  5079.5   873.2  5099.5  875.11
#Mann= 4 ,-1 , 0
  4596.4     .12       0  4972.7    .035       0  4987.3    .035       0
  4991.5    .035       0
Bank Sta=4987.3,4991.5
XS Rating Curve= 0 ,0
Exp/Cntr=0.3,0.1

Type RM Length L Ch R = 1 ,7861    ,464,464,464
BEGIN DESCRIPTION:
Guadalupe Tributary 29 17.0
END DESCRIPTION:
XS GIS Cut Line= 4
      2229974.97       13866825.        2229825.       13866825.
        2229675.       13866875.      2229282.23     13867005.92
#Sta/Elev= 30
    4846   885.2  4848.5   885.2    4886  876.04    4916  865.26    4936  859.68
    4946  857.71    4966   856.9    4976  855.33  4993.5  840.83  4998.6  840.83
  5004.4  838.91  5004.7  838.41  5008.7  838.91    5017   839.4  5038.1  844.81
  5059.2   846.5  5069.8  850.65  5080.3  853.28  5158.9  857.61  5175.2  859.26
  5227.9  861.18  5259.5  861.36    5270  863.47  5291.1  864.83  5312.2  868.35
    5386  872.12  5459.8  878.53  5512.5  881.92  5549.4  888.19  5568.1  889.46
#Mann= 4 ,-1 , 0
    4846     .12       0  5004.4     .05       0  5008.7     .12       0
  5158.9    .035       0
Bank Sta=5004.4,5008.7
XS Rating Curve= 0 ,0
Exp/Cntr=0.3,0.1

Type RM Length L Ch R = 1 ,7397    ,452,452,452
BEGIN DESCRIPTION:
Guadalupe Tributary 29 16.0
END DESCRIPTION:
XS GIS Cut Line= 4
      2229975.02     13866324.99        2229625.       13866425.
        2229525.       13866475.      2229178.35     13866648.33
#Sta/Elev= 30
  4640.6  925.31  4662.7  919.81  4691.3  909.17    4755  893.68  4769.3  889.61
  4775.8  886.26  4827.8  872.16  4836.9  868.64  4842.1  868.33  4848.6  864.86
  4875.9  856.43  4909.7  850.61  4953.9  846.91    4963  844.33  4982.5  832.72
  4992.1  832.11  4992.3  831.61  4996.4  832.11  5007.4  833.04    5027  840.83
  5049.3  845.31  5124.8  850.35  5161.2  854.59  5271.2  859.66    5340  862.72
  5377.7  868.33  5407.1  870.85  5429.5  870.58  5437.9  872.23    5504  877.17
#Mann= 5 ,-1 , 0
  4640.6     .12       0  4992.1     .05       0  4996.4     .12       0
  5271.2    .035       0  5377.7     .07       0
Bank Sta=4992.1,4996.4
XS Rating Curve= 0 ,0
Exp/Cntr=0.3,0.1

Type RM Length L Ch R = 1 ,6945    ,466,466,466
BEGIN DESCRIPTION:
Guadalupe Tributary 29 15.0
END DESCRIPTION:
XS GIS Cut Line= 4
      2229874.98     13866174.99        2229475.       13866025.
        2229375.       13866075.      2229054.33     13866235.33
#Sta/Elev= 30
  4572.8  902.38  4587.9  900.25  4643.1  884.86  4673.3  880.23  4698.3  874.03
  4703.6  874.14  4728.5  865.93  4758.8  862.12  4783.7  853.31    4789  854.32
    4814  846.77  4819.3  847.35  4893.2  839.53  4935.9  832.39  5011.8  828.39
  5012.1  827.89  5016.2  828.39  5030.7  838.25  5036.3  838.12  5053.1  842.12
  5077.3  843.31  5114.6  844.68  5172.6  849.54  5185.6  850.19  5259.9  855.75
  5380.1  861.71  5412.8  861.77  5438.8  862.15  5455.6  867.48  5470.3  869.64
#Mann= 8 ,-1 , 0
  4572.8     .12       0  5011.8     .05       0  5016.2     .12       0
  5077.3     .07       0  5172.6     .12       0  5185.6    .035       0
  5380.1     .07       0  5412.8     .12       0
Bank Sta=5011.8,5016.2
XS Rating Curve= 0 ,0
Exp/Cntr=0.3,0.1

Type RM Length L Ch R = 1 ,6479    ,470,470,470
BEGIN DESCRIPTION:
Guadalupe Tributary 29 14.0
END DESCRIPTION:
XS GIS Cut Line= 3
      2230151.66     13865748.44        2229425.       13865575.
      2228823.71     13865588.24
#Sta/Elev= 30
  4252.1  902.24  4269.2  899.55  4320.6  896.44  4347.8  890.59  4454.3   876.5
  4526.2  865.19  4577.7  861.26  4598.2   857.7  4670.2  853.17  4783.3  837.82
  4849.3  835.64  4903.3  831.18    4958  825.76  4978.4  821.96  4978.7  821.46
    4983  821.96  5009.2  824.71  5029.2  831.34  5109.2  834.09  5169.2  842.12
  5209.2  843.94  5251.1  850.45  5279.2  851.24  5329.2  858.78  5398.3  863.01
  5469.3   863.2  5479.3     865  5489.3  869.07  5551.1  875.93  5600.6  877.69
#Mann= 8 ,-1 , 0
  4252.1    .063       0  4347.8     .12       0  4903.3     .07       0
  4978.4     .05       0    4983     .07       0  5251.1    .035       0
  5398.3     .07       0  5551.1     .12       0
Bank Sta=4978.4,4983
XS Rating Curve= 0 ,0
Exp/Cntr=0.3,0.1

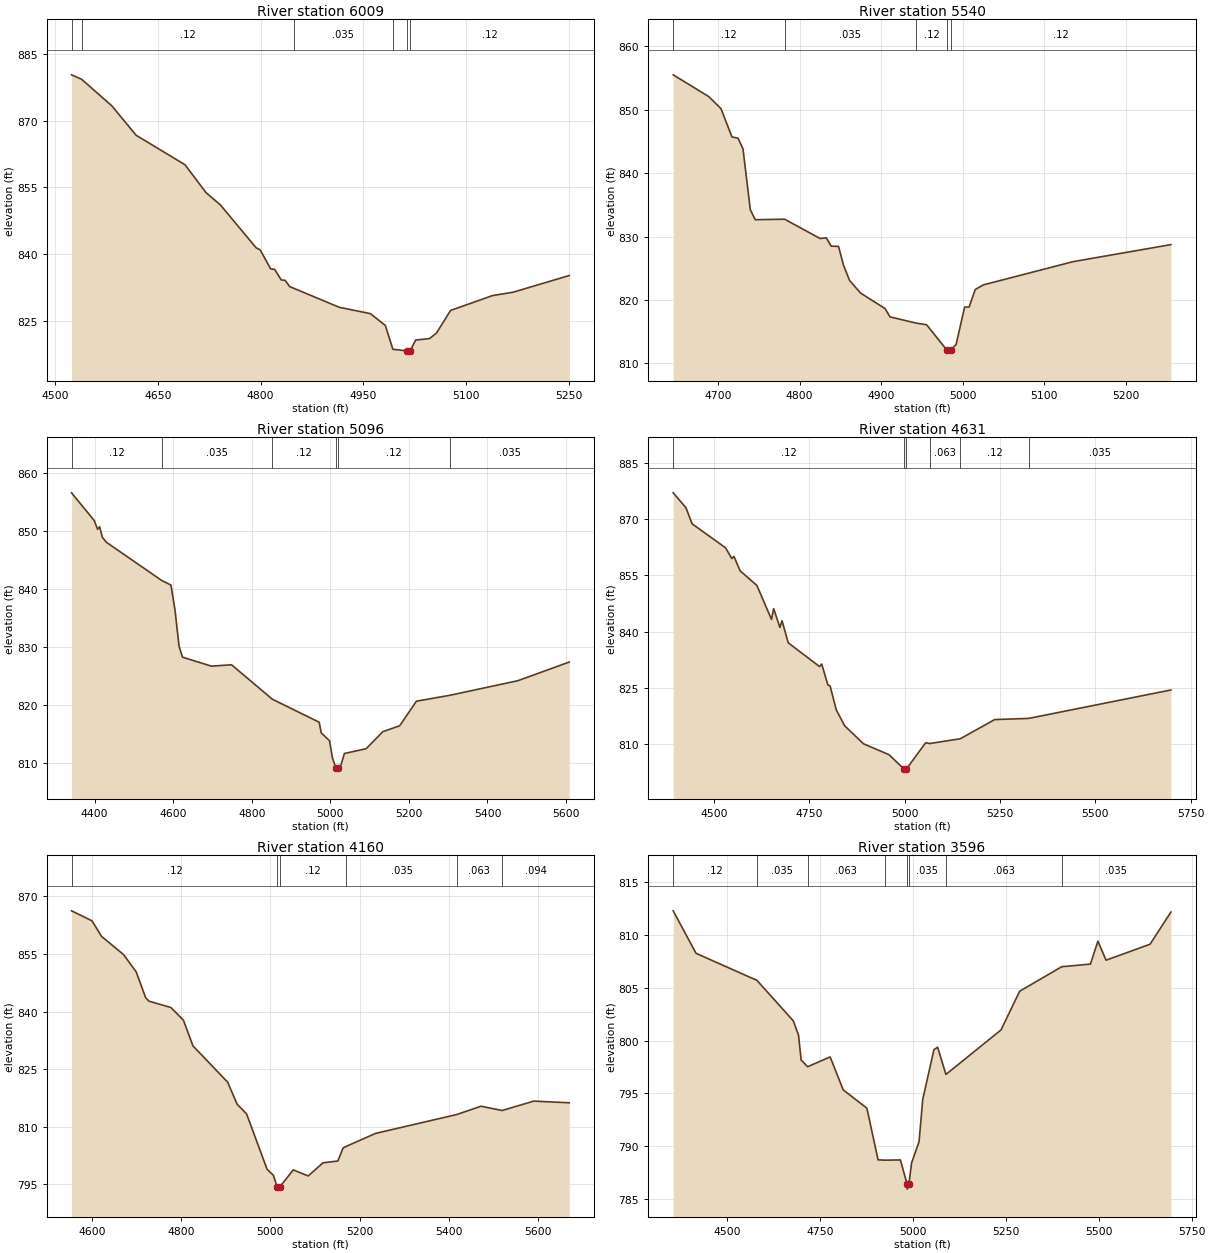
Type RM Length L Ch R = 1 ,6009    ,469,469,469
BEGIN DESCRIPTION:
Guadalupe Tributary 29 13.0
END DESCRIPTION:
XS GIS Cut Line= 3
      2230124.97     13865474.98        2229725.       13865225.
      2229475.02       13865175.
#Sta/Elev= 30
  4523.9  880.34  4538.7  879.33  4582.8  873.35  4618.2  866.74  4689.6   860.1
  4720.2  853.84  4741.4  851.04  4793.3  841.43  4799.2  840.98  4814.6  836.67
  4820.4  836.57  4829.9  834.21  4835.8  834.09  4842.3   832.7  4848.2  832.32
  4914.8  828.03  4960.2  826.61    4982  823.95    4993  818.59  5013.6  818.22
    5014  817.72    5018  817.72  5018.3  818.22  5026.2  820.66  5046.6     821
  5056.8  822.26  5077.2  827.32  5138.3  830.66  5168.9  831.44  5250.5  835.18
#Mann= 6 ,-1 , 0
  4523.9    .035       0  4538.7     .12       0  4848.2    .035       0
    4993     .12       0  5013.6     .05       0  5018.3     .12       0
Bank Sta=5013.6,5018.3
XS Rating Curve= 0 ,0
Exp/Cntr=0.3,0.1

Type RM Length L Ch R = 1 ,5540    ,444,444,444
BEGIN DESCRIPTION:
Guadalupe Tributary 29 12.0
END DESCRIPTION:
XS GIS Cut Line= 3
      2230124.98     13865124.97        2229925.       13864825.
      2229675.02       13864825.
#Sta/Elev= 30
  4644.9  855.53  4688.4  852.11  4703.5   850.2    4717  845.73  4724.5  845.53
  4730.5  843.85  4739.5  834.24  4745.5  832.67  4781.6  832.75  4825.1   829.7
  4832.7  829.81  4838.7   828.5  4847.7  828.46  4853.7  825.54  4861.2   823.1
  4874.7   821.1  4904.8  818.65  4910.8  817.34  4942.9  816.36  4955.8  816.09
  4980.5  812.12  4980.9  811.62  4985.2  812.12  4991.9  812.96  5002.4  818.89
  5007.9  818.89  5015.4  821.66  5025.4  822.39  5135.4  826.05  5255.4  828.74
#Mann= 5 ,-1 , 0
  4644.9     .12       0  4781.6    .035       0  4942.9     .12       0
  4980.5     .05       0  4985.2     .12       0
Bank Sta=4980.5,4985.2
XS Rating Curve= 0 ,0
Exp/Cntr=0.3,0.1

Type RM Length L Ch R = 1 ,5096    ,465,465,465
BEGIN DESCRIPTION:
Guadalupe Tributary 29 11.0
END DESCRIPTION:
XS GIS Cut Line= 3
      2230326.12     13865111.18        2230175.       13864475.
      2229599.91     13864263.89
#Sta/Elev= 30
  4341.6  856.52  4399.3  851.76  4407.9  850.24  4413.1  850.69  4419.9  848.89
  4430.2  848.02  4571.1  841.44  4594.6  840.66  4604.9  836.35  4615.2  830.11
    4624  828.25  4697.4  826.71  4748.8  826.94  4852.6  821.02  4971.8  817.06
    4977  815.23  4998.1  813.88  5005.4  810.96  5014.4  809.15  5014.8  808.65
  5019.1  809.15  5027.4  809.75  5035.9  811.68  5091.4  812.51    5134  815.45
  5176.6  816.45  5219.2  820.68  5304.7   821.7  5477.2   824.2  5608.1  827.41
#Mann= 6 ,-1 , 0
  4341.6     .12       0  4571.1    .035       0  4852.6     .12       0
  5014.4     .05       0  5019.1     .12       0  5304.7    .035       0
Bank Sta=5014.4,5019.1
XS Rating Curve= 0 ,0
Exp/Cntr=0.3,0.1

Type RM Length L Ch R = 1 ,4631    ,471,471,471
BEGIN DESCRIPTION:
Guadalupe Tributary 29 10.0
END DESCRIPTION:
XS GIS Cut Line= 3
      2230913.53     13864363.54        2230375.       13864075.
      2229689.45     13863972.02
#Sta/Elev= 30
  4393.6  876.97    4427     873  4443.2  868.71  4530.9  862.31  4547.2  859.45
  4552.9  860.01  4569.1  856.17    4613  852.28  4651.2  843.22  4656.9  846.11
  4673.1   841.1  4678.8  842.88  4695.1  836.99  4777.1  830.66  4782.8  831.34
    4799  825.75  4804.7  825.52    4821   819.1  4842.9  814.88  4892.4  810.07
  4959.2  807.17  4999.2  803.29  4999.6  802.79  5004.3  803.29  5055.1  810.35
  5065.7  810.14  5145.9  811.42  5236.1  816.53  5325.1  816.84  5697.8  824.42
#Mann= 6 ,-1 , 0
  4393.6     .12       0  4999.2     .05       0  5004.3     .12       0
  5065.7    .063       0  5145.9     .12       0  5325.1    .035       0
Bank Sta=4999.2,5004.3
XS Rating Curve= 0 ,0
Exp/Cntr=0.3,0.1

Type RM Length L Ch R = 1 ,4160    ,564,564,564
BEGIN DESCRIPTION:
Guadalupe Tributary 29 9.0
END DESCRIPTION:
XS GIS Cut Line= 3
      2230888.64     13863986.19        2230575.       13863675.
       2229928.7     13863484.58
#Sta/Elev= 30
  4554.2  866.25  4600.1  863.64  4621.3  859.61  4670.8  854.85  4699.1  850.35
  4720.3  843.63  4727.4  842.73  4776.8  841.07  4805.1  837.74  4826.3  831.07
  4904.1  821.62  4925.3  815.88  4946.5  813.37  4992.5  798.91  5006.5  797.37
  5015.3  794.25  5015.7  793.75  5020.5  794.25  5051.2  798.76  5084.6  797.18
  5117.9  800.61  5151.2  801.08  5162.8  804.47  5170.5  804.92  5235.8  808.27
  5417.5  813.18    5472  815.35  5519.3  814.23  5590.3  816.68  5669.8  816.24
#Mann= 6 ,-1 , 0
  4554.2     .12       0  5015.3     .05       0  5020.5     .12       0
  5170.5    .035       0  5417.5    .063       0  5519.3    .094       0
Bank Sta=5015.3,5020.5
XS Rating Curve= 0 ,0
Exp/Cntr=0.3,0.1

Type RM Length L Ch R = 1 ,3596    ,408,408,408
BEGIN DESCRIPTION:
A19315
END DESCRIPTION:
XS GIS Cut Line= 3
      2231355.03     13863551.86      2231002.55     13863220.74
      2230149.06     13863156.73
#Sta/Elev= 30
  4354.6  812.27  4416.1  808.25    4580  805.69  4677.9  801.86    4692  800.49
  4698.9  798.16  4716.5  797.52    4777  798.45  4812.2  795.33  4875.9   793.6
    4906  788.71  4924.1  788.68  4966.1   788.7  4983.9  786.44  4984.3  785.94
  4989.1  786.44  4996.2  788.42  5016.3  790.43  5026.3  794.44  5056.4  799.14
  5066.4  799.36  5088.6  796.79  5236.9     801    5287  804.66  5400.2  806.98
  5477.6  807.23  5497.6   809.4  5519.7   807.6    5638  809.11  5694.1  812.15
#Mann= 8 ,-1 , 0
  4354.6     .12       0    4580    .035       0  4716.5    .063       0
  4924.1    .035       0  4983.9    .035       0  4989.1    .035       0
  5088.6    .063       0  5400.2    .035       0
Bank Sta=4983.9,4989.1
XS Rating Curve= 0 ,0
Exp/Cntr=0.3,0.1