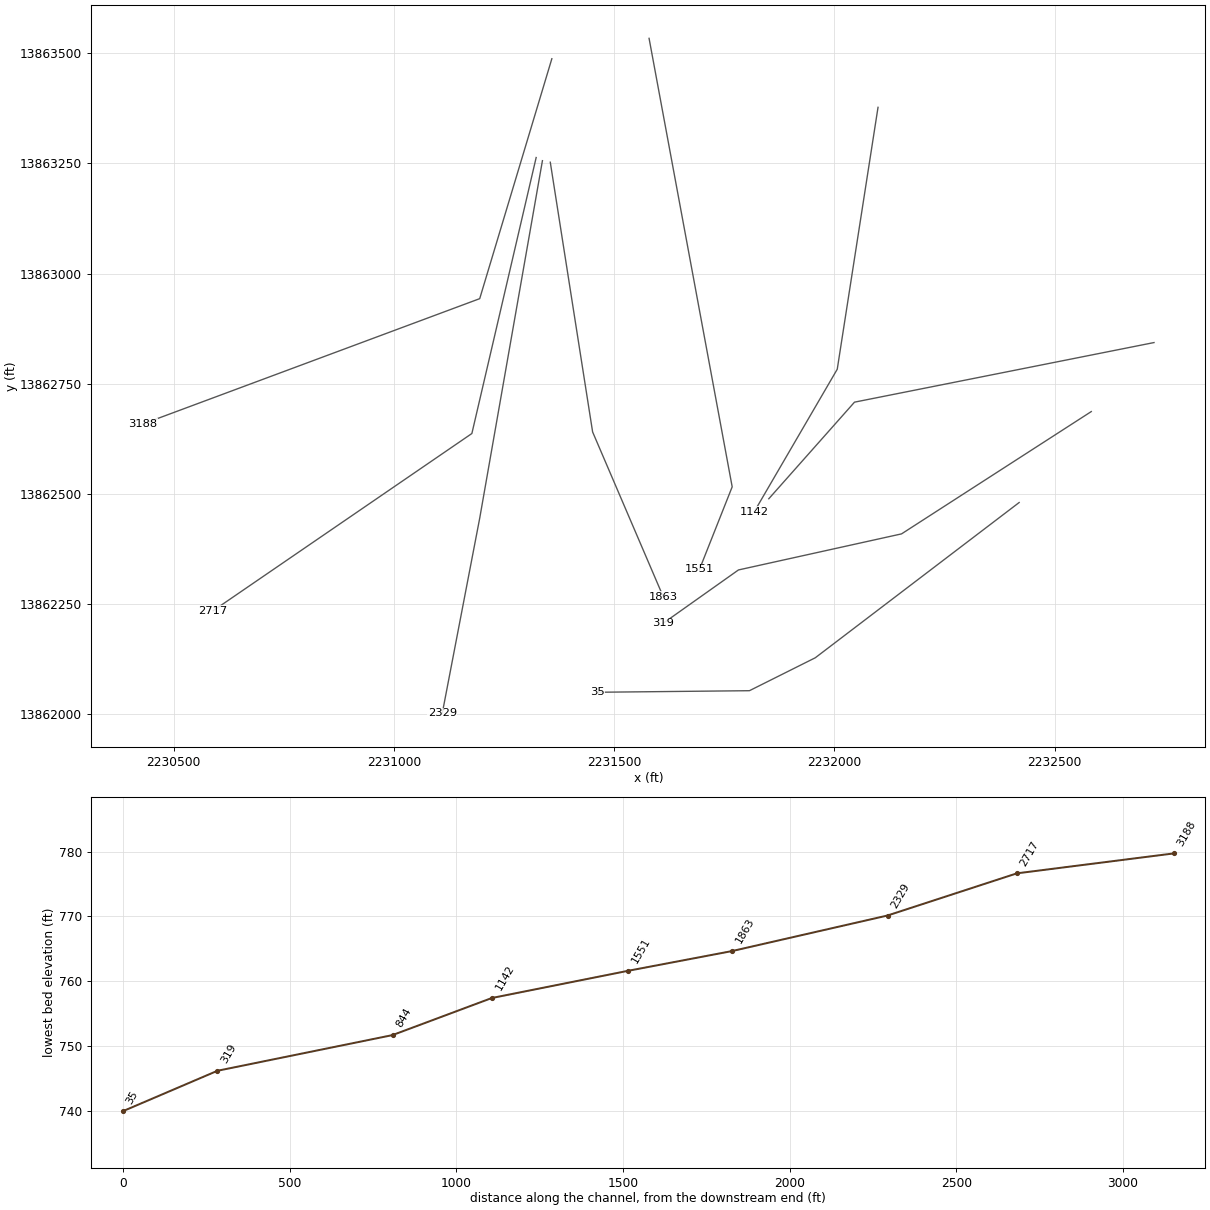
HEC-RAS study Guadalupe Tributary 29.prj: Guadalupe Tributary 29 Base Level Engineering

--- Guadalupe Tributary 29.g01 (geometry) --- (continued)

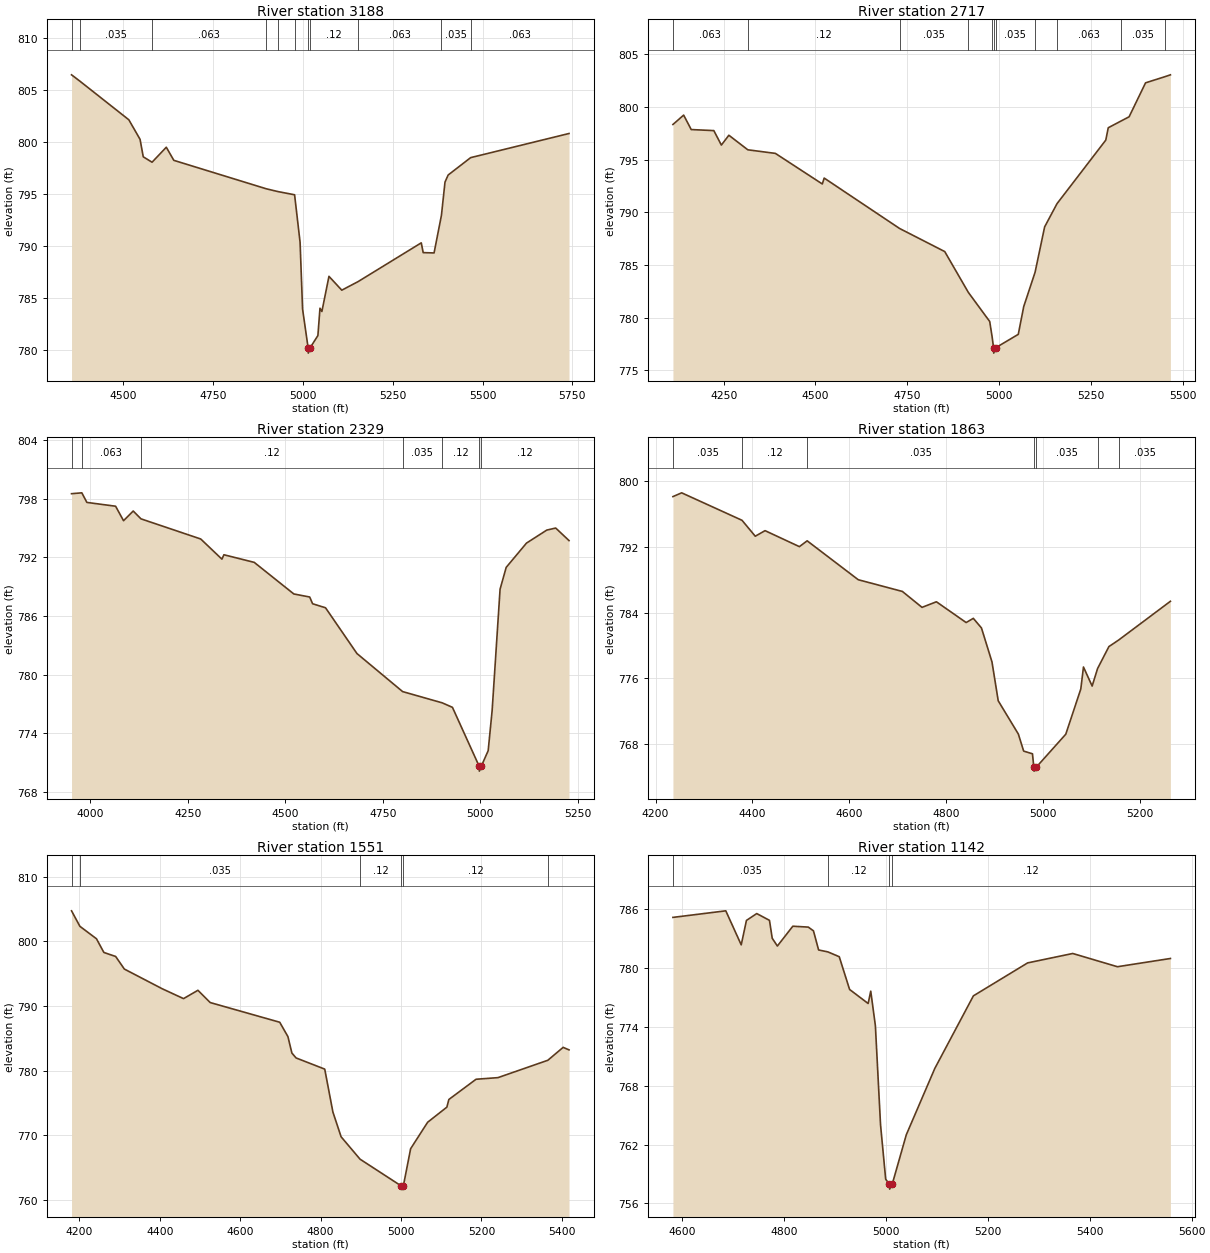
Type RM Length L Ch R = 1 ,3188    ,471,471,471
BEGIN DESCRIPTION:
A19314
END DESCRIPTION:
XS GIS Cut Line= 3
      2231358.57     13863487.76       2231194.8     13862943.05
      2230429.65     13862658.34
#Sta/Elev= 30
  4355.6  806.46  4377.8  805.88  4515.1  802.14  4546.4  800.26  4555.3  798.58
  4579.8  798.06  4619.5   799.5  4640.4  798.24  4897.4  795.51    4930  795.24
  4976.7  794.93    4992  790.36  4998.9  783.95  5014.4  780.21  5014.8  779.71
  5019.7  780.21  5041.6   781.4  5047.4  784.03  5052.7  783.71  5072.4  787.09
  5108.1  785.76  5153.8  786.59  5329.4  790.31  5334.8  789.37  5365.1  789.34
  5385.6  792.96  5395.5  796.15  5404.3  796.83  5466.9   798.5  5740.8  800.82
#Mann= 11 ,-1 , 0
  4355.6     .12       0  4377.8    .035       0  4579.8    .063       0
  4897.4     .12       0    4930    .063       0  4976.7     .12       0
  5014.4     .05       0  5019.7     .12       0  5153.8    .063       0
  5385.6    .035       0  5466.9    .063       0
Bank Sta=5014.4,5019.7
XS Rating Curve= 0 ,0
Exp/Cntr=0.3,0.1

Type RM Length L Ch R = 1 ,2717    ,388,388,388
BEGIN DESCRIPTION:
A19313
END DESCRIPTION:
XS GIS Cut Line= 3
      2231322.96     13863263.46      2231176.99     13862636.88
      2230589.77     13862234.71
#Sta/Elev= 30
  4111.8  798.32    4141  799.21  4161.6  797.84  4223.2  797.74  4243.7  796.37
  4264.2   797.3  4315.8  795.92  4390.9  795.58  4518.7  792.68  4523.8  793.24
  4729.2  788.46  4852.2  786.27  4916.3  782.41  4974.7  779.64  4981.3  778.18
  4985.2  777.14  4985.6  776.64  4990.5  777.14  5052.5  778.42  5067.4  781.06
  5098.3  784.31  5124.3  788.61    5158  790.81  5290.9  796.84  5297.6  798.01
  5332.4  798.65  5354.4  799.05  5399.2  802.27  5453.5  802.87  5466.9  803.03
#Mann= 11 ,-1 , 0
  4111.8    .063       0  4315.8     .12       0  4729.2    .035       0
  4916.3    .063       0  4981.3    .035       0  4985.2    .035       0
  4990.5    .035       0  5098.3     .12       0    5158    .063       0
  5332.4    .035       0  5453.5     .12       0
Bank Sta=4985.2,4990.5
XS Rating Curve= 0 ,0
Exp/Cntr=0.3,0.1

Type RM Length L Ch R = 1 ,2329    ,466,466,466
BEGIN DESCRIPTION:
A19312
END DESCRIPTION:
XS GIS Cut Line= 3
       2231337.2     13863256.33       2231194.8     13862444.63
      2231109.72     13862001.52
#Sta/Elev= 30
  3951.9  798.51  3978.3   798.6  3991.2  797.62  4064.9  797.23  4085.2  795.75
    4110  796.74  4129.9  795.94  4283.1  793.88  4337.4  791.82  4342.5  792.27
  4420.3  791.49  4521.8  788.26  4562.4  787.95  4569.9  787.26    4603  786.85
  4683.6  782.17  4800.7  778.28  4902.2  777.13  4928.4  776.67  4996.9  770.65
  4997.4  770.15  5002.3  770.65    5020  772.24  5030.2  776.37  5050.5  788.75
  5066.2  790.98  5118.2  793.46  5170.2  794.79  5193.1     795  5227.2  793.72
#Mann= 7 ,-1 , 0
  3951.9    .035       0  3978.3    .063       0  4129.9     .12       0
  4800.7    .035       0  4902.2     .12       0  4996.9     .05       0
  5002.3     .12       0
Bank Sta=4996.9,5002.3
XS Rating Curve= 0 ,0
Exp/Cntr=0.3,0.1

Type RM Length L Ch R = 1 ,1863    ,312,312,312
BEGIN DESCRIPTION:
A19311
END DESCRIPTION:
XS GIS Cut Line= 3
        2231355.     13863252.81      2231451.13     13862640.44
      2231611.35     13862266.59
#Sta/Elev= 30
  4235.9  798.14  4253.9   798.6  4378.5  795.25  4405.8  793.31    4426  793.99
  4496.9  792.04  4512.9  792.75  4618.3  788.01  4709.4  786.58  4749.9  784.64
  4779.6  785.32    4841  782.79  4855.8   783.3  4872.6  782.13  4894.3  777.99
  4907.2  773.25  4948.7   769.2  4959.7  767.12  4977.9  766.79  4980.6  765.18
  4981.1  764.68    4986  765.18  5046.6  769.18  5077.6  774.69  5083.1  777.37
    5101  775.05  5112.2  777.18  5135.6  779.86    5156  780.67  5262.5  785.38
#Mann= 7 ,-1 , 0
  4235.9    .035       0  4378.5     .12       0  4512.9    .035       0
  4980.6    .035       0    4986    .035       0  5112.2     .12       0
    5156    .035       0
Bank Sta=4980.6,4986
XS Rating Curve= 0 ,0
Exp/Cntr=0.3,0.1

Type RM Length L Ch R = 1 ,1551    ,409,409,409
BEGIN DESCRIPTION:
A19310
END DESCRIPTION:
XS GIS Cut Line= 3
      2231579.29     13863534.05      2231767.98     13862515.83
      2231693.77     13862328.55
#Sta/Elev= 30
  4180.8  804.75  4201.6  802.35  4242.8  800.42  4261.2   798.3  4290.5  797.68
  4312.1  795.73  4406.5  792.67  4459.3  791.15  4495.1  792.44  4525.6  790.54
  4698.5  787.49  4718.9  785.26  4728.7  782.72  4739.2  781.96  4810.4  780.23
  4830.7  773.58  4851.1  769.75  4898.2  766.28  5000.5  762.14    5001  761.64
  5005.9  762.14    5024   767.9  5066.3     772  5114.1  774.34  5119.1  775.53
  5186.7  778.66  5241.1  778.91  5365.2   781.6  5403.2   783.6  5417.8  783.21
#Mann= 6 ,-1 , 0
  4180.8     .12       0  4201.6    .035       0  4898.2     .12       0
  5000.5     .05       0  5005.9     .12       0  5365.2    .035       0
Bank Sta=5000.5,5005.9
XS Rating Curve= 0 ,0
Exp/Cntr=0.3,0.1

Type RM Length L Ch R = 1 ,1142    ,298,298,298
BEGIN DESCRIPTION:
A19309
END DESCRIPTION:
XS GIS Cut Line= 3
      2232099.08     13863377.44      2232006.51     13862782.84
      2231818.16     13862459.45
#Sta/Elev= 30
  4582.3  785.16    4686  785.83  4716.3  782.36  4726.5  784.85  4746.7  785.55
  4771.7  784.86  4777.1  783.03  4787.2  782.24  4817.5  784.26  4847.9  784.17
    4858  783.79  4868.1  781.84  4886.4  781.64  4908.6  781.15  4928.9  777.81
  4965.3  776.38  4970.4  777.64  4979.5  774.11  4989.6  764.02  4999.7  758.46
  5007.1  757.95  5007.5  757.45  5012.5  757.95  5040.2     763  5096.1  769.76
  5171.8  777.16  5278.2  780.52  5366.7  781.48  5454.4  780.13  5558.3  780.97
#Mann= 4 ,-1 , 0
  4582.3    .035       0  4886.4     .12       0  5007.1     .05       0
  5012.5     .12       0
Bank Sta=5007.1,5012.5
XS Rating Curve= 0 ,0
Exp/Cntr=0.3,0.1

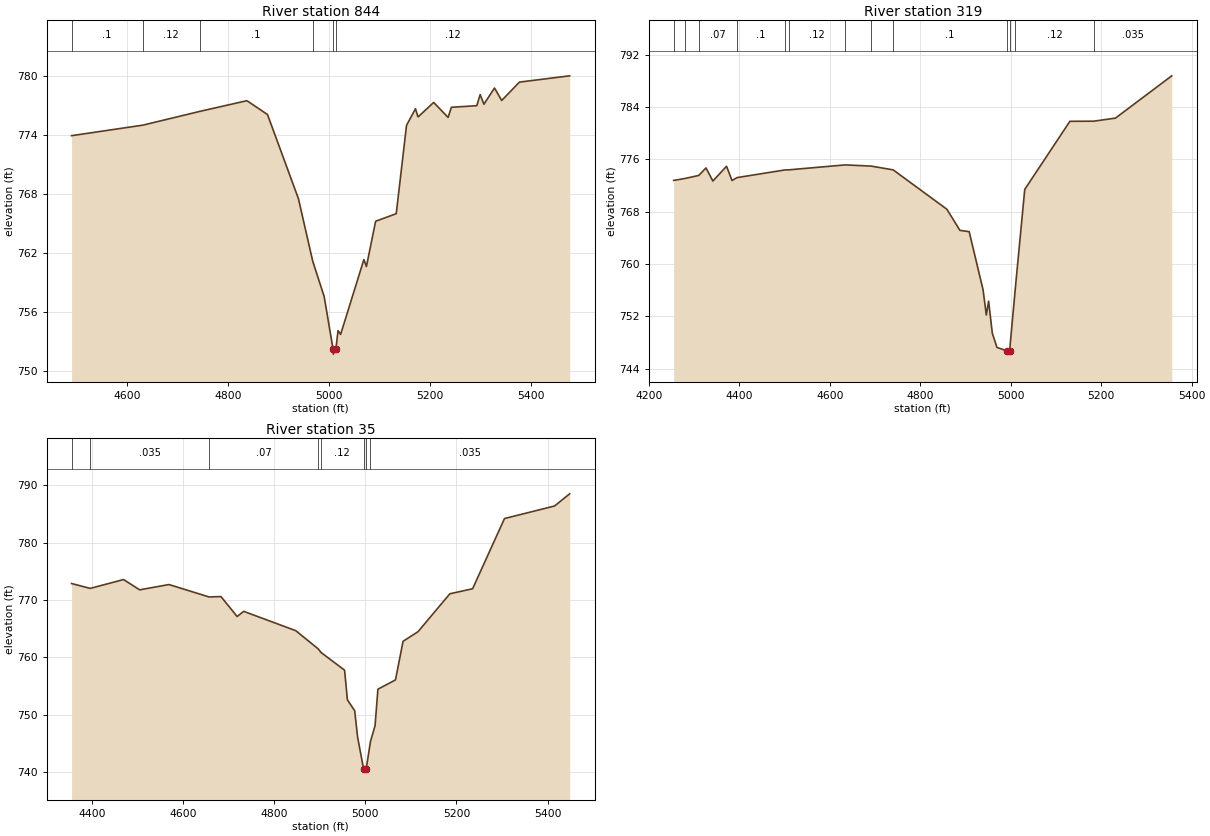
Type RM Length L Ch R = 1 ,844     ,525,525,525
BEGIN DESCRIPTION:
A19308
END DESCRIPTION:
XS GIS Cut Line= 3
      2232725.67     13862843.37      2232045.67     13862708.08
      2231851.12     13862488.76
#Sta/Elev= 30
  4490.2  773.97  4631.3  775.04  4744.1  776.44  4837.5  777.53  4878.3  776.12
  4939.5  767.56  4967.8   761.2  4990.5   757.6  5008.1  752.24  5008.6  751.74
  5013.6  752.24    5018  754.14  5023.1  753.75  5069.1  761.36  5074.2  760.66
  5092.4  765.26  5133.2  766.03  5153.6  775.02  5171.3  776.71  5176.4  775.88
  5207.4  777.35  5235.9  775.83  5242.5  776.86  5292.7  777.02  5299.4  778.15
  5306.9  777.17  5327.8  778.82  5342.1  777.55  5377.2  779.42  5476.7  780.06
#Mann= 6 ,-1 , 0
  4490.2      .1       0  4631.3     .12       0  4744.1      .1       0
  4967.8     .12       0  5008.1     .05       0  5013.6     .12       0
Bank Sta=5008.1,5013.6
XS Rating Curve= 0 ,0
Exp/Cntr=0.3,0.1

Type RM Length L Ch R = 1 ,319     ,284,284,284
BEGIN DESCRIPTION:
A19307
END DESCRIPTION:
XS GIS Cut Line= 4
      2232583.26     13862686.73      2232152.47     13862409.03
      2231782.22     13862327.14       2231611.3     13862206.07
#Sta/Elev= 30
  4254.8  772.79    4280  773.09  4310.3  773.55  4326.3   774.7  4341.5   772.7
  4371.7  774.95  4383.8  772.78    4395  773.22  4500.8  774.39    4510  774.41
  4633.9  775.16  4691.2  774.98  4740.1   774.4  4858.8  768.39  4887.7  765.16
  4908.1  764.96  4938.9  756.06    4946  752.23  4951.1  754.35  4959.3  749.44
  4969.6  747.27    4992  746.75  4992.5  746.25  4997.5  746.75  5010.5  756.55
    5031  771.42  5130.8  781.82  5183.7  781.84  5231.6  782.31    5356  788.77
#Mann= 13 ,-1 , 0
  4254.8     .12       0    4280      .1       0  4310.3     .07       0
    4395      .1       0  4500.8     .07       0    4510     .12       0
  4633.9      .1       0  4691.2    .035       0  4740.1      .1       0
    4992     .05       0  4997.5      .1       0  5010.5     .12       0
  5183.7    .035       0
Bank Sta=4992,4997.5
XS Rating Curve= 0 ,0
Exp/Cntr=0.3,0.1

Type RM Length L Ch R = 1 ,35      ,0,0,0
BEGIN DESCRIPTION:
A19306
END DESCRIPTION:
XS GIS Cut Line= 4
      2232419.48     13862480.23      2231956.67     13862127.78
      2231807.14     13862053.01      2231461.78     13862049.45
#Sta/Elev= 30
  4354.4  772.89  4395.4  772.04  4468.6  773.58    4504  771.79  4568.4  772.71
  4656.4  770.55  4682.7  770.61  4718.1  767.14  4732.6  768.04    4847  764.67
  4896.4  761.49  4902.5  760.87  4954.2  757.79  4960.4  752.62  4976.5   750.7
  4982.7  746.17  4996.1  740.52  4996.6  740.02  5001.6  740.52    5011  745.34
  5021.2  748.13  5027.4  754.47    5066  756.09  5082.7  762.82  5115.5  764.49
  5185.5   771.1  5235.5  771.98  5305.5  784.21  5415.5   786.4  5448.7  788.52
#Mann= 8 ,-1 , 0
  4354.4     .07       0  4395.4    .035       0  4656.4     .07       0
  4896.4      .1       0  4902.5     .12       0  4996.1     .05       0
  5001.6     .12       0    5011    .035       0
Bank Sta=4996.1,5001.6
XS Rating Curve= 0 ,0
Exp/Cntr=0.3,0.1

Chan Stop Cuts=-1
Use User Specified Reach Order=0
Composite Channel Slope=5