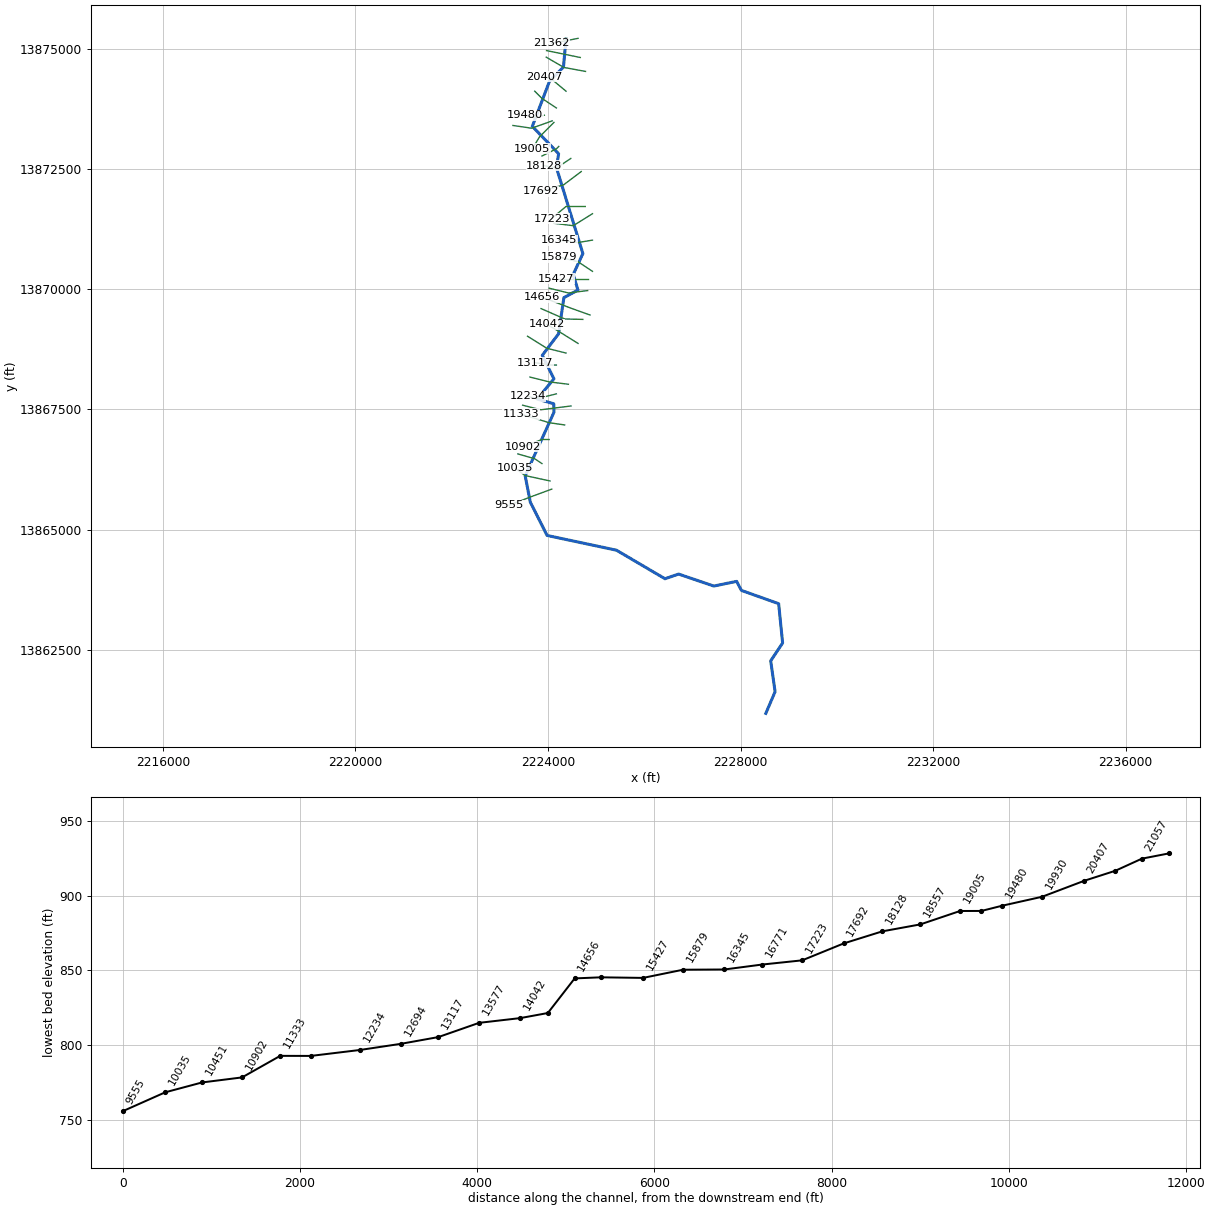
--- Guadalupe Tributary 32.prj (project) ---

Proj Title=Guadalupe Tributary 32 Base Level Engineering
Current Plan=p01
Default Exp/Contr=0.3,0.1
English Units
Geom File=g01
Flow File=f01
Plan File=p01
Y Axis Title=Elevation
X Axis Title(PF)=Main Channel Distance
X Axis Title(XS)=Station
BEGIN DESCRIPTION:
Guadalupe Tributary 32
END DESCRIPTION:
DSS Export Rating Curves= 0
DSS Export Rating Curve Sorted= 0
DSS Export Volume Flow Curves= 0
DXF OffsetX= 0
DXF OffsetY= 0
DXF ScaleX= 1
DXF ScaleY= 10

--- Guadalupe Tributary 32.p01 (plan) ---

Plan Title=Multiple Run
Short Identifier=Multiple
Geom File=g01
Flow File=f01
Subcritical Flow
K Sum by GR= 0
Std Step Tol= 0.01
Critical Tol= 0.01
Num of Std Step Trials= 20
Max Error Tol= 0.3
Flow Tol Ratio= 0.001
Split Flow NTrial= 30
Split Flow Tol= 0.02
Split Flow Ratio= 0.02
Log Output Level= 0
Friction Slope Method= 1
Unsteady Friction Slope Method= 2
Unsteady Bridges Friction Slope Method= 1
Parabolic Critical Depth
Global Vel Dist=  1 , 1 , 1
Global Log Level= 0
CheckData=True
Encroach Param= -1, 0, 0, 0
BEGIN DESCRIPTION:
Multiple Run
END DESCRIPTION:

--- Guadalupe Tributary 32.f01 (steady flow) ---

Flow Title=Multiple
Number of Profiles=7
Profile Names=10-year,25-year,50-year,1pct_min,100-year,1pct_plu,500-year
River Rch & RM= Guadalupe Tribut,Reach-1,21362
    1044    1764    2447    1646    3284    6553    5850
River Rch & RM= Guadalupe Tribut,Reach-1,17223
    1629    2806    3943    2681    5349   10673    9741
River Rch & RM= Guadalupe Tribut,Reach-1,10902
    2250    3938    5592    3837    7656   15276   14211
River Rch & RM= Guadalupe Tribut,Reach-1,6494
    2784    4927    7049    4870    9717   19388   18285
Boundary for River Rch & Prof#=Guadalupe Tribut,Reach-1,1
Up Type=0
Dn Type=3
Dn Slope=0.005
Boundary for River Rch & Prof#=Guadalupe Tribut,Reach-1,2
Up Type=0
Dn Type=3
Dn Slope=0.005
Boundary for River Rch & Prof#=Guadalupe Tribut,Reach-1,3
Up Type=0
Dn Type=3
Dn Slope=0.005
Boundary for River Rch & Prof#=Guadalupe Tribut,Reach-1,4
Up Type=0
Dn Type=3
Dn Slope=0.005
Boundary for River Rch & Prof#=Guadalupe Tribut,Reach-1,5
Up Type=0
Dn Type=3
Dn Slope=0.005
Boundary for River Rch & Prof#=Guadalupe Tribut,Reach-1,6
Up Type=0
Dn Type=3
Dn Slope=0.005
Boundary for River Rch & Prof#=Guadalupe Tribut,Reach-1,7
Up Type=0
Dn Type=3
Dn Slope=0.005

--- Guadalupe Tributary 32.g01 (geometry) ---

Geom Title=Existing Conditions
Program Version=4.10

River Reach=Guadalupe Tribut,Reach-1
Reach XY= 30
        2224375.     13875210.79      2224321.87     13874626.63
      2224030.47     13874327.45      2223675.07     13873393.23
      2224221.25     13872823.45       2224176.8     13872531.11
       2224725.3     13870745.18      2224525.02     13870310.62
       2224623.3      13869985.8      2224330.52     13869827.43
      2224221.47     13869076.45       2223882.6     13868628.33
      2224124.52     13868138.73      2223776.52     13867717.23
      2224120.37     13867619.83      2224125.11     13867443.46
      2223527.14     13866119.03      2223633.24     13865571.77
      2223982.54     13864878.06      2225423.42     13864571.17
      2226430.93     13863977.23      2226714.36     13864074.44
      2227445.21     13863824.79      2227919.95     13863922.83
      2228018.23     13863734.15      2228792.15     13863458.55
      2228874.49     13862640.21      2228626.97     13862269.11
      2228717.89       13861625.        2228525.       13861175.

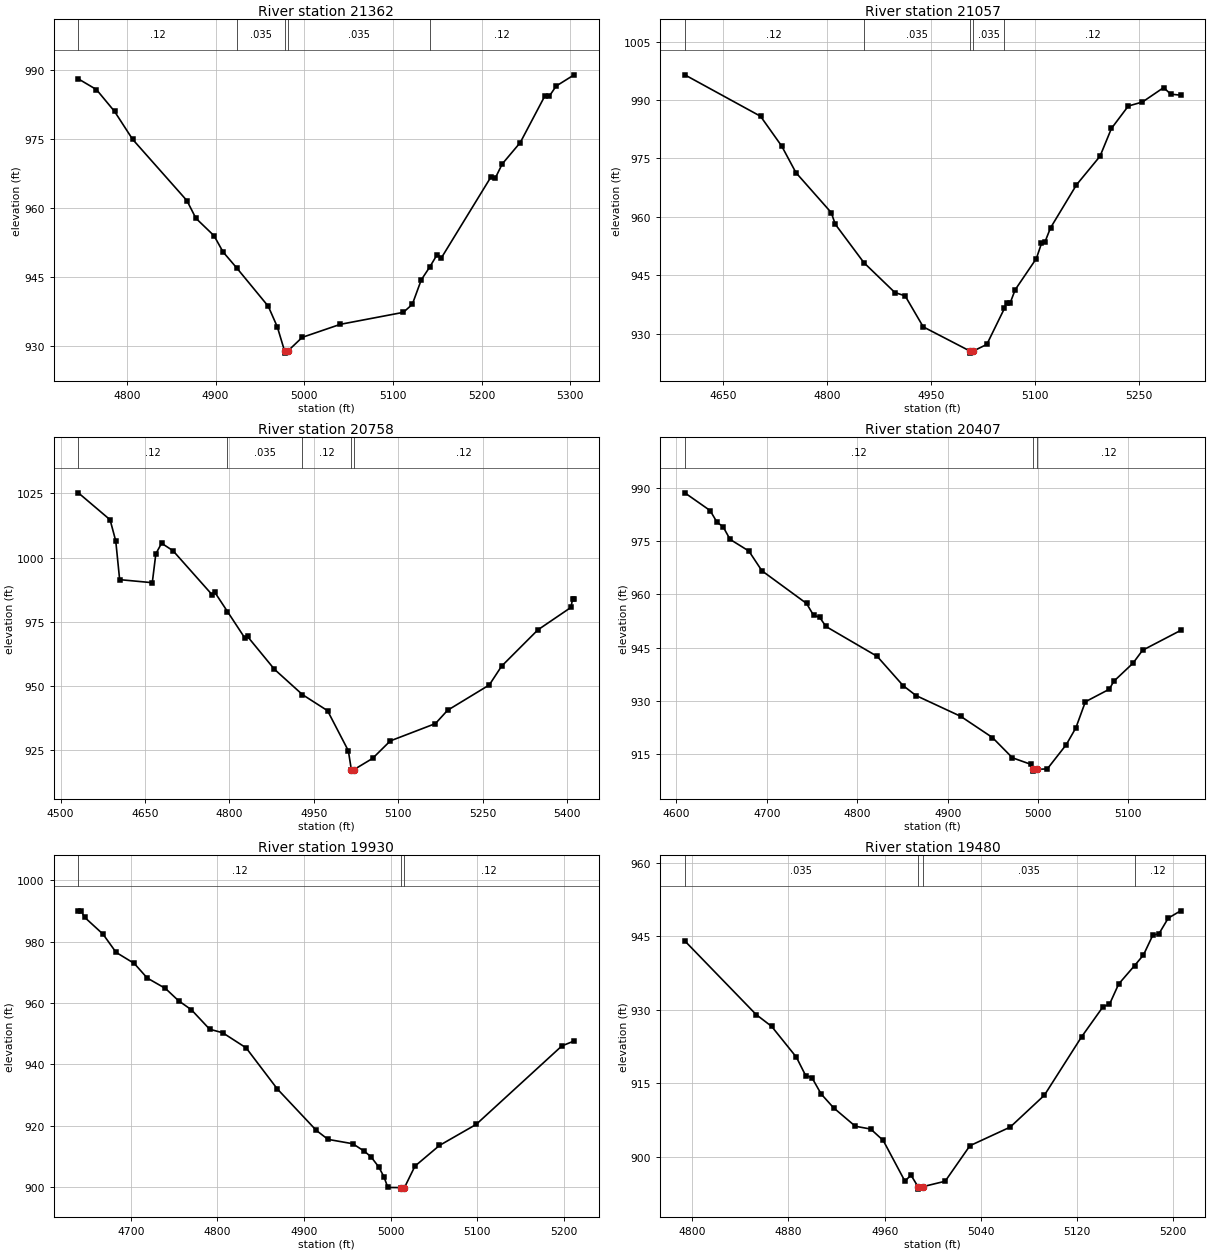
Type RM Length L Ch R = 1 ,21362   ,305,305,305
BEGIN DESCRIPTION:
Guadalupe Tributary 32 46.0
END DESCRIPTION:
XS GIS Cut Line= 3
      2224624.99       13875225.        2224375.       13875175.
      2224074.98       13875125.
#Sta/Elev= 30
  4745.2  988.09  4765.6  985.77    4786  981.03  4806.4  974.96  4867.6  961.65
  4877.8   957.8  4898.2  954.02  4908.4  950.49  4923.7  947.04  4959.4  938.68
  4969.6   934.2  4977.7  929.01    4978  928.51  4981.7  929.01  4997.6  931.93
  5040.7  934.77  5111.7  937.37  5121.8  939.11  5131.9  944.43  5141.4   947.2
  5149.7  949.88  5154.7  949.24  5210.5  966.79  5215.6  966.63  5223.2  969.61
  5243.5  974.25  5271.3   984.4  5276.4  984.36    5284  986.53  5304.3  988.97
#Mann= 5 ,-1 , 0
  4745.2     .12       0  4923.7    .035       0  4977.7    .035       0
  4981.7    .035       0  5141.4     .12       0
Bank Sta=4977.7,4981.7
XS Rating Curve= 0 ,0
Exp/Cntr=0.3,0.1

Type RM Length L Ch R = 1 ,21057   ,299,299,299
BEGIN DESCRIPTION:
A19344
END DESCRIPTION:
XS GIS Cut Line= 2
       2224672.1     13874826.37      2223971.01     13874969.78
#Sta/Elev= 30
  4594.4  996.46  4703.7  985.82  4734.3  978.15  4754.8  971.34  4805.8  961.07
  4811.5  958.11  4852.9  948.22  4897.6  940.55  4912.4   939.7  4938.5  931.74
  5006.3  925.49  5006.5  924.99  5010.3  925.49  5030.3  927.23  5055.8  936.51
  5058.7  937.99  5063.8  937.78  5071.2  941.26  5101.8  949.29  5109.2  953.17
  5114.3  953.58  5122.2  957.15  5159.7  968.21  5193.7  975.56  5210.1  982.68
  5234.5  988.45  5254.9  989.48  5285.5  993.18  5295.7   991.5    5310  991.23
#Mann= 5 ,-1 , 0
  4594.4     .12       0  4852.9    .035       0  5006.3    .035       0
  5010.3    .035       0  5055.8     .12       0
Bank Sta=5006.3,5010.3
XS Rating Curve= 0 ,0
Exp/Cntr=0.3,0.1

Type RM Length L Ch R = 1 ,20758   ,351,351,351
BEGIN DESCRIPTION:
Guadalupe Tributary 32 45.0
END DESCRIPTION:
XS GIS Cut Line= 3
      2224780.45     13874536.39      2224331.11     13874619.24
      2223964.68     13874832.73
#Sta/Elev= 30
  4531.5 1025.17  4587.9 1014.69    4598 1006.42  4604.9  991.39  4662.9   990.2
  4669.2 1001.43  4679.4 1005.55  4699.7 1002.65  4768.9  985.59    4774  986.46
  4796.5  978.97    4827  968.79  4832.1  969.27    4880  956.49  4929.8  946.64
  4974.3   940.4  5011.3  924.79  5016.6  917.38  5016.9  916.88  5020.6  917.38
  5054.3  921.83  5085.8  928.64    5166  935.38  5187.5  940.54  5261.7  950.41
  5283.5   957.7    5348  971.84  5406.7  980.57  5409.8  983.92  5412.5  983.92
#Mann= 5 ,-1 , 0
  4531.5     .12       0  4796.5    .035       0  4929.8     .12       0
  5016.6     .05       0  5020.6     .12       0
Bank Sta=5016.6,5020.6
XS Rating Curve= 0 ,0
Exp/Cntr=0.3,0.1

Type RM Length L Ch R = 1 ,20407   ,477,477,477
BEGIN DESCRIPTION:
Guadalupe Tributary 32 44.0
END DESCRIPTION:
XS GIS Cut Line= 3
        2224375.       13874125.        2224075.       13874375.
      2223925.03     13874424.99
#Sta/Elev= 30
  4609.2  988.65  4637.2  983.65    4645  980.29  4651.5  979.11  4659.3  975.52
  4680.1  972.23  4694.5  966.67  4743.9  957.45  4751.7  954.09  4758.3  953.58
  4765.4  950.95    4822  942.54  4850.7  934.29    4865  931.48  4914.5  925.61
  4949.6  919.63  4971.7  913.92  4992.6  912.03  4994.5  910.66  4994.7  910.16
  4998.5  910.66  5010.3  910.79  5031.3  917.64  5041.9  922.37  5052.4  929.72
  5078.8  933.25    5084  935.53  5105.1   940.6  5115.7  944.25  5157.8  949.84
#Mann= 3 ,-1 , 0
  4609.2     .12       0  4994.5     .05       0  4998.5     .12       0
Bank Sta=4994.5,4998.5
XS Rating Curve= 0 ,0
Exp/Cntr=0.3,0.1

Type RM Length L Ch R = 1 ,19930   ,450,450,450
BEGIN DESCRIPTION:
Guadalupe Tributary 32 43.0
END DESCRIPTION:
XS GIS Cut Line= 3
      2224174.99     13873775.01        2223875.       13873975.
      2223724.98     13874125.02
#Sta/Elev= 30
  4639.4     990  4642.4     990  4646.9  987.83  4667.9  982.41    4683  976.48
    4704  972.87    4719  968.12    4740  964.74  4755.1  960.75  4770.1  957.77
  4791.1  951.46  4806.1  950.32  4833.2   945.4  4869.2  932.04  4914.3  918.53
  4927.8  915.61  4956.4  914.19  4969.9  911.72  4977.4  909.95  4986.4  906.64
  4992.4  903.42  4996.9  899.96  5012.1  899.92  5012.3  899.42  5016.1  899.92
  5028.2   906.9  5056.5  913.63  5098.9  920.48  5197.9  946.03  5212.1  947.64
#Mann= 3 ,-1 , 0
  4639.4     .12       0  5012.1     .05       0  5016.1     .12       0
Bank Sta=5012.1,5016.1
XS Rating Curve= 0 ,0
Exp/Cntr=0.3,0.1

Type RM Length L Ch R = 1 ,19480   ,234,234,234
BEGIN DESCRIPTION:
Guadalupe Tributary 32 42.0
END DESCRIPTION:
XS GIS Cut Line= 3
      2223925.03     13873625.01        2223725.       13873575.
      2223525.04     13873624.99
#Sta/Elev= 30
  4793.8  944.08  4853.1  929.06    4866  926.64  4886.6  920.35  4894.3   916.6
  4899.5  916.18  4907.2  912.84  4917.5  910.03  4935.6  906.26  4948.4  905.69
  4958.8  903.36  4976.8  895.07  4981.9  896.28  4987.7  893.93  4987.9  893.43
  4991.7  893.93  5010.3  895.04  5030.9  902.29  5064.4  906.09  5092.8  912.59
  5123.7  924.49  5141.7  930.69  5146.9  931.12  5154.6  935.29  5167.8  939.04
  5175.2  941.21  5182.9  945.22  5188.1  945.55  5195.8  948.73  5206.1  950.22
#Mann= 4 ,-1 , 0
  4793.8    .035       0  4987.7    .035       0  4991.7    .035       0
  5167.8     .12       0
Bank Sta=4987.7,4991.7
XS Rating Curve= 0 ,0
Exp/Cntr=0.3,0.1

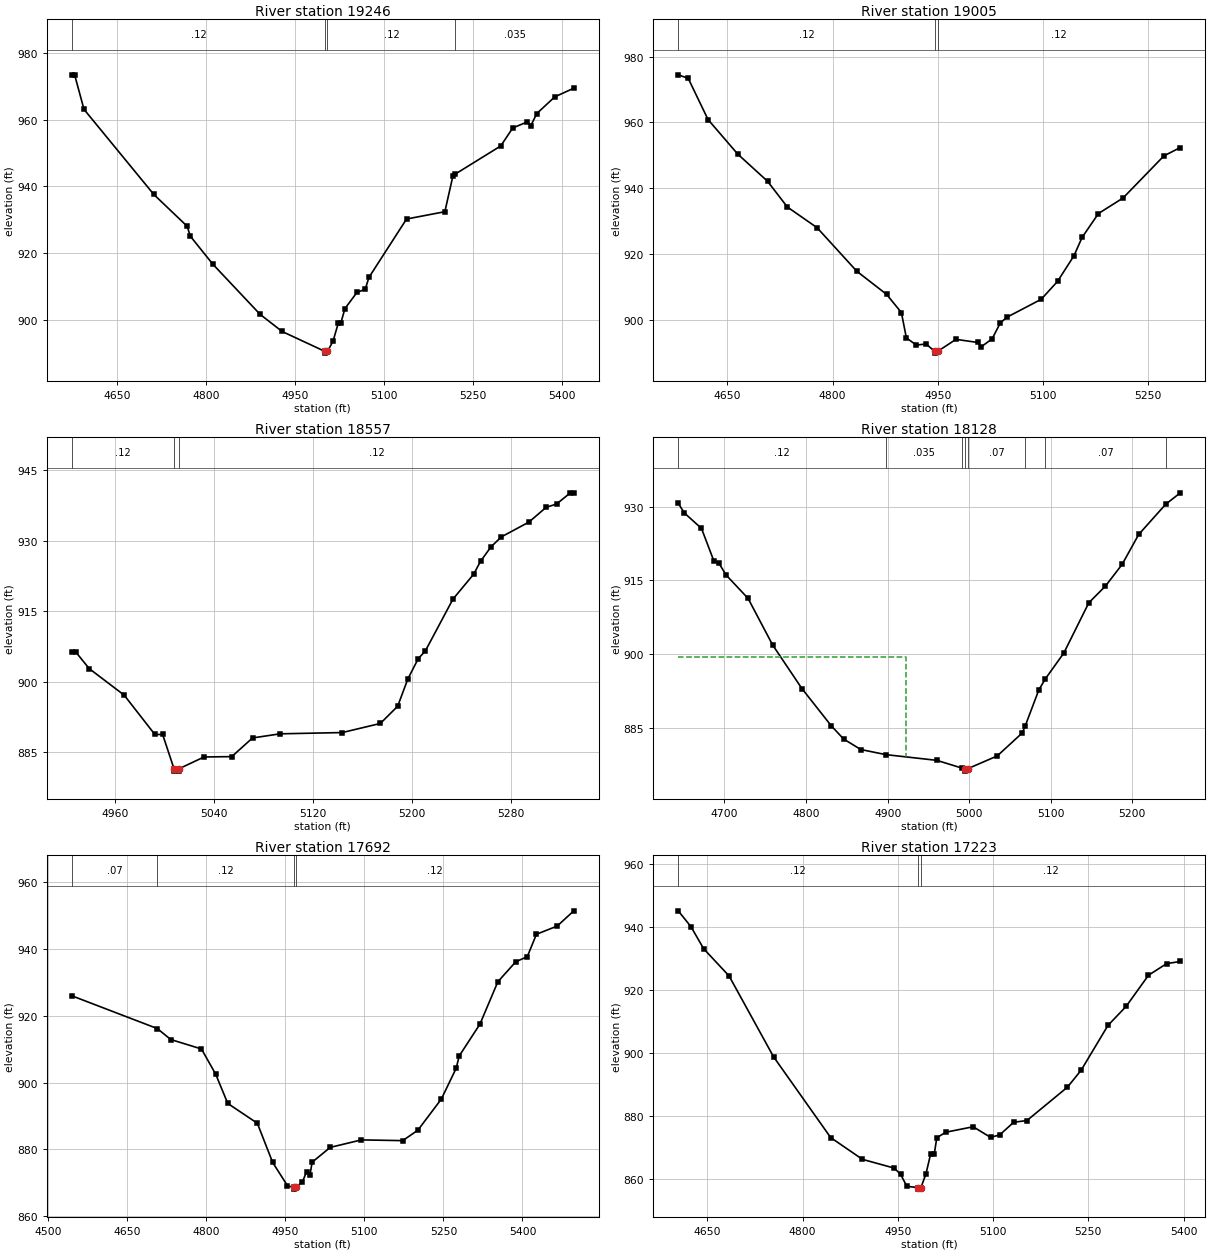
Type RM Length L Ch R = 1 ,19246   ,241,241,241
BEGIN DESCRIPTION:
A19345
END DESCRIPTION:
XS GIS Cut Line= 3
      2224088.96     13873507.12      2223661.92     13873354.15
      2223273.14     13873411.51
#Sta/Elev= 30
  4573.2  973.54    4578  973.54  4593.8  963.17  4711.6  937.59  4767.8  928.04
  4773.1  925.06  4811.1  916.64  4890.8  901.57  4927.9  896.43  5000.3  890.43
  5000.5  889.93  5004.3  890.43  5013.8  893.54  5022.5   898.9  5026.8   898.9
  5033.8  903.31    5054  908.15  5068.1  909.13  5074.2  912.66  5137.7  930.22
  5202.3  932.42  5215.8   943.1  5220.1  943.75  5296.6  952.18  5316.8  957.59
  5341.5   959.4  5347.2  958.24  5357.3   961.9  5387.6  966.92  5419.8  969.53
#Mann= 4 ,-1 , 0
  4573.2     .12       0  5000.3     .05       0  5004.3     .12       0
  5220.1    .035       0
Bank Sta=5000.3,5004.3
XS Rating Curve= 0 ,0
Exp/Cntr=0.3,0.1

Type RM Length L Ch R = 1 ,19005   ,448,448,448
BEGIN DESCRIPTION:
Guadalupe Tributary 32 41.0
END DESCRIPTION:
XS GIS Cut Line= 3
      2224125.03     13873475.03        2223825.       13873175.
      2223674.98     13872924.96
#Sta/Elev= 30
  4579.9  974.49  4594.1  973.43  4622.4  960.89  4664.8  950.38  4707.2  942.15
  4735.5  934.31  4777.9  928.02  4834.5  914.79  4876.9  907.78  4898.1  902.23
  4905.2  894.53  4919.4  892.35  4933.5  892.68  4945.6   890.4  4945.9   889.9
  4949.6   890.4  4975.9  894.09  5007.1  893.14    5012  891.83  5027.5  894.25
  5039.2  899.11  5048.9  900.85  5097.5  906.27  5120.8  911.72  5144.1  919.48
  5155.8  925.09  5179.1  932.34  5214.1  937.04  5272.4  949.85  5295.8  952.39
#Mann= 3 ,-1 , 0
  4579.9     .12       0  4945.6     .05       0  4949.6     .12       0
Bank Sta=4945.6,4949.6
XS Rating Curve= 0 ,0
Exp/Cntr=0.3,0.1

Type RM Length L Ch R = 1 ,18557   ,429,429,429
BEGIN DESCRIPTION:
Guadalupe Tributary 32 40.0
END DESCRIPTION:
XS GIS Cut Line= 3
      2224224.99     13872974.99        2224175.       13872925.
      2223875.01       13872775.
#Sta/Elev= 30
    4925  906.21  4928.5  906.21  4939.1  902.76  4967.4   897.1  4992.2  888.72
  4998.5  888.72  5007.7  881.41  5007.9  880.91  5011.4  880.91  5011.7  881.41
    5032  883.93  5054.4     884  5071.2  887.98  5093.5  888.86  5143.8  889.13
  5174.6  891.07  5188.6  894.74  5196.9   900.6  5205.3   904.9  5210.9  906.48
  5233.3  917.56  5250.1  922.89  5255.6  925.62    5264  928.68  5272.4  930.82
  5294.8  933.99  5308.7  937.13  5317.1  937.83  5328.3  940.22  5331.1  940.22
#Mann= 3 ,-1 , 0
    4925     .12       0  5007.7     .05       0  5011.7     .12       0
Bank Sta=5007.7,5011.7
XS Rating Curve= 0 ,0
Exp/Cntr=0.3,0.1

Type RM Length L Ch R = 1 ,18128   ,436,436,436
BEGIN DESCRIPTION:
Guadalupe Tributary 32 39.0
END DESCRIPTION:
XS GIS Cut Line= 3
      2224474.99     13872724.99        2224175.       13872525.
      2223924.99       13872575.
#Sta/Elev= 30
  4643.3  930.67  4650.8  928.71  4671.8  925.57  4686.9  918.99  4692.9  918.58
  4701.9  916.11  4728.9  911.35    4759  901.89    4795  893.01  4831.1  885.42
  4846.1  882.77  4867.1  880.64  4897.9   879.6  4960.3  878.44  4990.6  876.89
  4994.3  876.75  4994.6  876.25  4998.3  876.75  5034.4  879.34    5065     884
  5068.4  885.32  5085.4  892.77  5093.4  895.01    5116  900.25  5146.6  910.45
    5167  913.85  5187.4  918.24  5207.8  924.34  5240.9  930.48  5258.8   932.8
#Mann= 8 ,-1 , 0
  4643.3     .12       0  4897.9    .035       0  4990.6     .07       0
  4994.3     .05       0  4998.3     .07       0  5068.4     .12       0
  5093.4     .07       0  5240.9     .12       0
#XS Ineff= 2 , 0
       0  4922.7  899.45               0
Permanent Ineff=
       F       F
Bank Sta=4994.3,4998.3
XS Rating Curve= 0 ,0
Exp/Cntr=0.3,0.1

Type RM Length L Ch R = 1 ,17692   ,469,469,469
BEGIN DESCRIPTION:
Guadalupe Tributary 32 38.0
END DESCRIPTION:
XS GIS Cut Line= 3
      2224691.22     13872452.34        2224325.       13872175.
      2223849.95     13872041.25
#Sta/Elev= 30
  4544.6  925.96  4706.9  916.16  4732.5  912.88  4790.7  910.06  4817.8  902.51
  4840.6  893.78  4896.8  887.85  4925.9  876.12  4953.8  869.22  4965.6  868.65
  4965.8  868.15  4969.6  868.65  4982.2  870.26  4990.4  873.41  4996.7  872.41
  5000.8   876.2  5035.1  880.63  5094.3  882.87  5172.7  882.65  5201.4  885.76
    5246  895.07  5274.1  904.27    5280  907.99  5319.2  917.46  5353.3  930.16
  5387.3  936.13  5409.1  937.65  5426.5  944.35  5465.8   946.8  5497.5  951.36
#Mann= 4 ,-1 , 0
  4544.6     .07       0  4706.9     .12       0  4965.6     .05       0
  4969.6     .12       0
Bank Sta=4965.6,4969.6
XS Rating Curve= 0 ,0
Exp/Cntr=0.3,0.1

Type RM Length L Ch R = 1 ,17223   ,452,452,452
BEGIN DESCRIPTION:
Guadalupe Tributary 32 37.0
END DESCRIPTION:
XS GIS Cut Line= 3
      2224774.97       13871725.        2224375.       13871725.
      2224074.99     13871474.99
#Sta/Elev= 30
  4604.3  945.19  4624.3  940.16  4644.3  933.16  4684.3  924.52  4754.3  898.86
  4844.3  873.18  4894.3  866.26  4944.3  863.48  4954.3  861.53  4964.3  857.68
  4982.1   857.3  4982.4   856.8  4986.4   857.3  4994.3  861.62  5001.8  868.05
  5007.5  868.05  5011.4  873.13  5025.7  874.88  5068.7  876.61    5096  873.24
  5110.4  874.02  5132.5  878.04  5153.3  878.58  5217.1  889.19  5238.6  894.55
  5280.9   908.8  5309.5  914.84  5344.7  924.73  5373.3  928.43  5394.8   929.1
#Mann= 3 ,-1 , 0
  4604.3     .12       0  4982.1     .05       0  4986.4     .12       0
Bank Sta=4982.1,4986.4
XS Rating Curve= 0 ,0
Exp/Cntr=0.3,0.1

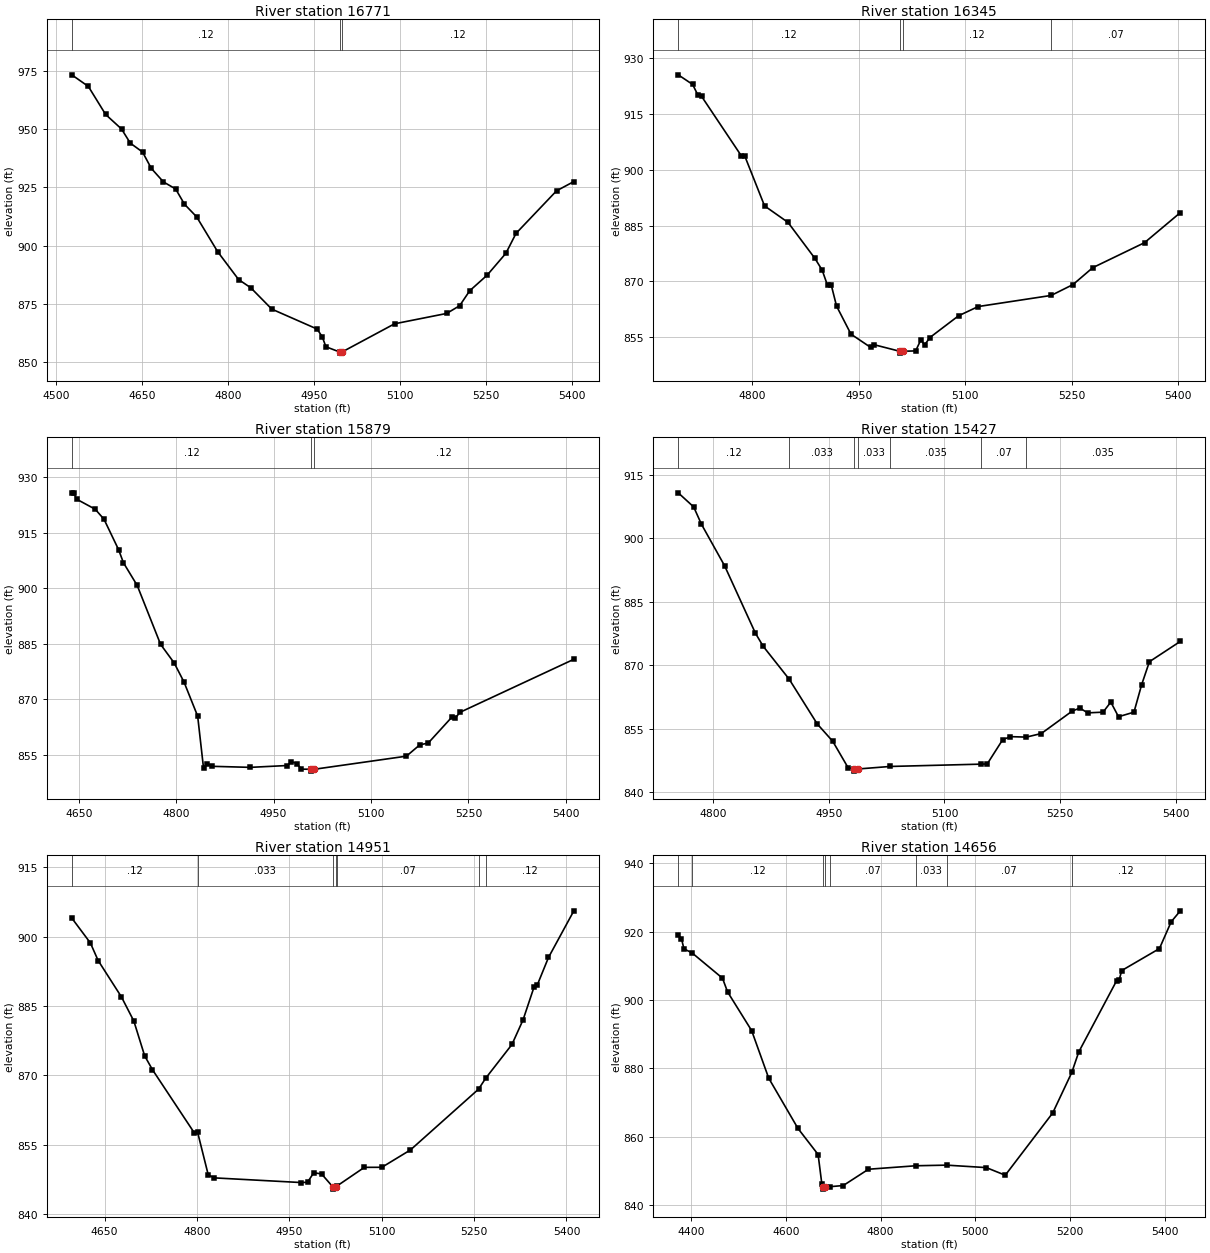
Type RM Length L Ch R = 1 ,16771   ,426,426,426
BEGIN DESCRIPTION:
Guadalupe Tributary 32 36.0
END DESCRIPTION:
XS GIS Cut Line= 3
      2224925.03     13871575.02        2224525.       13871325.
      2224125.04     13871374.99
#Sta/Elev= 30
  4527.9  973.17  4556.8  968.19  4586.9  956.19  4614.6  949.97  4629.9  943.91
  4651.2  940.11  4666.5  933.09  4687.7  927.29  4708.9  924.28  4724.3  917.75
  4745.5  912.33  4782.1  897.42  4818.6  885.49  4839.8  881.97  4876.4  872.83
  4955.4  864.29  4964.3  860.98  4970.7  856.71  4994.5  854.48  4994.8  853.98
  4998.9  854.48  5090.3  866.54    5181  870.97  5203.7  874.28  5221.3   880.7
  5251.6  887.36  5284.3  896.74    5302  905.28  5372.5  923.48  5402.7  927.46
#Mann= 3 ,-1 , 0
  4527.9     .12       0  4994.5     .05       0  4998.9     .12       0
Bank Sta=4994.5,4998.9
XS Rating Curve= 0 ,0
Exp/Cntr=0.3,0.1

Type RM Length L Ch R = 1 ,16345   ,466,466,466
BEGIN DESCRIPTION:
Guadalupe Tributary 32 35.0
END DESCRIPTION:
XS GIS Cut Line= 3
      2224924.98       13871025.        2224625.       13870975.
      2224225.03       13871025.
#Sta/Elev= 30
  4695.9  925.53  4716.2  922.94  4723.8  919.99  4728.8  919.73  4784.6  903.79
  4789.7  903.65  4817.5  890.27  4850.5  885.84  4888.5  876.13  4898.6  873.01
  4906.2  868.88  4911.3  869.09  4918.9  863.32  4939.2  855.78  4967.1  852.19
  4972.1  852.92  5007.9  851.17  5008.2  850.67  5012.3  851.17  5030.3  851.27
  5037.8   854.3  5042.8  852.83  5050.4  854.87  5090.7  860.71  5118.4   863.2
  5221.2  866.19    5252  869.12  5279.7  873.65  5352.7  880.38  5403.1  888.46
#Mann= 4 ,-1 , 0
  4695.9     .12       0  5007.9     .05       0  5012.3     .12       0
  5221.2     .07       0
Bank Sta=5007.9,5012.3
XS Rating Curve= 0 ,0
Exp/Cntr=0.3,0.1

Type RM Length L Ch R = 1 ,15879   ,452,452,452
BEGIN DESCRIPTION:
Guadalupe Tributary 32 34.0
END DESCRIPTION:
XS GIS Cut Line= 3
        2224925.       13870375.        2224625.       13870575.
      2224224.96     13870675.01
#Sta/Elev= 30
  4639.3  925.81  4642.3  925.81  4646.8  924.09  4675.4  921.37  4688.9  918.67
  4711.4  910.42  4718.9  906.87    4740  900.76    4776  884.82    4797  879.77
  4812.1  874.61  4833.1  865.39  4842.1  851.39  4848.1  852.53  4855.6  851.81
  4914.2  851.53  4971.3  852.03  4977.3  853.06  4986.3  852.55  4992.3  851.05
  5007.9  851.01  5008.2  850.51  5012.4  851.01  5154.5  854.56  5175.1  857.63
    5188   858.1    5224  865.04  5229.2  864.76  5236.9  866.42  5412.2  880.77
#Mann= 3 ,-1 , 0
  4639.3     .12       0  5007.9     .05       0  5012.4     .12       0
Bank Sta=5007.9,5012.4
XS Rating Curve= 0 ,0
Exp/Cntr=0.3,0.1

Type RM Length L Ch R = 1 ,15427   ,476,476,476
BEGIN DESCRIPTION:
Guadalupe Tributary 32 33.0
END DESCRIPTION:
XS GIS Cut Line= 3
        2224825.       13870225.        2224575.       13870225.
        2224175.       13870225.
#Sta/Elev= 30
  4755.3  910.72  4775.3  907.39  4785.3  903.32  4815.3  893.51  4855.3  877.56
  4865.3  874.49  4898.9  866.74  4935.3  856.16  4955.3  852.08  4975.3  845.81
    4983  845.53  4983.3  845.03  4987.6  845.53  5029.4  846.13  5147.6  846.68
  5155.3  846.72  5175.3  852.44  5185.3  853.17  5205.9  853.06  5225.3   853.9
  5265.3   859.2  5275.3  859.92  5285.3  858.78  5305.3  858.95  5315.3  861.32
  5325.3  857.87  5345.3  858.95  5355.3  865.47  5365.3  870.86  5405.3  875.65
#Mann= 7 ,-1 , 0
  4755.3     .12       0  4898.9    .033       0    4983    .033       0
  4987.6    .033       0  5029.4    .035       0  5147.6     .07       0
  5205.9    .035       0
Bank Sta=4983,4987.6
XS Rating Curve= 0 ,0
Exp/Cntr=0.3,0.1

Type RM Length L Ch R = 1 ,14951   ,295,295,295
BEGIN DESCRIPTION:
Guadalupe Tributary 32 32.0
END DESCRIPTION:
XS GIS Cut Line= 3
      2224824.98       13869975.        2224425.       13869925.
        2224025.       13870025.
#Sta/Elev= 30
  4596.6  904.03  4626.8  898.65  4639.4  894.85  4677.2  886.99  4697.4  881.76
    4715  874.23  4727.6  871.25  4795.6  857.58  4800.8   857.8  4818.3  848.47
  4828.4  847.85  4969.5  846.84  4979.5  846.91  4989.6  848.97  5002.3   848.7
  5020.5  845.92  5020.9  845.42  5025.2  845.92  5026.7  846.04  5071.8  850.13
  5100.2  850.14  5146.6  853.89  5257.2  867.03  5268.9  869.41  5311.5   876.7
  5329.5  882.01  5347.6  889.21  5352.7  889.58  5370.8   895.5    5412  905.59
#Mann= 7 ,-1 , 0
  4596.6     .12       0  4800.8    .033       0  5020.5    .033       0
  5025.2    .033       0  5026.7     .07       0  5257.2    .035       0
  5268.9     .12       0
Bank Sta=5020.5,5025.2
XS Rating Curve= 0 ,0
Exp/Cntr=0.3,0.1

Type RM Length L Ch R = 1 ,14656   ,303,303,303
BEGIN DESCRIPTION:
A19343
END DESCRIPTION:
XS GIS Cut Line= 4
      2224872.85     13869466.44      2224474.51     13869609.84
      2224257.82     13869692.69      2223879.33     13869835.82
#Sta/Elev= 30
  4372.8   919.1  4379.6  917.99  4384.9     915  4401.8  913.85  4466.2  906.43
    4477   902.4  4527.8  891.08  4563.8  877.17  4625.6  862.45  4668.1  854.82
    4676  846.18  4678.9  845.19  4679.3  844.69  4683.6  845.19  4694.2  845.42
  4721.2  845.74  4774.4  850.51  4874.5  851.53  4939.4  851.71  5023.2  850.99
  5063.2  848.76  5163.4  866.98  5203.7  878.84  5218.4  884.84  5298.2  905.65
  5303.5  905.82  5309.1  908.66  5388.7  915.09  5413.5  922.93  5432.8  926.14
#Mann= 8 ,-1 , 0
  4372.8    .035       0  4401.8     .12       0  4678.9     .05       0
  4683.6     .12       0  4694.2     .07       0  4874.5    .033       0
  4939.4     .07       0  5203.7     .12       0
Bank Sta=4678.9,4683.6
XS Rating Curve= 0 ,0
Exp/Cntr=0.3,0.1

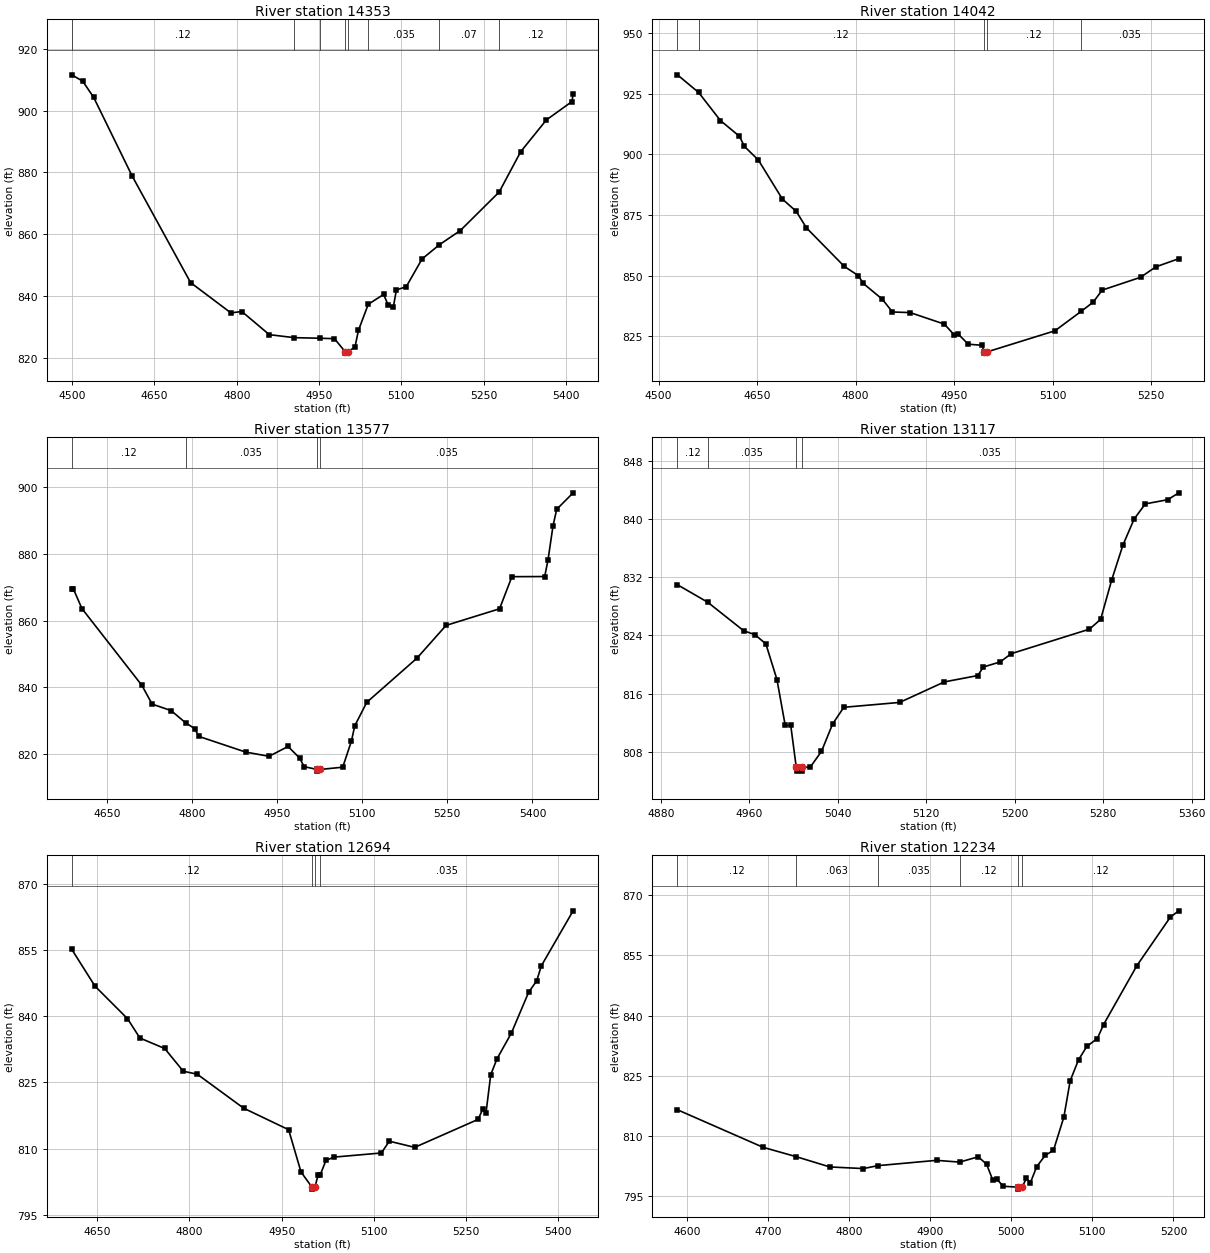
Type RM Length L Ch R = 1 ,14353   ,311,311,311
BEGIN DESCRIPTION:
Guadalupe Tributary 32 31.0
END DESCRIPTION:
XS GIS Cut Line= 3
      2224725.02       13869375.      2224350.23     13869383.59
      2223856.63     13869600.14
#Sta/Elev= 30
  4499.3  911.58  4519.3  909.52  4539.3  904.28  4609.3  878.86    4716  844.31
  4789.4  834.51  4809.4  834.95  4859.4  827.46  4904.7  826.49  4951.3   826.3
  4978.2  826.16  4997.5  821.98  4997.9  821.48  5002.5  821.98  5015.5  823.38
  5021.9  828.85  5039.8  837.29  5067.7  840.48  5076.5  836.94  5085.6  836.49
  5091.1  841.95    5109  842.97  5137.8  851.95  5169.4  856.57  5207.5  861.15
  5278.4  873.63  5317.7   886.7  5364.5  896.98  5411.2  902.94  5413.2  905.41
#Mann= 8 ,-1 , 0
  4499.3     .12       0  4904.7     .07       0  4951.3     .12       0
  4997.5     .05       0  5002.5     .12       0  5039.8    .035       0
  5169.4     .07       0  5278.4     .12       0
Bank Sta=4997.5,5002.5
XS Rating Curve= 0 ,0
Exp/Cntr=0.3,0.1

Type RM Length L Ch R = 1 ,14042   ,465,465,465
BEGIN DESCRIPTION:
Guadalupe Tributary 32 30.0
END DESCRIPTION:
XS GIS Cut Line= 3
      2224625.01     13868874.99        2224225.       13869125.
      2223974.97     13869275.02
#Sta/Elev= 30
  4528.8  932.84  4561.1  925.56  4594.3  913.98  4623.2   907.5  4630.8  903.31
    4652  897.71  4688.6   881.6  4709.8   876.5  4725.2  869.73  4782.9  853.82
  4804.2  850.04  4811.8   846.8  4840.7  840.31  4856.1  835.05  4883.2  834.79
  4935.1  830.05  4950.4  825.54  4956.3  825.89  4971.6  821.76  4992.9  821.31
  4995.1  818.58  4995.4  818.08  5000.1  818.58  5103.5  827.29  5143.7  835.36
  5161.8   839.1  5175.4  844.06  5233.8  849.34  5257.1  853.66  5292.1  857.03
#Mann= 5 ,-1 , 0
  4528.8    .035       0  4561.1     .12       0  4995.1     .05       0
  5000.1     .12       0  5143.7    .035       0
Bank Sta=4995.1,5000.1
XS Rating Curve= 0 ,0
Exp/Cntr=0.3,0.1

Type RM Length L Ch R = 1 ,13577   ,460,460,460
BEGIN DESCRIPTION:
Guadalupe Tributary 32 29.0
END DESCRIPTION:
XS GIS Cut Line= 3
      2224375.01       13868675.        2223975.       13868775.
      2223575.01     13869024.99
#Sta/Elev= 30
  4587.7  869.65  4590.3  869.65  4605.7  863.64  4711.4  840.61  4729.4  834.99
  4762.9  833.05  4788.4  829.38  4804.2  827.67  4811.9   825.3  4894.4   820.6
  4935.6  819.34  4969.1  822.28  4989.7  818.79  4997.4  816.23  5020.5  815.39
  5020.9  814.89  5025.6  815.39  5065.5  816.07  5080.8  823.88  5086.7  828.47
  5107.9  835.53  5196.4  848.78  5247.7   858.6    5342  863.58  5363.8  873.21
  5421.6  873.25  5427.5  878.28  5436.3   888.5  5442.8  893.42  5471.7  898.36
#Mann= 4 ,-1 , 0
  4587.7     .12       0  4788.4    .035       0  5020.5    .035       0
  5025.6    .035       0
Bank Sta=5020.5,5025.6
XS Rating Curve= 0 ,0
Exp/Cntr=0.3,0.1

Type RM Length L Ch R = 1 ,13117   ,423,423,423
BEGIN DESCRIPTION:
Guadalupe Tributary 32 28.0
END DESCRIPTION:
XS GIS Cut Line= 3
      2224174.97       13868425.        2224075.       13868425.
      2223725.03       13868475.
#Sta/Elev= 30
  4894.9  830.98  4922.3  828.57  4954.9  824.64  4964.9  824.12  4974.9  822.84
  4984.9  817.94  4992.4  811.62  4997.4  811.62  5002.4  805.84  5002.8  805.34
  5007.2  805.34  5007.5  805.84  5015.1   805.9  5025.2  808.06  5035.3  811.84
  5045.4  814.12  5095.9  814.79  5136.3  817.61  5166.6  818.49  5171.6  819.66
  5186.8  820.36  5196.9   821.5  5267.6  824.87  5277.7  826.22  5287.8  831.69
  5297.9  836.45    5308  840.02  5318.1   842.1  5338.3  842.67  5348.4  843.62
#Mann= 4 ,-1 , 0
  4894.9     .12       0  4922.3    .035       0  5002.4    .035       0
  5007.5    .035       0
Bank Sta=5002.4,5007.5
XS Rating Curve= 0 ,0
Exp/Cntr=0.3,0.1

Type RM Length L Ch R = 1 ,12694   ,460,460,460
BEGIN DESCRIPTION:
Guadalupe Tributary 32 27.0
END DESCRIPTION:
XS GIS Cut Line= 3
      2224425.04       13868025.        2224025.       13868075.
      2223624.96     13868175.01
#Sta/Elev= 30
  4608.5  855.15  4646.3  846.81  4699.2  839.44  4719.4  835.05  4759.7  832.68
  4789.9  827.53  4812.6  826.86  4888.2  819.15  4961.3  814.28  4981.4  804.71
    4999  801.32  4999.4  800.82  5004.2  801.32  5009.1     804  5012.5     804
    5022  807.32  5034.8  808.07  5112.2  809.01    5125  811.68  5166.3  810.28
  5269.3  816.61  5277.1  818.94  5282.2  817.96    5290  826.75  5300.3  830.37
  5323.5  836.15  5351.8  845.46  5364.7  847.99  5372.4  851.43    5424  863.87
#Mann= 4 ,-1 , 0
  4608.5     .12       0    4999     .05       0  5004.2     .12       0
  5012.5    .035       0
Bank Sta=4999,5004.2
XS Rating Curve= 0 ,0
Exp/Cntr=0.3,0.1

Type RM Length L Ch R = 1 ,12234   ,556,556,556
BEGIN DESCRIPTION:
Guadalupe Tributary 32 26.0
END DESCRIPTION:
XS GIS Cut Line= 3
      2224175.01       13867825.        2223775.       13867725.
      2223574.98     13867775.01
#Sta/Elev= 30
  4588.1  816.51  4693.8  807.14  4734.7   804.8  4776.2  802.24  4817.5  801.84
  4835.5  802.57  4907.7  803.89  4936.3  803.45  4959.2  804.78  4969.5  802.91
  4977.2  798.92  4982.4  799.13  4990.1  797.42  5008.1  797.21  5008.5  796.71
  5013.3  797.21  5018.5  799.37  5023.6  798.35  5031.3  802.31  5041.7  805.11
    5052   806.4  5064.8  814.68  5072.6  823.75  5082.9  828.97  5093.2  832.33
  5106.1  834.28  5113.8  837.77    5155   852.5  5196.3  864.61  5206.6  866.14
#Mann= 6 ,-1 , 0
  4588.1     .12       0  4734.7    .063       0  4835.5    .035       0
  4936.3     .12       0  5008.1     .05       0  5013.3     .12       0
Bank Sta=5008.1,5013.3
XS Rating Curve= 0 ,0
Exp/Cntr=0.3,0.1

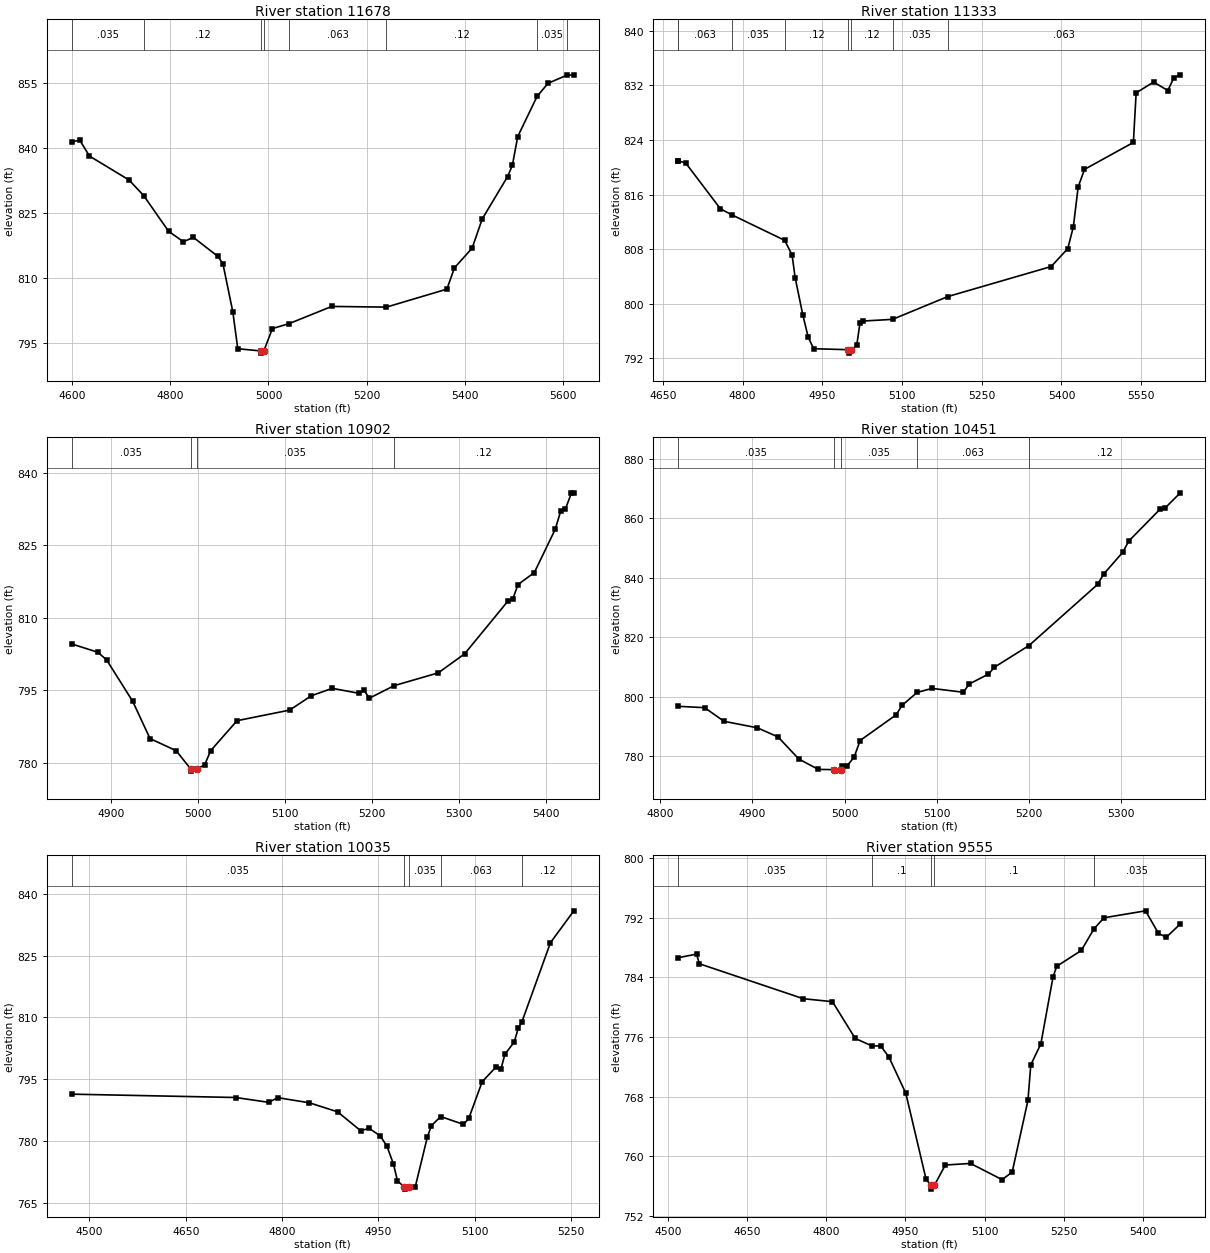
Type RM Length L Ch R = 1 ,11678   ,345,345,345
BEGIN DESCRIPTION:
A19342
END DESCRIPTION:
XS GIS Cut Line= 3
      2224480.85     13867573.57      2223853.12     13867493.91
      2223473.95      13867589.5
#Sta/Elev= 30
  4598.9  841.41  4614.9  841.91    4635   838.2  4715.7  832.67  4745.5  829.08
  4796.3  820.84  4826.6  818.41  4846.7  819.44  4897.1  815.02  4907.2   813.3
  4927.4  802.18  4937.4  793.72  4985.2  793.21  4985.6  792.71  4990.5  793.21
    5008  798.38  5042.3  799.53    5129  803.49  5240.5  803.33  5363.8  807.48
  5379.3  812.41  5415.2  816.93    5436  823.71  5487.5  833.44  5497.4  836.07
  5508.2  842.68  5547.7  851.96  5570.1     855  5607.9  856.83  5622.7  856.95
#Mann= 8 ,-1 , 0
  4598.9    .035       0  4745.5     .12       0  4985.2     .05       0
  4990.5     .12       0  5042.3    .063       0  5240.5     .12       0
  5547.7    .035       0  5607.9    .094       0
Bank Sta=4985.2,4990.5
XS Rating Curve= 0 ,0
Exp/Cntr=0.3,0.1

Type RM Length L Ch R = 1 ,11333   ,431,431,431
BEGIN DESCRIPTION:
Guadalupe Tributary 32 25.0
END DESCRIPTION:
XS GIS Cut Line= 3
      2224347.04     13867178.43        2224025.       13867225.
      2223432.43      13867404.7
#Sta/Elev= 30
    4679  820.95  4679.3  820.95  4693.1  820.62  4758.3  813.92  4779.3  813.05
  4879.3  809.29  4893.2  807.15  4898.9  803.84  4913.4  798.36  4923.6  795.08
  4933.7  793.41  4999.2  793.26  4999.6  792.76  5004.5  793.26  5014.8  793.88
  5020.8  797.11  5026.1  797.46  5082.2  797.71  5186.1  801.05  5380.6  805.45
  5411.9  808.08  5422.4  811.29  5431.4  817.11  5443.3  819.69  5535.3  823.64
  5540.5  830.91  5573.4  832.49    5600  831.25  5611.6  833.12  5623.6  833.55
#Mann= 8 ,-1 , 0
    4679    .035       0  4679.3    .063       0  4779.3    .035       0
  4879.3     .12       0  4999.2     .05       0  5004.5     .12       0
  5082.2    .035       0  5186.1    .063       0
Bank Sta=4999.2,5004.5
XS Rating Curve= 0 ,0
Exp/Cntr=0.3,0.1

Type RM Length L Ch R = 1 ,10902   ,451,451,451
BEGIN DESCRIPTION:
Guadalupe Tributary 32 24.0
END DESCRIPTION:
XS GIS Cut Line= 3
      2224024.95       13866875.        2223875.       13866875.
      2223474.96     13866724.98
#Sta/Elev= 30
  4854.8  804.62  4884.8   802.9  4894.8  801.33  4924.8  792.76  4944.8  785.03
  4974.8  782.53  4991.3   778.8  4991.8   778.3  4998.2   778.8  5007.4  779.53
  5014.5  782.54  5044.8  788.74  5105.3  790.93  5130.2   793.9  5154.3  795.44
  5185.4  794.39  5190.8     795    5197   793.4  5225.4  795.99  5276.2  798.64
  5306.5  802.59  5356.3  813.51  5361.6  813.85  5367.9  816.92  5386.6  819.41
  5410.6  828.35  5416.8  832.07  5422.2  832.49  5429.3   835.9    5432   835.9
#Mann= 4 ,-1 , 0
  4854.8    .035       0  4991.3    .035       0  4998.2    .035       0
  5225.4     .12       0
Bank Sta=4991.3,4998.2
XS Rating Curve= 0 ,0
Exp/Cntr=0.3,0.1

Type RM Length L Ch R = 1 ,10451   ,416,416,416
BEGIN DESCRIPTION:
Guadalupe Tributary 32 23.0
END DESCRIPTION:
XS GIS Cut Line= 3
      2223875.02     13866374.99        2223725.       13866475.
      2223375.01       13866575.
#Sta/Elev= 30
  4819.7  796.72  4848.3  796.27  4869.3  791.68  4905.4   789.5  4927.9  786.42
  4950.4     779  4971.5   775.5    4989  775.42  4989.5  774.92  4995.9  775.42
    4997  776.59  5002.6  776.59  5010.4  779.66  5016.9  785.22  5055.9  793.85
  5062.4  797.06  5078.7   801.4  5094.9  802.75  5128.7  801.45  5135.2  804.23
    5156  807.55  5162.5  809.88    5200  817.18  5274.3  837.72  5280.8  841.16
  5301.6  848.54  5308.1   852.3  5341.9  862.98  5347.1  863.32    5364  868.54
#Mann= 5 ,-1 , 0
  4819.7    .035       0    4989    .035       0  4995.9    .035       0
  5078.7    .063       0    5200     .12       0
Bank Sta=4989,4995.9
XS Rating Curve= 0 ,0
Exp/Cntr=0.3,0.1

Type RM Length L Ch R = 1 ,10035   ,480,480,480
BEGIN DESCRIPTION:
Guadalupe Tributary 32 22.0
END DESCRIPTION:
XS GIS Cut Line= 3
       2224044.3     13866012.12        2223525.       13866125.
      2223325.02     13866274.98
#Sta/Elev= 30
  4472.7  791.36  4727.8  790.55    4779  789.38  4793.3  790.51  4842.4  789.27
  4886.4  787.07  4922.3  782.49  4935.6  783.06    4953   781.2  4963.2  778.73
  4973.4  774.38  4979.6  770.32  4990.4  768.81  4990.9  768.31  4997.3  768.81
  5007.3  768.88    5026  780.88  5032.3  783.69  5046.9  785.93  5082.3  784.02
  5090.6  785.48  5111.4  794.37  5132.3  797.85  5140.6  797.42  5146.8  801.06
  5161.4  804.03  5167.7  807.47    5173  808.79  5217.7  828.13  5254.1  835.86
#Mann= 5 ,-1 , 0
  4472.7    .035       0  4990.4    .035       0  4997.3    .035       0
  5046.9    .063       0    5173     .12       0
Bank Sta=4990.4,4997.3
XS Rating Curve= 0 ,0
Exp/Cntr=0.3,0.1

Type RM Length L Ch R = 1 ,9555    ,450,450,450
BEGIN DESCRIPTION:
Guadalupe Tributary 32 21.0
END DESCRIPTION:
XS GIS Cut Line= 3
      2224079.32     13865843.21        2223625.       13865675.
      2223190.26     13865505.43
#Sta/Elev= 30
  4519.8  786.62  4554.5   787.1  4559.8  785.81  4756.6  781.13    4812  780.73
    4855  775.81  4887.4  774.78  4903.2  774.82    4919   773.3  4950.9  768.46
  4989.1     757  4998.1  756.12  4998.6  755.62    5005  756.12  5025.7  758.85
  5073.5  759.06  5133.3  756.89  5152.4   757.9  5182.3  767.52  5187.6  772.26
  5206.7  775.07  5229.7     784  5236.6  785.46  5283.3  787.59  5307.4  790.49
  5326.3  791.97    5405   792.9  5429.5  789.88  5444.3  789.36  5470.9  791.14
#Mann= 5 ,-1 , 0
  4519.8    .035       0  4887.4      .1       0  4998.1     .05       0
    5005      .1       0  5307.4    .035       0
Bank Sta=4998.1,5005
XS Rating Curve= 0 ,0
Exp/Cntr=0.3,0.1