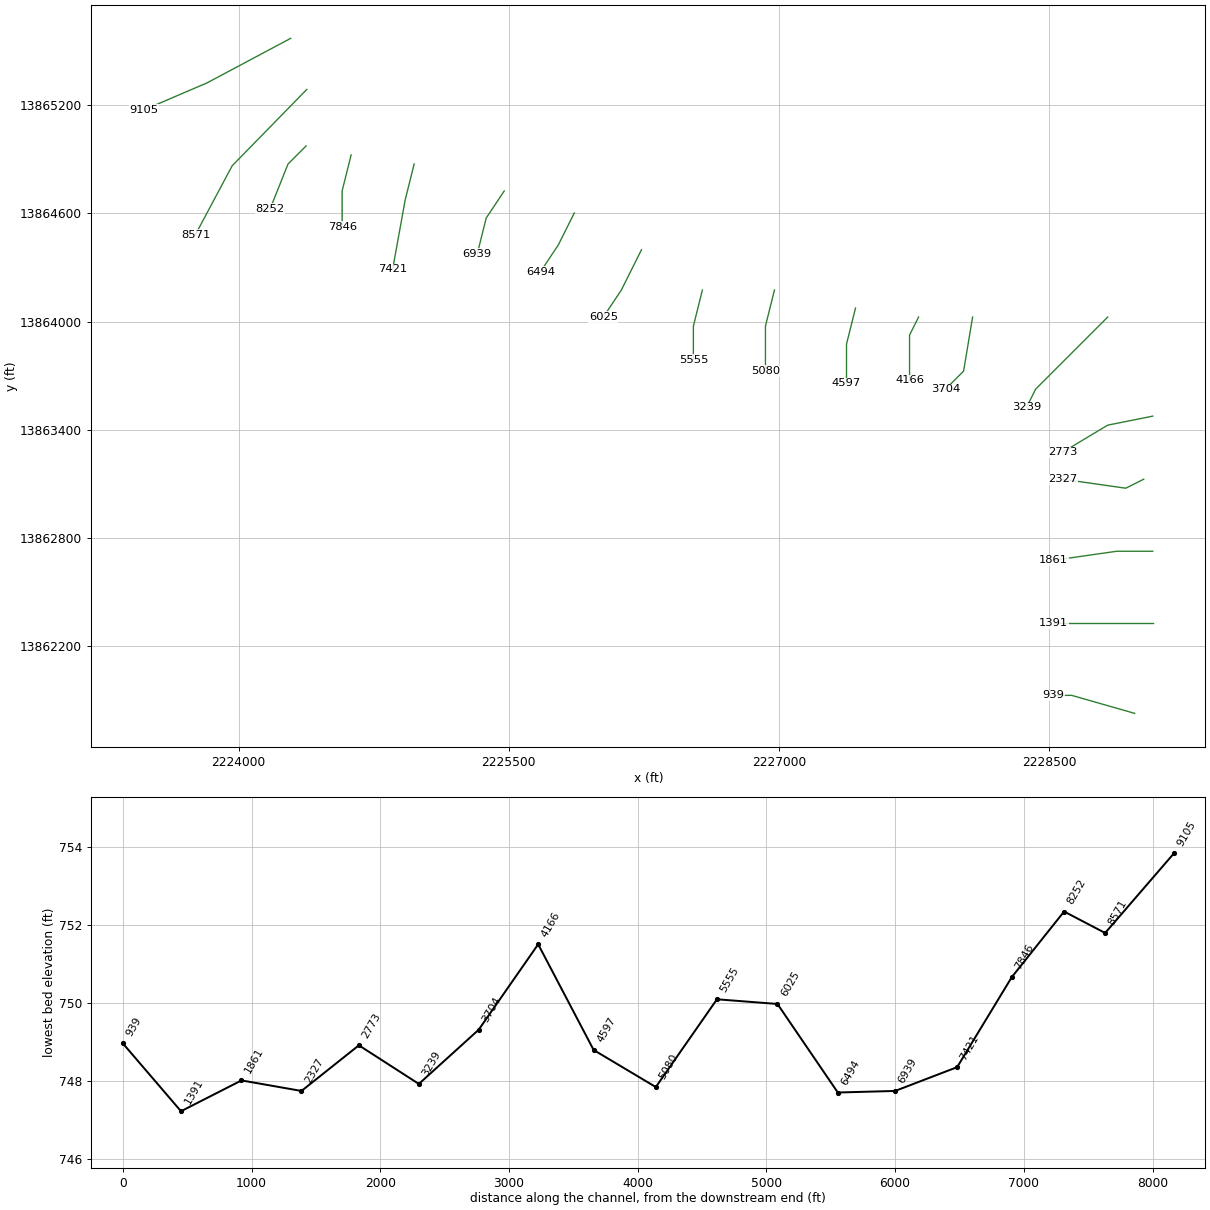
HEC-RAS study Guadalupe Tributary 32.prj: Guadalupe Tributary 32 Base Level Engineering

--- Guadalupe Tributary 32.g01 (geometry) --- (continued)

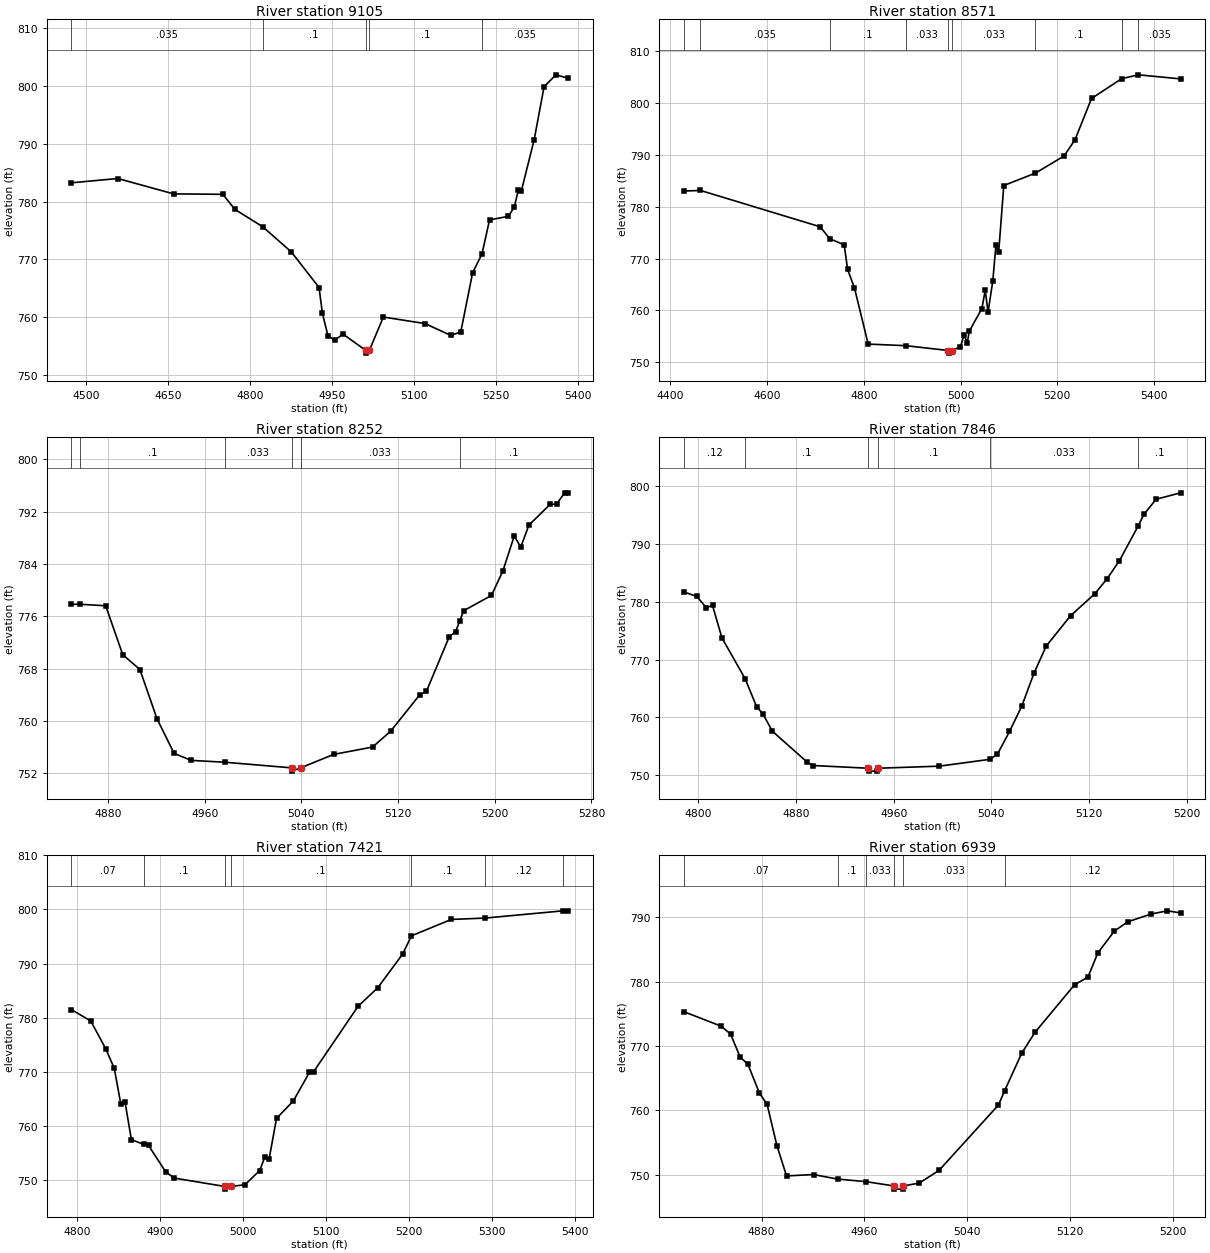
Type RM Length L Ch R = 1 ,9105    ,534,534,534
BEGIN DESCRIPTION:
Guadalupe Tributary 32 20.0
END DESCRIPTION:
XS GIS Cut Line= 3
      2224289.68     13865572.36        2223825.       13865325.
      2223475.01       13865175.
#Sta/Elev= 30
  4473.8  783.23  4558.3  783.97  4660.4  781.32  4750.4  781.24  4772.4  778.64
  4823.2  775.65  4875.6   771.3  4926.2  765.16  4932.3  760.74  4942.5  756.83
  4954.9  756.08  4970.1  757.12  5011.1  754.34  5011.6  753.84  5018.3  754.34
  5043.7  760.07  5119.9  758.94    5167   756.9  5185.2  757.49  5206.9  767.73
  5223.9  770.93  5237.8  776.83  5272.2  777.44  5283.1  779.07  5290.3  781.95
  5295.8  781.78  5319.4  790.69  5337.5  799.84  5359.3  801.86    5381  801.28
#Mann= 5 ,-1 , 0
  4473.8    .035       0  4823.2      .1       0  5011.1     .05       0
  5018.3      .1       0  5223.9    .035       0
Bank Sta=5011.1,5018.3
XS Rating Curve= 0 ,0
Exp/Cntr=0.3,0.1

Type RM Length L Ch R = 1 ,8571    ,319,319,319
BEGIN DESCRIPTION:
Guadalupe Tributary 32 19.0
END DESCRIPTION:
XS GIS Cut Line= 3
      2224378.91     13865288.75      2223964.65     13864864.93
      2223760.72     13864482.56
#Sta/Elev= 30
  4428.7  782.98  4462.4  783.09  4709.9   776.1  4729.5   773.8  4759.4  772.64
  4766.5   767.9  4780.7  764.32    4809  753.54  4887.2  753.23    4975   752.3
  4975.5   751.8  4982.3   752.3  4999.8  753.03    5007  755.25    5014  753.81
  5017.8  755.99  5043.9  760.36    5051  763.89  5056.7  759.62  5066.6  765.71
    5073  772.53  5078.7  771.21  5089.3  784.04  5154.6  786.42  5213.9  789.72
  5236.6  792.87  5270.6  800.78  5332.7  804.58  5367.3  805.33  5454.7  804.55
#Mann= 9 ,-1 , 0
  4428.7    .063       0  4462.4    .035       0  4729.5      .1       0
  4887.2    .033       0    4975    .033       0  4982.3    .033       0
  5154.6      .1       0  5332.7     .07       0  5367.3    .035       0
Bank Sta=4975,4982.3
XS Rating Curve= 0 ,0
Exp/Cntr=0.3,0.1

Type RM Length L Ch R = 1 ,8252    ,406,406,406
BEGIN DESCRIPTION:
Guadalupe Tributary 32 18.0
END DESCRIPTION:
XS GIS Cut Line= 3
      2224375.02     13864975.02        2224275.       13864875.
        2224175.       13864625.
#Sta/Elev= 30
  4849.8  777.84  4856.6  777.84  4878.1  777.61  4892.2  770.14  4906.4  767.87
  4920.5  760.37  4934.7  755.06  4948.8  753.99  4976.7  753.71  5031.9  752.85
  5032.4  752.35  5039.4  752.85  5066.6   754.9  5098.9  756.03  5113.8  758.44
    5138  764.03  5143.4  764.52  5162.2  772.82  5167.6  773.66  5170.9  775.24
  5174.3  776.86  5197.2  779.18  5206.7  782.92  5216.1  788.27  5221.5  786.57
  5228.2  789.92  5245.7  793.08  5251.1  793.14  5257.8  794.86  5260.5  794.86
#Mann= 6 ,-1 , 0
  4849.8    .063       0  4856.6      .1       0  4976.7    .033       0
  5031.9    .033       0  5039.4    .033       0  5170.9      .1       0
Bank Sta=5031.9,5039.4
XS Rating Curve= 0 ,0
Exp/Cntr=0.3,0.1

Type RM Length L Ch R = 1 ,7846    ,425,425,425
BEGIN DESCRIPTION:
Guadalupe Tributary 32 17.0
END DESCRIPTION:
XS GIS Cut Line= 3
        2224625.       13864925.        2224575.       13864725.
        2224575.     13864524.96
#Sta/Elev= 30
  4788.6   781.7  4798.9  780.95  4806.6  779.02  4811.8  779.38  4819.5  773.76
  4838.4  766.72  4847.9  761.83    4853  760.59  4860.8  757.58  4889.1  752.25
  4894.3  751.64  4939.4  751.17  4939.9  750.67  4946.5  750.67    4947  751.17
  4997.3  751.53  5038.6  752.71  5044.8  753.56  5054.8  757.54  5064.8  761.91
  5074.8  767.62  5084.8  772.33  5104.8  777.61  5124.8  781.44  5134.8  784.05
  5144.8  787.16  5159.9  793.08  5164.8  795.18  5174.8  797.79  5194.8   798.9
#Mann= 6 ,-1 , 0
  4788.6     .12       0  4838.4      .1       0  4939.4     .05       0
    4947      .1       0  5038.6    .033       0  5159.9      .1       0
Bank Sta=4939.4,4947
XS Rating Curve= 0 ,0
Exp/Cntr=0.3,0.1

Type RM Length L Ch R = 1 ,7421    ,482,482,482
BEGIN DESCRIPTION:
Guadalupe Tributary 32 16.0
END DESCRIPTION:
XS GIS Cut Line= 3
        2224975.     13864874.99        2224925.       13864675.
      2224855.41     13864289.78
#Sta/Elev= 30
  4793.4  781.49  4816.6   779.4  4834.6  774.27  4844.9  770.66  4852.7  764.13
  4857.8  764.49  4865.5   757.5  4880.1  756.63  4886.2  756.42  4906.8  751.54
  4917.1   750.4  4977.7  748.86  4978.2  748.36  4985.3  748.86  5002.1  749.16
  5019.9  751.78  5026.3  754.34  5031.4     754  5040.2   761.4  5060.5  764.65
  5079.8   769.9  5084.9  770.04  5138.4  782.11  5162.1  785.53    5192  791.74
  5202.7  795.12  5250.6  798.14    5291  798.39  5384.6  799.72    5391  799.73
#Mann= 7 ,-1 , 0
  4793.4     .07       0  4880.1      .1       0  4977.7     .05       0
  4985.3      .1       0  5202.7      .1       0    5291     .12       0
  5384.6    .035       0
Bank Sta=4977.7,4985.3
XS Rating Curve= 0 ,0
Exp/Cntr=0.3,0.1

Type RM Length L Ch R = 1 ,6939    ,445,445,445
BEGIN DESCRIPTION:
Guadalupe Tributary 32 15.0
END DESCRIPTION:
XS GIS Cut Line= 3
      2225475.03     13864725.04        2225375.       13864575.
        2225325.     13864374.98
#Sta/Elev= 30
  4819.7  775.32  4848.3   773.1  4855.8  771.87  4863.3  768.27  4869.3  767.17
  4878.3  762.68  4884.3  760.91  4891.9  754.51  4899.4   749.8  4920.4  750.02
  4939.1  749.31  4961.1  748.92  4982.7  748.25  4983.2  747.75  4989.8  747.75
  4990.3  748.25  5002.6  748.68  5018.1  750.66  5064.4  760.83  5069.2  763.05
  5082.5  768.88  5092.8  772.12  5123.7  779.54    5134   780.7  5141.8  784.48
  5154.6  787.86  5164.9   789.3    5183  790.51  5195.9  791.02  5206.2  790.69
#Mann= 6 ,-1 , 0
  4819.7     .07       0  4939.1      .1       0  4961.1    .033       0
  4982.7    .033       0  4990.3    .033       0  5069.2     .12       0
Bank Sta=4982.7,4990.3
XS Rating Curve= 0 ,0
Exp/Cntr=0.3,0.1

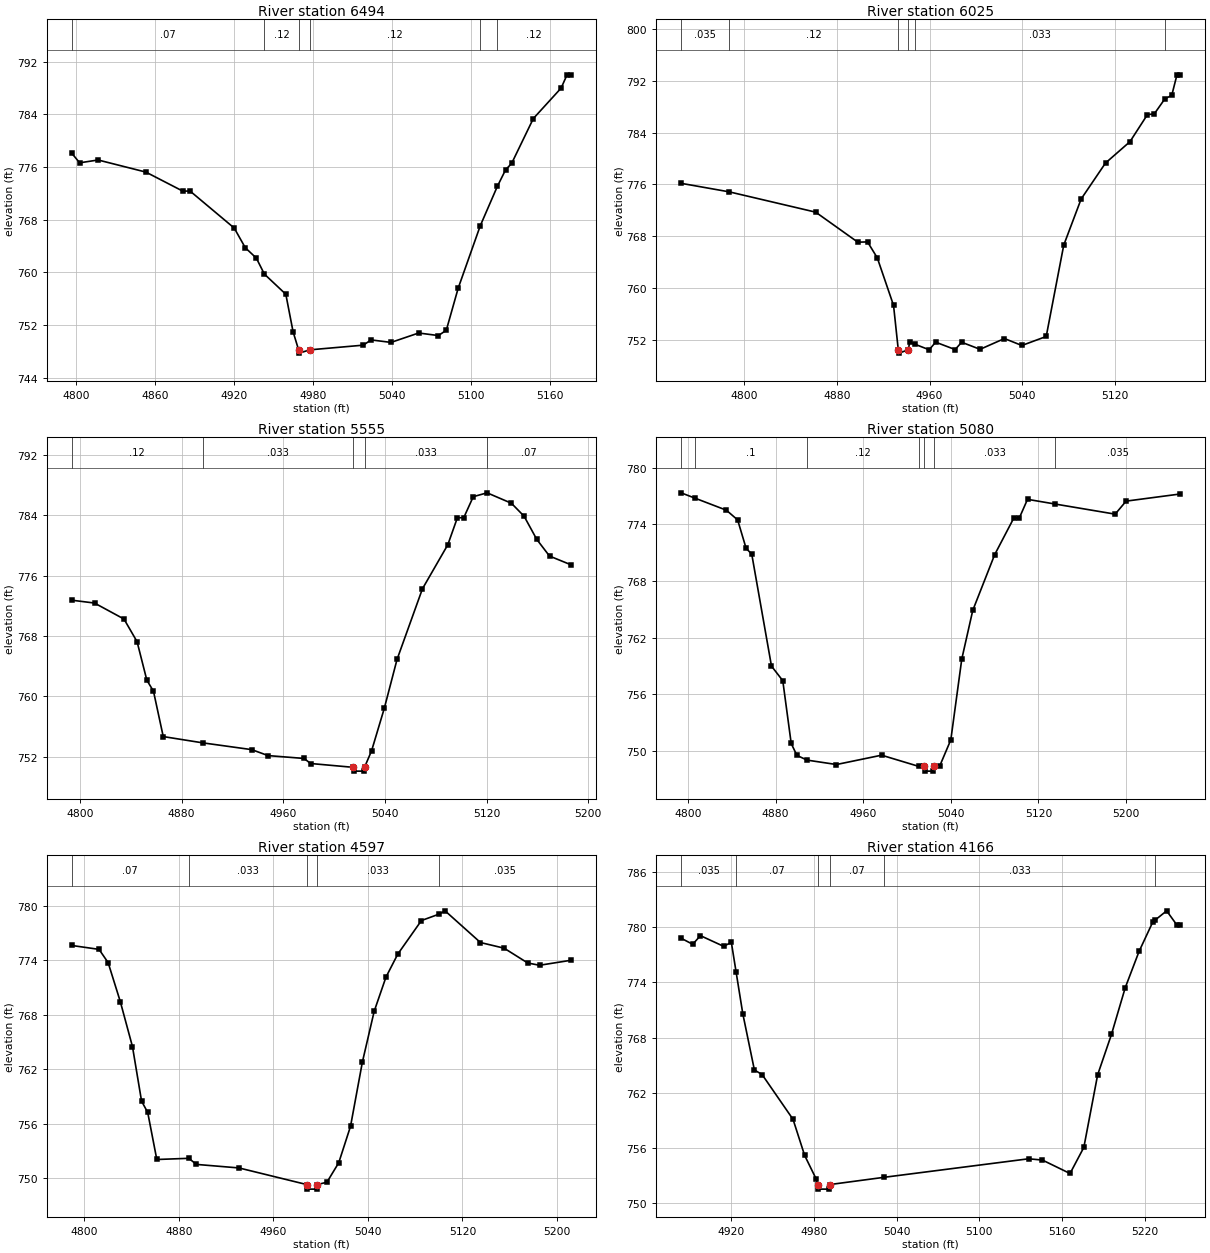
Type RM Length L Ch R = 1 ,6494    ,469,469,469
BEGIN DESCRIPTION:
Guadalupe Tributary 32 14.0
END DESCRIPTION:
XS GIS Cut Line= 4
      2225863.99     13864602.99        2225825.       13864525.
        2225775.       13864425.      2225674.99     13864274.98
#Sta/Elev= 30
  4796.6  778.13  4802.7  776.65  4816.7  777.08    4853  775.24    4881  772.35
  4886.6  772.35  4920.1  766.73  4928.5  763.74  4936.9  762.16    4943  759.73
  4959.3  756.66  4964.8  750.97    4969  748.21  4969.5  747.71  4977.5  748.21
  5018.1  748.92  5024.1  749.72  5039.2  749.34  5060.2  750.77  5075.2  750.38
  5081.2  751.19  5090.2  757.57    5107  767.08    5120  773.08  5126.3  775.61
  5130.8  776.55  5147.3  783.38  5168.4  788.01  5172.9  790.03  5175.9  790.03
#Mann= 6 ,-1 , 0
  4796.6     .07       0    4943     .12       0    4969     .05       0
  4977.5     .12       0    5107    .033       0    5120     .12       0
Bank Sta=4969,4977.5
XS Rating Curve= 0 ,0
Exp/Cntr=0.3,0.1

Type RM Length L Ch R = 1 ,6025    ,470,470,470
BEGIN DESCRIPTION:
Guadalupe Tributary 32 13.0
END DESCRIPTION:
XS GIS Cut Line= 4
      2226236.87     13864398.74        2226175.       13864275.
        2226125.       13864175.      2226025.02     13864025.02
#Sta/Elev= 30
  4745.8  776.18  4787.4  774.86  4861.8  771.73  4898.1   767.1  4906.5  767.14
  4914.9  764.68  4928.9  757.35    4933  750.48  4933.5  749.98  4941.6  750.48
  4942.8  751.67  4947.8  751.32  4959.6   750.5  4965.2  751.67    4982  750.53
  4987.6  751.66  5003.5  750.57  5024.5  752.23  5039.5  751.16  5060.5  752.55
  5075.6  766.64  5090.6  773.76  5111.6  779.31  5132.7  782.61  5147.7  786.77
  5153.7  786.91  5162.8  789.22  5168.7  789.75  5173.2  792.92  5176.2  792.92
#Mann= 6 ,-1 , 0
  4745.8    .035       0  4787.4     .12       0    4933    .033       0
  4941.6     .12       0  4947.8    .033       0  5162.8     .07       0
Bank Sta=4933,4941.6
XS Rating Curve= 0 ,0
Exp/Cntr=0.3,0.1

Type RM Length L Ch R = 1 ,5555    ,475,475,475
BEGIN DESCRIPTION:
Guadalupe Tributary 32 12.0
END DESCRIPTION:
XS GIS Cut Line= 4
      2226574.99     13864174.96        2226525.       13863975.
        2226525.       13863875.        2226525.     13863788.12
#Sta/Elev= 30
  4793.4  772.76  4811.4  772.38  4834.6  770.26  4844.9  767.26  4852.6  762.15
  4857.8   760.7  4865.5  754.68  4896.5  753.85  4935.1  752.95    4948  752.16
  4976.3  751.78  4981.5  751.11  5015.2   750.6  5015.7   750.1  5023.4   750.1
  5023.9   750.6  5029.5  752.81  5039.5  758.44  5049.5   764.9  5069.5  774.27
  5089.5  780.12    5097  783.69    5102  783.69  5109.5  786.48  5120.4  786.99
  5139.5  785.61  5149.5  783.89  5159.5  780.81  5169.5  778.61  5186.4  777.45
#Mann= 5 ,-1 , 0
  4793.4     .12       0  4896.5    .033       0  5015.2    .033       0
  5023.9    .033       0  5120.4     .07       0
Bank Sta=5015.2,5023.9
XS Rating Curve= 0 ,0
Exp/Cntr=0.3,0.1

Type RM Length L Ch R = 1 ,5080    ,483,483,483
BEGIN DESCRIPTION:
Guadalupe Tributary 32 11.0
END DESCRIPTION:
XS GIS Cut Line= 4
      2226975.01     13864175.03        2226925.       13863975.
        2226925.       13863875.        2226925.     13863725.39
#Sta/Elev= 30
  4793.8  777.35  4806.6  776.78  4835.1  775.51  4845.4  774.48  4853.1  771.48
  4858.3  770.84  4876.3  758.98  4886.6  757.44  4894.3  750.78  4899.5  749.52
  4908.7  749.02  4935.6  748.55  4976.8  749.54  5010.5  748.36  5015.6  748.35
  5016.1  747.85  5023.9  747.85  5024.4  748.35    5030  748.43    5040  751.17
    5050  759.73    5060  764.88    5080  770.79  5097.5  774.68  5102.5  774.68
    5110  776.66  5135.3  776.16    5190  775.09    5200  776.47  5249.6  777.23
#Mann= 7 ,-1 , 0
  4793.8     .07       0  4806.6      .1       0  4908.7     .12       0
  5010.5    .033       0  5015.6     .05       0  5024.4    .033       0
  5135.3    .035       0
Bank Sta=5015.6,5024.4
XS Rating Curve= 0 ,0
Exp/Cntr=0.3,0.1

Type RM Length L Ch R = 1 ,4597    ,431,431,431
BEGIN DESCRIPTION:
Guadalupe Tributary 32 10.0
END DESCRIPTION:
XS GIS Cut Line= 4
      2227424.99     13864074.97        2227375.       13863875.
        2227375.       13863775.        2227375.     13863658.42
#Sta/Elev= 30
  4789.2  775.61  4812.4  775.18  4820.1  773.72  4830.4  769.43  4840.7  764.48
  4848.4  758.48  4853.6  757.24  4861.3  752.06  4888.4  752.19  4894.8  751.52
  4930.9  751.13  4988.3   749.3  4988.8   748.8  4996.6   748.8  4997.1   749.3
  5005.3  749.56  5015.3   751.7  5025.3  755.72  5035.3  762.77  5045.3  768.36
  5055.3  772.13  5065.3  774.66  5085.3  778.35  5100.3  779.06  5105.3  779.42
  5135.3  775.93  5155.3  775.31  5175.3  773.68  5185.3  773.43  5211.9  773.98
#Mann= 5 ,-1 , 0
  4789.2     .07       0  4888.4    .033       0  4988.3    .033       0
  4997.1    .033       0  5100.3    .035       0
Bank Sta=4988.3,4997.1
XS Rating Curve= 0 ,0
Exp/Cntr=0.3,0.1

Type RM Length L Ch R = 1 ,4166    ,462,462,462
BEGIN DESCRIPTION:
Guadalupe Tributary 32 9.0
END DESCRIPTION:
XS GIS Cut Line= 3
      2227775.01     13864025.02        2227725.       13863925.
        2227725.     13863675.03
#Sta/Elev= 30
  4883.9   778.8  4892.3  778.14  4897.9  779.08  4914.7  777.92  4920.3  778.35
  4923.7  775.17  4928.6  770.59    4937  764.47  4942.6  763.97    4965   759.1
  4973.4  755.18  4981.8   752.6  4982.9  752.01  4983.4  751.51  4991.3  751.51
  4991.8  752.01  5030.7  752.79  5135.7  754.81  5145.7  754.67  5165.7  753.21
  5175.7  756.05  5185.7  763.94  5195.7  768.33  5205.7  773.42  5215.7  777.36
  5225.7  780.58  5227.4  780.78  5235.7  781.78  5243.2  780.22  5245.7  780.22
#Mann= 6 ,-1 , 0
  4883.9    .035       0  4923.7     .07       0  4982.9     .05       0
  4991.8     .07       0  5030.7    .033       0  5227.4     .07       0
Bank Sta=4982.9,4991.8
XS Rating Curve= 0 ,0
Exp/Cntr=0.3,0.1

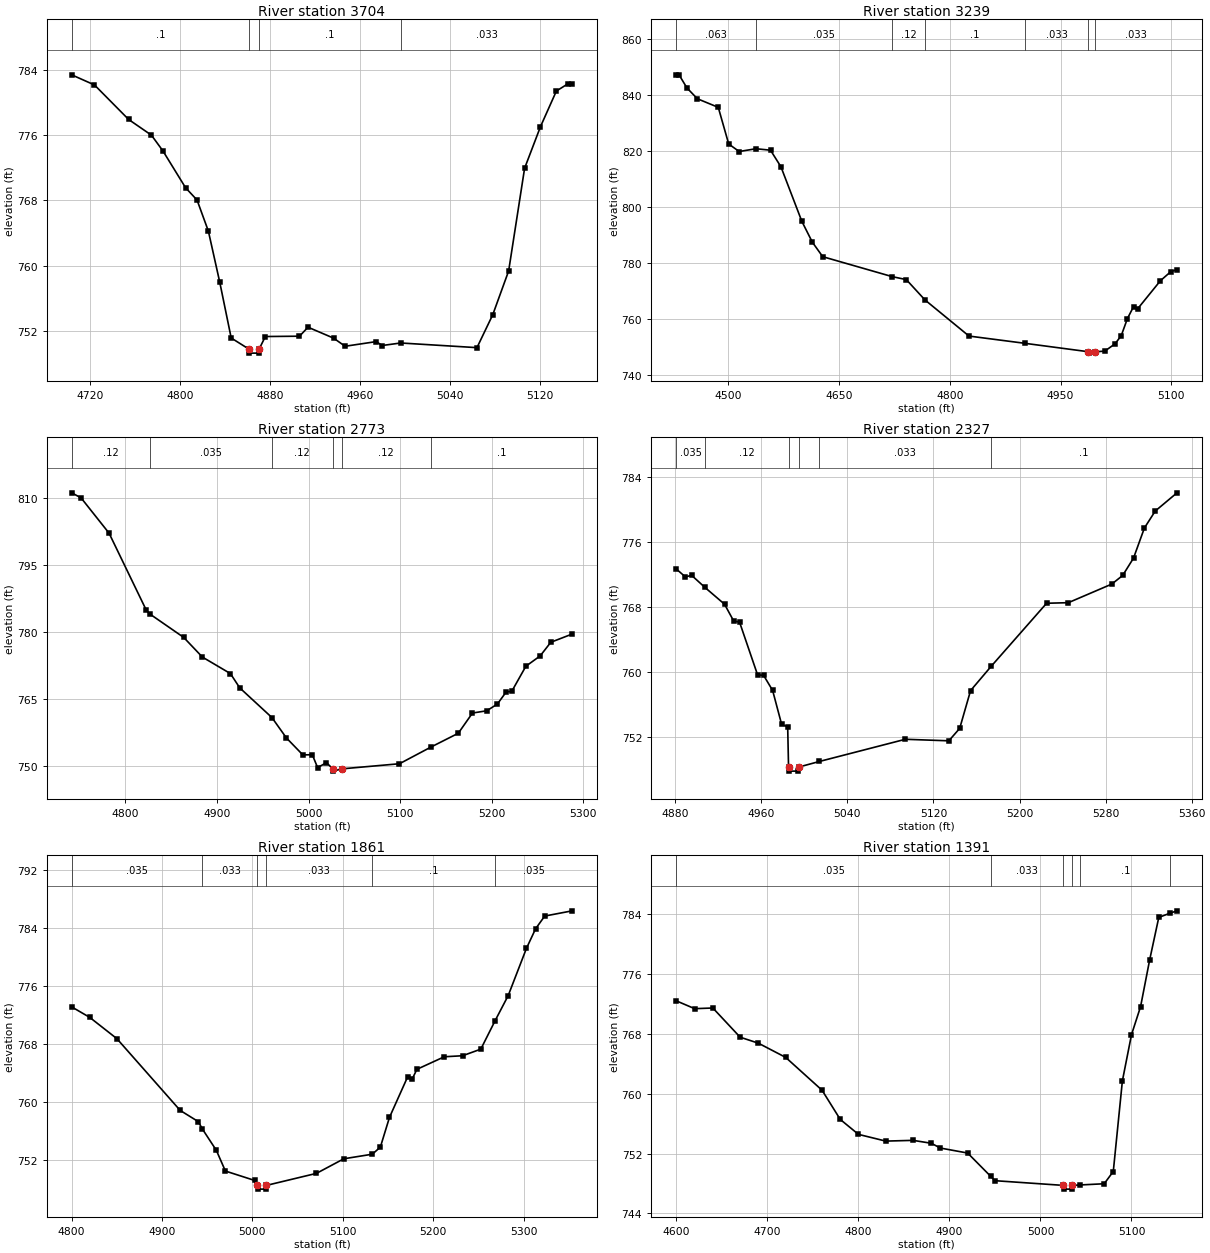
Type RM Length L Ch R = 1 ,3704    ,465,465,465
BEGIN DESCRIPTION:
Guadalupe Tributary 32 8.0
END DESCRIPTION:
XS GIS Cut Line= 3
      2228075.01     13864025.05        2228025.       13863725.
        2227925.       13863625.
#Sta/Elev= 30
  4703.5  783.35  4723.8  782.11  4754.2  777.89  4774.5  775.97  4784.7  774.05
  4804.9  769.54  4815.1  768.04  4825.2  764.23  4835.3     758  4845.5  751.17
  4861.2  749.82  4861.7  749.32  4869.9  749.32  4870.4  749.82  4875.9  751.35
  4906.3  751.39  4913.9  752.49  4936.7  751.15  4946.9  750.16  4974.7  750.73
  4979.8  750.25  4996.4  750.56  5064.3  749.99  5078.4  754.03  5092.5  759.37
  5106.7  771.92  5120.8     777    5135  781.37  5145.6  782.28  5149.1  782.28
#Mann= 4 ,-1 , 0
  4703.5      .1       0  4861.2    .033       0  4870.4      .1       0
  4996.4    .033       0
Bank Sta=4861.2,4870.4
XS Rating Curve= 0 ,0
Exp/Cntr=0.3,0.1

Type RM Length L Ch R = 1 ,3239    ,466,466,466
BEGIN DESCRIPTION:
Guadalupe Tributary 32 7.0
END DESCRIPTION:
XS GIS Cut Line= 3
      2228825.01     13864025.01        2228425.       13863625.
        2228375.       13863525.
#Sta/Elev= 30
  4430.1  847.26  4433.6  847.26  4444.3  842.58  4458.4  838.72  4486.7  835.65
  4500.8  822.58    4515  819.89  4537.7  820.88  4557.4  820.36  4571.5  814.45
  4599.8  794.98    4614  787.54  4628.1  782.35  4722.3  775.22  4741.2  774.17
  4766.5  766.91  4826.1  754.02  4901.5  751.44  4987.6  748.43  4988.1  747.93
    4997  748.43  5009.8  748.63  5023.7  751.24  5032.1  754.13  5040.5  760.27
  5048.9  764.57  5054.5   763.8  5085.2  773.78  5099.2  777.01  5107.6  777.71
#Mann= 7 ,-1 , 0
  4430.1    .063       0  4537.7    .035       0  4722.3     .12       0
  4766.5      .1       0  4901.5    .033       0  4987.6    .033       0
    4997    .033       0
Bank Sta=4987.6,4997
XS Rating Curve= 0 ,0
Exp/Cntr=0.3,0.1

Type RM Length L Ch R = 1 ,2773    ,446,446,446
BEGIN DESCRIPTION:
Guadalupe Tributary 32 6.0
END DESCRIPTION:
XS GIS Cut Line= 3
      2229074.96     13863474.99        2228825.       13863425.
      2228574.96     13863274.98
#Sta/Elev= 30
  4741.4  811.09  4751.6  809.97  4782.2  802.08  4822.9  784.85  4826.8  784.01
  4863.7  778.79  4884.1   774.4  4914.7  770.71  4924.9  767.52    4960  760.89
  4975.9  756.32  4993.8  752.54  5004.1  752.59  5009.9  749.71  5019.6  750.81
  5026.5  749.42    5027  748.92    5036  749.42  5099.3  750.57  5133.4  754.27
  5163.5  757.38    5179   761.9  5194.6   762.4  5206.2  763.91  5215.9  766.64
  5221.8  766.71  5237.3  772.35  5252.9  774.66  5264.5   777.7  5287.9  779.55
#Mann= 6 ,-1 , 0
  4741.4     .12       0  4826.8    .035       0    4960     .12       0
  5026.5     .05       0    5036     .12       0  5133.4      .1       0
Bank Sta=5026.5,5036
XS Rating Curve= 0 ,0
Exp/Cntr=0.3,0.1

Type RM Length L Ch R = 1 ,2327    ,466,466,466
BEGIN DESCRIPTION:
Guadalupe Tributary 32 5.0
END DESCRIPTION:
XS GIS Cut Line= 3
      2229024.98     13863124.99        2228925.       13863075.
      2228575.03       13863125.
#Sta/Elev= 30
  4881.1  772.61  4889.5  771.64  4895.1  771.86  4907.3  770.39  4925.8  768.29
  4934.2  766.25  4939.8  766.07  4956.5   759.6  4962.1  759.54  4970.5  757.68
  4978.9  753.49  4984.5  753.21  4985.3  748.25  4985.8  747.75  4994.3  747.75
  4994.8  748.25    5014  748.94  5093.9  751.67  5134.3  751.48  5144.4  753.01
  5154.5  757.66  5173.8  760.67  5225.2  768.41  5245.4  768.48  5285.8  770.77
  5295.9  771.83    5306  773.97  5316.1  777.67  5326.2  779.76  5346.4     782
#Mann= 6 ,-1 , 0
  4881.1    .035       0  4907.3     .12       0  4985.3     .05       0
  4994.8     .12       0    5014    .033       0  5173.8      .1       0
Bank Sta=4985.3,4994.8
XS Rating Curve= 0 ,0
Exp/Cntr=0.3,0.1

Type RM Length L Ch R = 1 ,1861    ,470,470,470
BEGIN DESCRIPTION:
Guadalupe Tributary 32 4.0
END DESCRIPTION:
XS GIS Cut Line= 3
        2229075.       13862725.        2228875.       13862725.
      2228524.95     13862674.99
#Sta/Elev= 30
  4800.1  773.12  4820.1  771.67  4850.1  768.74  4920.1  758.86  4940.1  757.32
  4944.7  756.29  4960.1  753.36  4970.1  750.51  5002.6  749.21  5005.5  748.52
    5006  748.02  5014.5  748.02    5015  748.52  5070.8  750.19  5101.1   752.2
  5132.6  752.83  5141.5  753.81  5151.6  757.91  5171.8  763.52  5176.9  763.23
  5181.9  764.52  5212.2  766.25  5232.4  766.39  5252.6   767.3  5268.5  771.24
  5282.9  774.68  5303.1  781.19  5313.2  783.88  5323.3  785.63  5353.7  786.35
#Mann= 6 ,-1 , 0
  4800.1    .035       0  4944.7    .033       0  5005.5    .033       0
    5015    .033       0  5132.6      .1       0  5268.5    .035       0
Bank Sta=5005.5,5015
XS Rating Curve= 0 ,0
Exp/Cntr=0.3,0.1

Type RM Length L Ch R = 1 ,1391    ,452,452,452
BEGIN DESCRIPTION:
Guadalupe Tributary 32 3.0
END DESCRIPTION:
XS GIS Cut Line= 3
      2229074.95       13862325.        2228675.       13862325.
      2228524.95       13862325.
#Sta/Elev= 30
    4600  772.43    4620  771.39    4640  771.48    4670  767.57    4690  766.77
    4720  764.87    4760  760.47    4780  756.56    4800  754.56    4830  753.66
    4860  753.76    4880  753.37    4890  752.73    4920  752.06  4945.4  748.93
    4950  748.36  5025.2  747.73  5025.7  747.23  5034.3  747.23  5034.8  747.73
  5043.9  747.79    5070  747.95    5080  749.59    5090  761.72    5100   767.9
    5110  771.67    5120  777.94    5130  783.61  5142.5  784.18    5150  784.49
#Mann= 6 ,-1 , 0
    4600    .035       0  4945.4    .033       0  5025.2    .033       0
  5034.8    .033       0  5043.9      .1       0  5142.5    .035       0
Bank Sta=5025.2,5034.8
XS Rating Curve= 0 ,0
Exp/Cntr=0.3,0.1

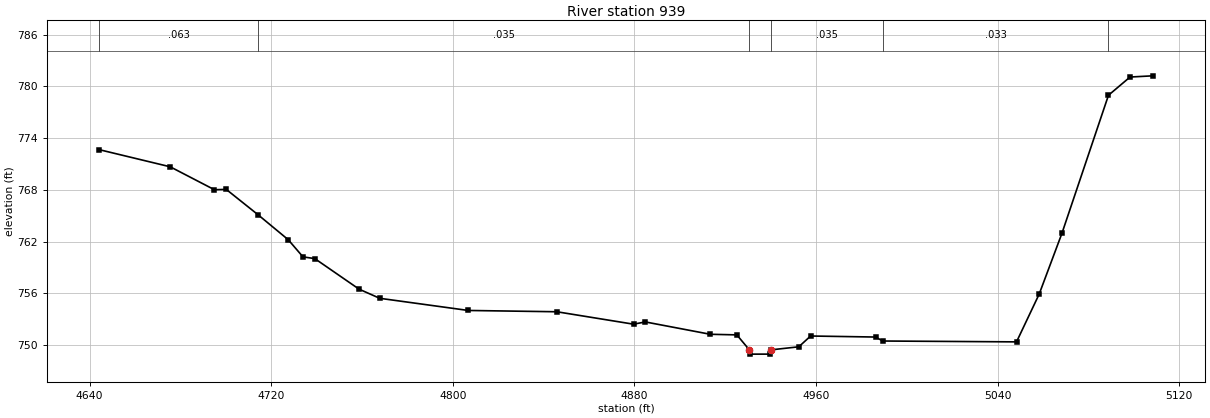
Type RM Length L Ch R = 1 ,939     ,430,430,430
BEGIN DESCRIPTION:
Guadalupe Tributary 32 2.0
END DESCRIPTION:
XS GIS Cut Line= 3
      2228974.97     13861825.01        2228625.       13861925.
      2228524.97       13861925.
#Sta/Elev= 30
  4644.3  772.66  4675.5  770.68    4695  768.02  4700.2  768.06  4714.4  765.08
  4727.5  762.23    4734  760.24  4739.2  760.04  4758.7   756.5  4767.8  755.44
  4806.8  754.03  4845.8  753.88  4879.6  752.44  4884.8   752.7  4913.4  751.27
  4925.1   751.2  4930.6  749.47  4931.1  748.97  4939.8  748.97  4940.3  749.47
  4952.4  749.82  4957.6  751.07  4986.2  750.95  4989.4  750.49  5048.3  750.39
  5058.3  755.94  5068.3  762.97  5088.8  778.97  5098.3  781.08  5108.3  781.22
#Mann= 6 ,-1 , 0
  4644.3    .063       0  4714.4    .035       0  4930.6    .033       0
  4940.3    .035       0  4989.4    .033       0  5088.8    .035       0
Bank Sta=4930.6,4940.3
XS Rating Curve= 0 ,0
Exp/Cntr=0.3,0.1