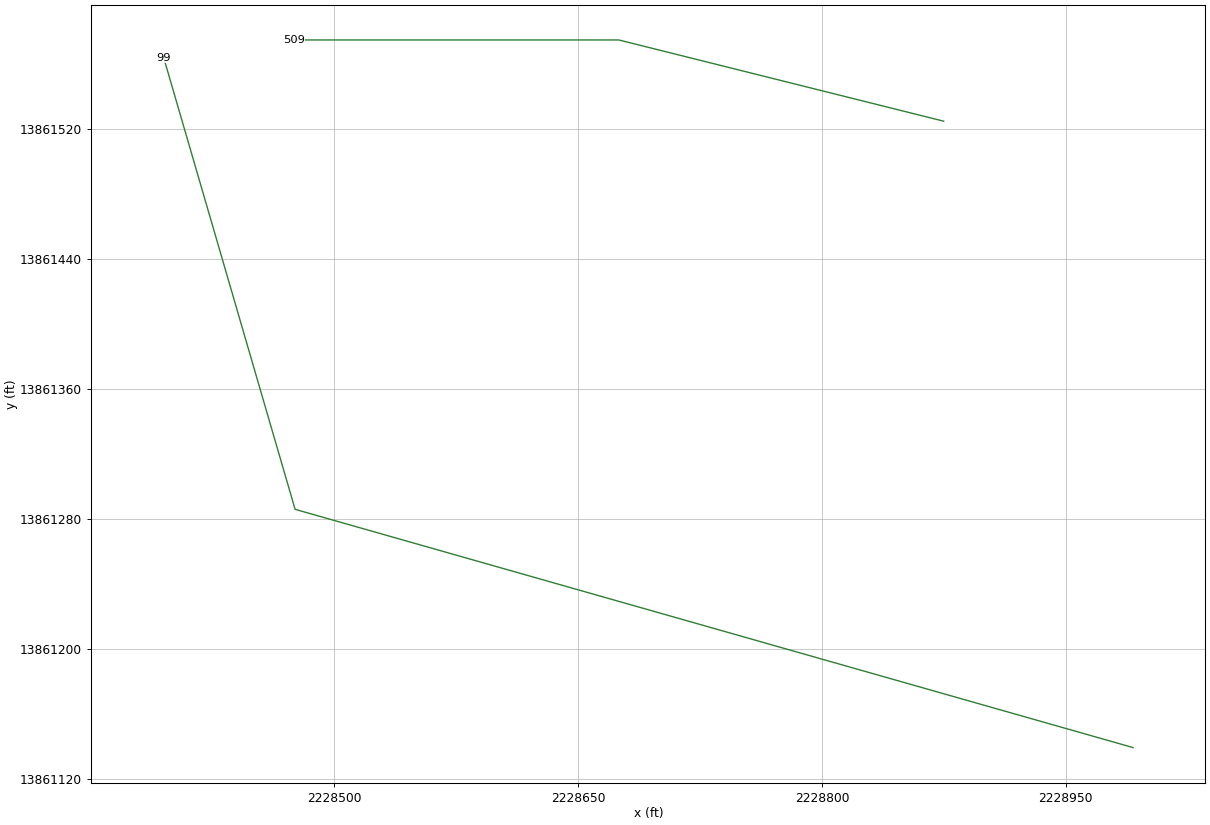
HEC-RAS study Guadalupe Tributary 32.prj: Guadalupe Tributary 32 Base Level Engineering

--- Guadalupe Tributary 32.g01 (geometry) --- (continued)

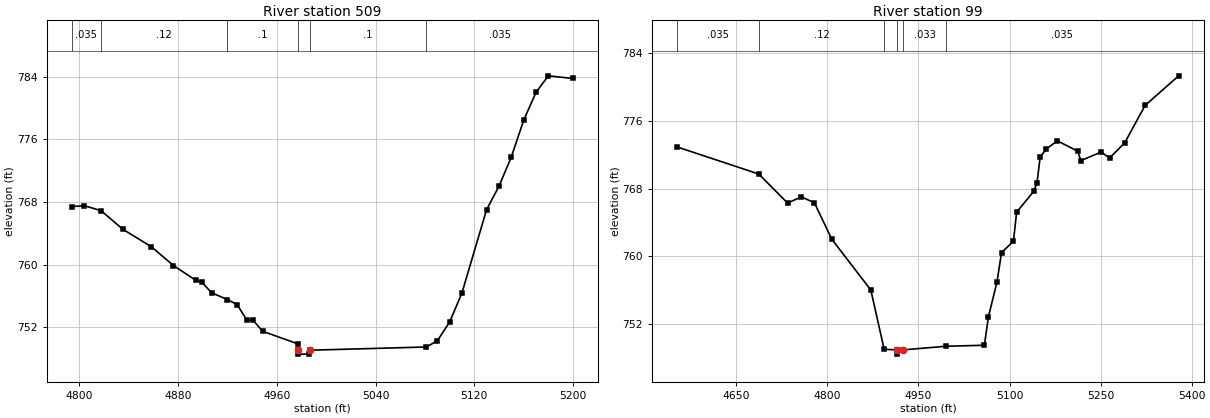
Type RM Length L Ch R = 1 ,509     ,410,410,410
BEGIN DESCRIPTION:
Guadalupe Tributary 32 1.0
END DESCRIPTION:
XS GIS Cut Line= 3
      2228874.96     13861525.01        2228675.       13861575.
      2228475.01       13861575.
#Sta/Elev= 30
  4793.9  767.41  4804.2  767.52  4817.7  766.88  4835.1  764.53  4858.3  762.29
  4876.3  759.88  4894.4  757.99  4899.5  757.71  4907.2   756.4    4920  755.53
  4927.9  754.89  4935.6  752.94  4940.7  752.91  4948.5  751.48  4976.8  749.89
  4977.1  749.06  4977.6  748.56  4986.3  748.56  4986.8  749.06  5081.1  749.47
    5090  750.25    5100  752.65    5110  756.37    5130  767.03    5140     770
    5150  773.74    5160  778.43    5170     782    5180  784.11    5200  783.77
#Mann= 6 ,-1 , 0
  4793.9    .035       0  4817.7     .12       0    4920      .1       0
  4977.1     .05       0  4986.8      .1       0  5081.1    .035       0
Bank Sta=4977.1,4986.8
XS Rating Curve= 0 ,0
Exp/Cntr=0.3,0.1

Type RM Length L Ch R = 1 ,99      ,0,0,0
BEGIN DESCRIPTION:
A19341
END DESCRIPTION:
XS GIS Cut Line= 3
      2228991.51     13861139.46      2228475.75      13861286.1
      2228394.85     13861564.17
#Sta/Elev= 30
  4552.8  772.93  4686.9  769.74  4734.4  766.31  4757.1  767.04  4778.6  766.34
  4807.3  762.03  4871.5  756.04  4893.5  749.03  4914.5  748.96    4915  748.46
  4924.2  748.96  4995.7  749.39  5058.6  749.51  5065.2  752.86  5079.4  756.99
  5086.8  760.45  5106.5  761.81  5111.7  765.23  5139.9   767.7  5145.3  768.72
  5150.5  771.74  5160.8  772.71  5178.8  773.66  5212.3  772.44  5217.5  771.32
    5251  772.34  5264.9  771.63  5289.8  773.43  5323.3  777.84  5378.6  781.34
#Mann= 6 ,-1 , 0
  4552.8    .035       0  4686.9     .12       0  4893.5    .033       0
  4914.5    .035       0  4924.2    .033       0  4995.7    .035       0
Bank Sta=4914.5,4924.2
XS Rating Curve= 0 ,0
Exp/Cntr=0.3,0.1

Chan Stop Cuts=-1
Use User Specified Reach Order=0
Composite Channel Slope=5