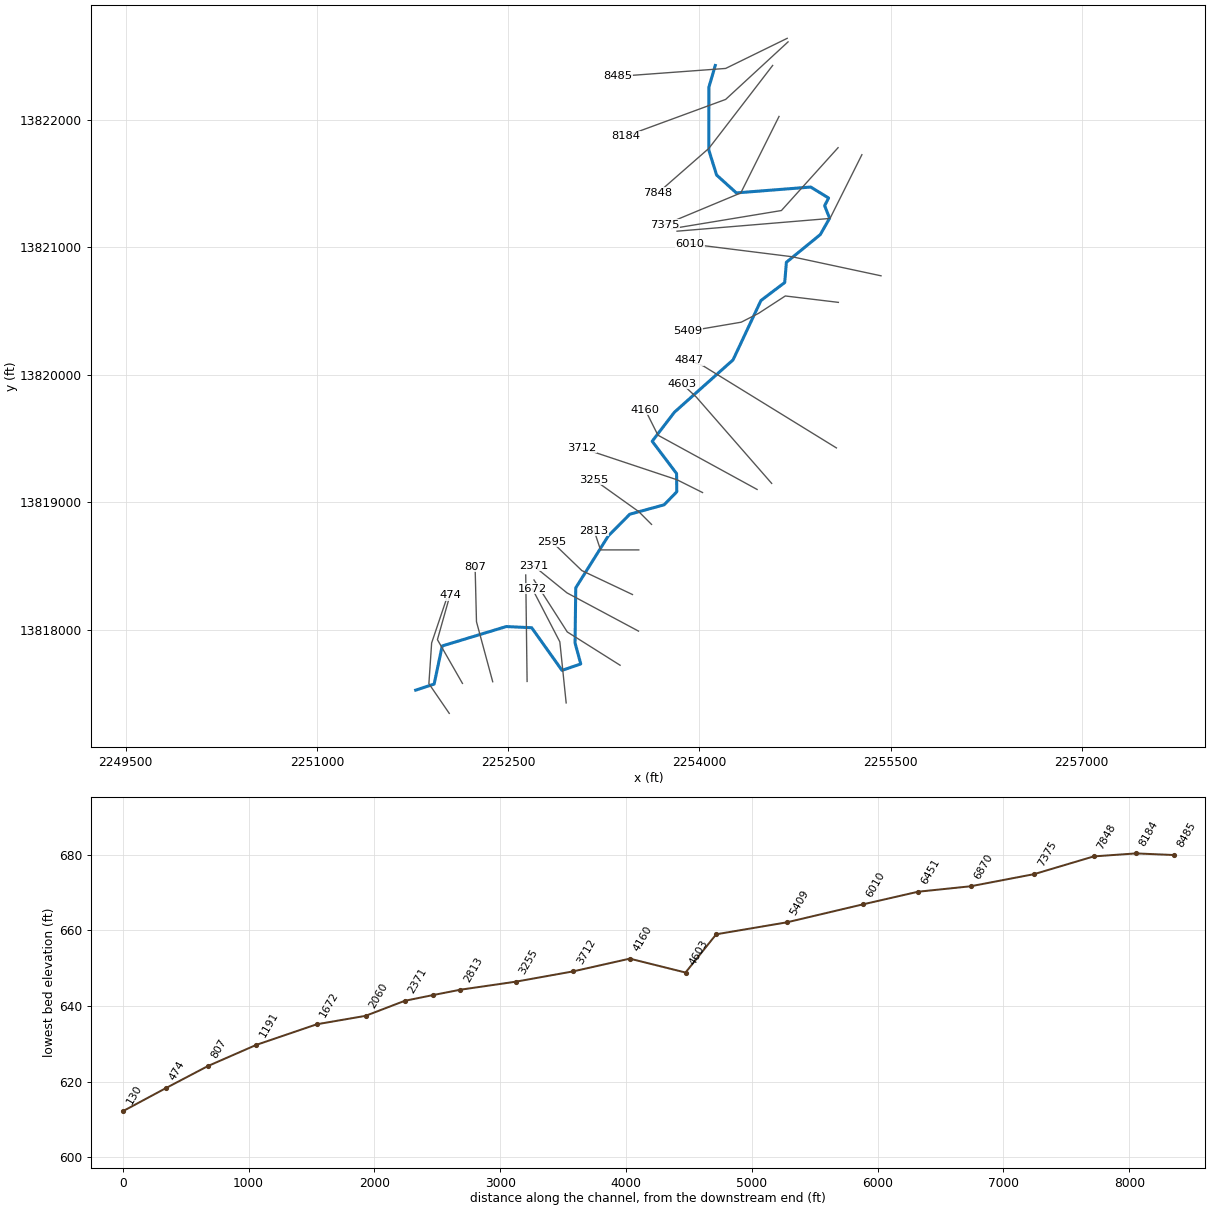
--- Guadalupe Tributary 4.prj (project) ---

Proj Title=Guadalupe Tributary 4 Base Level Engineering
Current Plan=p01
Default Exp/Contr=0.3,0.1
English Units
Geom File=g01
Flow File=f01
Plan File=p01
BEGIN DESCRIPTION:
Guadalupe Tributary 4
END DESCRIPTION:

--- Guadalupe Tributary 4.p01 (plan) ---

Plan Title=Multiple Run
Short Identifier=Multiple
Geom File=g01
Flow File=f01
Subcritical Flow
K Sum by GR= 0
Std Step Tol= 0.01
Critical Tol= 0.01
Num of Std Step Trials= 20
Max Error Tol= 0.3
Flow Tol Ratio= 0.001
Split Flow NTrial= 30
Split Flow Tol= 0.02
Split Flow Ratio= 0.02
Log Output Level= 0
Friction Slope Method= 1
Unsteady Friction Slope Method= 2
Unsteady Bridges Friction Slope Method= 1
Parabolic Critical Depth
Global Vel Dist=  1 , 1 , 1
Global Log Level= 0
CheckData=True
Encroach Param= -1, 0, 0, 0
BEGIN DESCRIPTION:
Multiple Run
END DESCRIPTION:

--- Guadalupe Tributary 4.f01 (steady flow) ---

Flow Title=Multiple
Number of Profiles=7
Profile Names=10-year,25-year,50-year,1pct_min,100-year,1pct_plu,500-year
River Rch & RM= Guadalupe Tribut,Reach-1,8485
     936    1550    2120    1404    2801    5589    4837
River Rch & RM= Guadalupe Tribut,Reach-1,6010
    1277    2150    2972    1986    3962    7906    6973
River Rch & RM= Guadalupe Tribut,Reach-1,3712
    1444    2442    3385    2268    4525    9028    8005
Boundary for River Rch & Prof#=Guadalupe Tribut,Reach-1,1
Up Type=0
Dn Type=3
Dn Slope=0.005
Boundary for River Rch & Prof#=Guadalupe Tribut,Reach-1,2
Up Type=0
Dn Type=3
Dn Slope=0.005
Boundary for River Rch & Prof#=Guadalupe Tribut,Reach-1,3
Up Type=0
Dn Type=3
Dn Slope=0.005
Boundary for River Rch & Prof#=Guadalupe Tribut,Reach-1,4
Up Type=0
Dn Type=3
Dn Slope=0.005
Boundary for River Rch & Prof#=Guadalupe Tribut,Reach-1,5
Up Type=0
Dn Type=3
Dn Slope=0.005
Boundary for River Rch & Prof#=Guadalupe Tribut,Reach-1,6
Up Type=0
Dn Type=3
Dn Slope=0.005
Boundary for River Rch & Prof#=Guadalupe Tribut,Reach-1,7
Up Type=0
Dn Type=3
Dn Slope=0.005

--- Guadalupe Tributary 4.g01 (geometry) ---

Geom Title=Existing Conditions

River Reach=Guadalupe Tribut,Reach-1
Reach XY= 30
      2254125.00     13822425.00      2254075.06     13822254.97
      2254074.57     13821759.82      2254135.52     13821565.21
      2254290.16     13821425.38      2254873.45     13821471.25
      2255013.90     13821385.32      2254982.84     13821325.10
      2255021.63     13821226.74      2254948.71     13821098.18
      2254682.81     13820881.21      2254669.64     13820722.30
      2254483.13     13820581.07      2254264.24     13820115.32
      2253804.61     13819705.16      2253630.06     13819477.29
      2253821.47     13819223.53      2253822.96     13819080.85
      2253723.54     13818978.54      2253454.91     13818905.22
      2253285.78     13818734.68      2253030.47     13818327.45
      2253025.07     13817895.03      2253069.91     13817730.44
      2252922.70     13817680.09      2252684.83     13818014.53
      2252485.51     13818023.78      2251983.10     13817871.65
      2251919.61     13817572.29      2251775.00     13817525.00

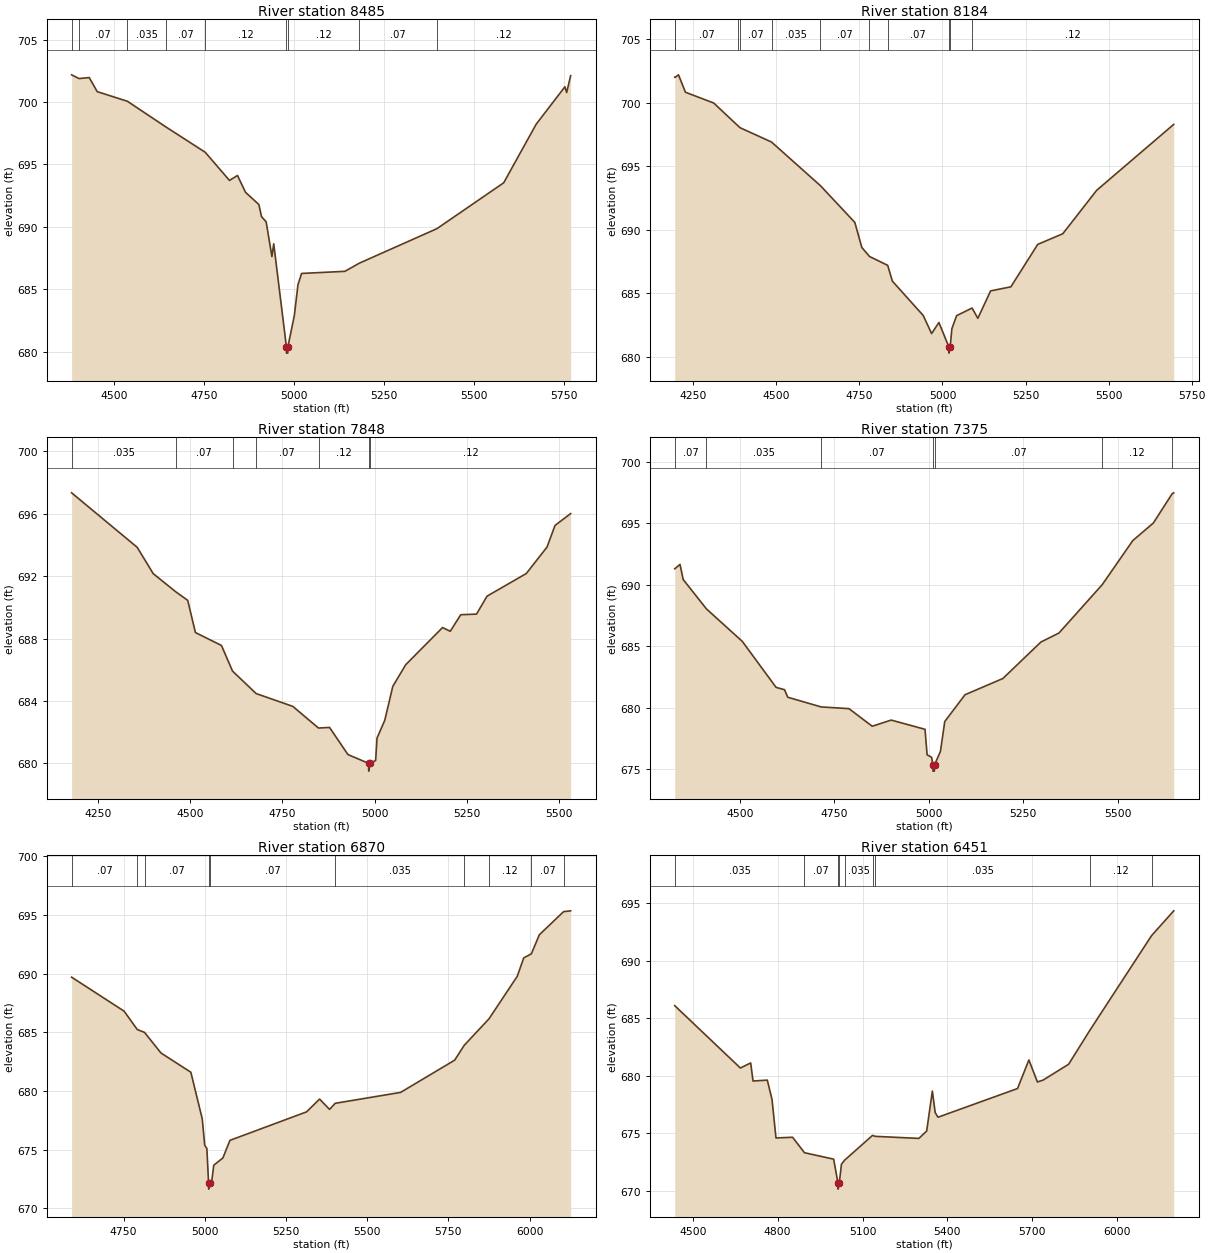
Type RM Length L Ch R = 1,8485,301,301,301
BEGIN DESCRIPTION:
A19362
END DESCRIPTION:
XS GIS Cut Line= 3
      2254688.96     13822637.75      2254206.29     13822401.62
      2253359.52     13822339.16
#Sta/Elev= 30
  4381.5  702.19  4402.3  701.89  4430.4  701.97  4452.7  700.84  4536.5  700.07
  4644.6  697.99  4752.7  695.98  4820.1  693.72  4842.3  694.12  4864.6  692.77
  4901.7  691.79  4909.1  690.82  4922.0  690.40  4938.0  687.61  4943.0  688.64
  4978.3  680.37  4978.5  679.87  4982.0  679.87  4982.3  680.37  5000.3  682.89
  5010.4  685.36  5020.4  686.26  5140.7  686.43  5181.3  687.09  5396.3  689.85
  5581.9  693.53  5672.2  698.23  5751.9  701.23  5756.9  700.77  5767.9  702.12
#Mann=9,-1,0
  4381.5   0.035       0  4402.3    0.07       0  4536.5   0.035       0
  4644.6    0.07       0  4752.7    0.12       0  4978.3    0.05       0
  4982.3    0.12       0  5181.3    0.07       0  5396.3    0.12       0
Bank Sta=4978.3,4982.3
Exp/Cntr=0.3,0.1

Type RM Length L Ch R = 1,8184,336,336,336
BEGIN DESCRIPTION:
A19363
END DESCRIPTION:
XS GIS Cut Line= 3
      2254695.87     13822609.95      2254206.29     13822158.57
      2253421.55     13821870.36
#Sta/Elev= 30
  4194.2  702.02  4195.8  702.02  4205.5  702.21  4226.5  700.84  4311.6  699.99
  4384.4  698.20  4391.3  698.04  4485.5  696.92  4632.9  693.48  4736.3  690.59
  4757.3  688.62  4780.4  687.91  4835.2  687.21  4849.2  685.97  4942.2  683.26
  4967.3  681.84  4989.3  682.71  5019.2  680.80  5019.5  680.30  5023.3  680.80
  5028.3  682.22  5042.6  683.25  5089.2  683.85  5106.5  683.04  5144.9  685.20
  5205.9  685.52  5286.7  688.86  5362.2  689.70  5464.2  693.12  5696.1  698.31
#Mann=11,-1,0
  4194.2   0.035       0  4195.8    0.07       0  4384.4   0.035       0
  4391.3    0.07       0  4485.5   0.035       0  4632.9    0.07       0
  4780.4    0.12       0  4835.2    0.07       0  5019.2    0.05       0
  5023.3    0.07       0  5089.2    0.12       0
Bank Sta=5019.2,5023.3
Exp/Cntr=0.3,0.1

Type RM Length L Ch R = 1,7848,473,473,473
BEGIN DESCRIPTION:
Guadalupe Tributary 4 16.0
END DESCRIPTION:
XS GIS Cut Line= 3
      2254575.00     13822425.00      2254075.00     13821775.00
      2253674.98     13821424.98
#Sta/Elev= 30
  4179.4  697.34  4357.0  693.85  4400.5  692.16  4461.5  691.00  4493.9  690.45
  4514.7  688.39  4585.3  687.56  4615.2  685.92  4679.1  684.48  4778.4  683.66
  4848.1  682.27  4878.0  682.31  4927.9  680.57  4983.8  680.01  4984.1  679.51
  4988.0  680.01  5002.8  680.19  5006.6  681.63  5027.5  682.76  5049.3  684.94
  5084.4  686.33  5184.1  688.71  5204.9  688.47  5233.4  689.53  5276.1  689.57
  5304.6  690.72  5410.9  692.17  5466.9  693.86  5488.7  695.25  5531.0  696.01
#Mann=7,-1,0
  4179.4   0.035       0  4461.5    0.07       0  4615.2   0.035       0
  4679.1    0.07       0  4848.1    0.12       0  4983.8    0.05       0
  4988.0    0.12       0
Bank Sta=4983.8,4988
Exp/Cntr=0.3,0.1

Type RM Length L Ch R = 1,7375,505,505,505
BEGIN DESCRIPTION:
Guadalupe Tributary 4 15.0
END DESCRIPTION:
XS GIS Cut Line= 3
      2254625.01     13822025.01      2254325.00     13821425.00
      2253725.03     13821175.01
#Sta/Elev= 30
  4328.0  691.28  4342.0  691.64  4350.4  690.41  4412.0  688.02  4506.9  685.38
  4596.3  681.64  4618.7  681.45  4627.1  680.84  4715.6  680.05  4789.2  679.91
  4850.7  678.48  4901.0  678.98  4990.5  678.23  4996.0  676.16  5008.0  675.95
  5011.4  675.33  5011.6  674.83  5015.3  674.83  5015.6  675.33  5031.3  676.44
  5042.7  678.86  5096.3  681.04  5196.5  682.36  5297.3  685.33  5345.0  686.06
  5459.7  690.00  5540.5  693.58  5594.7  695.00  5644.5  697.38  5648.8  697.46
#Mann=7,-1,0
  4328.0    0.07       0  4412.0   0.035       0  4715.6    0.07       0
  5011.4    0.05       0  5015.6    0.07       0  5459.7    0.12       0
  5644.5   0.035       0
Bank Sta=5011.4,5015.6
Exp/Cntr=0.3,0.1

Type RM Length L Ch R = 1,6870,419,419,419
BEGIN DESCRIPTION:
A19361
END DESCRIPTION:
XS GIS Cut Line= 3
      2255088.23     13821780.08      2254643.79     13821287.04
      2253782.67     13821144.68
#Sta/Elev= 30
  4589.7  689.70  4751.4  686.80  4791.7  685.24  4814.2  684.99  4865.0  683.23
  4956.9  681.59  4992.0  677.61  4999.5  675.37  5006.2  675.08  5011.5  672.12
  5011.8  671.62  5015.8  672.12  5020.4  672.13  5027.4  673.66  5055.5  674.28
  5077.2  675.78  5313.1  678.21  5353.3  679.30  5384.0  678.42  5401.2  678.94
  5602.6  679.87  5769.2  682.62  5798.6  683.89  5875.0  686.15  5961.8  689.77
  5982.0  691.35  6005.3  691.69  6030.0  693.32  6104.6  695.29  6126.3  695.36
#Mann=10,-1,0
  4589.7    0.07       0  4791.7   0.035       0  4814.2    0.07       0
  5011.5    0.05       0  5015.8    0.07       0  5401.2   0.035       0
  5798.6    0.07       0  5875.0    0.12       0  6005.3    0.07       0
  6104.6   0.035       0
Bank Sta=5011.5,5015.8
Exp/Cntr=0.3,0.1

Type RM Length L Ch R = 1,6451,441,441,441
BEGIN DESCRIPTION:
Guadalupe Tributary 4 14.0
END DESCRIPTION:
XS GIS Cut Line= 3
      2255275.01     13821725.03      2255025.00     13821225.00
      2253825.00     13821125.00
#Sta/Elev= 30
  4436.5  686.09  4668.5  680.68  4704.9  681.12  4713.2  679.55  4763.6  679.63
  4780.3  677.95  4794.3  674.61  4853.0  674.67  4894.9  673.33  4998.1  672.77
  5013.5  670.67  5013.8  670.17  5017.8  670.67  5025.6  672.33  5036.7  672.68
  5135.3  674.83  5145.7  674.75  5299.1  674.57  5326.7  675.21  5346.8  678.68
  5356.8  676.81  5366.8  676.41  5647.8  678.90  5687.9  681.38  5718.0  679.47
  5738.1  679.63  5828.4  681.01  5904.8  684.01  6121.4  692.17  6199.7  694.32
#Mann=9,-1,0
  4436.5   0.035       0  4894.9    0.07       0  5013.5    0.05       0
  5017.8    0.07       0  5036.7   0.035       0  5135.3    0.07       0
  5145.7   0.035       0  5904.8    0.12       0  6121.4    0.07       0
Bank Sta=5013.5,5017.8
Exp/Cntr=0.3,0.1

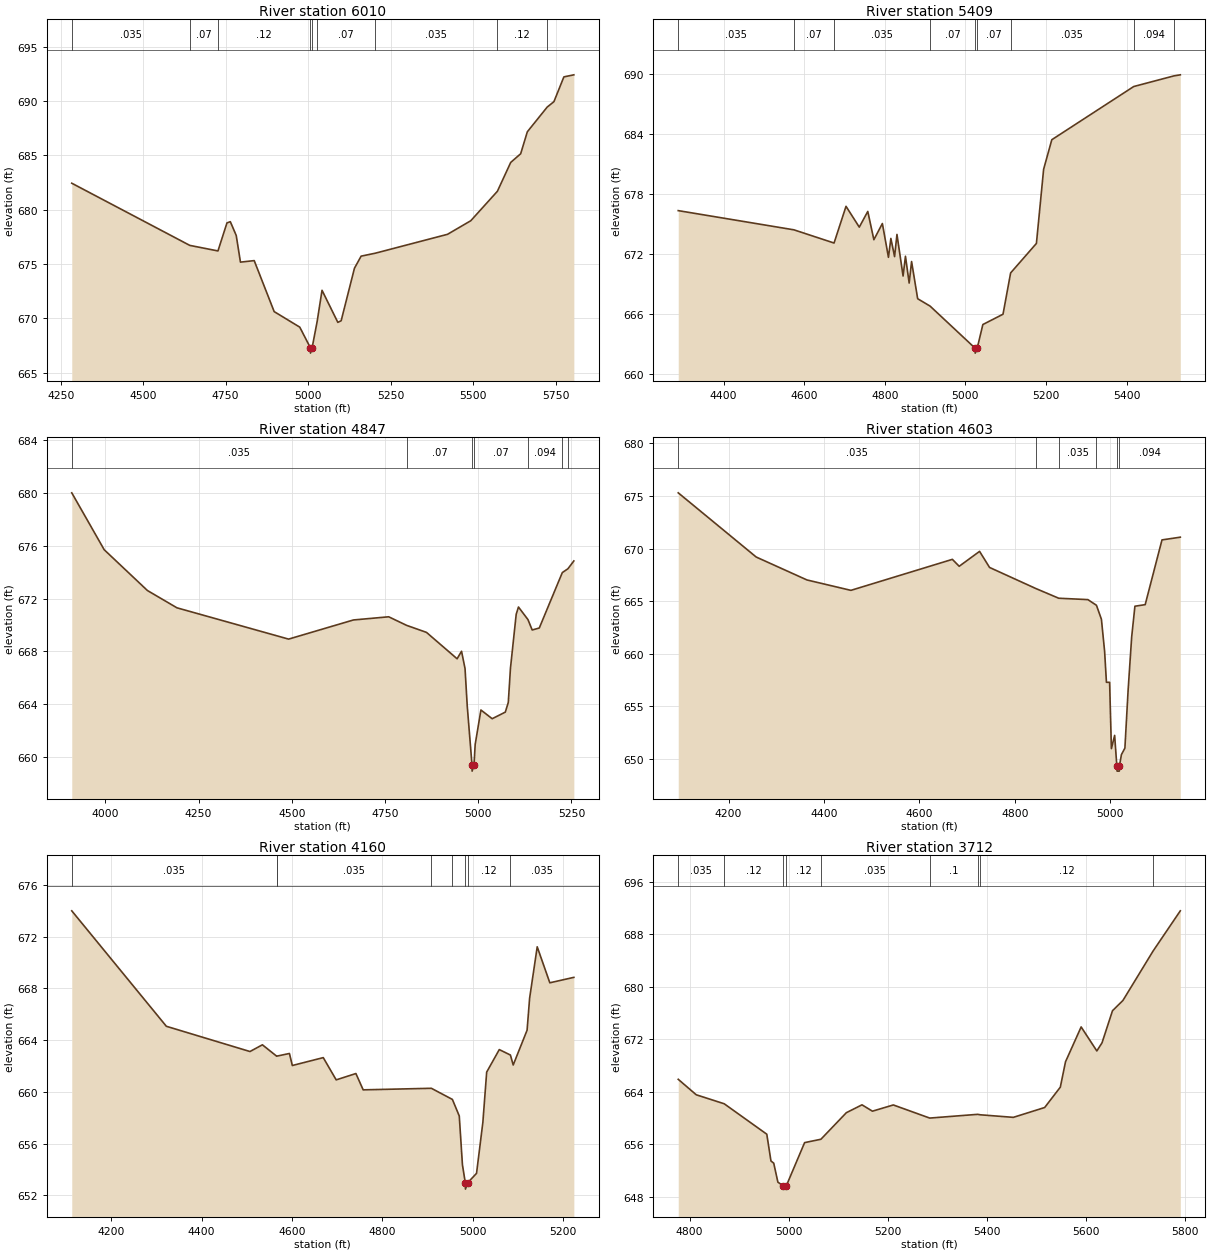
Type RM Length L Ch R = 1,6010,601,601,601
BEGIN DESCRIPTION:
Guadalupe Tributary 4 13.0
END DESCRIPTION:
XS GIS Cut Line= 3
      2255425.03     13820774.99      2254725.00     13820925.00
      2253925.04     13821024.99
#Sta/Elev= 30
  4283.5  682.44  4641.3  676.72  4726.7  676.21  4754.0  678.79  4764.2  678.90
  4782.1  677.63  4794.9  675.18  4836.6  675.32  4897.1  670.63  4974.7  669.20
  5006.8  667.31  5007.2  666.81  5012.2  667.31  5027.4  669.72  5042.2  672.59
  5090.1  669.64  5100.2  669.79  5140.5  674.62  5160.7  675.73  5203.5  676.00
  5422.7  677.74  5493.2  678.99  5573.9  681.70  5614.2  684.35  5644.4  685.15
  5664.6  687.17  5725.0  689.45  5745.2  689.94  5775.4  692.22  5805.6  692.41
#Mann=9,-1,0
  4283.5   0.035       0  4641.3    0.07       0  4726.7    0.12       0
  5006.8    0.05       0  5012.2    0.12       0  5027.4    0.07       0
  5203.5   0.035       0  5573.9    0.12       0  5725.0    0.07       0
Bank Sta=5006.8,5012.2
Exp/Cntr=0.3,0.1

Type RM Length L Ch R = 1,5409,562,562,562
BEGIN DESCRIPTION:
Guadalupe Tributary 4 12.0
END DESCRIPTION:
XS GIS Cut Line= 5
      2255090.57     13820566.69      2254674.29     13820616.86
      2254464.28     13820480.45      2254328.33     13820411.19
      2253910.65     13820339.98
#Sta/Elev= 30
  4287.5  676.34  4574.6  674.42  4674.2  673.10  4703.9  676.77  4736.8  674.69
  4757.9  676.26  4773.0  673.43  4794.1  675.05  4809.2  671.67  4815.2  673.56
  4824.4  671.74  4830.3  673.96  4845.5  669.80  4851.4  671.78  4860.6  669.10
  4866.6  671.25  4881.7  667.53  4912.6  666.79  5024.1  662.59  5024.5  662.09
  5029.5  662.59  5043.5  664.95  5093.5  665.98  5112.4  670.11  5176.4  673.06
  5194.3  680.48  5214.6  683.43  5417.9  688.75  5517.3  689.81  5533.5  689.92
#Mann=9,-1,0
  4287.5   0.035       0  4574.6    0.07       0  4674.2   0.035       0
  4912.6    0.07       0  5024.1    0.05       0  5029.5    0.07       0
  5112.4   0.035       0  5417.9   0.094       0  5517.3   0.035       0
Bank Sta=5024.1,5029.5
Exp/Cntr=0.3,0.1

Type RM Length L Ch R = 1,4847,244,244,244
BEGIN DESCRIPTION:
Guadalupe Tributary 4 11.0
END DESCRIPTION:
XS GIS Cut Line= 3
      2255075.01     13819425.00      2254031.25     13820067.87
      2253918.98     13820112.04
#Sta/Elev= 30
  3909.8  680.01  3996.8  675.70  4112.7  672.61  4191.9  671.30  4491.3  668.93
  4665.2  670.38  4759.8  670.62  4807.9  669.97  4861.1  669.44  4943.2  667.44
  4955.1  668.01  4964.5  666.70  4970.4  663.87  4983.1  659.43  4983.5  658.93
  4988.6  659.43  4991.7  660.95  5007.1  663.56  5037.3  662.90  5072.5  663.40
  5080.5  664.13  5086.3  666.72  5101.7  670.81  5107.8  671.36  5133.2  670.41
  5144.6  669.62  5163.6  669.77  5225.4  673.97  5240.5  674.26  5256.3  674.85
#Mann=7,-1,0
  3909.8   0.035       0  4807.9    0.07       0  4983.1    0.05       0
  4988.6    0.07       0  5133.2   0.094       0  5225.4   0.035       0
  5240.5   0.094       0
Bank Sta=4983.1,4988.6
Exp/Cntr=0.3,0.1

Type RM Length L Ch R = 1,4603,443,443,443
BEGIN DESCRIPTION:
Guadalupe Tributary 4 10.0
END DESCRIPTION:
XS GIS Cut Line= 3
      2254567.30     13819146.72      2253975.00     13819825.00
      2253863.80     13819927.90
#Sta/Elev= 30
  4094.6  675.30  4258.0  669.19  4364.3  667.01  4456.4  666.02  4669.0  668.97
  4683.3  668.31  4726.0  669.73  4746.9  668.20  4843.6  666.20  4891.9  665.27
  4952.9  665.14  4970.9  664.60  4981.3  663.27  4988.0  660.21  4991.8  657.27
  4998.5  657.27  5002.2  650.96  5009.0  652.22  5013.6  649.32  5014.1  648.82
  5018.7  648.82  5019.1  649.32  5023.2  650.39  5030.5  651.01  5037.3  656.57
  5044.7  661.59  5051.5  664.51  5073.0  664.66  5108.2  670.82  5146.6  671.08
#Mann=6,-1,0
  4094.6   0.035       0  4843.6   0.094       0  4891.9   0.035       0
  4970.9   0.094       0  5013.6    0.05       0  5019.1   0.094       0
Bank Sta=5013.6,5019.1
Exp/Cntr=0.3,0.1

Type RM Length L Ch R = 1,4160,448,448,448
BEGIN DESCRIPTION:
Guadalupe Tributary 4 9.0
END DESCRIPTION:
XS GIS Cut Line= 3
      2254452.94     13819099.25      2253675.00     13819525.00
      2253575.01     13819724.97
#Sta/Elev= 30
  4112.9  673.99  4322.1  665.07  4507.0  663.12  4534.5  663.64  4565.7  662.77
  4565.9  662.76  4594.3  662.97  4600.7  662.04  4669.1  662.65  4697.7  660.93
  4741.3  661.42  4757.4  660.16  4908.2  660.28  4954.7  659.42  4969.9  658.14
  4976.9  654.38  4983.2  652.99  4983.6  652.49  4988.8  652.99  5008.1  653.71
  5022.1  657.65  5030.5  661.53  5058.4  663.27  5083.0  662.85  5089.2  662.08
  5119.9  664.77  5125.5  667.24  5142.3  671.21  5170.2  668.43  5223.3  668.85
#Mann=8,-1,0
  4112.9   0.035       0  4565.7    0.12       0  4565.9   0.035       0
  4908.2     0.1       0  4954.7    0.12       0  4983.2    0.05       0
  4988.8    0.12       0  5083.0   0.035       0
Bank Sta=4983.2,4988.8
Exp/Cntr=0.3,0.1

Type RM Length L Ch R = 1,3712,457,457,457
BEGIN DESCRIPTION:
Guadalupe Tributary 4 8.0
END DESCRIPTION:
XS GIS Cut Line= 3
      2254025.04     13819074.98      2253825.00     13819175.00
      2253075.02     13819424.99
#Sta/Elev= 30
  4776.9  665.88  4813.3  663.52  4869.8  662.15  4955.8  657.51  4964.2  653.43
  4969.8  653.10  4978.2  650.20  4989.2  649.64  4989.7  649.14  4995.2  649.64
  5032.2  656.23  5065.1  656.74  5116.5  660.79  5148.1  661.99  5169.2  661.02
  5211.4  661.97  5284.9  659.97  5381.6  660.54  5387.1  660.47  5453.8  660.08
  5517.1  661.58  5548.7  664.68  5559.2  668.55  5590.8  673.86  5622.5  670.20
  5633.0  671.45  5654.1  676.33  5675.2  677.90  5736.1  685.43  5791.1  691.56
#Mann=9,-1,0
  4776.9   0.035       0  4869.8    0.12       0  4989.2    0.05       0
  4995.2    0.12       0  5065.1   0.035       0  5284.9     0.1       0
  5381.6   0.035       0  5387.1    0.12       0  5736.1     0.1       0
Bank Sta=4989.2,4995.2
Exp/Cntr=0.3,0.1

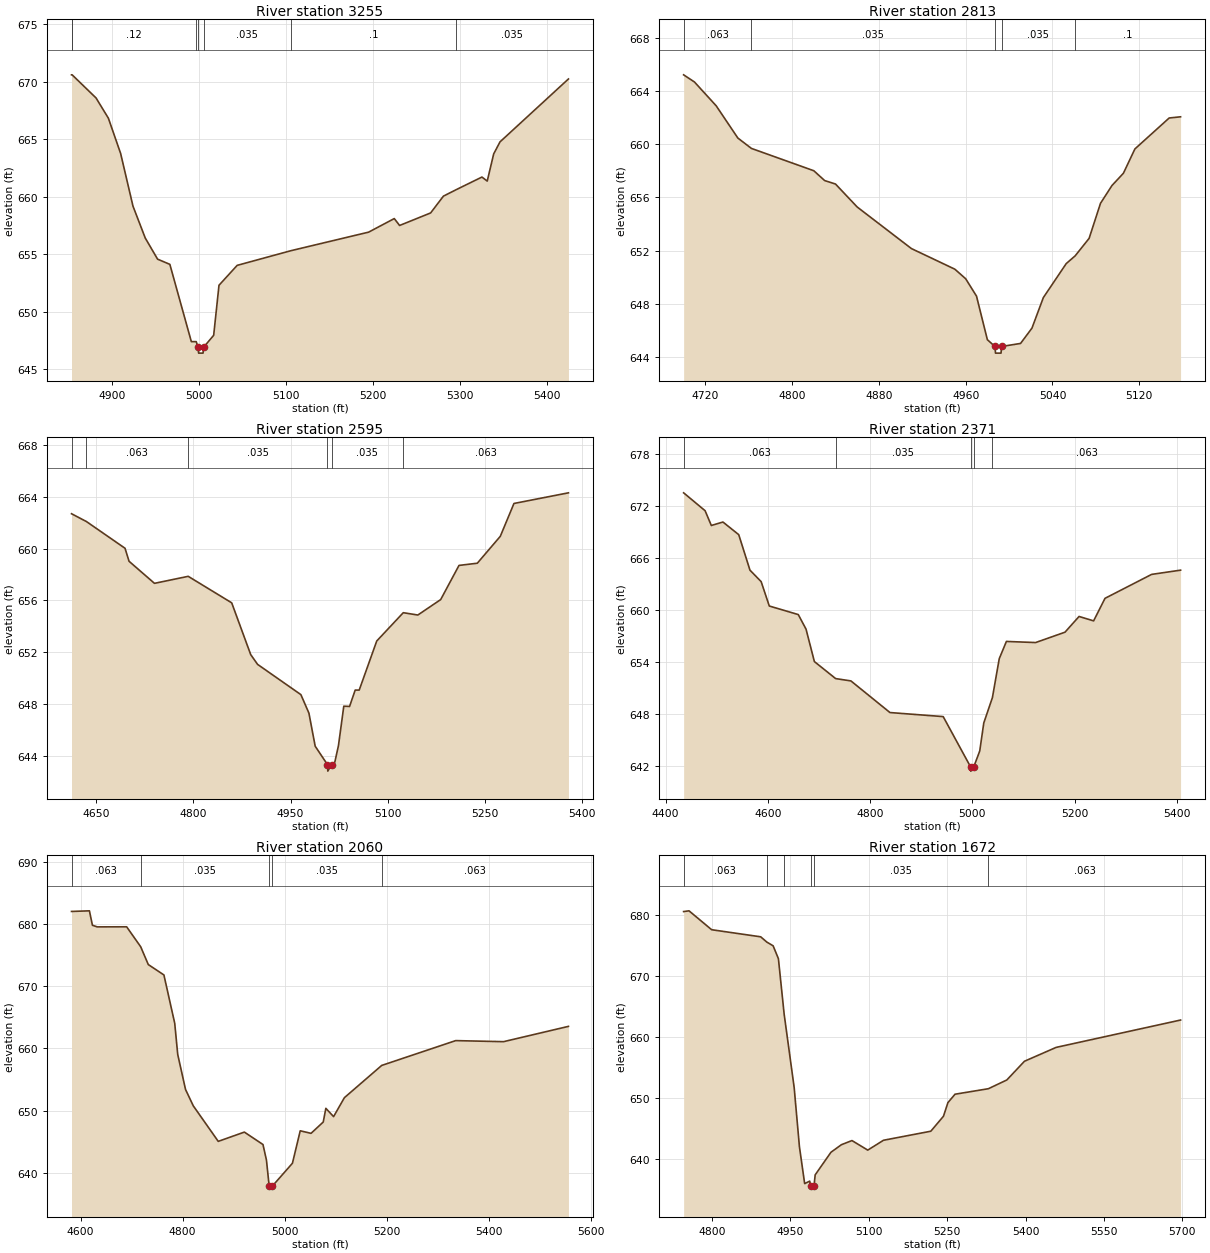
Type RM Length L Ch R = 1,3255,442,442,442
BEGIN DESCRIPTION:
Guadalupe Tributary 4 7.0
END DESCRIPTION:
XS GIS Cut Line= 3
      2253624.97     13818825.03      2253525.00     13818925.00
      2253175.00     13819175.00
#Sta/Elev= 30
  4853.0  670.61  4853.7  670.61  4881.2  668.60  4895.4  666.84  4909.5  663.77
  4923.7  659.19  4937.8  656.42  4952.0  654.58  4966.1  654.13  4990.8  647.41
  4996.4  647.41  4998.7  646.91  4999.2  646.41  5004.3  646.41  5004.8  646.91
  5016.5  647.96  5022.6  652.31  5043.5  654.04  5105.5  655.32  5194.7  656.93
  5224.2  658.11  5230.3  657.51  5266.0  658.60  5280.7  660.06  5295.3  660.62
  5325.0  661.72  5331.1  661.37  5338.5  663.73  5345.8  664.78  5424.5  670.25
#Mann=7,-1,0
  4853.0   0.035       0  4853.7    0.12       0  4996.4   0.035       0
  4998.7   0.035       0  5004.8   0.035       0  5105.5     0.1       0
  5295.3   0.035       0
Bank Sta=4998.7,5004.8
Exp/Cntr=0.3,0.1

Type RM Length L Ch R = 1,2813,218,218,218
BEGIN DESCRIPTION:
Guadalupe Tributary 4 6.0
END DESCRIPTION:
XS GIS Cut Line= 3
      2253525.02     13818625.00      2253225.00     13818625.00
      2253175.01     13818774.97
#Sta/Elev= 30
  4700.0  665.23  4710.0  664.69  4730.0  662.90  4750.0  660.47  4762.5  659.69
  4820.0  658.01  4830.0  657.27  4840.0  657.01  4860.0  655.28  4910.0  652.15
  4950.0  650.60  4960.0  649.88  4970.0  648.57  4980.0  645.29  4987.0  644.78
  4987.5  644.28  4992.6  644.28  4993.1  644.78  5010.6  645.01  5021.1  646.16
  5031.6  648.46  5052.7  651.02  5060.9  651.60  5073.8  652.92  5084.3  655.56
  5094.9  656.90  5105.4  657.82  5116.0  659.65  5147.6  661.98  5158.1  662.07
#Mann=5,-1,0
  4700.0   0.063       0  4762.5   0.035       0  4987.0   0.035       0
  4993.1   0.035       0  5060.9     0.1       0
Bank Sta=4987,4993.1
Exp/Cntr=0.3,0.1

Type RM Length L Ch R = 1,2595,224,224,224
BEGIN DESCRIPTION:
A19360
END DESCRIPTION:
XS GIS Cut Line= 3
      2253475.37     13818274.96      2253078.32     13818462.70
      2252841.70     13818690.71
#Sta/Elev= 30
  4611.6  662.68  4634.6  662.08  4694.3  660.02  4700.5  659.02  4739.8  657.32
  4791.9  657.86  4859.1  655.82  4888.5  651.83  4899.1  651.08  4966.0  648.75
  4978.4  647.33  4988.1  644.78  5007.1  643.36  5007.6  642.86  5013.4  643.36
  5018.4  643.55  5024.0  644.81  5032.3  647.86  5041.2  647.84  5049.9  649.10
  5056.1  649.10  5083.2  652.88  5124.2  655.06  5146.7  654.88  5182.0  656.07
  5210.3  658.70  5238.6  658.87  5274.1  660.94  5295.2  663.47  5379.4  664.29
#Mann=6,-1,0
  4611.6   0.035       0  4634.6   0.063       0  4791.9   0.035       0
  5007.1   0.035       0  5013.4   0.035       0  5124.2   0.063       0
Bank Sta=5007.1,5013.4
Exp/Cntr=0.3,0.1

Type RM Length L Ch R = 1,2371,311,311,311
BEGIN DESCRIPTION:
A19359
END DESCRIPTION:
XS GIS Cut Line= 3
      2253522.83     13817987.97      2252961.79     13818287.91
      2252700.68     13818499.39
#Sta/Elev= 30
  4435.2  673.56  4477.2  671.49  4489.4  669.78  4512.1  670.18  4543.0  668.72
  4565.0  664.61  4586.9  663.28  4602.8  660.46  4659.5  659.47  4674.7  657.78
  4691.0  654.03  4732.6  652.06  4762.5  651.79  4838.9  648.13  4943.0  647.66
  4996.5  641.85  4997.0  641.35  5002.9  641.85  5014.5  643.68  5022.4  646.92
  5039.3  649.86  5052.7  654.37  5066.7  656.36  5123.8  656.23  5181.3  657.43
  5208.8  659.25  5237.3  658.74  5259.6  661.35  5350.8  664.12  5407.4  664.61
#Mann=5,-1,0
  4435.2   0.063       0  4732.6   0.035       0  4996.5   0.035       0
  5002.9   0.035       0  5039.3   0.063       0
Bank Sta=4996.5,5002.9
Exp/Cntr=0.3,0.1

Type RM Length L Ch R = 1,2060,388,388,388
BEGIN DESCRIPTION:
A19358
END DESCRIPTION:
XS GIS Cut Line= 3
      2253378.27     13817720.38      2252963.95     13817981.49
      2252702.85     13818389.33
#Sta/Elev= 30
  4582.1  682.03  4617.2  682.13  4623.1  679.81  4632.5  679.55  4690.2  679.56
  4717.7  676.35  4732.6  673.49  4763.2  671.82  4784.4  664.05  4790.3  659.03
  4805.6  653.40  4820.8  650.77  4869.7  645.06  4920.9  646.55  4957.4  644.55
  4964.2  642.04  4969.5  637.88  4970.0  637.38  4975.9  637.88  5015.1  641.54
  5030.4  646.76  5051.6  646.35  5075.5  648.17  5080.6  650.37  5095.8  649.04
  5116.9  652.08  5190.1  657.27  5335.1  661.26  5428.9  661.09  5556.1  663.55
#Mann=5,-1,0
  4582.1   0.063       0  4717.7   0.035       0  4969.5   0.035       0
  4975.9   0.035       0  5190.1   0.063       0
Bank Sta=4969.5,4975.9
Exp/Cntr=0.3,0.1

Type RM Length L Ch R = 1,1672,481,481,481
BEGIN DESCRIPTION:
A19357
END DESCRIPTION:
XS GIS Cut Line= 3
      2252955.33     13817424.71      2252905.69     13817903.80
      2252690.00     13818320.08
#Sta/Elev= 30
  4746.1  680.54  4756.4  680.66  4799.7  677.57  4893.5  676.41  4905.4  675.54
  4917.3  674.94  4927.4  672.83  4938.4  663.74  4957.5  651.79  4967.6  642.08
  4977.6  636.05  4987.3  636.46  4989.1  635.65  4989.6  635.15  4995.5  635.65
  4997.7  637.48  5027.9  641.18  5048.0  642.42  5068.1  643.09  5098.3  641.53
  5128.4  643.14  5218.9  644.62  5243.1  647.07  5251.6  649.29  5265.2  650.67
  5329.0  651.57  5364.3  653.00  5398.0  656.06  5458.7  658.33  5696.6  662.80
#Mann=6,-1,0
  4746.1   0.063       0  4905.4   0.094       0  4938.4   0.035       0
  4989.1   0.035       0  4995.5   0.035       0  5329.0   0.063       0
Bank Sta=4989.1,4995.5
Exp/Cntr=0.3,0.1

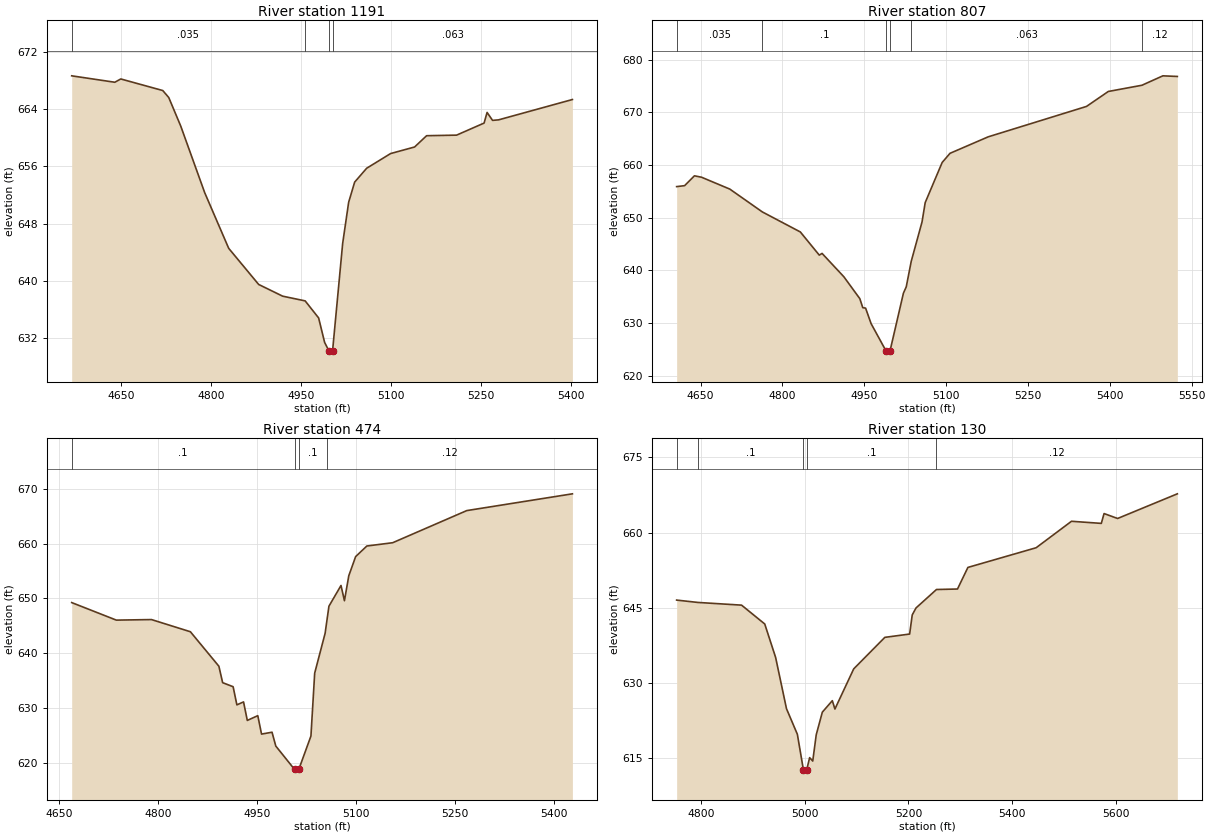
Type RM Length L Ch R = 1,1191,384,384,384
BEGIN DESCRIPTION:
A19356
END DESCRIPTION:
XS GIS Cut Line= 2
      2252648.90     13817593.09      2252638.11     13818428.22
#Sta/Elev= 30
  4567.6  668.69  4639.5  667.79  4649.5  668.25  4719.5  666.63  4729.5  665.65
  4749.5  661.65  4789.5  652.31  4829.5  644.52  4879.5  639.46  4919.5  637.82
  4957.0  637.16  4979.5  634.77  4989.5  631.34  4996.4  630.20  4996.9  629.70
  5002.3  629.70  5002.8  630.20  5019.6  645.21  5029.6  650.98  5039.6  653.80
  5059.6  655.74  5099.6  657.80  5139.6  658.72  5159.6  660.30  5209.6  660.38
  5255.5  662.07  5260.5  663.56  5269.6  662.45  5279.6  662.52  5402.8  665.37
#Mann=4,-1,0
  4567.6   0.035       0  4957.0   0.063       0  4996.4    0.05       0
  5002.8   0.063       0
Bank Sta=4996.4,5002.8
Exp/Cntr=0.3,0.1

Type RM Length L Ch R = 1,807,333,333,333
BEGIN DESCRIPTION:
A19355
END DESCRIPTION:
XS GIS Cut Line= 3
      2252379.15     13817590.94      2252251.85     13818061.33
      2252241.09     13818491.48
#Sta/Elev= 30
  4606.2  655.92  4620.8  656.10  4638.8  657.97  4651.8  657.70  4703.6  655.45
  4763.3  651.11  4832.9  647.31  4867.6  642.91  4872.7  643.24  4912.6  638.81
  4941.9  634.65  4947.3  632.94  4952.5  632.85  4962.6  629.90  4990.5  624.62
  4991.0  624.12  4997.0  624.62  5021.8  635.69  5027.0  636.90  5036.1  641.73
  5055.9  649.21  5061.7  652.88  5092.8  660.50  5107.2  662.24  5177.2  665.37
  5357.3  671.14  5397.3  673.98  5458.9  675.16  5497.3  676.95  5523.8  676.83
#Mann=6,-1,0
  4606.2   0.035       0  4763.3     0.1       0  4990.5    0.05       0
  4997.0     0.1       0  5036.1   0.063       0  5458.9    0.12       0
Bank Sta=4990.5,4997
Exp/Cntr=0.3,0.1

Type RM Length L Ch R = 1,474,344,344,344
BEGIN DESCRIPTION:
A19354
END DESCRIPTION:
XS GIS Cut Line= 3
      2252141.80     13817577.96      2251945.43     13817921.07
      2252044.28     13818271.36
#Sta/Elev= 30
  4669.1  649.24  4736.8  646.04  4790.1  646.14  4849.1  643.92  4892.3  637.63
  4898.0  634.63  4913.9  633.89  4919.6  630.58  4929.7  631.12  4935.4  627.74
  4951.3  628.61  4957.0  625.25  4972.9  625.59  4978.6  623.07  5007.0  618.81
  5007.5  618.31  5013.5  618.81  5031.9  624.89  5037.6  636.37  5053.4  643.63
  5056.3  646.11  5059.2  648.58  5077.5  652.36  5082.7  649.58  5089.3  654.13
  5099.7  657.63  5116.7  659.56  5155.9  660.16  5268.2  666.02  5428.4  669.08
#Mann=4,-1,0
  4669.1     0.1       0  5007.0    0.05       0  5013.5     0.1       0
  5056.3    0.12       0
Bank Sta=5007,5013.5
Exp/Cntr=0.3,0.1

Type RM Length L Ch R = 1,130,0,0,0
BEGIN DESCRIPTION:
A19353
END DESCRIPTION:
XS GIS Cut Line= 4
      2252038.24     13817342.71      2251878.53     13817575.80
      2251900.11     13817895.17      2252016.56     13818240.20
#Sta/Elev= 30
  4752.4  646.51  4793.5  646.04  4877.8  645.50  4922.5  641.74  4943.5  635.07
  4964.5  624.83  4985.5  619.72  4997.1  612.67  4997.6  612.17  5003.6  612.67
  5009.2  615.06  5015.2  614.38  5021.9  619.61  5033.7  624.14  5053.0  626.43
  5058.0  624.76  5094.3  632.78  5154.4  639.07  5202.3  639.73  5207.3  643.55
  5214.6  644.94  5254.1  648.62  5294.7  648.72  5314.8  653.03  5446.6  656.96
  5514.8  662.24  5572.4  661.82  5577.7  663.78  5603.9  662.80  5719.2  667.72
#Mann=5,-1,0
  4752.4   0.035       0  4793.5     0.1       0  4997.1    0.05       0
  5003.6     0.1       0  5254.1    0.12       0
Bank Sta=4997.1,5003.6
Exp/Cntr=0.3,0.1

Chan Stop Cuts=-1