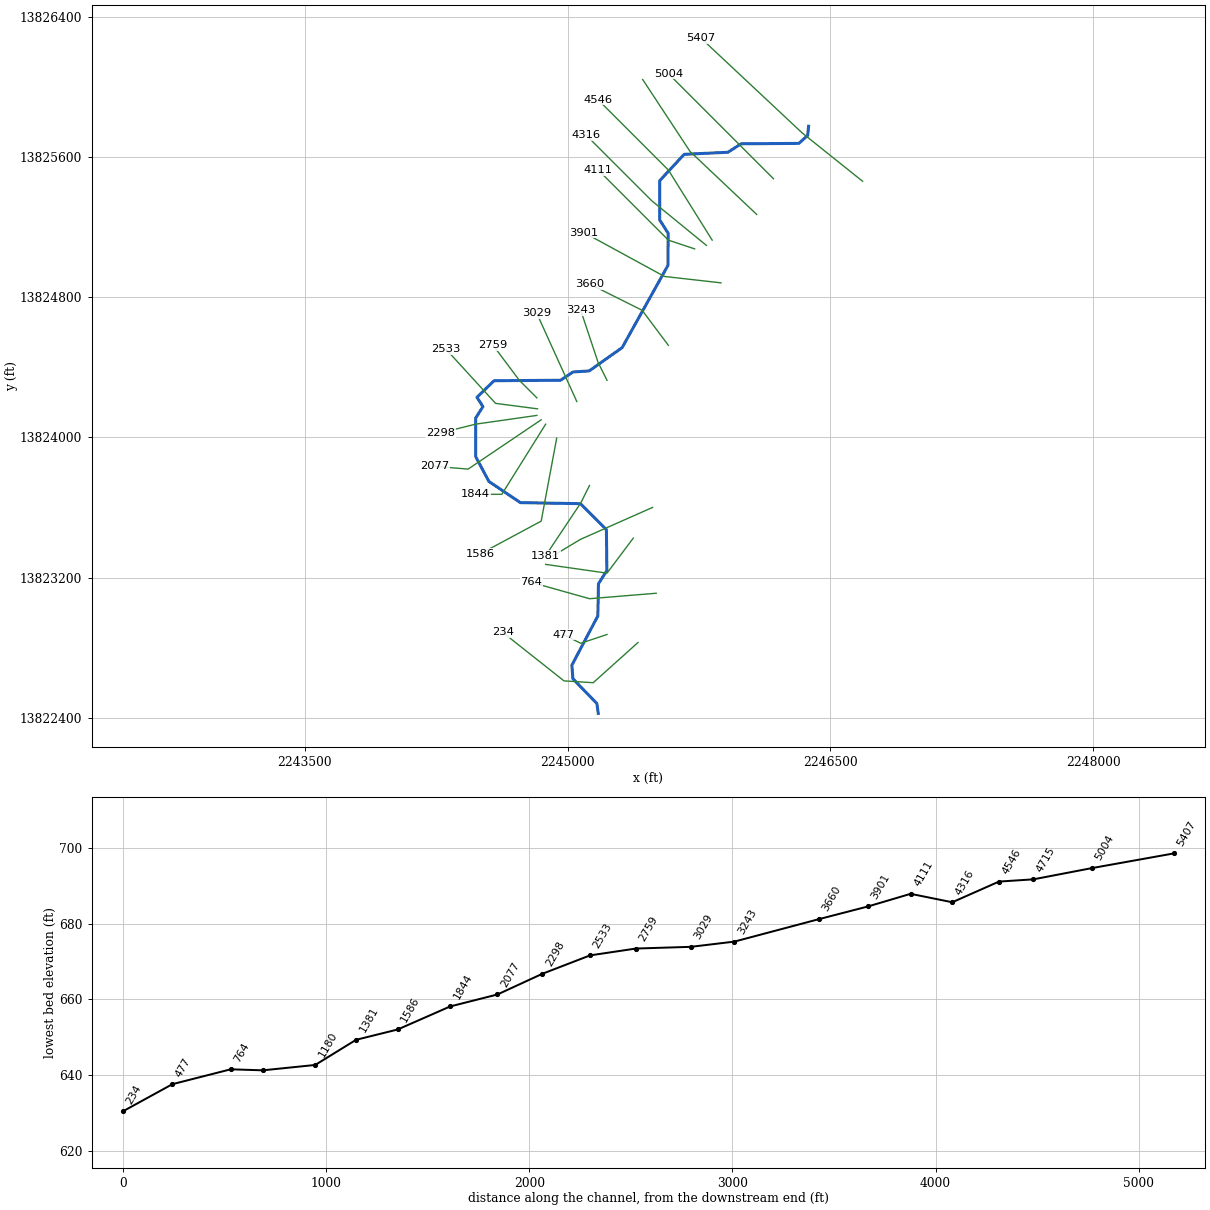
--- Guadalupe Tributary 7.prj (project) ---

Proj Title=Guadalupe Tributary 7 Base Level Engineering
Current Plan=p01
Default Exp/Contr=0.3,0.1
English Units
Geom File=g01
Flow File=f01
Plan File=p01
BEGIN DESCRIPTION:
Guadalupe Tributary 7
END DESCRIPTION:

--- Guadalupe Tributary 7.p01 (plan) ---

Plan Title=Multiple Run
Short Identifier=Multiple
Geom File=g01
Flow File=f01
Subcritical Flow
K Sum by GR= 0
Std Step Tol= 0.01
Critical Tol= 0.01
Num of Std Step Trials= 20
Max Error Tol= 0.3
Flow Tol Ratio= 0.001
Split Flow NTrial= 30
Split Flow Tol= 0.02
Split Flow Ratio= 0.02
Log Output Level= 0
Friction Slope Method= 1
Unsteady Friction Slope Method= 2
Unsteady Bridges Friction Slope Method= 1
Parabolic Critical Depth
Global Vel Dist=  1 , 1 , 1
Global Log Level= 0
CheckData=True
Encroach Param= -1, 0, 0, 0
BEGIN DESCRIPTION:
Multiple Run
END DESCRIPTION:

--- Guadalupe Tributary 7.f01 (steady flow) ---

Flow Title=Multiple
Number of Profiles=7
Profile Names=10-year,25-year,50-year,1pct_min,100-year,1pct_plu,500-year
River Rch & RM= Guadalupe Tribut,Reach-1,5407
    1149    1951    2715    1830    3652    7286    6537
River Rch & RM= Guadalupe Tribut,Reach-1,4715
    1486    2549    3571    2420    4828    9633    8738
Boundary for River Rch & Prof#=Guadalupe Tribut,Reach-1,1
Up Type=0
Dn Type=3
Dn Slope=0.005
Boundary for River Rch & Prof#=Guadalupe Tribut,Reach-1,2
Up Type=0
Dn Type=3
Dn Slope=0.005
Boundary for River Rch & Prof#=Guadalupe Tribut,Reach-1,3
Up Type=0
Dn Type=3
Dn Slope=0.005
Boundary for River Rch & Prof#=Guadalupe Tribut,Reach-1,4
Up Type=0
Dn Type=3
Dn Slope=0.005
Boundary for River Rch & Prof#=Guadalupe Tribut,Reach-1,5
Up Type=0
Dn Type=3
Dn Slope=0.005
Boundary for River Rch & Prof#=Guadalupe Tribut,Reach-1,6
Up Type=0
Dn Type=3
Dn Slope=0.005
Boundary for River Rch & Prof#=Guadalupe Tribut,Reach-1,7
Up Type=0
Dn Type=3
Dn Slope=0.005

--- Guadalupe Tributary 7.g01 (geometry) ---

Geom Title=Existing Conditions

River Reach=Guadalupe Tribut,Reach-1
Reach XY= 30
      2246375.00     13825775.00      2246369.87     13825722.05
      2246319.31     13825676.93      2245990.22     13825674.48
      2245914.50     13825626.22      2245665.20     13825614.52
      2245526.05     13825464.57      2245525.52     13825240.22
      2245573.78     13825164.49      2245572.76     13824980.93
      2245311.38     13824511.76      2245123.42     13824378.82
      2245030.98     13824372.64      2244959.78     13824325.52
      2244580.83     13824322.94      2244482.99     13824228.35
      2244517.19     13824175.10      2244475.65     13824109.84
      2244475.51     13823890.21      2244551.27     13823748.12
      2244730.93     13823627.24      2245073.54     13823621.46
      2245221.46     13823473.54      2245224.48     13823240.22
      2245176.22     13823164.49      2245172.76     13822980.93
      2245024.58     13822700.00      2245030.40     13822622.57
      2245167.24     13822481.21      2245175.00     13822425.00

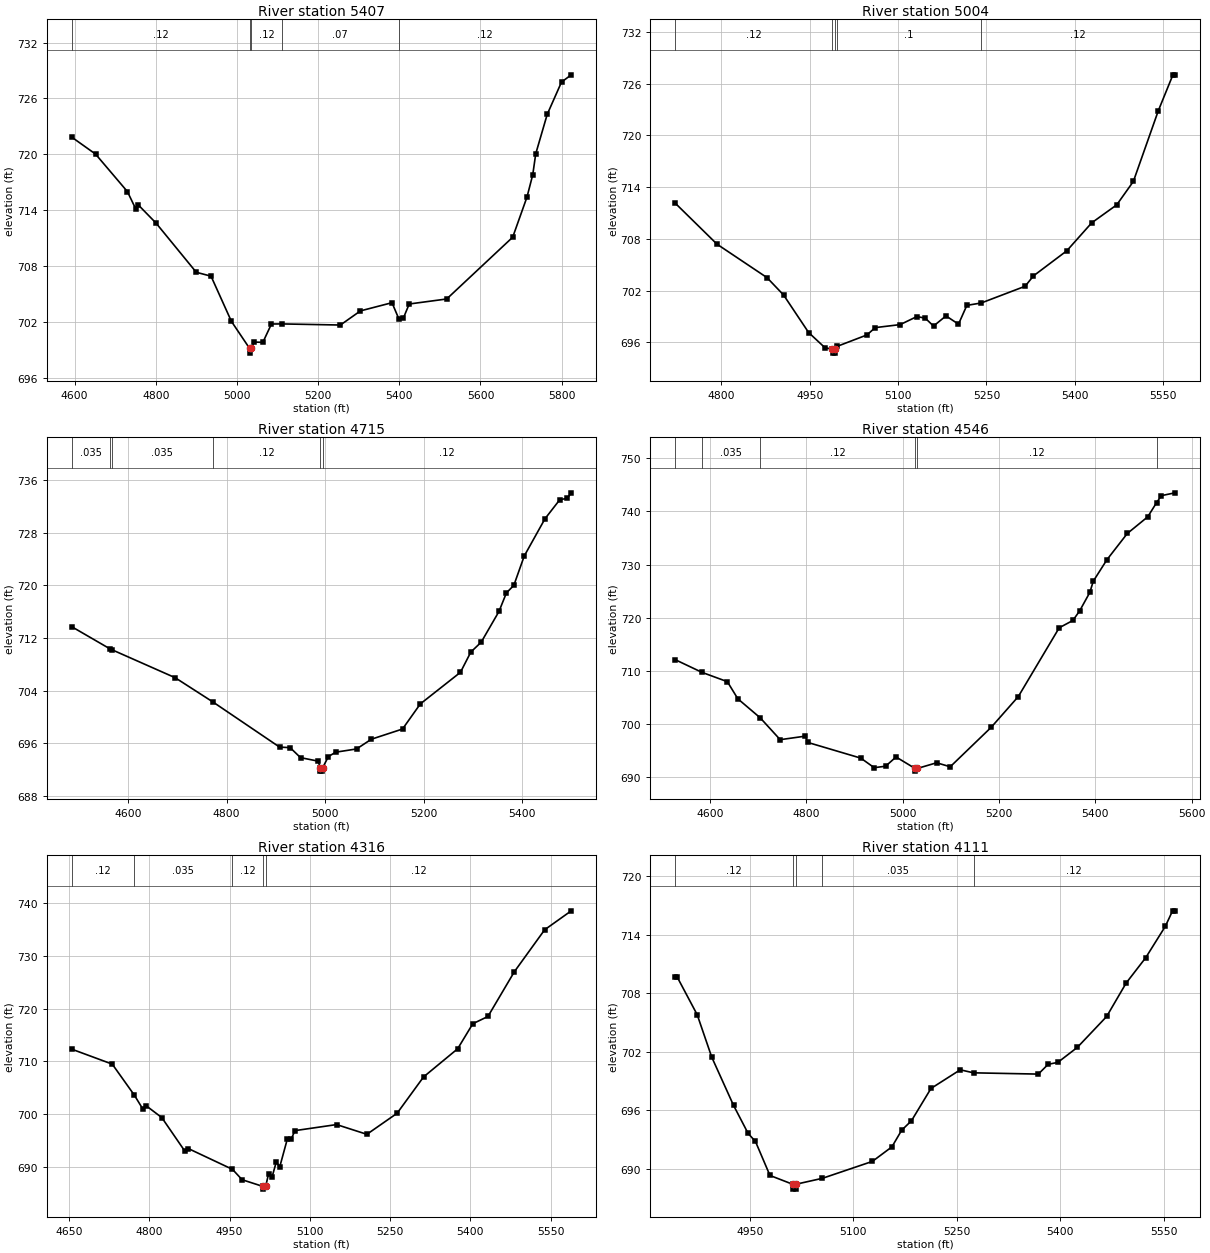
Type RM Length L Ch R = 1,5407,403,403,403
BEGIN DESCRIPTION:
A19400
END DESCRIPTION:
XS GIS Cut Line= 3
      2246683.13     13825460.89      2246338.34     13825736.72
      2245762.29     13826276.25
#Sta/Elev= 30
  4592.8  721.84  4651.7  720.01  4730.2  715.98  4751.0  714.09  4757.4  714.53
  4800.6  712.60  4899.8  707.31  4936.2  706.89  4986.3  702.04  5031.3  699.12
  5031.5  698.62  5035.3  699.12  5042.5  699.81  5063.9  699.78  5085.0  701.75
  5110.1  701.76  5254.9  701.64  5304.3  703.16  5382.0  704.04  5398.7  702.32
  5410.3  702.41  5424.4  703.90  5516.8  704.44  5679.4  711.08  5714.6  715.40
  5728.8  717.80  5736.1  720.04  5764.4  724.28  5799.6  727.75  5823.6  728.53
#Mann=5,-1,0
  4592.8    0.12       0  5031.3    0.05       0  5035.3    0.12       0
  5110.1    0.07       0  5398.7    0.12       0
Bank Sta=5031.3,5035.3
Exp/Cntr=0.3,0.1

Type RM Length L Ch R = 1,5004,289,289,289
BEGIN DESCRIPTION:
Guadalupe Tributary 7 11.0
END DESCRIPTION:
XS GIS Cut Line= 3
      2246175.00     13825475.00      2245975.00     13825675.00
      2245575.02     13826074.98
#Sta/Elev= 30
  4721.7  712.12  4792.4  707.38  4877.3  703.50  4905.5  701.48  4948.0  697.13
  4976.3  695.33  4988.3  695.24  4988.6  694.74  4992.2  694.74  4992.4  695.24
  4996.2  695.52  5047.0  696.85  5061.1  697.70  5103.5  698.05  5131.8  698.98
  5146.0  698.80  5160.1  697.88  5181.3  699.06  5202.5  698.10  5216.7  700.28
  5241.2  700.56  5315.7  702.50  5329.8  703.70  5386.4  706.61  5428.8  709.86
  5471.2  711.94  5499.5  714.66  5541.9  722.87  5566.7  727.03  5570.2  727.03
#Mann=5,-1,0
  4721.7    0.12       0  4988.3    0.05       0  4992.4    0.12       0
  4996.2     0.1       0  5241.2    0.12       0
Bank Sta=4988.3,4992.4
Exp/Cntr=0.3,0.1

Type RM Length L Ch R = 1,4715,169,169,169
BEGIN DESCRIPTION:
A19399
END DESCRIPTION:
XS GIS Cut Line= 3
      2246078.70     13825271.87      2245698.48     13825631.25
      2245428.57     13826041.31
#Sta/Elev= 30
  4485.3  713.72  4562.5  710.37  4566.2  710.24  4695.4  705.96  4772.3  702.26
  4907.4  695.41  4928.8  695.33  4949.9  693.81  4985.5  693.28  4990.1  692.26
  4990.4  691.76  4994.4  691.76  4994.7  692.26  5006.5  693.98  5021.4  694.64
  5063.6  695.13  5093.7  696.61  5156.9  698.16  5193.1  701.98  5274.5  706.78
  5295.5  709.85  5316.6  711.36  5352.7  716.03  5367.8  718.85  5382.9  720.00
  5404.0  724.46  5446.1  730.12  5476.2  733.02  5491.3  733.22  5499.4  734.06
#Mann=6,-1,0
  4485.3   0.035       0  4562.5    0.12       0  4566.2   0.035       0
  4772.3    0.12       0  4990.1    0.05       0  4994.7    0.12       0
Bank Sta=4990.1,4994.7
Exp/Cntr=0.3,0.1

Type RM Length L Ch R = 1,4546,230,230,230
BEGIN DESCRIPTION:
Guadalupe Tributary 7 10.0
END DESCRIPTION:
XS GIS Cut Line= 3
      2245825.02     13825124.97      2245575.00     13825525.00
      2245175.01     13825924.99
#Sta/Elev= 30
  4528.0  712.10  4583.0  709.74  4635.9  707.98  4657.7  704.76  4704.1  701.19
  4745.6  697.08  4797.5  697.74  4803.4  696.55  4913.1  693.61  4940.8  691.82
  4964.4  692.09  4986.2  693.83  5025.7  691.67  5026.0  691.17  5030.3  691.67
  5070.4  692.74  5098.7  691.99  5183.6  699.39  5240.1  705.19  5325.0  718.11
  5353.3  719.48  5367.4  721.28  5388.6  724.76  5395.7  726.86  5424.0  730.89
  5466.4  735.83  5508.8  738.96  5527.1  741.61  5537.1  742.94  5565.4  743.47
#Mann=6,-1,0
  4528.0    0.12       0  4583.0   0.035       0  4704.1    0.12       0
  5025.7    0.05       0  5030.3    0.12       0  5527.1    0.07       0
Bank Sta=5025.7,5030.3
Exp/Cntr=0.3,0.1

Type RM Length L Ch R = 1,4316,205,205,205
BEGIN DESCRIPTION:
A19398
END DESCRIPTION:
XS GIS Cut Line= 3
      2245792.24     13825094.79      2245479.73     13825350.00
      2245104.74     13825725.00
#Sta/Elev= 30
  4654.8  712.31  4730.7  709.46  4771.8  703.59  4788.2  700.87  4794.6  701.51
  4823.3  699.30  4866.4  692.92  4872.9  693.41  4955.4  689.46  4973.4  687.49
  5012.7  686.20  5013.0  685.70  5017.4  686.20  5022.9  688.63  5029.4  688.01
  5037.3  690.87  5043.7  689.91  5058.1  695.29  5065.2  695.21  5072.2  696.82
  5150.0  697.97  5206.6  696.12  5263.1  700.12  5312.6  707.03  5376.3  712.38
  5404.6  717.14  5432.9  718.52  5482.3  727.03  5538.9  735.00  5588.6  738.60
#Mann=5,-1,0
  4654.8    0.12       0  4771.8   0.035       0  4955.4    0.12       0
  5012.7    0.05       0  5017.4    0.12       0
Bank Sta=5012.7,5017.4
Exp/Cntr=0.3,0.1

Type RM Length L Ch R = 1,4111,210,210,210
BEGIN DESCRIPTION:
Guadalupe Tributary 7 9.0
END DESCRIPTION:
XS GIS Cut Line= 3
      2245725.02     13825074.99      2245575.00     13825125.00
      2245175.01     13825524.99
#Sta/Elev= 30
  4842.3  709.64  4845.0  709.64  4873.9  705.79  4895.0  701.44  4926.6  696.50
  4947.7  693.63  4958.3  692.81  4979.3  689.33  5012.2  688.43  5012.6  687.93
  5016.6  687.93  5016.9  688.43  5055.4  689.04  5127.7  690.77  5156.0  692.26
  5170.1  693.96  5184.3  694.93  5212.6  698.24  5255.0  700.15  5274.2  699.84
  5368.1  699.71  5382.3  700.71  5396.4  700.91  5424.7  702.45  5467.1  705.61
  5495.4  709.04  5523.7  711.63  5552.0  714.83  5562.6  716.43  5566.1  716.43
#Mann=5,-1,0
  4842.3    0.12       0  5012.2    0.05       0  5016.9    0.12       0
  5055.4   0.035       0  5274.2    0.12       0
Bank Sta=5012.2,5016.9
Exp/Cntr=0.3,0.1

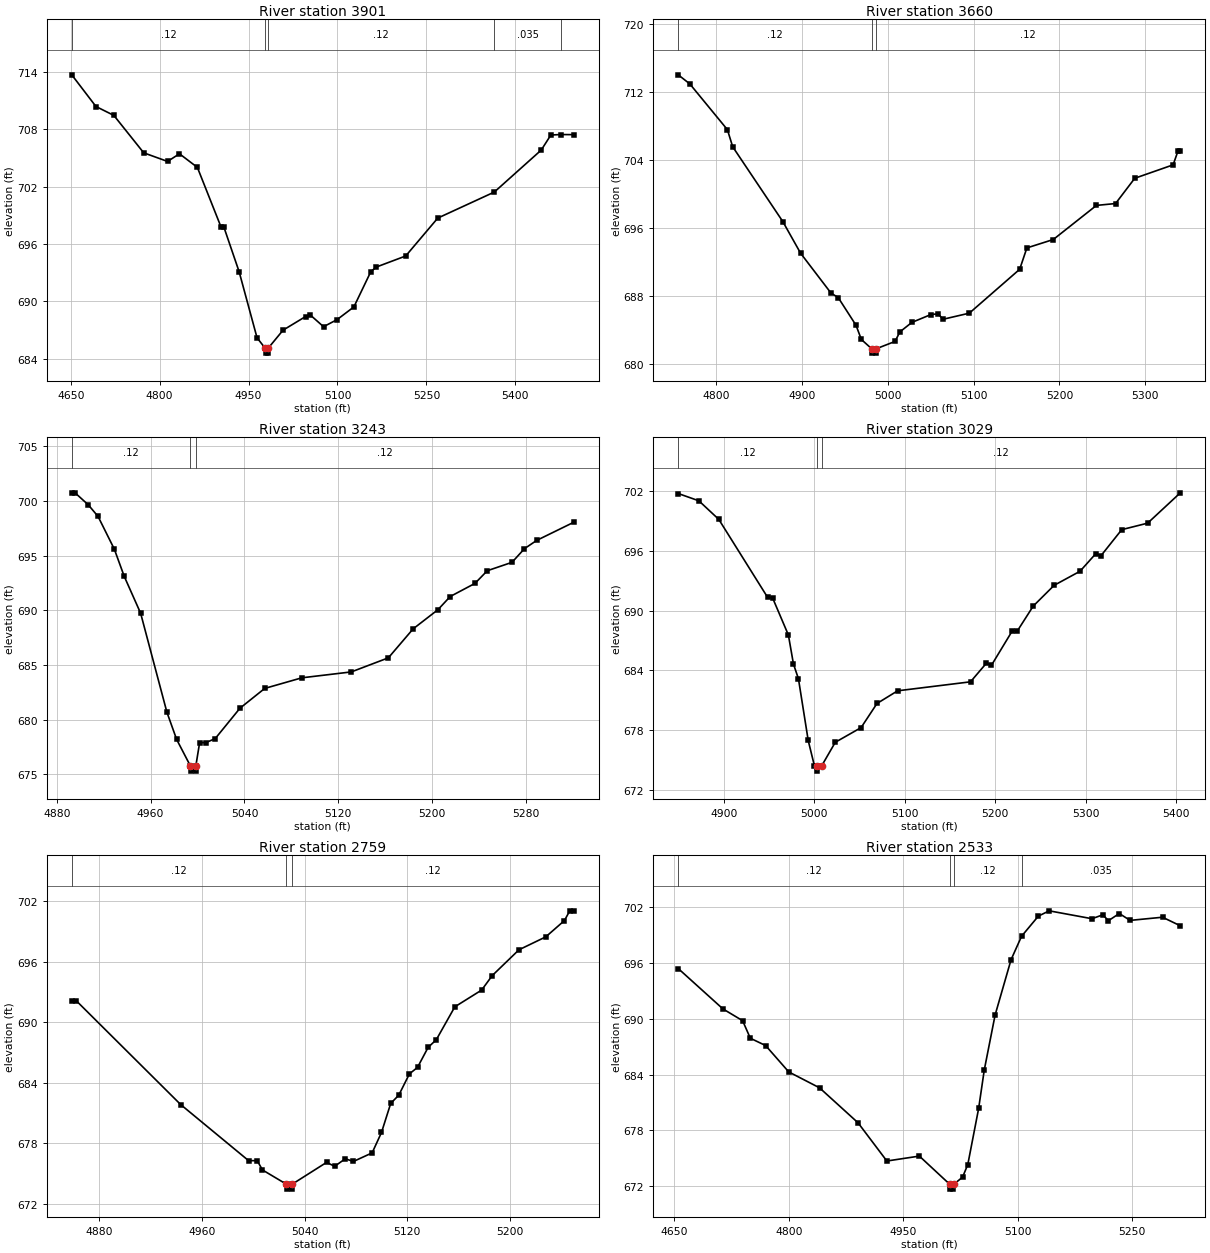
Type RM Length L Ch R = 1,3901,241,241,241
BEGIN DESCRIPTION:
A19397
END DESCRIPTION:
XS GIS Cut Line= 3
      2245875.59     13824881.25      2245552.65     13824917.71
      2245094.29     13825167.72
#Sta/Elev= 30
  4651.7  713.67  4692.5  710.36  4722.7  709.43  4773.1  705.52  4813.3  704.62
  4833.4  705.42  4863.6  704.00  4903.4  697.79  4908.4  697.75  4934.1  693.09
  4964.3  686.19  4978.2  685.09  4978.6  684.59  4982.6  684.59  4982.9  685.09
  5008.2  686.99  5046.1  688.41  5053.7  688.60  5076.5  687.35  5099.3  688.09
  5127.7  689.42  5156.3  693.11  5165.7  693.59  5215.1  694.74  5269.2  698.70
  5364.6  701.42  5443.8  705.81  5460.0  707.38  5476.6  707.43  5498.8  707.42
#Mann=5,-1,0
  4651.7    0.12       0  4978.2    0.05       0  4982.9    0.12       0
  5364.6   0.035       0  5476.6    0.07       0
Bank Sta=4978.2,4982.9
Exp/Cntr=0.3,0.1

Type RM Length L Ch R = 1,3660,417,417,417
BEGIN DESCRIPTION:
Guadalupe Tributary 7 8.0
END DESCRIPTION:
XS GIS Cut Line= 3
      2245575.00     13824525.01      2245425.00     13824725.00
      2245125.00     13824875.00
#Sta/Elev= 30
  4755.5  714.04  4769.0  712.97  4812.8  707.58  4819.0  705.56  4877.4  696.75
  4898.2  693.01  4933.6  688.32  4942.0  687.79  4962.8  684.52  4969.0  682.85
  4981.2  681.74  4981.6  681.24  4985.7  681.24  4986.0  681.74  5008.3  682.62
  5013.9  683.74  5027.9  684.86  5050.2  685.79  5058.6  685.87  5064.2  685.23
  5094.9  685.95  5153.6  691.12  5162.0  693.64  5192.8  694.63  5243.1  698.65
  5265.4  698.87  5287.8  701.85  5332.5  703.43  5338.1  705.03  5340.9  705.03
#Mann=3,-1,0
  4755.5    0.12       0  4981.2    0.05       0  4986.0    0.12       0
Bank Sta=4981.2,4986
Exp/Cntr=0.3,0.1

Type RM Length L Ch R = 1,3243,214,214,214
BEGIN DESCRIPTION:
Guadalupe Tributary 7 7.0
END DESCRIPTION:
XS GIS Cut Line= 3
      2245225.00     13824325.00      2245175.00     13824425.00
      2245075.01     13824724.97
#Sta/Elev= 30
  4892.8  700.76  4895.6  700.76  4906.8  699.67  4915.2  698.60  4929.1  695.60
  4937.5  693.12  4951.5  689.74  4973.9  680.68  4982.2  678.19  4993.8  675.79
  4994.2  675.29  4998.3  675.29  4998.6  675.79  5001.8  677.90  5007.2  677.90
  5015.1  678.27  5036.2  681.05  5057.3  682.86  5088.9  683.83  5131.1  684.37
  5162.7  685.66  5183.8  688.31  5204.9  690.06  5215.4  691.27  5236.5  692.47
  5247.0  693.63  5268.1  694.40  5278.7  695.65  5289.2  696.41  5320.8  698.07
#Mann=3,-1,0
  4892.8    0.12       0  4993.8    0.05       0  4998.6    0.12       0
Bank Sta=4993.8,4998.6
Exp/Cntr=0.3,0.1

Type RM Length L Ch R = 1,3029,270,270,270
BEGIN DESCRIPTION:
A19396
END DESCRIPTION:
XS GIS Cut Line= 2
      2245052.63     13824204.21      2244823.49     13824709.36
#Sta/Elev= 30
  4849.8  701.73  4872.6  701.00  4894.6  699.14  4948.5  691.33  4954.0  691.28
  4971.5  687.55  4977.1  684.64  4982.6  683.17  4993.4  676.98  5000.2  674.46
  5003.3  674.41  5003.6  673.91  5008.1  674.41  5023.3  676.80  5051.8  678.27
  5069.4  680.69  5092.2  681.96  5172.7  682.86  5190.3  684.73  5195.8  684.51
  5218.9  687.97  5224.4  687.95  5242.0  690.45  5265.1  692.53  5293.7  693.94
  5311.2  695.71  5316.7  695.48  5339.8  698.11  5368.4  698.76  5404.5  701.80
#Mann=3,-1,0
  4849.8    0.12       0  5003.3    0.05       0  5008.1    0.12       0
Bank Sta=5003.3,5008.1
Exp/Cntr=0.3,0.1

Type RM Length L Ch R = 1,2759,226,226,226
BEGIN DESCRIPTION:
Guadalupe Tributary 7 6.0
END DESCRIPTION:
XS GIS Cut Line= 3
      2244825.02     13824224.98      2244725.00     13824325.00
      2244574.97     13824525.04
#Sta/Elev= 30
  4858.5  692.11  4862.1  692.11  4943.4  681.84  4996.4  676.28  5003.1  676.28
  5007.2  675.36  5025.7  673.96  5026.0  673.46  5030.1  673.46  5030.5  673.96
  5057.2  676.11  5063.5  675.72  5071.8  676.47  5078.1  676.20  5092.7  677.05
  5100.0  679.07  5107.2  681.95  5113.5  682.77  5121.8  684.88  5128.1  685.52
  5136.4  687.51  5142.7  688.25  5157.2  691.52  5178.1  693.18  5186.4  694.62
  5207.2  697.17  5228.1  698.45  5242.7  700.07  5246.8  701.03  5250.0  701.03
#Mann=3,-1,0
  4858.5    0.12       0  5025.7    0.05       0  5030.5    0.12       0
Bank Sta=5025.7,5030.5
Exp/Cntr=0.3,0.1

Type RM Length L Ch R = 1,2533,235,235,235
BEGIN DESCRIPTION:
A19395
END DESCRIPTION:
XS GIS Cut Line= 3
      2244828.68     13824162.50      2244589.11     13824193.75
      2244307.84     13824501.06
#Sta/Elev= 30
  4654.9  695.42  4713.5  691.07  4739.3  689.80  4749.4  687.91  4769.5  687.12
  4799.8  684.28  4840.1  682.57  4890.6  678.80  4928.4  674.68  4971.0  675.21
  5011.1  672.15  5011.5  671.65  5015.6  671.65  5015.9  672.15  5027.7  672.95
  5034.5  674.30  5048.7  680.34  5056.1  684.49  5070.3  690.41  5091.2  696.37
  5105.0  698.90  5127.0  701.07  5141.2  701.64  5197.3  700.79  5211.5  701.21
  5218.9  700.58  5233.1  701.35  5247.3  700.61  5289.8  700.95  5313.1  700.03
#Mann=4,-1,0
  4654.9    0.12       0  5011.1    0.05       0  5015.9    0.12       0
  5105.0   0.035       0
Bank Sta=5011.1,5015.9
Exp/Cntr=0.3,0.1

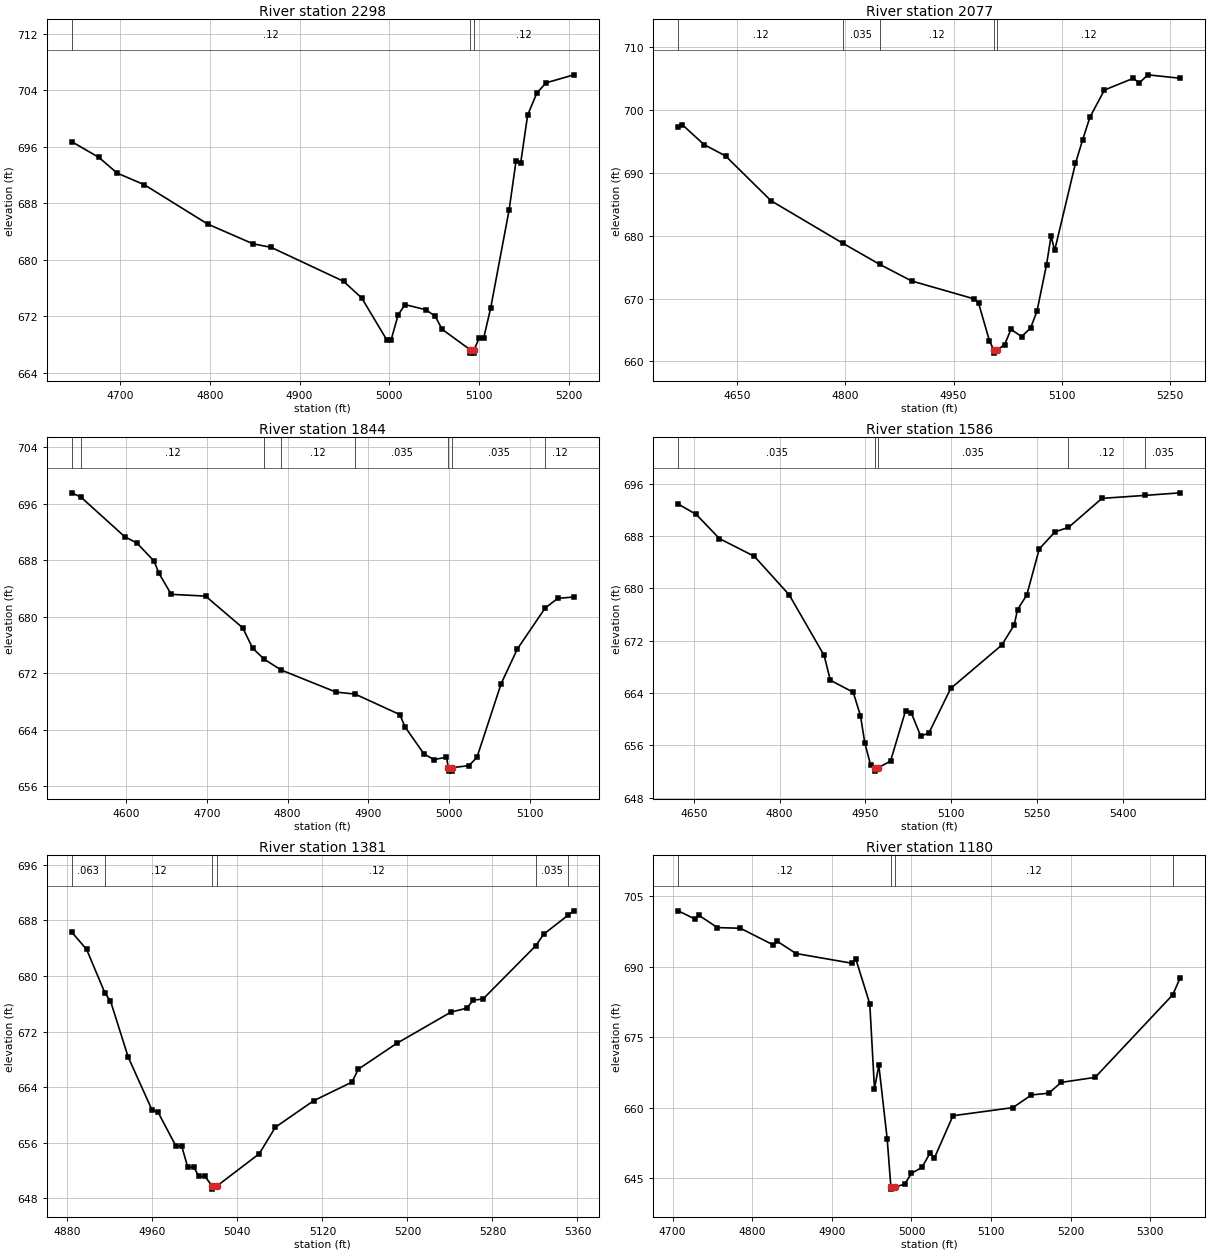
Type RM Length L Ch R = 1,2298,221,221,221
BEGIN DESCRIPTION:
Guadalupe Tributary 7 5.0
END DESCRIPTION:
XS GIS Cut Line= 3
      2244824.99     13824125.00      2244475.00     13824075.00
      2244275.00     13824025.00
#Sta/Elev= 30
  4646.1  696.72  4676.4  694.49  4696.6  692.28  4726.9  690.63  4797.6  685.06
  4848.1  682.26  4868.3  681.76  4949.1  676.95  4969.3  674.59  4997.1  668.69
  5002.2  668.69  5010.0  672.23  5017.7  673.65  5040.9  672.92  5051.2  672.01
  5058.9  670.16  5090.0  667.28  5090.4  666.78  5094.5  666.78  5094.8  667.28
  5100.1  668.90  5105.3  668.92  5113.0  673.11  5133.6  687.03  5141.4  694.03
  5146.5  693.68  5154.3  700.49  5164.6  703.63  5174.9  705.06  5205.8  706.19
#Mann=3,-1,0
  4646.1    0.12       0  5090.0    0.05       0  5094.8    0.12       0
Bank Sta=5090,5094.8
Exp/Cntr=0.3,0.1

Type RM Length L Ch R = 1,2077,233,233,233
BEGIN DESCRIPTION:
A19394
END DESCRIPTION:
XS GIS Cut Line= 3
      2244849.54     13824100.01      2244432.86     13823818.75
      2244240.11     13823834.38
#Sta/Elev= 30
  4568.3  697.32  4574.1  697.65  4604.0  694.51  4633.9  692.70  4696.9  685.57
  4796.5  678.80  4847.9  675.42  4891.8  672.80  4978.7  669.94  4984.7  669.27
  4999.7  663.30  5005.7  661.81  5006.1  661.31  5010.5  661.81  5020.7  662.63
  5029.6  665.09  5044.3  663.95  5056.7  665.28  5065.6  667.94  5078.9  675.38
  5085.2  679.93  5090.2  677.66  5119.0  691.51  5129.1  695.30  5139.1  698.87
  5159.2  703.19  5199.3  705.06  5207.3  704.31  5219.4  705.61  5264.4  705.06
#Mann=5,-1,0
  4568.3    0.12       0  4796.5   0.035       0  4847.9    0.12       0
  5005.7    0.05       0  5010.5    0.12       0
Bank Sta=5005.7,5010.5
Exp/Cntr=0.3,0.1

Type RM Length L Ch R = 1,1844,258,258,258
BEGIN DESCRIPTION:
Guadalupe Tributary 7 4.0
END DESCRIPTION:
XS GIS Cut Line= 3
      2244874.99     13824074.98      2244625.00     13823675.00
      2244474.98     13823675.00
#Sta/Elev= 30
  4532.7  697.51  4544.1  696.90  4598.1  691.32  4613.5  690.39  4634.7  687.84
  4640.6  686.13  4655.9  683.15  4698.4  682.90  4744.4  678.41  4756.7  675.53
  4771.3  673.94  4792.3  672.43  4859.9  669.32  4883.5  669.04  4938.9  666.14
  4945.4  664.39  4969.0  660.54  4981.4  659.78  4996.7  660.11  4999.0  658.64
  4999.4  658.14  5003.5  658.14  5003.8  658.64  5024.4  658.91  5034.4  660.08
  5064.4  670.52  5084.4  675.41  5118.8  681.20  5134.4  682.58  5154.4  682.77
#Mann=8,-1,0
  4532.7   0.035       0  4544.1    0.12       0  4771.3   0.035       0
  4792.3    0.12       0  4883.5   0.035       0  4999.0   0.035       0
  5003.8   0.035       0  5118.8    0.12       0
Bank Sta=4999,5003.8
Exp/Cntr=0.3,0.1

Type RM Length L Ch R = 1,1586,205,205,205
BEGIN DESCRIPTION:
A19393
END DESCRIPTION:
XS GIS Cut Line= 3
      2244938.07     13823995.85      2244849.53     13823521.88
      2244500.58     13823334.38
#Sta/Elev= 30
  4622.7  692.89  4654.1  691.31  4694.8  687.61  4755.8  684.90  4816.8  679.01
  4877.9  669.74  4888.8  665.95  4928.8  664.11  4941.5  660.52  4949.1  656.33
  4959.3  652.97  4966.8  652.55  4967.2  652.05  4972.0  652.55  4994.1  653.58
  5020.3  661.27  5030.5  660.93  5046.8  657.43  5061.0  657.85  5099.4  664.70
  5188.6  671.32  5210.5  674.41  5216.2  676.75  5232.4  678.98  5254.3  686.04
  5281.9  688.65  5305.4  689.32  5363.9  693.76  5439.9  694.22  5501.0  694.61
#Mann=5,-1,0
  4622.7   0.035       0  4966.8   0.035       0  4972.0   0.035       0
  5305.4    0.12       0  5439.9   0.035       0
Bank Sta=4966.8,4972
Exp/Cntr=0.3,0.1

Type RM Length L Ch R = 1,1381,201,201,201
BEGIN DESCRIPTION:
Guadalupe Tributary 7 3.0
END DESCRIPTION:
XS GIS Cut Line= 3
      2245125.02     13823725.04      2245075.00     13823625.00
      2244875.00     13823325.00
#Sta/Elev= 30
  4884.2  686.30  4898.2  683.81  4915.5  677.50  4920.6  676.41  4937.3  668.32
  4959.7  660.71  4965.3  660.41  4982.1  655.54  4987.7  655.47  4993.3  652.48
  4999.1  652.48  5003.6  651.19  5009.6  651.14  5016.0  649.82  5016.4  649.32
  5021.2  649.82  5060.6  654.41  5075.7  658.22  5111.7  662.03  5147.8  664.72
  5153.8  666.58  5189.8  670.28  5240.9  674.79  5255.9  675.36  5262.0  676.53
  5271.0  676.66  5321.0  684.38  5328.1  685.99  5351.5  688.78  5356.6  689.37
#Mann=6,-1,0
  4884.2   0.063       0  4915.5    0.12       0  5016.0    0.05       0
  5021.2    0.12       0  5321.0   0.035       0  5351.5   0.063       0
Bank Sta=5016,5021.2
Exp/Cntr=0.3,0.1

Type RM Length L Ch R = 1,1180,258,258,258
BEGIN DESCRIPTION:
A19392
END DESCRIPTION:
XS GIS Cut Line= 3
      2245484.98     13823600.01      2245073.48     13823417.71
      2244918.59     13823324.77
#Sta/Elev= 30
  4707.0  701.94  4727.6  700.23  4733.0  700.98  4756.3  698.37  4785.1  698.23
  4826.1  694.70  4831.6  695.43  4854.9  692.85  4924.7  690.79  4930.2  691.61
  4947.6  682.15  4953.5  664.07  4959.0  669.03  4969.5  653.31  4974.1  643.17
  4974.5  642.67  4979.4  643.17  4991.3  643.69  5000.0  646.04  5013.2  647.30
  5023.3  650.36  5028.8  649.30  5052.1  658.30  5127.4  660.03  5150.7  662.73
  5172.4  663.10  5188.0  665.40  5230.7  666.47  5328.2  684.06  5337.7  687.73
#Mann=4,-1,0
  4707.0    0.12       0  4974.1    0.05       0  4979.4    0.12       0
  5328.2   0.035       0
Bank Sta=4974.1,4979.4
Exp/Cntr=0.3,0.1

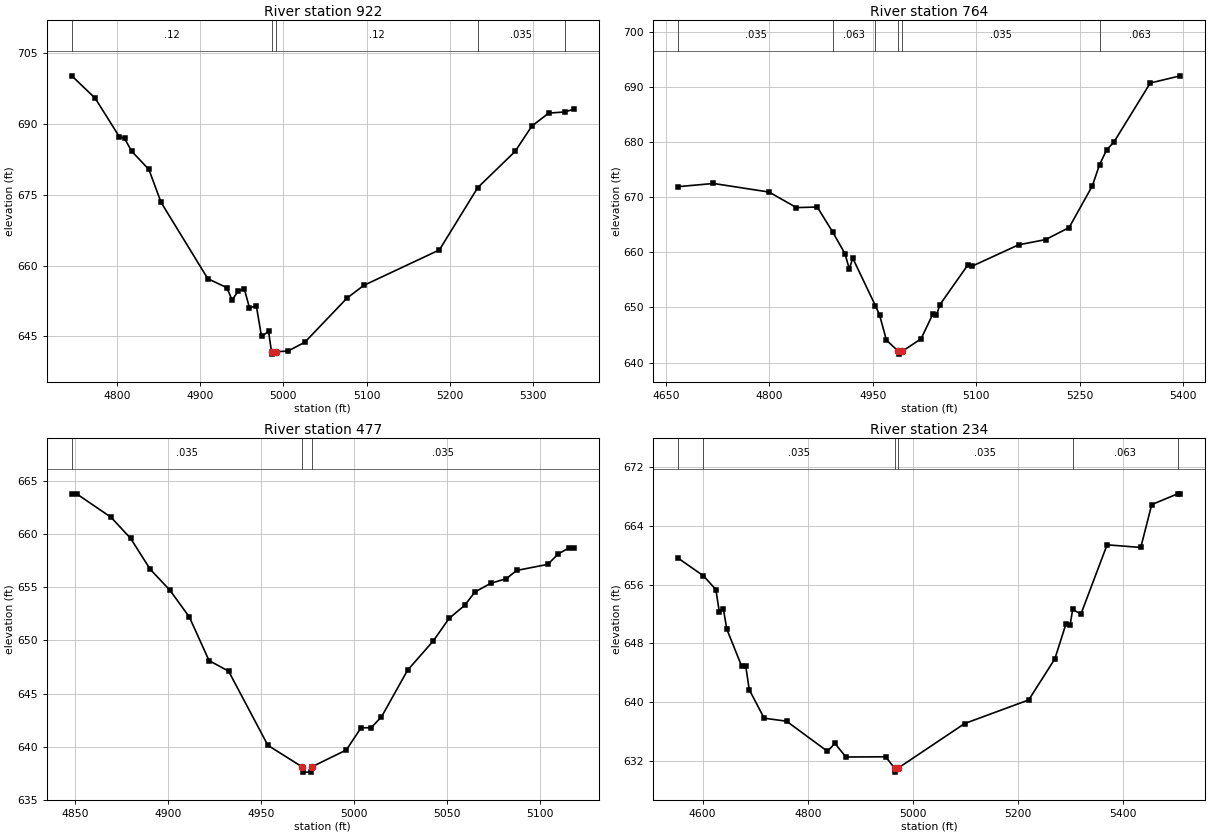
Type RM Length L Ch R = 1,922,158,158,158
BEGIN DESCRIPTION:
Guadalupe Tributary 7 2.0
END DESCRIPTION:
XS GIS Cut Line= 3
      2245375.00     13823424.99      2245225.00     13823225.00
      2244875.05     13823274.99
#Sta/Elev= 30
  4745.7  700.13  4773.8  695.40  4803.0  687.21  4809.2  686.88  4817.6  684.19
  4838.4  680.32  4853.0  673.37  4909.2  657.21  4932.2  655.30  4938.4  652.68
  4945.7  654.59  4953.0  655.11  4959.2  651.10  4967.6  651.40  4973.8  644.98
  4982.2  646.05  4985.8  641.75  4986.2  641.25  4991.1  641.75  5005.8  641.91
  5026.0  643.79  5076.5  653.10  5096.7  655.79  5187.6  663.30  5233.6  676.46
  5278.5  684.12  5298.7  689.49  5318.9  692.24  5338.3  692.49  5349.2  693.07
#Mann=5,-1,0
  4745.7    0.12       0  4985.8    0.05       0  4991.1    0.12       0
  5233.6   0.035       0  5338.3   0.063       0
Bank Sta=4985.8,4991.1
Exp/Cntr=0.3,0.1

Type RM Length L Ch R = 1,764,287,287,287
BEGIN DESCRIPTION:
A19391
END DESCRIPTION:
XS GIS Cut Line= 3
      2245505.82     13823110.42      2245125.57     13823079.17
      2244792.23     13823172.92
#Sta/Elev= 30
  4668.0  671.89  4719.0  672.47  4799.7  670.91  4839.4  668.09  4869.5  668.20
  4891.9  663.66  4909.6  659.76  4916.0  656.97  4921.0  658.92  4953.7  650.33
  4959.8  648.64  4969.8  644.05  4987.2  642.02  4987.6  641.52  4992.5  642.02
  5020.0  644.30  5037.2  648.82  5042.2  648.54  5047.3  650.48  5088.0  657.73
  5093.2  657.42  5161.3  661.34  5200.5  662.29  5234.6  664.47  5268.3  672.04
  5278.7  675.88  5289.0  678.56  5299.4  679.95  5352.3  690.69  5395.8  691.99
#Mann=6,-1,0
  4668.0   0.035       0  4891.9   0.063       0  4953.7   0.035       0
  4987.2   0.035       0  4992.5   0.035       0  5278.7   0.063       0
Bank Sta=4987.2,4992.5
Exp/Cntr=0.3,0.1

Type RM Length L Ch R = 1,477,243,243,243
BEGIN DESCRIPTION:
Guadalupe Tributary 7 1.0
END DESCRIPTION:
XS GIS Cut Line= 3
      2245224.99     13822875.00      2245075.00     13822825.00
      2244975.01     13822875.00
#Sta/Elev= 30
  4848.2  663.82  4850.8  663.82  4869.3  661.61  4879.8  659.63  4890.4  656.70
  4900.9  654.75  4911.4  652.21  4922.0  648.10  4932.5  647.11  4953.6  640.12
  4972.0  638.09  4972.4  637.59  4976.9  637.59  4977.3  638.09  4995.8  639.68
  5003.7  641.77  5009.1  641.77  5014.7  642.80  5028.7  647.19  5042.6  649.97
  5051.0  652.07  5059.4  653.31  5065.0  654.58  5073.4  655.38  5081.8  655.83
  5087.4  656.60  5104.1  657.17  5109.7  658.16  5115.3  658.70  5118.1  658.70
#Mann=3,-1,0
  4848.2   0.035       0  4972.0   0.035       0  4977.3   0.035       0
Bank Sta=4972,4977.3
Exp/Cntr=0.3,0.1

Type RM Length L Ch R = 1,234,0,0,0
BEGIN DESCRIPTION:
A19390
END DESCRIPTION:
XS GIS Cut Line= 4
      2245401.61     13822829.17      2245146.40     13822600.00
      2244979.73     13822610.42      2244630.80     13822886.44
#Sta/Elev= 30
  4553.5  659.58  4601.5  657.18  4625.0  655.32  4631.7  652.26  4639.2  652.73
  4645.9  649.91  4674.3  644.84  4681.8  644.94  4688.5  641.68  4716.9  637.78
  4759.5  637.37  4837.3  633.27  4851.5  634.34  4872.4  632.49  4948.0  632.52
  4965.4  630.93  4965.8  630.43  4970.7  630.93  5098.2  637.05  5220.1  640.27
  5269.8  645.87  5290.6  650.56  5298.6  650.42  5303.7  652.60  5319.4  651.97
  5369.1  661.41  5433.2  661.05  5454.0  666.89  5503.2  668.36  5508.4  668.36
#Mann=6,-1,0
  4553.5   0.063       0  4601.5   0.035       0  4965.4   0.035       0
  4970.7   0.035       0  5303.7   0.063       0  5503.2   0.035       0
Bank Sta=4965.4,4970.7
Exp/Cntr=0.3,0.1

Chan Stop Cuts=-1