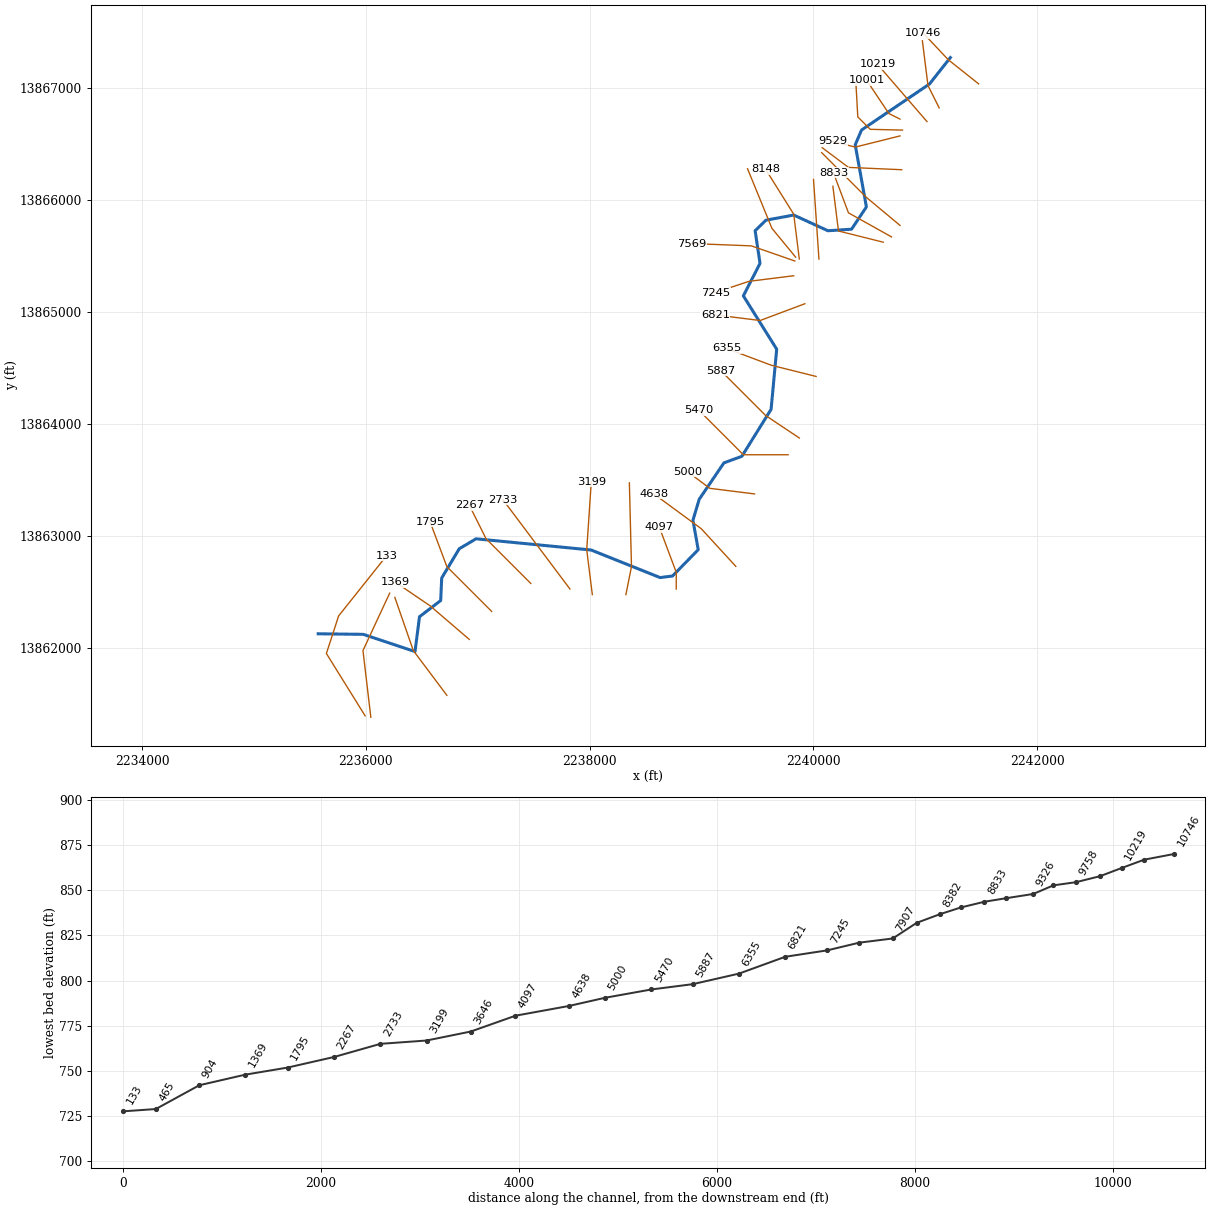
--- Heiser Creek.prj (project) ---

Proj Title=Heiser Creek Base Level Engineering
Current Plan=p01
Default Exp/Contr=0.3,0.1
English Units
Geom File=g01
Flow File=f01
Plan File=p01
BEGIN DESCRIPTION:
Heiser Creek
END DESCRIPTION:

--- Heiser Creek.p01 (plan) ---

Plan Title=Multiple Run
Short Identifier=Multiple
Geom File=g01
Flow File=f01
Subcritical Flow
K Sum by GR= 0
Std Step Tol= 0.01
Critical Tol= 0.01
Num of Std Step Trials= 20
Max Error Tol= 0.3
Flow Tol Ratio= 0.001
Split Flow NTrial= 30
Split Flow Tol= 0.02
Split Flow Ratio= 0.02
Log Output Level= 0
Friction Slope Method= 1
Unsteady Friction Slope Method= 2
Unsteady Bridges Friction Slope Method= 1
Parabolic Critical Depth
Global Vel Dist=  1 , 1 , 1
Global Log Level= 0
CheckData=True
Encroach Param= -1, 0, 0, 0
BEGIN DESCRIPTION:
Multiple Run
END DESCRIPTION:

--- Heiser Creek.f01 (steady flow) ---

Flow Title=Multiple
Number of Profiles=7
Profile Names=10-year,25-year,50-year,1pct_min,100-year,1pct_plu,500-year
River Rch & RM= Heiser Creek,Reach-1,10746
    1509    2620    3705    2539    5067   10110    9372
River Rch & RM= Heiser Creek,Reach-1,9529
    1798    3135    4443    3048    6082   12135   11276
River Rch & RM= Heiser Creek,Reach-1,4097
    2005    3507    4980    3421    6826   13620   12692
River Rch & RM= Heiser Creek,Reach-1,2267
    2048    3580    5080    3486    6955   13878   12906
Boundary for River Rch & Prof#=Heiser Creek,Reach-1,1
Up Type=0
Dn Type=3
Dn Slope=0.005
Boundary for River Rch & Prof#=Heiser Creek,Reach-1,2
Up Type=0
Dn Type=3
Dn Slope=0.005
Boundary for River Rch & Prof#=Heiser Creek,Reach-1,3
Up Type=0
Dn Type=3
Dn Slope=0.005
Boundary for River Rch & Prof#=Heiser Creek,Reach-1,4
Up Type=0
Dn Type=3
Dn Slope=0.005
Boundary for River Rch & Prof#=Heiser Creek,Reach-1,5
Up Type=0
Dn Type=3
Dn Slope=0.005
Boundary for River Rch & Prof#=Heiser Creek,Reach-1,6
Up Type=0
Dn Type=3
Dn Slope=0.005
Boundary for River Rch & Prof#=Heiser Creek,Reach-1,7
Up Type=0
Dn Type=3
Dn Slope=0.005

--- Heiser Creek.g01 (geometry) ---

Geom Title=Existing Conditions

River Reach=Heiser Creek,Reach-1
Reach XY= 30
      2241225.00     13867275.00      2241038.21     13867038.63
      2240430.82     13866627.31      2240374.71     13866495.18
      2240474.62     13865940.16      2240342.14     13865741.27
      2240130.94     13865727.26      2239825.01     13865867.47
      2239576.45     13865821.47      2239480.08     13865727.31
      2239523.80     13865435.50      2239374.79     13865145.06
      2239672.86     13864669.03      2239622.76     13864130.93
      2239361.54     13863711.37      2239201.10     13863652.28
      2238980.52     13863327.43      2238924.29     13863140.06
      2238971.47     13862876.47      2238741.75     13862641.40
      2238630.98     13862627.16      2238014.50     13862873.78
      2236985.50     13862973.80      2236835.65     13862885.00
      2236678.75     13862623.45      2236669.64     13862422.30
      2236480.45     13862277.47      2236440.12     13861965.95
      2235978.08     13862119.96      2235575.00     13862125.00

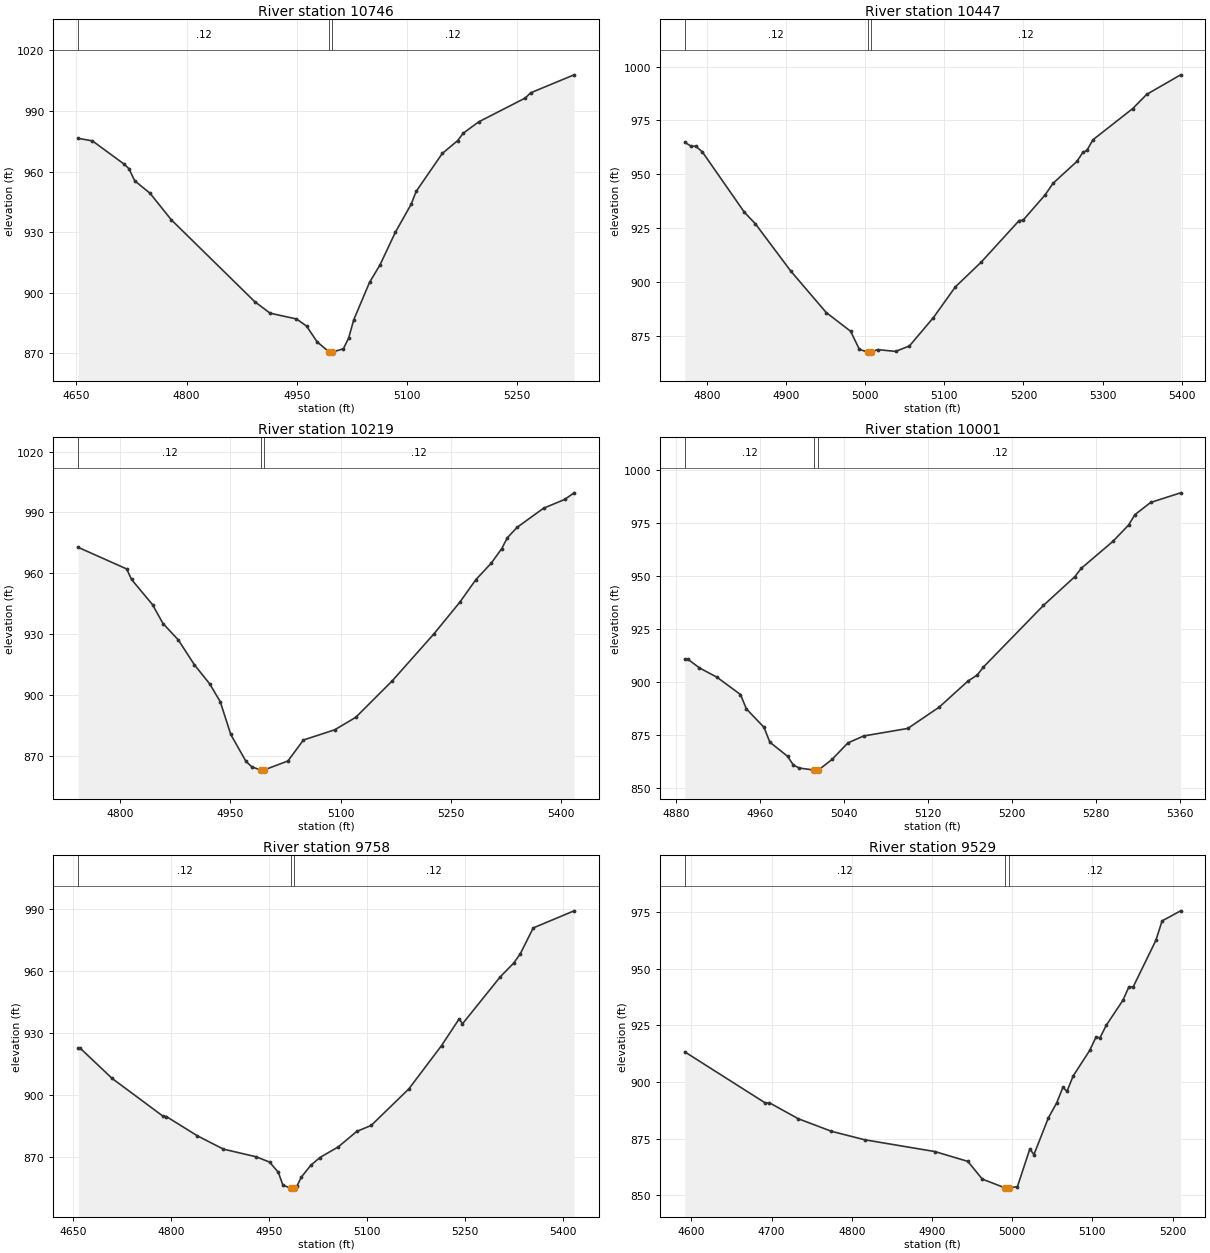
Type RM Length L Ch R = 1,10746,299,299,299
BEGIN DESCRIPTION:
A19405
END DESCRIPTION:
XS GIS Cut Line= 3
      2241477.62     13867039.97      2241206.76     13867255.28
      2240981.03     13867494.89
#Sta/Elev= 30
  4652.4  976.50  4671.7  975.25  4715.0  963.71  4721.4  961.52  4729.4  955.46
  4750.2  949.31  4779.1  936.20  4892.8  895.63  4913.6  889.95  4949.6  887.08
  4963.3  883.58  4977.7  875.75  4994.3  870.67  4994.6  870.17  4998.3  870.67
  5013.5  872.35  5020.7  877.72  5027.6  886.71  5049.1  905.22  5063.2  913.78
  5084.3  930.04  5105.7  943.84  5112.6  950.28  5148.2  969.04  5169.2  975.42
  5176.5  978.99  5197.5  984.61  5261.1  996.45  5268.4  999.03  5327.6 1007.94
#Mann=3,-1,0
  4652.4    0.12       0  4994.3    0.05       0  4998.3    0.12       0
Bank Sta=4994.3,4998.3
Exp/Cntr=0.3,0.1

Type RM Length L Ch R = 1,10447,228,228,228
BEGIN DESCRIPTION:
Heiser Creek 23.0
END DESCRIPTION:
XS GIS Cut Line= 3
      2241124.98     13866825.03      2241025.00     13867025.00
      2240975.00     13867425.02
#Sta/Elev= 30
  4771.9  964.90  4780.2  962.99  4785.8  963.11  4794.2  960.40  4847.3  932.41
  4861.3  927.00  4906.0  905.09  4950.7  885.89  4981.5  877.21  4992.7  868.74
  5003.5  867.55  5003.7  867.05  5007.6  867.55  5015.6  868.69  5038.3  867.84
  5055.9  870.39  5086.2  883.55  5113.9  897.78  5146.6  909.29  5194.5  928.56
  5199.5  928.74  5227.3  940.45  5237.3  945.82  5267.6  956.03  5275.1  960.22
  5280.2  961.10  5287.7  966.01  5338.1  980.54  5355.8  987.12  5398.6  996.18
#Mann=3,-1,0
  4771.9    0.12       0  5003.5    0.05       0  5007.6    0.12       0
Bank Sta=5003.5,5007.6
Exp/Cntr=0.3,0.1

Type RM Length L Ch R = 1,10219,218,218,218
BEGIN DESCRIPTION:
A19406
END DESCRIPTION:
XS GIS Cut Line= 2
      2241015.78     13866703.20      2240574.82     13867213.60
#Sta/Elev= 30
  4743.0  972.78  4808.9  962.14  4815.5  956.97  4844.1  944.52  4858.3  935.23
  4879.2  927.12  4901.1  914.84  4921.9  905.43  4936.2  896.68  4950.5  880.52
  4971.3  867.18  4979.0  864.59  4991.2  862.93  4991.4  862.43  4995.3  862.93
  5028.3  867.45  5049.3  877.77  5092.0  882.83  5120.5  888.96  5169.9  906.86
  5226.9  930.14  5262.0  945.71  5283.9  956.87  5304.8  964.99  5319.0  972.12
  5326.7  977.52  5340.1  982.68  5376.0  992.09  5404.6  996.39  5417.5  999.67
#Mann=3,-1,0
  4743.0    0.12       0  4991.2    0.05       0  4995.3    0.12       0
Bank Sta=4991.2,4995.3
Exp/Cntr=0.3,0.1

Type RM Length L Ch R = 1,10001,243,243,243
BEGIN DESCRIPTION:
Heiser Creek 22.0
END DESCRIPTION:
XS GIS Cut Line= 3
      2240775.02     13866724.99      2240675.00     13866775.00
      2240474.99     13867075.02
#Sta/Elev= 30
  4888.2  910.86  4891.0  910.86  4902.2  906.71  4919.0  902.26  4941.3  894.11
  4946.9  887.32  4963.7  878.61  4969.3  871.57  4986.1  864.94  4991.6  860.82
  4997.2  859.38  5011.4  858.40  5011.7  857.90  5015.6  858.40  5028.6  863.48
  5043.6  871.22  5058.6  874.51  5100.7  878.08  5130.7  888.18  5157.8  900.39
  5166.8  903.32  5172.8  907.12  5229.9  936.22  5259.9  949.85  5265.9  953.74
  5296.0  966.45  5311.0  974.19  5317.0  979.10  5332.0  984.88  5360.6  989.44
#Mann=3,-1,0
  4888.2    0.12       0  5011.4    0.05       0  5015.6    0.12       0
Bank Sta=5011.4,5015.6
Exp/Cntr=0.3,0.1

Type RM Length L Ch R = 1,9758,229,229,229
BEGIN DESCRIPTION:
A19407
END DESCRIPTION:
XS GIS Cut Line= 4
      2240797.00     13866626.80      2240508.84     13866633.75
      2240397.73     13866744.86      2240380.36     13867057.40
#Sta/Elev= 30
  4658.2  922.66  4661.7  922.66  4710.2  908.13  4788.0  889.85  4793.0  889.71
  4840.3  880.40  4880.3  873.92  4930.3  870.23  4950.9  867.65  4964.2  862.73
  4971.3  856.45  4983.3  855.06  4983.6  854.56  4987.5  855.06  4992.5  855.87
  4999.5  860.40  5013.7  866.03  5027.8  869.85  5056.1  875.06  5084.4  882.55
  5106.2  885.37  5163.8  903.07  5213.9  924.08  5240.9  937.04  5245.9  934.61
  5304.0  957.47  5324.1  963.96  5334.1  968.39  5354.1  981.03  5416.6  989.31
#Mann=3,-1,0
  4658.2    0.12       0  4983.3    0.05       0  4987.5    0.12       0
Bank Sta=4983.3,4987.5
Exp/Cntr=0.3,0.1

Type RM Length L Ch R = 1,9529,203,203,203
BEGIN DESCRIPTION:
Heiser Creek 21.0
END DESCRIPTION:
XS GIS Cut Line= 3
      2240774.98     13866575.00      2240375.00     13866475.00
      2240175.05     13866524.99
#Sta/Elev= 30
  4591.6  913.31  4692.1  890.77  4697.2  890.85  4733.3  883.81  4774.5  878.30
  4815.8  874.56  4903.4  869.37  4944.6  865.04  4962.7  857.22  4991.4  853.30
  4991.7  852.80  4995.7  853.30  5006.5  853.93  5021.9  870.45  5027.1  868.05
  5045.1  884.24  5055.4  890.77  5063.2  897.64  5068.3  895.94  5076.0  902.67
  5096.7  913.99  5104.4  919.75  5109.5  919.52  5117.3  925.04  5137.9  935.95
  5145.6  942.00  5150.8  941.91  5179.1  962.40  5186.9  971.01  5210.0  975.45
#Mann=3,-1,0
  4591.6    0.12       0  4991.4    0.05       0  4995.7    0.12       0
Bank Sta=4991.4,4995.7
Exp/Cntr=0.3,0.1

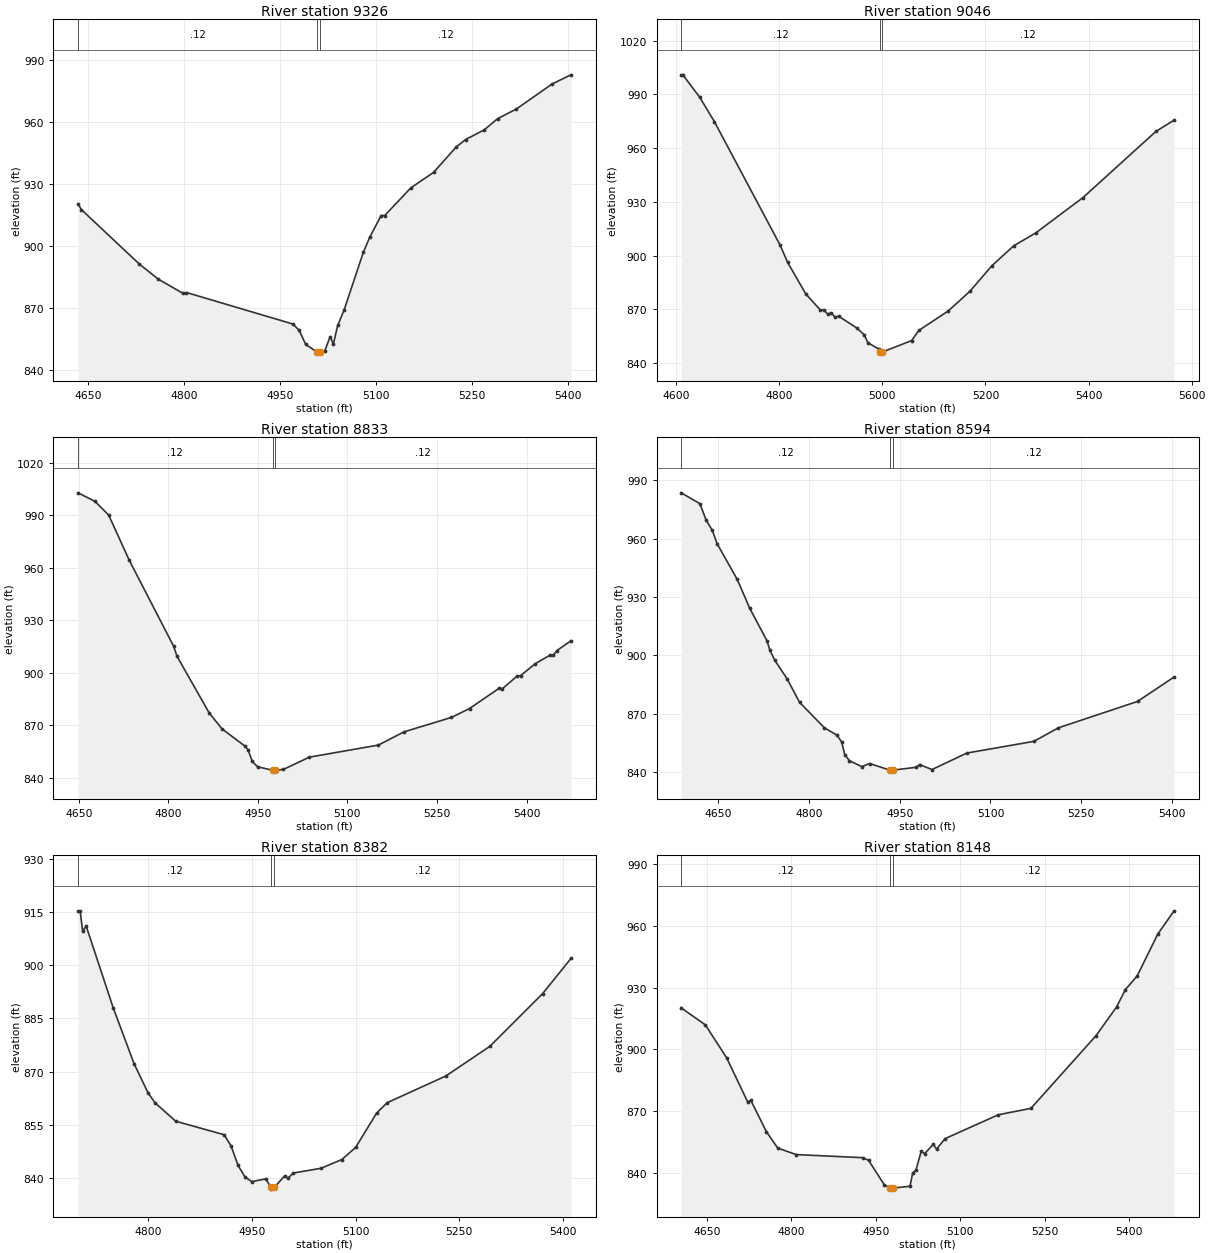
Type RM Length L Ch R = 1,9326,280,280,280
BEGIN DESCRIPTION:
A19408
END DESCRIPTION:
XS GIS Cut Line= 3
      2240790.11     13866272.64      2240314.39     13866293.47
      2240079.49     13866469.65
#Sta/Elev= 30
  4634.5  920.44  4639.6  917.67  4729.7  891.38  4759.7  883.92  4798.8  876.96
  4803.8  877.43  4969.9  862.16  4979.9  859.07  4990.0  852.28  5007.8  848.53
  5008.1  848.03  5012.2  848.53  5020.0  849.22  5028.2  856.04  5033.2  852.39
  5040.0  861.48  5050.0  868.93  5080.0  896.90  5090.0  904.22  5107.9  914.78
  5113.4  914.78  5154.3  928.22  5189.7  935.69  5225.1  948.04  5239.7  951.62
  5268.9  956.35  5289.7  961.76  5318.9  966.42  5375.1  978.64  5404.3  983.03
#Mann=3,-1,0
  4634.5    0.12       0  5007.8    0.05       0  5012.2    0.12       0
Bank Sta=5007.8,5012.2
Exp/Cntr=0.3,0.1

Type RM Length L Ch R = 1,9046,213,213,213
BEGIN DESCRIPTION:
Heiser Creek 20.0
END DESCRIPTION:
XS GIS Cut Line= 3
      2240774.99     13865775.01      2240475.00     13866025.00
      2240074.99     13866425.01
#Sta/Elev= 30
  4609.7 1000.87  4612.9 1000.87  4645.5  988.43  4674.1  974.77  4801.7  905.83
  4816.0  896.35  4851.2  878.74  4879.8  869.62  4886.3  869.82  4894.1  867.34
  4900.6  868.12  4908.4  865.57  4914.9  866.28  4950.1  859.69  4964.4  855.95
  4972.2  851.38  4993.0  847.90  4994.7  846.12  4995.0  845.62  4999.1  846.12
  5056.8  852.63  5070.9  858.33  5127.5  869.07  5169.9  880.13  5212.3  894.33
  5254.8  905.48  5297.2  912.61  5389.1  932.37  5530.5  969.26  5565.9  975.59
#Mann=3,-1,0
  4609.7    0.12       0  4994.7    0.05       0  4999.1    0.12       0
Bank Sta=4994.7,4999.1
Exp/Cntr=0.3,0.1

Type RM Length L Ch R = 1,8833,239,239,239
BEGIN DESCRIPTION:
A19409
END DESCRIPTION:
XS GIS Cut Line= 3
      2240699.78     13865671.96      2240314.39     13865887.22
      2240179.50     13866246.93
#Sta/Elev= 30
  4648.8 1002.68  4677.2  997.80  4700.1  989.96  4734.5  964.19  4808.9  915.04
  4814.6  909.29  4868.3  877.04  4890.0  867.81  4927.7  858.18  4933.4  855.94
  4940.6  849.26  4949.4  846.23  4974.6  844.22  4974.9  843.72  4979.0  844.22
  4992.8  844.70  5036.2  851.70  5151.9  858.60  5194.7  866.15  5274.2  874.39
  5304.5  879.48  5354.3  891.10  5359.6  890.82  5384.6  898.12  5389.9  898.23
  5414.8  905.13  5439.7  910.04  5445.1  909.95  5451.0  912.62  5474.4  918.17
#Mann=3,-1,0
  4648.8    0.12       0  4974.6    0.05       0  4979.0    0.12       0
Bank Sta=4974.6,4979
Exp/Cntr=0.3,0.1

Type RM Length L Ch R = 1,8594,212,212,212
BEGIN DESCRIPTION:
Heiser Creek 19.0
END DESCRIPTION:
XS GIS Cut Line= 3
      2240625.04     13865624.99      2240225.00     13865725.00
      2240175.00     13866125.04
#Sta/Elev= 30
  4588.3  983.58  4619.3  978.01  4629.6  969.54  4639.9  964.25  4647.6  957.51
  4681.1  939.04  4701.7  924.24  4730.1  907.62  4735.2  902.58  4743.0  897.59
  4763.6  887.94  4784.2  875.87  4825.4  862.76  4846.0  859.04  4853.8  855.55
  4858.9  849.03  4866.6  845.90  4887.3  842.85  4900.1  844.43  4933.9  841.03
  4934.2  840.53  4938.6  841.03  4977.5  842.52  4982.6  843.93  5003.2  841.33
  5061.1  849.83  5172.0  855.84  5212.3  862.78  5343.3  876.35  5403.8  888.91
#Mann=3,-1,0
  4588.3    0.12       0  4933.9    0.05       0  4938.6    0.12       0
Bank Sta=4933.9,4938.6
Exp/Cntr=0.3,0.1

Type RM Length L Ch R = 1,8382,234,234,234
BEGIN DESCRIPTION:
A19410
END DESCRIPTION:
XS GIS Cut Line= 2
      2240050.50     13865474.05      2240001.90     13866185.79
#Sta/Elev= 30
  4698.3  915.39  4701.3  915.39  4705.0  909.60  4710.0  911.11  4749.4  887.87
  4779.4  872.21  4799.5  864.01  4809.5  861.21  4839.6  855.97  4909.7  852.16
  4919.8  848.97  4929.8  843.52  4939.8  840.26  4949.8  838.90  4969.9  839.69
  4977.6  837.29  4977.9  836.79  4982.3  837.29  4997.1  840.48  5002.1  839.90
  5010.0  841.34  5050.1  842.68  5080.1  845.15  5100.2  848.60  5130.3  858.23
  5145.6  861.19  5230.5  868.73  5294.2  877.10  5370.8  892.03  5411.7  901.94
#Mann=3,-1,0
  4698.3    0.12       0  4977.6    0.05       0  4982.3    0.12       0
Bank Sta=4977.6,4982.3
Exp/Cntr=0.3,0.1

Type RM Length L Ch R = 1,8148,241,241,241
BEGIN DESCRIPTION:
Heiser Creek 18.0
END DESCRIPTION:
XS GIS Cut Line= 3
      2239875.00     13865474.98      2239825.00     13865875.00
      2239575.02     13866274.97
#Sta/Elev= 30
  4604.6  920.18  4647.5  911.89  4685.2  895.90  4723.0  874.19  4728.1  875.26
  4755.8  859.95  4775.9  851.98  4808.7  848.81  4927.1  847.29  4937.2  846.01
  4964.9  834.22  4975.1  832.50  4975.5  832.00  4979.9  832.50  5010.7  833.40
  5015.4  839.78  5021.3  841.30  5030.7  850.44  5036.6  849.24  5052.0  853.76
  5057.9  851.49  5073.2  856.59  5167.5  868.18  5225.3  871.28  5340.9  906.65
  5377.4  920.62  5392.8  928.98  5414.0  935.75  5450.5  956.07  5479.4  967.37
#Mann=3,-1,0
  4604.6    0.12       0  4975.1    0.05       0  4979.9    0.12       0
Bank Sta=4975.1,4979.9
Exp/Cntr=0.3,0.1

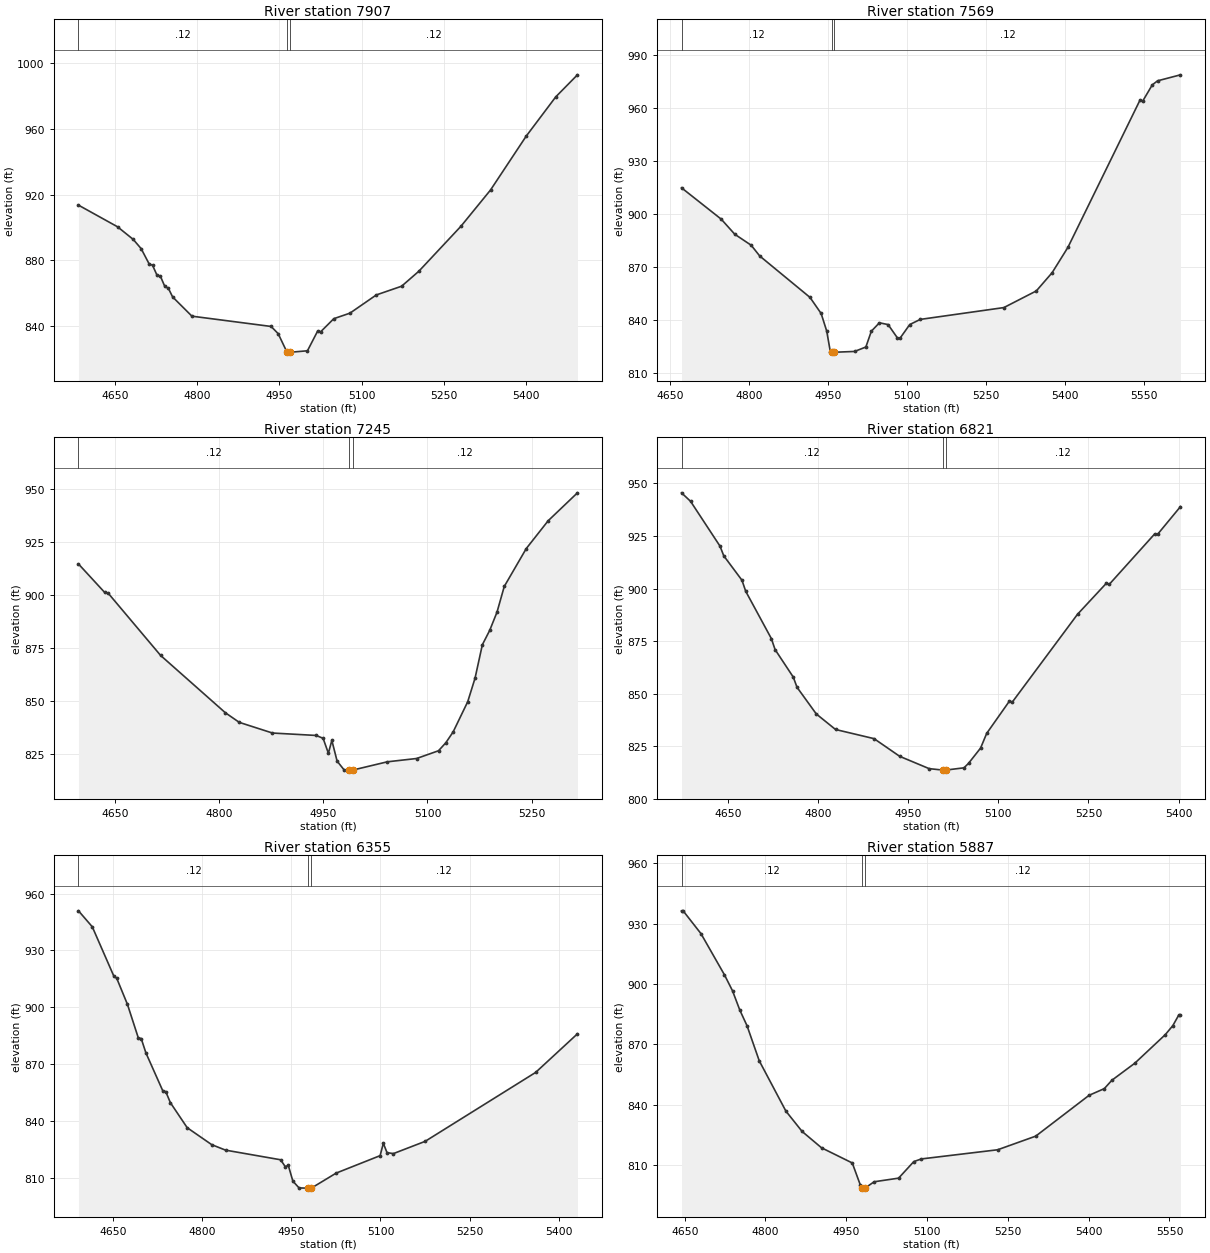
Type RM Length L Ch R = 1,7907,338,338,338
BEGIN DESCRIPTION:
A19404
END DESCRIPTION:
XS GIS Cut Line= 3
      2239842.18     13865491.38      2239630.37     13865748.33
      2239412.24     13866281.54
#Sta/Elev= 30
  4583.9  913.53  4655.0  900.35  4683.7  892.63  4698.1  887.01  4712.4  877.85
  4718.9  876.84  4726.7  871.03  4733.2  870.17  4741.1  864.04  4747.6  862.88
  4755.4  857.60  4790.6  845.87  4934.9  839.60  4947.7  835.23  4963.9  823.85
  4964.3  823.35  4968.7  823.85  5001.1  824.78  5019.7  836.83  5025.1  836.34
  5049.1  844.35  5078.5  847.71  5126.6  858.82  5172.6  864.12  5204.0  873.24
  5280.7  900.65  5334.7  922.79  5399.5  955.51  5453.5  979.52  5493.0  992.95
#Mann=3,-1,0
  4583.9    0.12       0  4963.9    0.05       0  4968.7    0.12       0
Bank Sta=4963.9,4968.7
Exp/Cntr=0.3,0.1

Type RM Length L Ch R = 1,7569,324,324,324
BEGIN DESCRIPTION:
Heiser Creek 17.0
END DESCRIPTION:
XS GIS Cut Line= 3
      2239835.27     13865456.65      2239446.34     13865592.08
      2238911.58     13865612.92
#Sta/Elev= 30
  4671.8  914.65  4747.2  896.88  4772.9  888.34  4804.0  882.13  4820.3  876.02
  4915.6  852.60  4936.8  843.47  4947.4  833.51  4954.2  821.89  4957.0  821.53
  4957.4  821.03  4961.9  821.53  5000.3  821.98  5021.7  824.50  5032.1  833.45
  5047.4  838.21  5063.9  837.19  5081.7  829.59  5086.8  829.59  5105.0  837.22
  5125.0  840.13  5283.6  846.82  5345.2  856.25  5375.2  866.57  5405.2  880.93
  5542.1  964.37  5547.1  963.73  5565.3  972.93  5575.3  975.22  5618.8  978.62
#Mann=3,-1,0
  4671.8    0.12       0  4957.0    0.05       0  4961.9    0.12       0
Bank Sta=4957,4961.9
Exp/Cntr=0.3,0.1

Type RM Length L Ch R = 1,7245,424,424,424
BEGIN DESCRIPTION:
Heiser Creek 16.0
END DESCRIPTION:
XS GIS Cut Line= 3
      2239825.02     13865325.00      2239425.00     13865275.00
      2239124.96     13865174.99
#Sta/Elev= 30
  4596.8  914.53  4634.6  901.09  4639.6  900.75  4715.2  871.37  4808.5  844.33
  4828.6  839.78  4876.5  834.74  4939.5  833.60  4949.5  832.25  4957.1  825.20
  4962.1  831.26  4969.7  821.47  4979.8  817.33  4987.4  817.26  4987.8  816.76
  4992.3  817.26  5042.1  821.16  5084.3  822.72  5115.9  826.38  5126.4  830.14
  5137.0  835.28  5158.0  849.52  5168.6  860.68  5179.1  876.41  5189.7  883.19
  5200.2  891.77  5210.7  903.94  5242.4  921.81  5274.0  934.94  5316.2  948.12
#Mann=3,-1,0
  4596.8    0.12       0  4987.4    0.05       0  4992.3    0.12       0
Bank Sta=4987.4,4992.3
Exp/Cntr=0.3,0.1

Type RM Length L Ch R = 1,6821,466,466,466
BEGIN DESCRIPTION:
Heiser Creek 15.0
END DESCRIPTION:
XS GIS Cut Line= 3
      2239924.99     13865075.00      2239525.00     13864925.00
      2239125.00     13864975.00
#Sta/Elev= 30
  4572.8  945.48  4587.9  941.43  4636.9  920.11  4643.1  915.54  4673.4  903.93
  4679.6  898.71  4722.3  876.20  4728.5  870.98  4758.8  857.88  4765.0  853.05
  4797.1  840.37  4829.1  832.99  4893.2  828.64  4935.9  820.23  4984.9  814.38
  5007.6  813.70  5008.0  813.20  5012.5  813.70  5042.8  814.77  5050.4  816.89
  5070.5  824.17  5080.6  831.12  5118.4  846.46  5123.4  846.08  5231.8  887.76
  5279.6  902.44  5284.7  902.00  5360.3  925.98  5365.3  925.86  5403.1  938.93
#Mann=3,-1,0
  4572.8    0.12       0  5007.6    0.05       0  5012.5    0.12       0
Bank Sta=5007.6,5012.5
Exp/Cntr=0.3,0.1

Type RM Length L Ch R = 1,6355,468,468,468
BEGIN DESCRIPTION:
Heiser Creek 14.0
END DESCRIPTION:
XS GIS Cut Line= 3
      2240024.98     13864425.01      2239625.00     13864525.00
      2239224.99     13864675.00
#Sta/Elev= 30
  4591.9  950.95  4615.1  942.51  4651.1  916.64  4656.3  915.26  4674.3  901.49
  4692.4  883.95  4697.5  883.40  4705.3  875.90  4733.6  855.93  4738.8  855.37
  4746.5  849.58  4774.8  836.34  4816.1  827.37  4839.3  824.49  4932.0  819.39
  4939.8  815.75  4944.9  816.44  4952.6  808.11  4963.0  804.52  4978.5  804.38
  4978.8  803.88  4983.5  804.38  5025.5  812.36  5099.4  821.57  5104.8  828.11
  5111.0  823.18  5121.7  822.65  5175.1  829.12  5361.1  865.56  5431.4  885.95
#Mann=3,-1,0
  4591.9    0.12       0  4978.5    0.05       0  4983.5    0.12       0
Bank Sta=4978.5,4983.5
Exp/Cntr=0.3,0.1

Type RM Length L Ch R = 1,5887,417,417,417
BEGIN DESCRIPTION:
Heiser Creek 13.0
END DESCRIPTION:
XS GIS Cut Line= 3
      2239875.03     13863874.98      2239575.00     13864075.00
      2239174.98     13864475.02
#Sta/Elev= 30
  4644.1  936.41  4647.1  936.41  4680.2  925.07  4723.8  904.59  4738.8  896.63
  4752.3  887.06  4765.8  879.21  4788.4  861.83  4837.9  836.80  4868.0  826.69
  4904.0  818.57  4961.1  811.02  4976.1  800.02  4979.6  798.51  4980.0  798.01
  4984.7  798.51  5001.7  801.67  5047.1  803.47  5075.4  811.72  5089.5  813.03
  5231.0  817.58  5301.7  824.36  5400.7  844.66  5429.0  847.99  5443.1  852.16
  5485.5  860.60  5542.1  874.80  5556.2  879.31  5566.8  884.37  5570.4  884.37
#Mann=3,-1,0
  4644.1    0.12       0  4979.6    0.05       0  4984.7    0.12       0
Bank Sta=4979.6,4984.7
Exp/Cntr=0.3,0.1

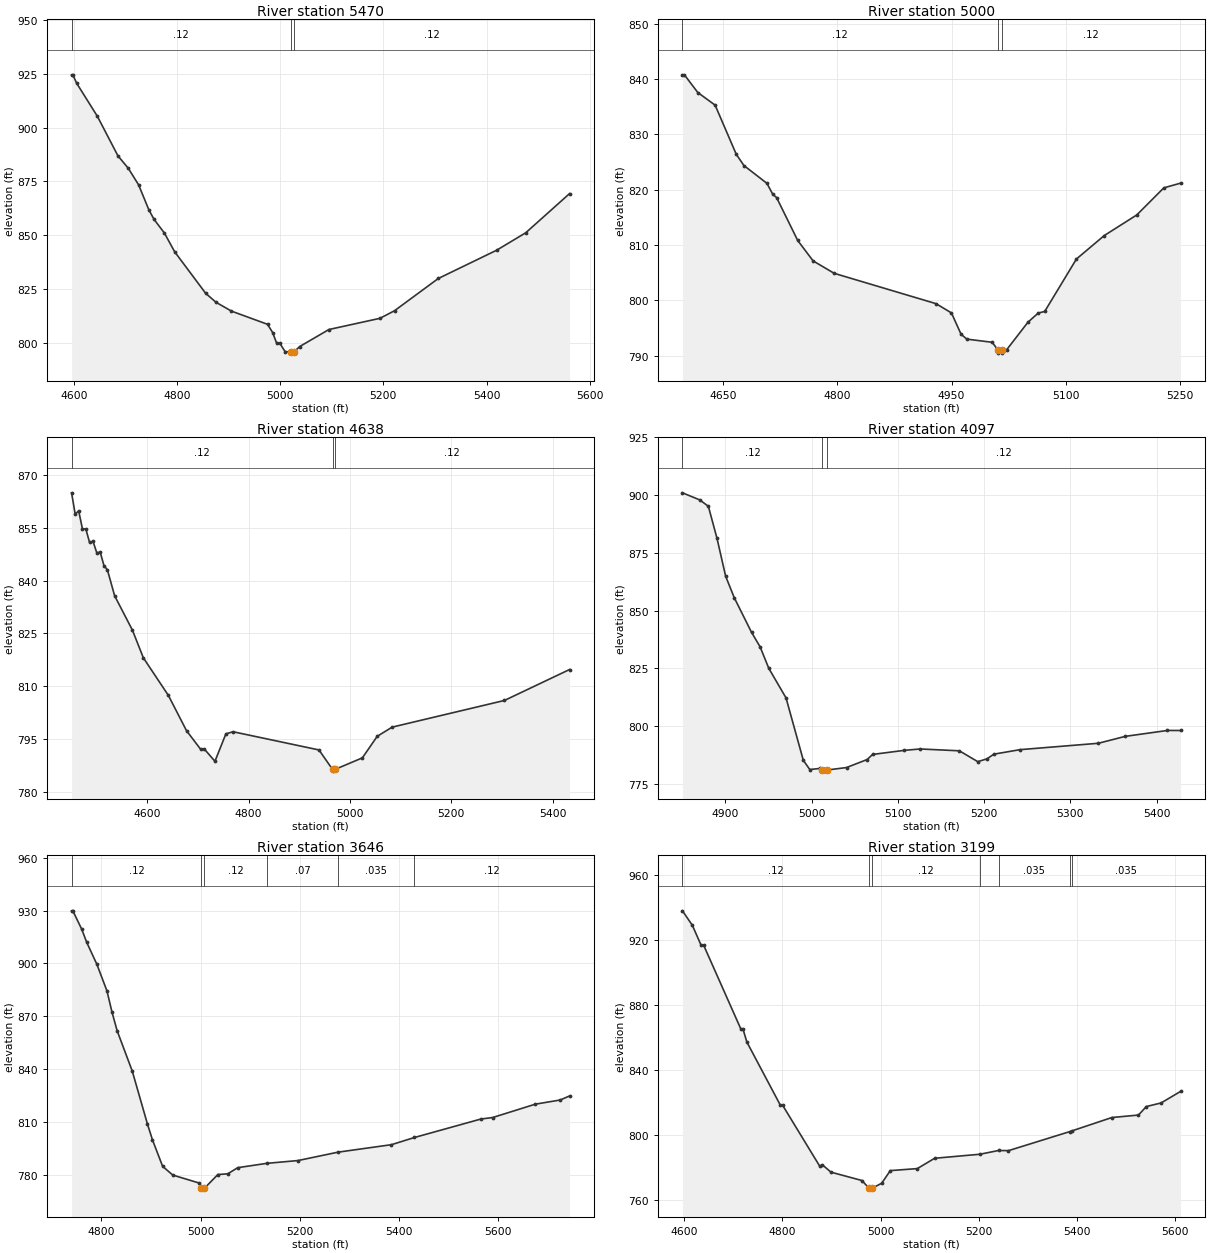
Type RM Length L Ch R = 1,5470,470,470,470
BEGIN DESCRIPTION:
Heiser Creek 12.0
END DESCRIPTION:
XS GIS Cut Line= 3
      2239774.97     13863725.00      2239375.00     13863725.00
      2238974.97     13864125.03
#Sta/Elev= 30
  4595.4  924.50  4597.9  924.50  4605.4  920.54  4645.4  905.23  4685.4  886.79
  4705.4  881.04  4725.4  873.33  4745.4  861.65  4755.4  857.26  4775.4  850.93
  4795.4  842.18  4855.4  822.91  4875.4  818.74  4905.4  814.62  4975.4  808.48
  4985.4  804.61  4992.9  799.78  4998.9  799.78  5009.5  795.77  5021.1  795.58
  5021.5  795.08  5026.2  795.58  5037.8  798.15  5094.4  806.06  5193.4  811.27
  5221.6  814.79  5306.5  829.79  5419.6  842.93  5476.2  851.07  5561.1  869.28
#Mann=3,-1,0
  4595.4    0.12       0  5021.1    0.05       0  5026.2    0.12       0
Bank Sta=5021.1,5026.2
Exp/Cntr=0.3,0.1

Type RM Length L Ch R = 1,5000,362,362,362
BEGIN DESCRIPTION:
Heiser Creek 11.0
END DESCRIPTION:
XS GIS Cut Line= 3
      2239474.98     13863375.00      2239075.00     13863425.00
      2238874.99     13863575.00
#Sta/Elev= 30
  4597.2  840.75  4599.7  840.75  4617.3  837.55  4640.0  835.27  4667.7  826.39
  4677.8  824.35  4708.0  821.13  4715.6  819.15  4720.6  818.57  4748.3  810.81
  4768.5  807.12  4796.2  804.87  4929.7  799.39  4949.9  797.72  4962.5  793.87
  4970.1  792.98  5003.4  792.41  5011.2  790.95  5011.6  790.45  5016.0  790.45
  5016.4  790.95  5022.2  791.04  5050.3  796.05  5063.8  797.70  5072.2  797.98
  5113.8  807.46  5150.3  811.70  5193.0  815.43  5228.4  820.32  5250.3  821.17
#Mann=3,-1,0
  4597.2    0.12       0  5011.2    0.05       0  5016.4    0.12       0
Bank Sta=5011.2,5016.4
Exp/Cntr=0.3,0.1

Type RM Length L Ch R = 1,4638,541,541,541
BEGIN DESCRIPTION:
Heiser Creek 10.0
END DESCRIPTION:
XS GIS Cut Line= 3
      2239307.44     13862727.51      2238998.42     13863064.30
      2238574.97     13863375.02
#Sta/Elev= 30
  4450.9  864.89  4458.1  858.81  4464.9  859.79  4472.3  854.70  4479.1  854.62
  4486.4  850.81  4493.2  851.13  4500.6  847.89  4507.4  848.05  4514.8  844.24
  4521.6  843.04  4535.8  835.70  4570.9  825.94  4592.5  818.08  4641.8  807.43
  4677.6  797.42  4705.3  792.17  4712.7  792.21  4733.7  788.73  4755.3  796.52
  4769.5  797.11  4938.9  791.95  4965.6  786.44  4966.0  785.94  4970.8  786.44
  5024.5  789.71  5053.8  795.82  5083.2  798.42  5304.7  805.99  5433.2  814.77
#Mann=3,-1,0
  4450.9    0.12       0  4965.6    0.05       0  4970.8    0.12       0
Bank Sta=4965.6,4970.8
Exp/Cntr=0.3,0.1

Type RM Length L Ch R = 1,4097,451,451,451
BEGIN DESCRIPTION:
Heiser Creek 9.0
END DESCRIPTION:
XS GIS Cut Line= 3
      2238775.00     13862524.99      2238775.00     13862675.00
      2238625.00     13863074.99
#Sta/Elev= 30
  4850.4  900.95  4870.4  897.89  4880.4  895.11  4890.4  881.25  4900.4  864.88
  4910.4  855.56  4930.4  840.60  4940.4  834.27  4950.4  825.03  4970.4  812.21
  4990.4  785.26  4997.9  781.22  5010.2  781.72  5012.6  781.03  5013.1  780.53
  5018.4  781.03  5040.5  782.08  5064.5  785.56  5070.7  787.75  5107.2  789.51
  5125.9  790.12  5171.3  789.32  5192.6  784.63  5203.3  785.84  5211.3  787.87
  5241.6  789.82  5332.4  792.58  5363.5  795.57  5412.5  798.13  5427.6  798.11
#Mann=3,-1,0
  4850.4    0.12       0  5012.6    0.05       0  5018.4    0.12       0
Bank Sta=5012.6,5018.4
Exp/Cntr=0.3,0.1

Type RM Length L Ch R = 1,3646,447,447,447
BEGIN DESCRIPTION:
Heiser Creek 8.0
END DESCRIPTION:
XS GIS Cut Line= 3
      2238324.99     13862474.96      2238375.00     13862725.00
      2238356.06     13863474.07
#Sta/Elev= 30
  4739.9  929.86  4742.5  929.86  4760.3  919.46  4770.5  911.93  4790.9  899.50
  4811.3  884.33  4821.5  872.24  4831.7  861.81  4862.3  838.81  4892.9  808.76
  4903.1  799.70  4923.5  784.73  4943.9  779.76  4997.4  775.20  5001.9  772.26
  5002.4  771.76  5007.8  772.26  5034.9  780.04  5054.9  780.46  5074.9  783.94
  5133.4  786.40  5196.3  787.99  5277.3  792.76  5385.0  797.01  5431.4  801.10
  5565.1  811.56  5589.2  812.45  5675.1  820.02  5725.1  822.39  5744.2  824.69
#Mann=6,-1,0
  4739.9    0.12       0  5001.9    0.05       0  5007.8    0.12       0
  5133.4    0.07       0  5277.3   0.035       0  5431.4    0.12       0
Bank Sta=5001.9,5007.8
Exp/Cntr=0.3,0.1

Type RM Length L Ch R = 1,3199,466,466,466
BEGIN DESCRIPTION:
Heiser Creek 7.0
END DESCRIPTION:
XS GIS Cut Line= 3
      2238025.00     13862475.02      2237975.00     13862875.00
      2238015.78     13863484.44
#Sta/Elev= 30
  4596.5  938.09  4616.6  929.14  4634.3  916.97  4639.3  917.12  4714.9  865.62
  4719.9  865.09  4727.5  857.35  4795.5  818.57  4800.6  818.27  4876.1  780.79
  4881.2  781.77  4898.8  777.21  4961.8  772.07  4976.5  767.27  4977.0  766.77
  4982.4  767.27  5002.1  770.42  5019.6  778.17  5074.6  779.41  5109.8  785.76
  5202.2  788.25  5239.9  790.55  5260.2  790.46  5384.6  802.15  5388.7  802.56
  5470.6  810.85  5524.8  812.37  5540.8  817.61  5570.9  819.82  5610.4  826.90
#Mann=7,-1,0
  4596.5    0.12       0  4976.5    0.05       0  4982.4    0.12       0
  5202.2    0.07       0  5239.9   0.035       0  5384.6    0.12       0
  5388.7   0.035       0
Bank Sta=4976.5,4982.4
Exp/Cntr=0.3,0.1

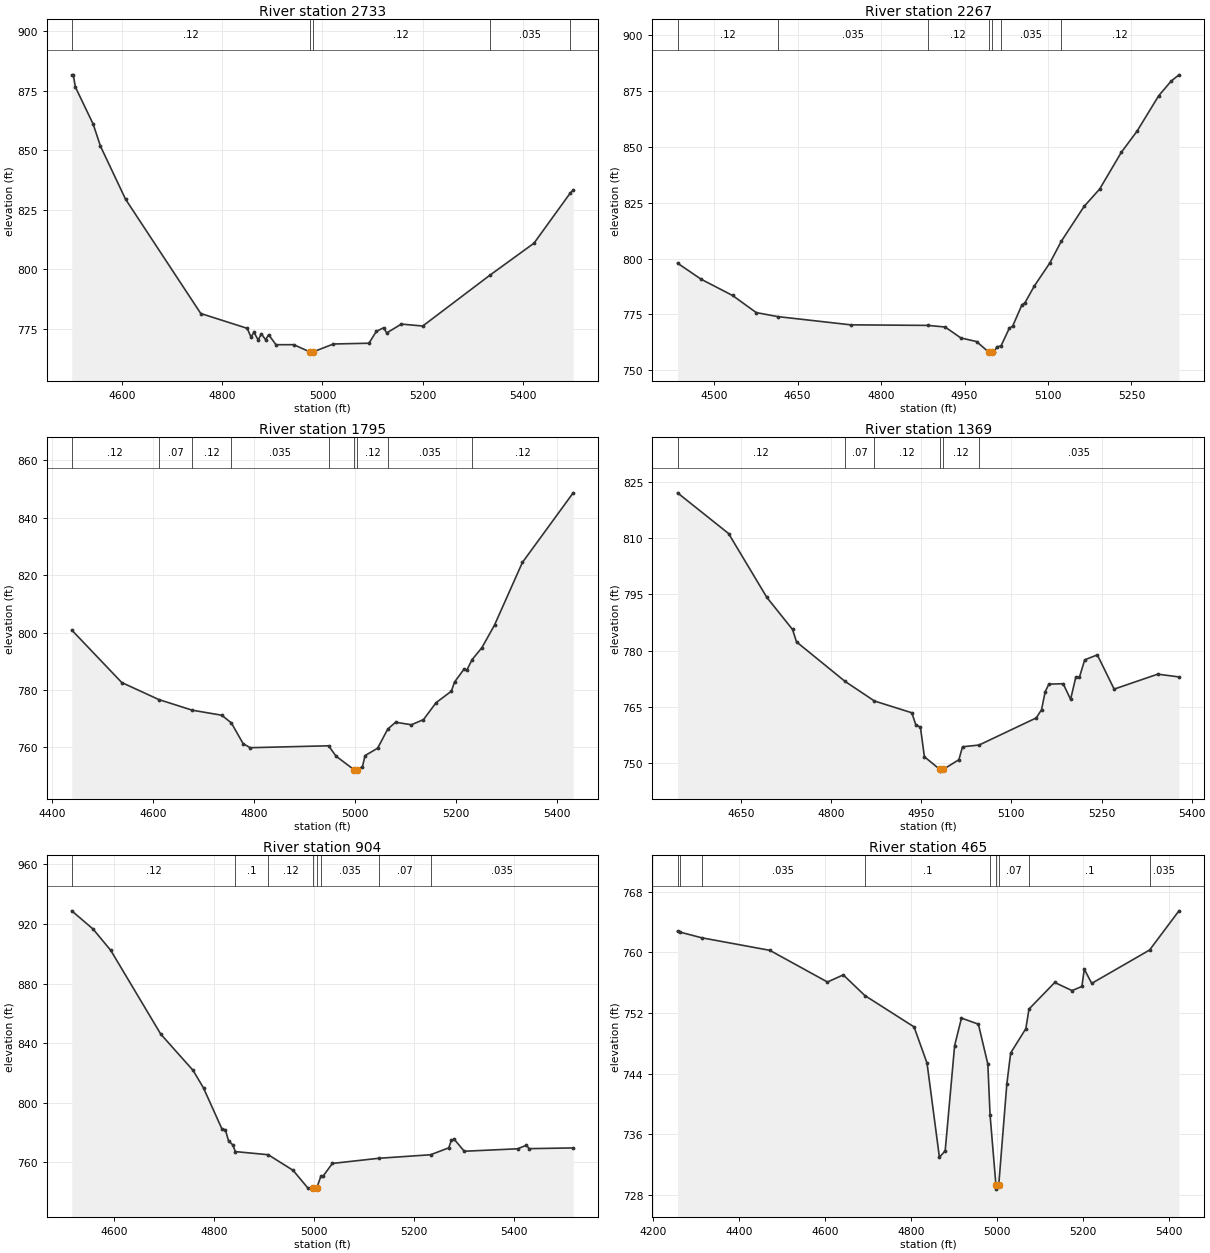
Type RM Length L Ch R = 1,2733,466,466,466
BEGIN DESCRIPTION:
Heiser Creek 6.0
END DESCRIPTION:
XS GIS Cut Line= 3
      2237825.00     13862525.00      2237525.00     13862925.00
      2237225.00     13863325.00
#Sta/Elev= 30
  4500.0  881.58  4503.1  881.58  4507.3  876.45  4542.7  860.94  4557.3  851.67
  4607.3  829.45  4757.3  781.54  4850.0  775.32  4857.3  771.73  4863.5  773.62
  4871.9  770.39  4878.1  773.05  4886.5  770.56  4892.7  772.65  4907.3  768.46
  4942.7  768.47  4975.1  765.43  4975.6  764.93  4981.1  765.43  5021.9  768.76
  5092.7  769.08  5107.3  774.01  5121.9  775.58  5128.1  773.39  5157.3  777.11
  5200.0  776.29  5333.5  797.53  5421.9  811.02  5493.7  831.90  5500.0  833.31
#Mann=5,-1,0
  4500.0    0.12       0  4975.1    0.05       0  4981.1    0.12       0
  5333.5   0.035       0  5493.7    0.12       0
Bank Sta=4975.1,4981.1
Exp/Cntr=0.3,0.1

Type RM Length L Ch R = 1,2267,472,472,472
BEGIN DESCRIPTION:
Heiser Creek 5.0
END DESCRIPTION:
XS GIS Cut Line= 3
      2237475.02     13862574.98      2237075.00     13862975.00
      2236925.01     13863274.98
#Sta/Elev= 30
  4434.2  797.93  4476.7  790.73  4533.2  783.46  4575.7  775.81  4613.9  774.03
  4745.4  770.33  4884.1  770.08  4915.1  769.36  4943.3  764.47  4971.6  762.85
  4993.3  758.17  4993.8  757.67  4999.4  758.17  5002.7  758.17  5008.3  760.54
  5015.4  760.83  5030.7  768.96  5036.3  769.66  5053.0  779.22  5058.6  780.23
  5075.4  787.71  5103.3  798.03  5123.7  807.65  5164.8  823.31  5192.8  831.10
  5231.9  847.59  5259.9  856.96  5299.0  872.88  5321.3  879.39  5335.3  882.20
#Mann=7,-1,0
  4434.2    0.12       0  4613.9   0.035       0  4884.1    0.12       0
  4993.3    0.05       0  4999.4    0.12       0  5015.4   0.035       0
  5123.7    0.12       0
Bank Sta=4993.3,4999.4
Exp/Cntr=0.3,0.1

Type RM Length L Ch R = 1,1795,426,426,426
BEGIN DESCRIPTION:
Heiser Creek 4.0
END DESCRIPTION:
XS GIS Cut Line= 3
      2237125.00     13862325.00      2236725.00     13862725.00
      2236574.99     13863125.02
#Sta/Elev= 30
  4439.1  800.92  4538.1  782.63  4611.6  776.69  4677.5  773.00  4736.1  771.24
  4755.2  768.55  4778.5  761.32  4792.6  759.92  4947.7  760.59  4962.4  756.98
  4998.1  752.26  4998.6  751.76  5004.3  752.26  5014.6  753.25  5019.9  757.17
  5044.8  759.75  5064.8  766.41  5080.4  768.80  5111.6  767.91  5135.6  769.71
  5160.5  775.61  5190.8  779.61  5197.0  782.78  5215.7  787.26  5221.1  786.86
  5231.9  790.63  5251.3  794.79  5276.2  802.64  5331.4  824.45  5432.0  848.72
#Mann=9,-1,0
  4439.1    0.12       0  4611.6    0.07       0  4677.5    0.12       0
  4755.2   0.035       0  4947.7    0.12       0  4998.1    0.05       0
  5004.3    0.12       0  5064.8   0.035       0  5231.9    0.12       0
Bank Sta=4998.1,5004.3
Exp/Cntr=0.3,0.1

Type RM Length L Ch R = 1,1369,465,465,465
BEGIN DESCRIPTION:
Heiser Creek 3.0
END DESCRIPTION:
XS GIS Cut Line= 3
      2236924.97     13862075.02      2236575.00     13862375.00
      2236265.79     13862585.14
#Sta/Elev= 30
  4544.1  822.12  4629.1  811.26  4692.8  794.22  4735.6  785.65  4742.2  782.34
  4823.1  771.79  4872.0  766.56  4934.2  763.42  4940.8  760.21  4948.5  759.57
  4955.1  751.69  4980.5  748.35  4981.0  747.85  4986.8  748.35  5012.5  750.89
  5018.6  754.35  5046.1  754.81  5141.3  762.05  5150.1  764.23  5156.2  769.04
  5162.3  771.06  5186.1  771.18  5198.5  767.01  5207.1  772.87  5213.1  772.85
  5222.0  777.55  5243.0  778.88  5271.0  769.74  5343.6  773.73  5378.9  772.99
#Mann=6,-1,0
  4544.1    0.12       0  4823.1    0.07       0  4872.0    0.12       0
  4980.5    0.05       0  4986.8    0.12       0  5046.1   0.035       0
Bank Sta=4980.5,4986.8
Exp/Cntr=0.3,0.1

Type RM Length L Ch R = 1,904,439,439,439
BEGIN DESCRIPTION:
Heiser Creek 2.0
END DESCRIPTION:
XS GIS Cut Line= 3
      2236725.00     13861574.99      2236425.00     13861975.00
      2236259.97     13862449.94
#Sta/Elev= 30
  4515.3  928.87  4558.0  916.62  4593.4  902.27  4693.4  846.03  4758.0  821.69
  4778.8  809.91  4815.3  782.67  4822.6  781.75  4828.8  774.44  4837.2  771.70
  4842.6  767.17  4908.2  765.08  4958.0  754.58  4987.2  742.84  4998.6  742.47
  4999.1  741.97  5004.9  742.47  5013.7  750.73  5018.0  750.73  5036.5  759.22
  5129.7  762.70  5232.8  765.05  5269.2  769.68  5274.5  774.71  5280.0  775.52
  5300.3  767.41  5407.0  769.06  5424.7  771.48  5430.0  769.16  5518.1  769.64
#Mann=8,-1,0
  4515.3    0.12       0  4842.6     0.1       0  4908.2    0.12       0
  4998.6    0.05       0  5004.9    0.12       0  5013.7   0.035       0
  5129.7    0.07       0  5232.8   0.035       0
Bank Sta=4998.6,5004.9
Exp/Cntr=0.3,0.1

Type RM Length L Ch R = 1,465,332,332,332
BEGIN DESCRIPTION:
Heiser Creek 1.0
END DESCRIPTION:
XS GIS Cut Line= 3
      2236045.35     13861378.72      2235975.00     13861975.00
      2236213.72     13862487.96
#Sta/Elev= 30
  4257.4  762.78  4262.8  762.69  4313.2  761.94  4472.0  760.28  4606.1  756.10
  4642.9  757.04  4693.0  754.32  4807.5  750.18  4837.7  745.40  4866.5  732.98
  4879.9  733.83  4901.9  747.72  4917.8  751.34  4957.1  750.54  4979.1  745.28
  4984.3  738.56  4998.0  729.28  4998.5  728.78  5004.4  729.28  5023.3  742.65
  5032.2  746.74  5067.4  749.94  5074.9  752.54  5134.7  756.04  5175.0  754.97
  5197.9  755.52  5203.4  757.80  5220.7  755.92  5355.3  760.32  5423.6  765.49
#Mann=9,-1,0
  4257.4   0.035       0  4262.8    0.07       0  4313.2   0.035       0
  4693.0     0.1       0  4984.3    0.07       0  4998.0    0.05       0
  5004.4    0.07       0  5074.9     0.1       0  5355.3   0.035       0
Bank Sta=4998,5004.4
Exp/Cntr=0.3,0.1

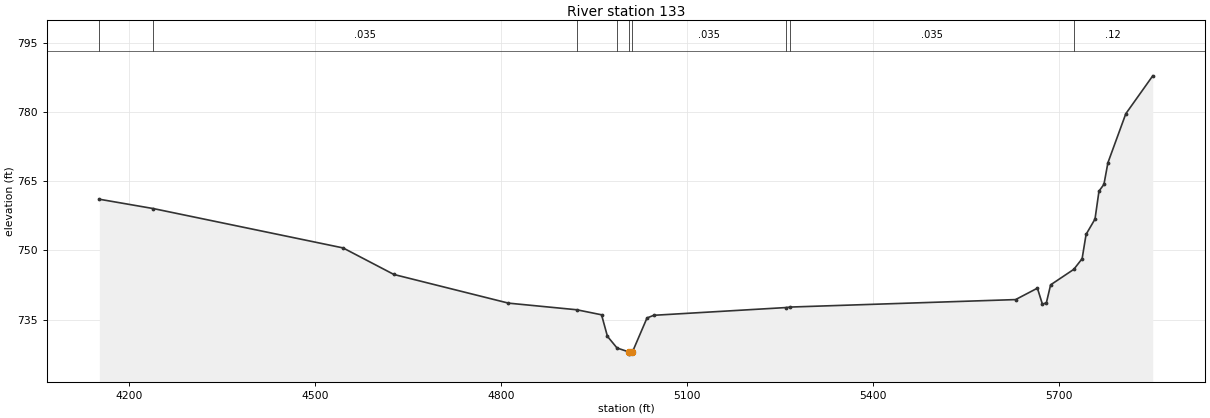
Type RM Length L Ch R = 1,133,0,0,0
BEGIN DESCRIPTION:
Heiser Creek 0.5
END DESCRIPTION:
XS GIS Cut Line= 4
      2235994.48     13861391.48      2235648.15     13861948.73
      2235757.52     13862284.67      2236187.23     13862823.76
#Sta/Elev= 30
  4152.5  761.13  4239.6  759.10  4545.5  750.56  4627.6  744.79  4812.3  738.57
  4922.5  737.13  4962.4  736.04  4971.9  731.36  4987.4  728.83  5005.9  728.00
  5006.4  727.50  5012.3  728.00  5035.7  735.35  5046.6  735.93  5259.8  737.61
  5266.9  737.72  5630.1  739.34  5665.3  741.82  5673.4  738.33  5679.8  738.67
  5686.6  742.54  5724.0  745.91  5737.4  748.22  5743.8  753.50  5758.2  756.83
  5764.6  762.89  5772.6  764.36  5779.0  769.05  5807.9  779.70  5851.3  787.92
#Mann=9,-1,0
  4152.5    0.07       0  4239.6   0.035       0  4922.5    0.07       0
  4987.4   0.035       0  5005.9   0.035       0  5012.3   0.035       0
  5259.8    0.07       0  5266.9   0.035       0  5724.0    0.12       0
Bank Sta=5005.9,5012.3
Exp/Cntr=0.3,0.1

Chan Stop Cuts=-1