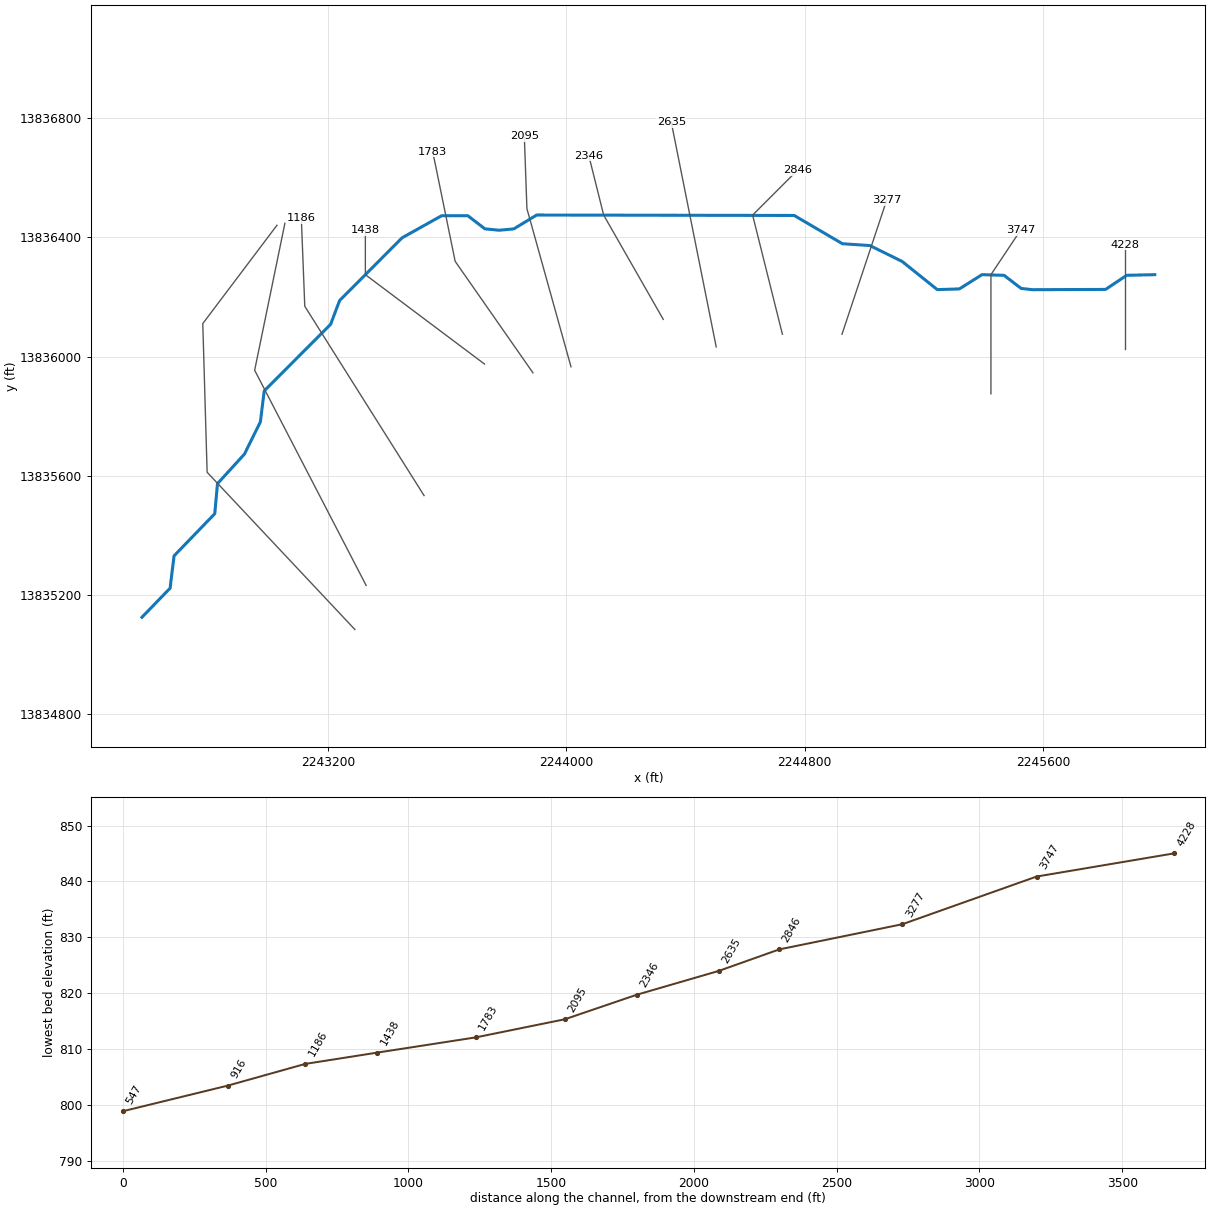
--- Isaac Creek Tributary 3.prj (project) ---

Proj Title=Isaac Creek Tributary 3 Base Level Engineering
Current Plan=p01
Default Exp/Contr=0.3,0.1
English Units
Geom File=g01
Flow File=f01
Plan File=p01
BEGIN DESCRIPTION:
Isaac Creek Tributary 3
END DESCRIPTION:

--- Isaac Creek Tributary 3.p01 (plan) ---

Plan Title=Multiple Run
Short Identifier=Multiple
Geom File=g01
Flow File=f01
Subcritical Flow
K Sum by GR= 0
Std Step Tol= 0.01
Critical Tol= 0.01
Num of Std Step Trials= 20
Max Error Tol= 0.3
Flow Tol Ratio= 0.001
Split Flow NTrial= 30
Split Flow Tol= 0.02
Split Flow Ratio= 0.02
Log Output Level= 0
Friction Slope Method= 1
Unsteady Friction Slope Method= 2
Unsteady Bridges Friction Slope Method= 1
Parabolic Critical Depth
Global Vel Dist=  1 , 1 , 1
Global Log Level= 0
CheckData=True
Encroach Param= -1, 0, 0, 0
BEGIN DESCRIPTION:
Multiple Run
END DESCRIPTION:

--- Isaac Creek Tributary 3.f01 (steady flow) ---

Flow Title=Multiple
Number of Profiles=7
Profile Names=10-year,25-year,50-year,1pct_min,100-year,1pct_plu,500-year
River Rch & RM= Isaac Creek Trib,Reach-1,4228
    1016    1682    2300    1522    3036    6058    5235
Boundary for River Rch & Prof#=Isaac Creek Trib,Reach-1,1
Up Type=0
Dn Type=3
Dn Slope=0.005
Boundary for River Rch & Prof#=Isaac Creek Trib,Reach-1,2
Up Type=0
Dn Type=3
Dn Slope=0.005
Boundary for River Rch & Prof#=Isaac Creek Trib,Reach-1,3
Up Type=0
Dn Type=3
Dn Slope=0.005
Boundary for River Rch & Prof#=Isaac Creek Trib,Reach-1,4
Up Type=0
Dn Type=3
Dn Slope=0.005
Boundary for River Rch & Prof#=Isaac Creek Trib,Reach-1,5
Up Type=0
Dn Type=3
Dn Slope=0.005
Boundary for River Rch & Prof#=Isaac Creek Trib,Reach-1,6
Up Type=0
Dn Type=3
Dn Slope=0.005
Boundary for River Rch & Prof#=Isaac Creek Trib,Reach-1,7
Up Type=0
Dn Type=3
Dn Slope=0.005

--- Isaac Creek Tributary 3.g01 (geometry) ---

Geom Title=Existing Conditions

River Reach=Isaac Creek Trib,Reach-1
Reach XY= 30
      2245975.00     13836275.00      2245880.87     13836272.90
      2245809.79     13836225.51      2245564.81     13836224.55
      2245526.56     13836228.78      2245469.02     13836272.83
      2245395.10     13836275.09      2245319.02     13836227.17
      2245245.05     13836224.79      2245127.29     13836319.15
      2245019.03     13836372.67      2244926.58     13836378.83
      2244764.50     13836473.80      2243899.92     13836475.20
      2243823.40     13836428.70      2243775.00     13836424.18
      2243726.60     13836428.71      2243669.03     13836472.83
      2243580.97     13836472.86      2243448.18     13836398.71
      2243238.63     13836188.21      2243208.35     13836108.33
      2242985.52     13835884.79      2242972.67     13835780.97
      2242919.15     13835672.71      2242828.63     13835573.50
      2242819.48     13835472.57      2242682.86     13835331.17
      2242669.54     13835222.55      2242575.00     13835125.00

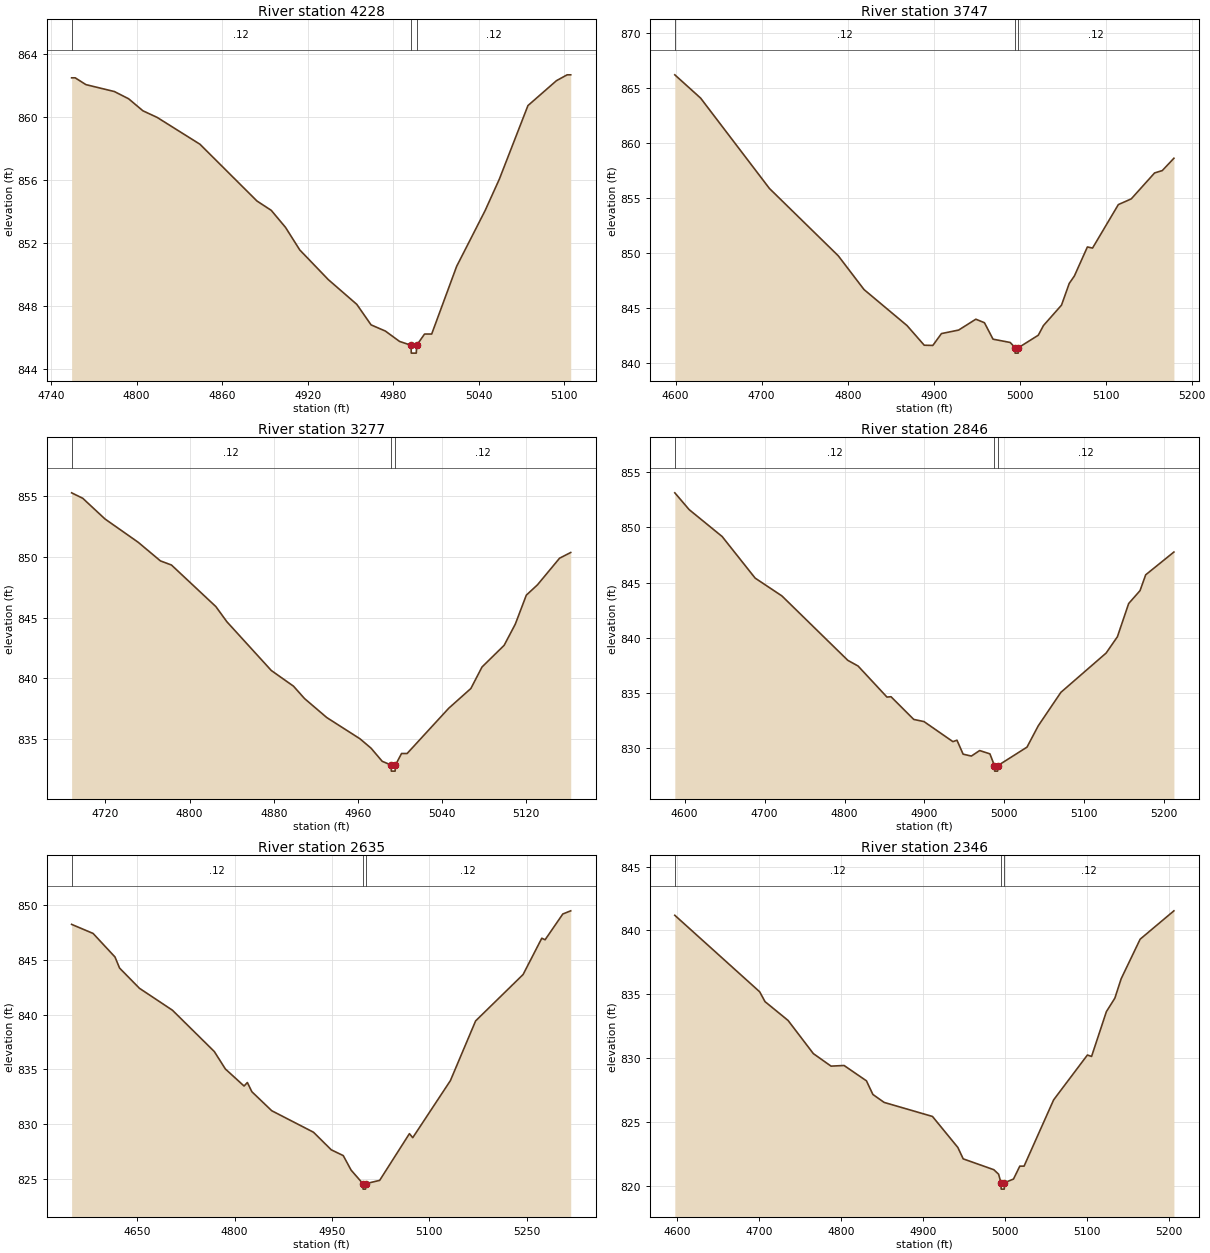
Type RM Length L Ch R = 1,4228,481,481,481
BEGIN DESCRIPTION:
Isaac Creek Tributary 3 7.0
END DESCRIPTION:
XS GIS Cut Line= 3
      2245875.00     13836025.05      2245875.00     13836275.00
      2245875.00     13836375.05
#Sta/Elev= 30
  4754.5  862.47  4757.0  862.47  4764.5  862.04  4784.5  861.60  4794.5  861.14
  4804.5  860.38  4814.5  859.96  4844.5  858.26  4884.5  854.66  4894.5  854.07
  4904.5  852.99  4914.5  851.56  4934.5  849.68  4954.5  848.11  4964.5  846.81
  4974.5  846.42  4984.5  845.76  4992.5  845.52  4992.7  845.02  4996.2  845.02
  4996.5  845.52  5002.0  846.23  5007.0  846.23  5024.5  850.52  5044.5  854.06
  5054.5  856.06  5074.5  860.71  5094.5  862.29  5102.0  862.66  5104.5  862.66
#Mann=3,-1,0
  4754.5    0.12       0  4992.5    0.05       0  4996.5    0.12       0
Bank Sta=4992.5,4996.5
Exp/Cntr=0.3,0.1

Type RM Length L Ch R = 1,3747,470,470,470
BEGIN DESCRIPTION:
Isaac Creek Tributary 3 6.0
END DESCRIPTION:
XS GIS Cut Line= 3
      2245425.00     13835874.96      2245425.00     13836275.00
      2245524.99     13836424.98
#Sta/Elev= 30
  4599.0  866.23  4629.0  864.11  4709.0  855.88  4789.0  849.75  4819.0  846.67
  4869.0  843.39  4889.0  841.60  4899.0  841.58  4909.0  842.66  4929.0  842.98
  4949.0  843.97  4959.0  843.65  4969.0  842.15  4989.0  841.85  4994.5  841.38
  4994.7  840.88  4998.3  840.88  4998.6  841.38  5021.6  842.51  5027.6  843.39
  5048.6  845.25  5057.6  847.23  5063.6  847.91  5078.7  850.55  5084.7  850.45
  5114.7  854.41  5129.7  854.93  5156.8  857.29  5165.8  857.51  5179.3  858.63
#Mann=3,-1,0
  4599.0    0.12       0  4994.5    0.05       0  4998.6    0.12       0
Bank Sta=4994.5,4998.6
Exp/Cntr=0.3,0.1

Type RM Length L Ch R = 1,3277,431,431,431
BEGIN DESCRIPTION:
Isaac Creek Tributary 3 5.0
END DESCRIPTION:
XS GIS Cut Line= 3
      2244924.99     13836074.96      2245025.00     13836375.00
      2245075.00     13836525.01
#Sta/Elev= 30
  4687.9  855.26  4698.5  854.81  4719.6  853.11  4751.2  851.19  4772.3  849.66
  4782.8  849.32  4825.0  845.90  4835.5  844.65  4877.7  840.64  4898.8  839.35
  4909.3  838.33  4930.4  836.77  4962.0  835.02  4972.5  834.25  4983.1  833.17
  4991.5  832.86  4991.8  832.36  4995.4  832.36  4995.7  832.86  5001.5  833.81
  5006.8  833.81  5046.3  837.53  5067.4  839.16  5078.0  840.93  5099.0  842.71
  5109.6  844.45  5120.1  846.84  5130.7  847.69  5151.7  849.88  5162.3  850.35
#Mann=3,-1,0
  4687.9    0.12       0  4991.5    0.05       0  4995.7    0.12       0
Bank Sta=4991.5,4995.7
Exp/Cntr=0.3,0.1

Type RM Length L Ch R = 1,2846,211,211,211
BEGIN DESCRIPTION:
Isaac Creek Tributary 3 4.0
END DESCRIPTION:
XS GIS Cut Line= 3
      2244724.99     13836075.03      2244625.00     13836475.00
      2244774.99     13836624.99
#Sta/Elev= 30
  4587.7  853.15  4605.7  851.62  4646.9  849.18  4688.2  845.40  4721.7  843.78
  4804.1  837.93  4817.0  837.41  4853.1  834.59  4858.2  834.62  4886.6  832.56
  4899.5  832.36  4935.6  830.54  4940.7  830.67  4948.4  829.40  4958.7  829.23
  4969.1  829.73  4981.9  829.43  4987.6  828.36  4987.9  827.86  4991.5  827.86
  4991.8  828.36  5028.3  830.04  5042.4  831.98  5070.7  835.02  5127.3  838.59
  5141.4  840.07  5155.5  843.09  5169.7  844.26  5176.8  845.70  5212.1  847.77
#Mann=3,-1,0
  4587.7    0.12       0  4987.6    0.05       0  4991.8    0.12       0
Bank Sta=4987.6,4991.8
Exp/Cntr=0.3,0.1

Type RM Length L Ch R = 1,2635,289,289,289
BEGIN DESCRIPTION:
A19461
END DESCRIPTION:
XS GIS Cut Line= 2
      2244502.76     13836032.57      2244351.89     13836786.93
#Sta/Elev= 30
  4548.8  848.27  4581.9  847.44  4615.7  845.28  4622.7  844.27  4653.3  842.42
  4704.2  840.41  4768.7  836.63  4785.8  835.03  4814.6  833.47  4819.7  833.79
  4826.6  832.95  4857.2  831.21  4921.6  829.24  4949.0  827.63  4967.5  827.10
  4979.6  825.77  4997.8  824.53  4998.1  824.03  5001.8  824.03  5002.1  824.53
  5023.6  824.83  5069.5  829.11  5074.6  828.74  5132.6  833.96  5171.5  839.43
  5244.7  843.68  5273.5  847.00  5278.6  846.86  5305.9  849.22  5318.1  849.51
#Mann=3,-1,0
  4548.8    0.12       0  4997.8    0.05       0  5002.1    0.12       0
Bank Sta=4997.8,5002.1
Exp/Cntr=0.3,0.1

Type RM Length L Ch R = 1,2346,251,251,251
BEGIN DESCRIPTION:
Isaac Creek Tributary 3 3.0
END DESCRIPTION:
XS GIS Cut Line= 3
      2244324.99     13836125.02      2244125.00     13836475.00
      2244075.01     13836674.96
#Sta/Elev= 30
  4596.9  841.18  4700.5  835.19  4707.0  834.42  4735.1  832.95  4766.0  830.35
  4787.6  829.37  4803.5  829.42  4830.8  828.22  4838.7  827.15  4852.4  826.53
  4911.4  825.43  4942.4  823.00  4948.9  822.11  4986.3  821.26  4992.1  820.91
  4995.0  820.24  4995.3  819.74  4999.0  819.74  4999.3  820.24  5010.3  820.53
  5018.0  821.54  5023.2  821.54  5059.3  826.73  5100.5  830.24  5105.6  830.13
  5123.7  833.64  5134.0  834.69  5141.7  836.21  5164.9  839.31  5206.1  841.53
#Mann=3,-1,0
  4596.9    0.12       0  4995.0    0.05       0  4999.3    0.12       0
Bank Sta=4995,4999.3
Exp/Cntr=0.3,0.1

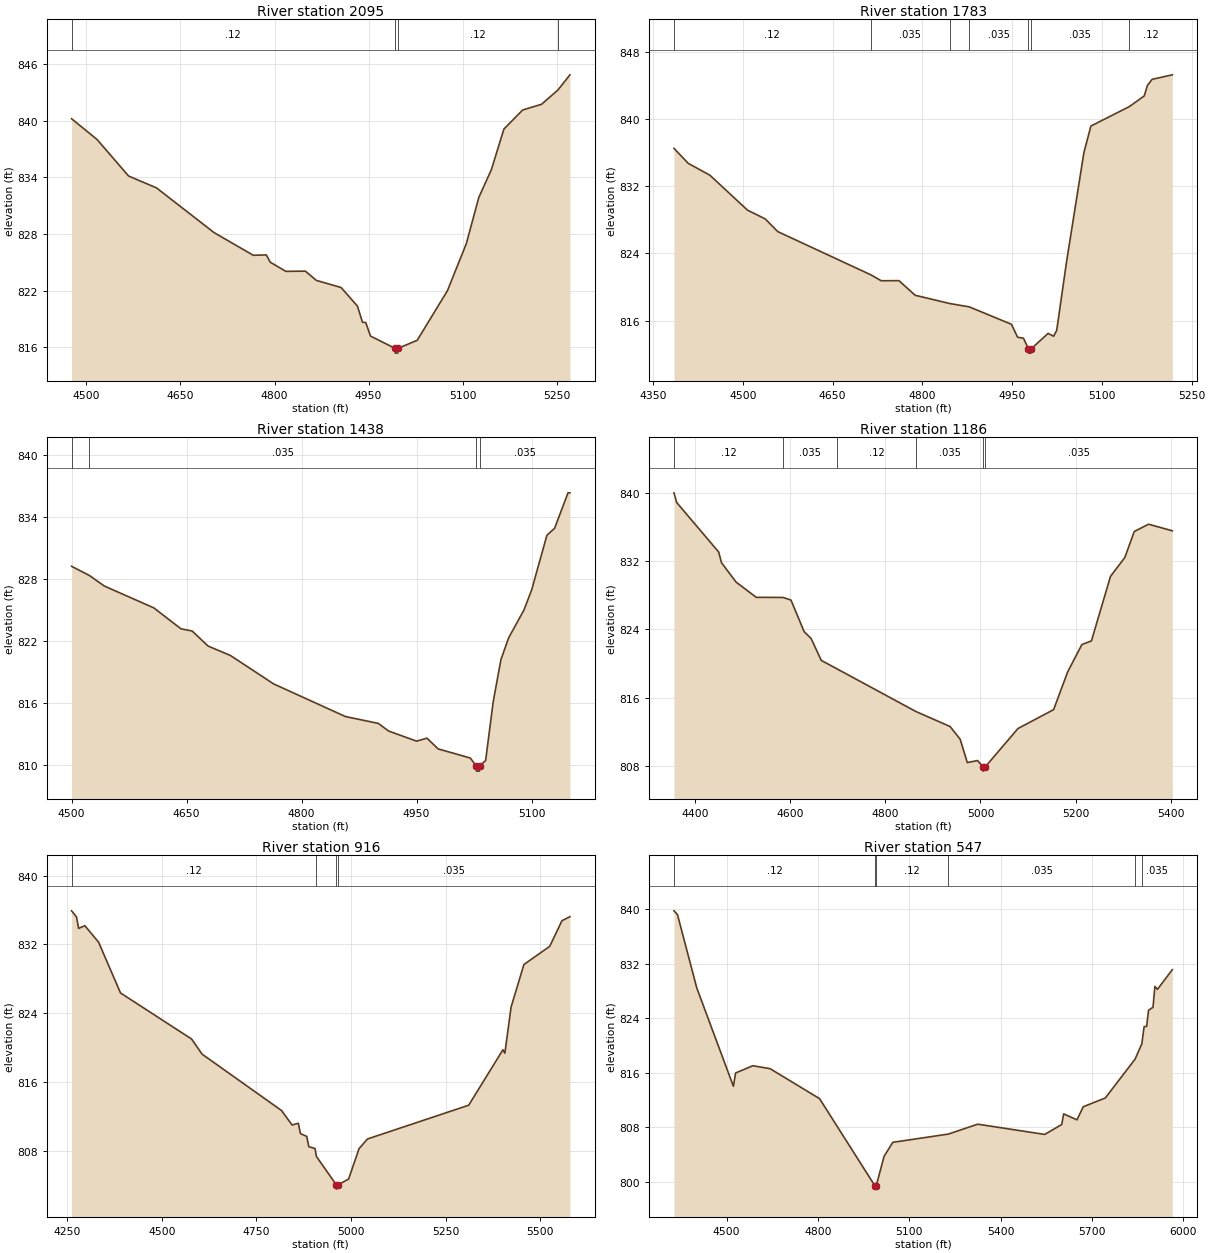
Type RM Length L Ch R = 1,2095,312,312,312
BEGIN DESCRIPTION:
A19460
END DESCRIPTION:
XS GIS Cut Line= 3
      2244015.31     13835965.81      2243867.34     13836496.76
      2243858.65     13836740.22
#Sta/Elev= 30
  4476.3  840.19  4517.0  837.99  4567.1  834.13  4611.7  832.87  4703.8  828.12
  4766.1  825.73  4786.9  825.77  4793.1  825.00  4818.0  824.03  4849.2  824.05
  4866.7  823.07  4906.1  822.32  4932.2  820.35  4940.3  818.63  4945.4  818.62
  4953.0  817.18  4992.3  815.87  4992.6  815.37  4996.4  815.37  4996.7  815.87
  5027.5  816.73  5075.8  821.99  5105.8  826.96  5125.8  831.86  5145.8  834.80
  5165.8  839.10  5195.8  841.12  5225.8  841.72  5251.9  843.23  5271.1  844.84
#Mann=4,-1,0
  4476.3    0.12       0  4992.3    0.05       0  4996.7    0.12       0
  5251.9   0.035       0
Bank Sta=4992.3,4996.7
Exp/Cntr=0.3,0.1

Type RM Length L Ch R = 1,1783,345,345,345
BEGIN DESCRIPTION:
A19459
END DESCRIPTION:
XS GIS Cut Line= 3
      2243887.65     13835945.48      2243626.52     13836319.77
      2243551.08     13836688.25
#Sta/Elev= 30
  4385.1  836.52  4408.9  834.73  4445.1  833.32  4507.9  829.16  4537.6  828.11
  4558.5  826.60  4713.8  821.46  4731.3  820.75  4760.9  820.76  4788.0  819.02
  4846.2  818.03  4878.4  817.64  4948.9  815.56  4959.1  814.03  4969.0  813.90
  4977.3  812.63  4977.6  812.13  4981.4  812.13  4981.7  812.63  5010.1  814.48
  5019.4  814.14  5024.5  814.85  5040.8  822.96  5069.9  836.01  5081.6  839.17
  5145.6  841.48  5170.7  842.76  5175.9  843.99  5183.7  844.73  5217.6  845.27
#Mann=7,-1,0
  4385.1    0.12       0  4713.8   0.035       0  4846.2    0.12       0
  4878.4   0.035       0  4977.3   0.035       0  4981.7   0.035       0
  5145.6    0.12       0
Bank Sta=4977.3,4981.7
Exp/Cntr=0.3,0.1

Type RM Length L Ch R = 1,1438,252,252,252
BEGIN DESCRIPTION:
Isaac Creek Tributary 3 1.0
END DESCRIPTION:
XS GIS Cut Line= 3
      2243724.96     13835975.03      2243325.00     13836275.00
      2243325.00     13836425.05
#Sta/Elev= 30
  4500.0  829.23  4523.3  828.34  4542.7  827.32  4607.2  825.21  4642.7  823.18
  4657.2  822.97  4678.1  821.51  4707.2  820.60  4763.5  817.85  4857.2  814.69
  4900.0  814.03  4913.5  813.29  4950.0  812.31  4963.5  812.60  4978.1  811.56
  5020.0  810.68  5027.8  809.91  5028.1  809.41  5031.9  809.41  5032.2  809.91
  5040.0  810.43  5050.0  816.16  5060.0  820.20  5070.0  822.30  5090.0  825.00
  5100.0  826.93  5120.0  832.24  5130.0  832.91  5147.5  836.34  5150.0  836.34
#Mann=4,-1,0
  4500.0    0.12       0  4523.3   0.035       0  5027.8   0.035       0
  5032.2   0.035       0
Bank Sta=5027.8,5032.2
Exp/Cntr=0.3,0.1

Type RM Length L Ch R = 1,1186,270,270,270
BEGIN DESCRIPTION:
A19458
END DESCRIPTION:
XS GIS Cut Line= 3
      2243522.05     13835533.50      2243121.66     13836168.90
      2243110.06     13836464.84
#Sta/Elev= 30
  4356.0  840.01  4361.8  838.87  4450.0  833.07  4455.9  831.82  4486.5  829.55
  4528.9  827.76  4585.0  827.75  4601.9  827.44  4629.6  823.73  4644.3  822.93
  4665.5  820.37  4699.2  819.36  4864.3  814.38  4936.2  812.62  4957.4  811.13
  4972.4  808.39  4993.9  808.63  5005.6  807.89  5005.9  807.39  5010.1  807.89
  5078.8  812.38  5153.8  814.60  5183.2  819.01  5213.2  822.23  5233.2  822.65
  5273.3  830.22  5303.3  832.42  5323.3  835.48  5353.3  836.33  5403.2  835.56
#Mann=6,-1,0
  4356.0    0.12       0  4585.0   0.035       0  4699.2    0.12       0
  4864.3   0.035       0  5005.6   0.035       0  5010.1   0.035       0
Bank Sta=5005.6,5010.1
Exp/Cntr=0.3,0.1

Type RM Length L Ch R = 1,916,369,369,369
BEGIN DESCRIPTION:
A19457
END DESCRIPTION:
XS GIS Cut Line= 3
      2243327.66     13835231.73      2242953.38     13835954.19
      2243054.92     13836447.39
#Sta/Elev= 30
  4261.3  835.90  4274.3  835.19  4279.9  833.86  4296.4  834.17  4332.6  832.26
  4390.6  826.35  4578.5  820.99  4606.3  819.23  4816.3  812.67  4844.1  810.99
  4860.6  811.19  4866.2  809.99  4882.7  809.67  4888.3  808.47  4904.8  808.25
  4908.4  807.33  4961.0  804.03  4961.3  803.53  4965.5  804.03  4993.4  804.70
  5021.1  808.24  5043.3  809.36  5310.9  813.29  5401.4  819.74  5406.5  819.34
  5422.9  824.70  5456.8  829.65  5525.0  831.77  5557.4  834.75  5578.5  835.22
#Mann=4,-1,0
  4261.3    0.12       0  4908.4   0.035       0  4961.0   0.035       0
  4965.5   0.035       0
Bank Sta=4961,4965.5
Exp/Cntr=0.3,0.1

Type RM Length L Ch R = 1,547,0,0,0
BEGIN DESCRIPTION:
A19456
END DESCRIPTION:
XS GIS Cut Line= 4
      2243289.92     13835083.77      2242793.80     13835611.81
      2242779.29     13836110.87      2243028.19     13836440.80
#Sta/Elev= 30
  4326.9  839.73  4338.4  839.19  4401.9  828.42  4522.1  814.01  4529.4  815.96
  4586.0  817.02  4642.7  816.59  4805.3  812.19  4986.8  799.43  4987.1  798.93
  4991.3  799.43  5017.3  803.75  5045.7  805.79  5228.2  807.00  5324.7  808.45
  5544.8  806.95  5600.7  808.40  5607.0  809.96  5650.7  809.09  5671.5  811.01
  5743.8  812.29  5841.4  817.97  5863.8  820.22  5871.3  822.74  5879.6  822.79
  5885.9  825.16  5900.5  825.58  5906.7  828.65  5915.0  828.21  5964.0  831.11
#Mann=6,-1,0
  4326.9    0.12       0  4986.8    0.05       0  4991.3    0.12       0
  5228.2   0.035       0  5841.4    0.12       0  5863.8   0.035       0
Bank Sta=4986.8,4991.3
Exp/Cntr=0.3,0.1

Chan Stop Cuts=-1