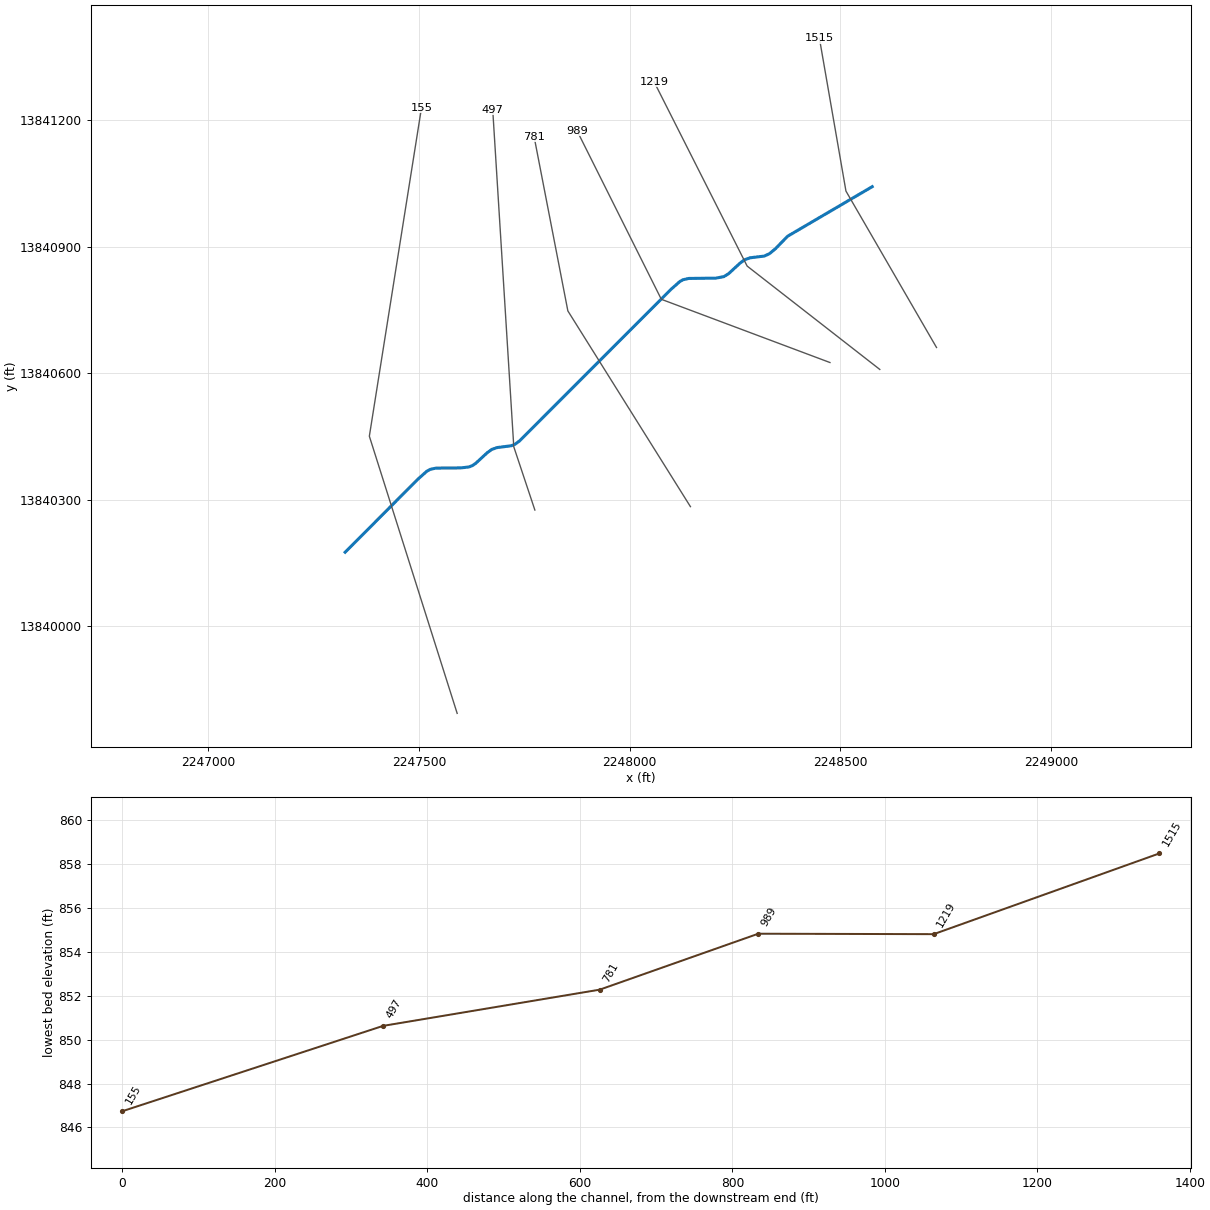
--- Isaac Creek Tributary 4.prj (project) ---

Proj Title=Isaac Creek Tributary 4 Base Level Engineering
Current Plan=p01
Default Exp/Contr=0.3,0.1
English Units
Geom File=g01
Flow File=f01
Plan File=p01
BEGIN DESCRIPTION:
Isaac Creek Tributary 4
END DESCRIPTION:

--- Isaac Creek Tributary 4.p01 (plan) ---

Plan Title=Multiple Run
Short Identifier=Multiple
Geom File=g01
Flow File=f01
Subcritical Flow
K Sum by GR= 0
Std Step Tol= 0.01
Critical Tol= 0.01
Num of Std Step Trials= 20
Max Error Tol= 0.3
Flow Tol Ratio= 0.001
Split Flow NTrial= 30
Split Flow Tol= 0.02
Split Flow Ratio= 0.02
Log Output Level= 0
Friction Slope Method= 1
Unsteady Friction Slope Method= 2
Unsteady Bridges Friction Slope Method= 1
Parabolic Critical Depth
Global Vel Dist=  1 , 1 , 1
Global Log Level= 0
CheckData=True
Encroach Param= -1, 0, 0, 0
BEGIN DESCRIPTION:
Multiple Run
END DESCRIPTION:

--- Isaac Creek Tributary 4.f01 (steady flow) ---

Flow Title=Multiple
Number of Profiles=7
Profile Names=10-year,25-year,50-year,1pct_min,100-year,1pct_plu,500-year
River Rch & RM= Isaac Creek Trib,Reach-1,1515
    1005    1670    2290    1521    3035    6055    5269
Boundary for River Rch & Prof#=Isaac Creek Trib,Reach-1,1
Up Type=0
Dn Type=3
Dn Slope=0.005
Boundary for River Rch & Prof#=Isaac Creek Trib,Reach-1,2
Up Type=0
Dn Type=3
Dn Slope=0.005
Boundary for River Rch & Prof#=Isaac Creek Trib,Reach-1,3
Up Type=0
Dn Type=3
Dn Slope=0.005
Boundary for River Rch & Prof#=Isaac Creek Trib,Reach-1,4
Up Type=0
Dn Type=3
Dn Slope=0.005
Boundary for River Rch & Prof#=Isaac Creek Trib,Reach-1,5
Up Type=0
Dn Type=3
Dn Slope=0.005
Boundary for River Rch & Prof#=Isaac Creek Trib,Reach-1,6
Up Type=0
Dn Type=3
Dn Slope=0.005
Boundary for River Rch & Prof#=Isaac Creek Trib,Reach-1,7
Up Type=0
Dn Type=3
Dn Slope=0.005

--- Isaac Creek Tributary 4.g01 (geometry) ---

Geom Title=Existing Conditions

River Reach=Isaac Creek Trib,Reach-1
Reach XY= 30
      2248575.26     13841042.19      2248374.38     13840924.45
      2248345.92     13840895.14      2248331.15     13840882.91
      2248318.96     13840877.51      2248285.63     13840873.49
      2248272.78     13840868.97      2248261.95     13840860.99
      2248234.66     13840835.82      2248223.42     13840828.82
      2248204.90     13840825.23      2248140.22     13840824.48
      2248126.50     13840821.39      2248118.83     13840817.14
      2248098.13     13840798.82      2247738.22     13840438.62
      2247727.30     13840430.83      2247718.97     13840427.50
      2247685.71     13840423.28      2247672.83     13840418.86
      2247661.96     13840410.95      2247634.65     13840385.84
      2247627.32     13840380.77      2247619.03     13840377.33
      2247600.00     13840375.00      2247540.22     13840374.48
      2247526.50     13840371.39      2247518.83     13840367.14
      2247498.13     13840348.82      2247325.00     13840175.00

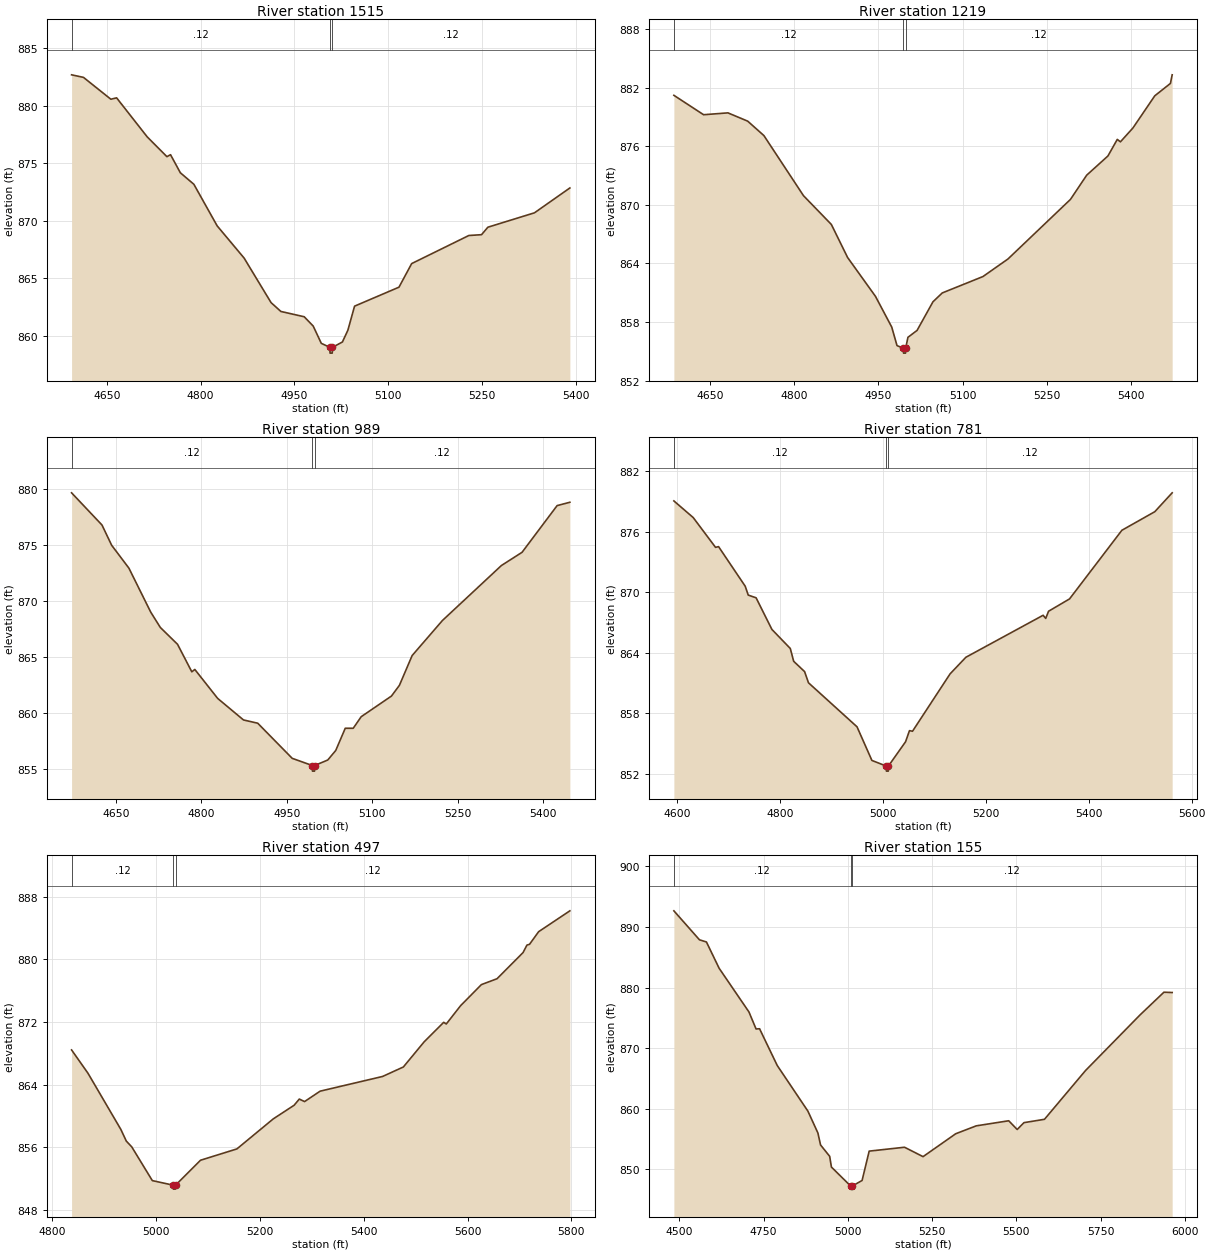
Type RM Length L Ch R = 1,1515,296,296,296
BEGIN DESCRIPTION:
A19465
END DESCRIPTION:
XS GIS Cut Line= 3
      2248727.83     13840660.67      2248512.98     13841031.77
      2248450.05     13841394.14
#Sta/Elev= 30
  4593.7  882.67  4612.7  882.45  4656.5  880.55  4665.7  880.67  4714.6  877.28
  4746.1  875.56  4751.9  875.73  4767.6  874.16  4789.2  873.16  4826.4  869.55
  4869.5  866.75  4912.6  862.88  4928.3  862.11  4965.6  861.65  4980.0  860.84
  4992.9  859.34  5006.7  858.99  5006.9  858.49  5010.4  858.49  5010.7  858.99
  5026.7  859.46  5035.4  860.48  5046.1  862.57  5117.1  864.22  5137.4  866.27
  5228.8  868.71  5249.1  868.78  5259.2  869.43  5333.7  870.68  5390.3  872.84
#Mann=3,-1,0
  4593.7    0.12       0  5006.7    0.05       0  5010.7    0.12       0
Bank Sta=5006.7,5010.7
Exp/Cntr=0.3,0.1

Type RM Length L Ch R = 1,1219,230,230,230
BEGIN DESCRIPTION:
A19464
END DESCRIPTION:
XS GIS Cut Line= 3
      2248593.25     13840608.61      2248278.60     13840853.82
      2248057.79     13841291.12
#Sta/Elev= 30
  4585.1  881.24  4638.1  879.25  4681.5  879.44  4716.8  878.59  4745.7  877.11
  4816.3  870.95  4866.0  868.00  4895.0  864.61  4944.7  860.63  4973.7  857.48
  4983.1  855.58  4994.5  855.31  4994.8  854.81  4998.3  854.81  4998.5  855.31
  5002.6  856.43  5018.9  857.14  5047.2  860.07  5063.8  860.98  5136.4  862.66
  5181.0  864.46  5292.5  870.57  5321.4  873.05  5359.3  875.02  5376.0  876.72
  5381.6  876.47  5403.9  877.89  5442.9  881.19  5470.8  882.46  5473.9  883.34
#Mann=3,-1,0
  4585.1    0.12       0  4994.5    0.05       0  4998.5    0.12       0
Bank Sta=4994.5,4998.5
Exp/Cntr=0.3,0.1

Type RM Length L Ch R = 1,989,208,208,208
BEGIN DESCRIPTION:
Isaac Creek Tributary 4 2.0
END DESCRIPTION:
XS GIS Cut Line= 3
      2248475.04     13840624.99      2248075.00     13840775.00
      2247874.98     13841175.04
#Sta/Elev= 30
  4572.5  879.63  4625.9  876.76  4642.8  874.96  4673.1  872.92  4711.4  869.00
  4728.3  867.63  4758.5  866.13  4783.5  863.68  4788.8  863.89  4828.9  861.31
  4874.2  859.39  4899.2  859.10  4959.7  855.97  4995.0  855.33  4995.3  854.83
  4998.8  854.83  4999.1  855.33  5022.1  855.82  5036.1  856.67  5052.8  858.65
  5066.8  858.65  5080.8  859.68  5133.9  861.52  5147.9  862.48  5170.2  865.13
  5223.3  868.25  5326.8  873.15  5363.1  874.33  5424.6  878.49  5447.0  878.79
#Mann=3,-1,0
  4572.5    0.12       0  4995.0    0.05       0  4999.1    0.12       0
Bank Sta=4995,4999.1
Exp/Cntr=0.3,0.1

Type RM Length L Ch R = 1,781,284,284,284
BEGIN DESCRIPTION:
A19463
END DESCRIPTION:
XS GIS Cut Line= 3
      2248144.04     13840283.10      2247853.26     13840747.48
      2247773.15     13841160.98
#Sta/Elev= 30
  4593.0  879.05  4630.6  877.40  4674.0  874.45  4679.9  874.52  4731.7  870.60
  4737.6  869.72  4752.9  869.45  4783.6  866.32  4819.4  864.43  4826.0  863.16
  4847.2  862.14  4854.8  861.03  4949.2  856.67  4978.1  853.34  5006.1  852.78
  5006.4  852.28  5010.0  852.28  5010.2  852.78  5043.6  855.19  5051.2  856.29
  5057.1  856.23  5130.1  861.91  5160.9  863.56  5311.1  867.72  5316.2  867.41
  5321.7  868.12  5362.5  869.34  5464.3  876.14  5528.3  877.98  5562.1  879.85
#Mann=3,-1,0
  4593.0    0.12       0  5006.1    0.05       0  5010.2    0.12       0
Bank Sta=5006.1,5010.2
Exp/Cntr=0.3,0.1

Type RM Length L Ch R = 1,497,342,342,342
BEGIN DESCRIPTION:
Isaac Creek Tributary 4 1.0
END DESCRIPTION:
XS GIS Cut Line= 3
      2247775.00     13840275.01      2247725.00     13840425.00
      2247675.00     13841225.04
#Sta/Elev= 30
  4837.3  868.42  4868.9  865.44  4932.2  858.26  4942.7  856.77  4953.2  856.03
  4992.8  851.72  5033.4  851.13  5033.7  850.63  5037.3  850.63  5037.5  851.13
  5085.6  854.32  5155.7  855.77  5225.8  859.61  5265.9  861.35  5275.9  862.14
  5286.0  861.82  5316.0  863.15  5436.3  865.03  5476.3  866.24  5516.4  869.46
  5554.0  871.95  5559.0  871.74  5586.6  874.08  5626.6  876.77  5656.7  877.52
  5706.8  880.86  5714.3  881.82  5719.3  881.92  5736.8  883.53  5797.0  886.20
#Mann=3,-1,0
  4837.3    0.12       0  5033.4    0.05       0  5037.5    0.12       0
Bank Sta=5033.4,5037.5
Exp/Cntr=0.3,0.1

Type RM Length L Ch R = 1,155,0,0,0
BEGIN DESCRIPTION:
A19462
END DESCRIPTION:
XS GIS Cut Line= 3
      2247590.67     13839792.60      2247382.34     13840450.17
      2247506.03     13841229.23
#Sta/Elev= 30
  4483.7  892.66  4559.6  887.88  4580.3  887.52  4617.9  883.19  4706.5  875.97
  4727.5  873.17  4738.0  873.20  4790.4  867.14  4881.4  859.61  4911.1  856.00
  4918.9  854.03  4946.0  852.15  4951.2  850.38  5008.5  847.24  5008.8  846.74
  5012.7  847.24  5042.2  848.17  5063.2  853.01  5168.1  853.65  5223.1  852.10
  5320.1  855.88  5380.9  857.18  5477.3  858.02  5502.4  856.58  5522.6  857.71
  5583.4  858.26  5704.9  866.29  5866.9  875.48  5937.8  879.23  5962.3  879.18
#Mann=3,-1,0
  4483.7    0.12       0  5008.5    0.05       0  5012.7    0.12       0
Bank Sta=5008.5,5012.7
Exp/Cntr=0.3,0.1

Chan Stop Cuts=-1