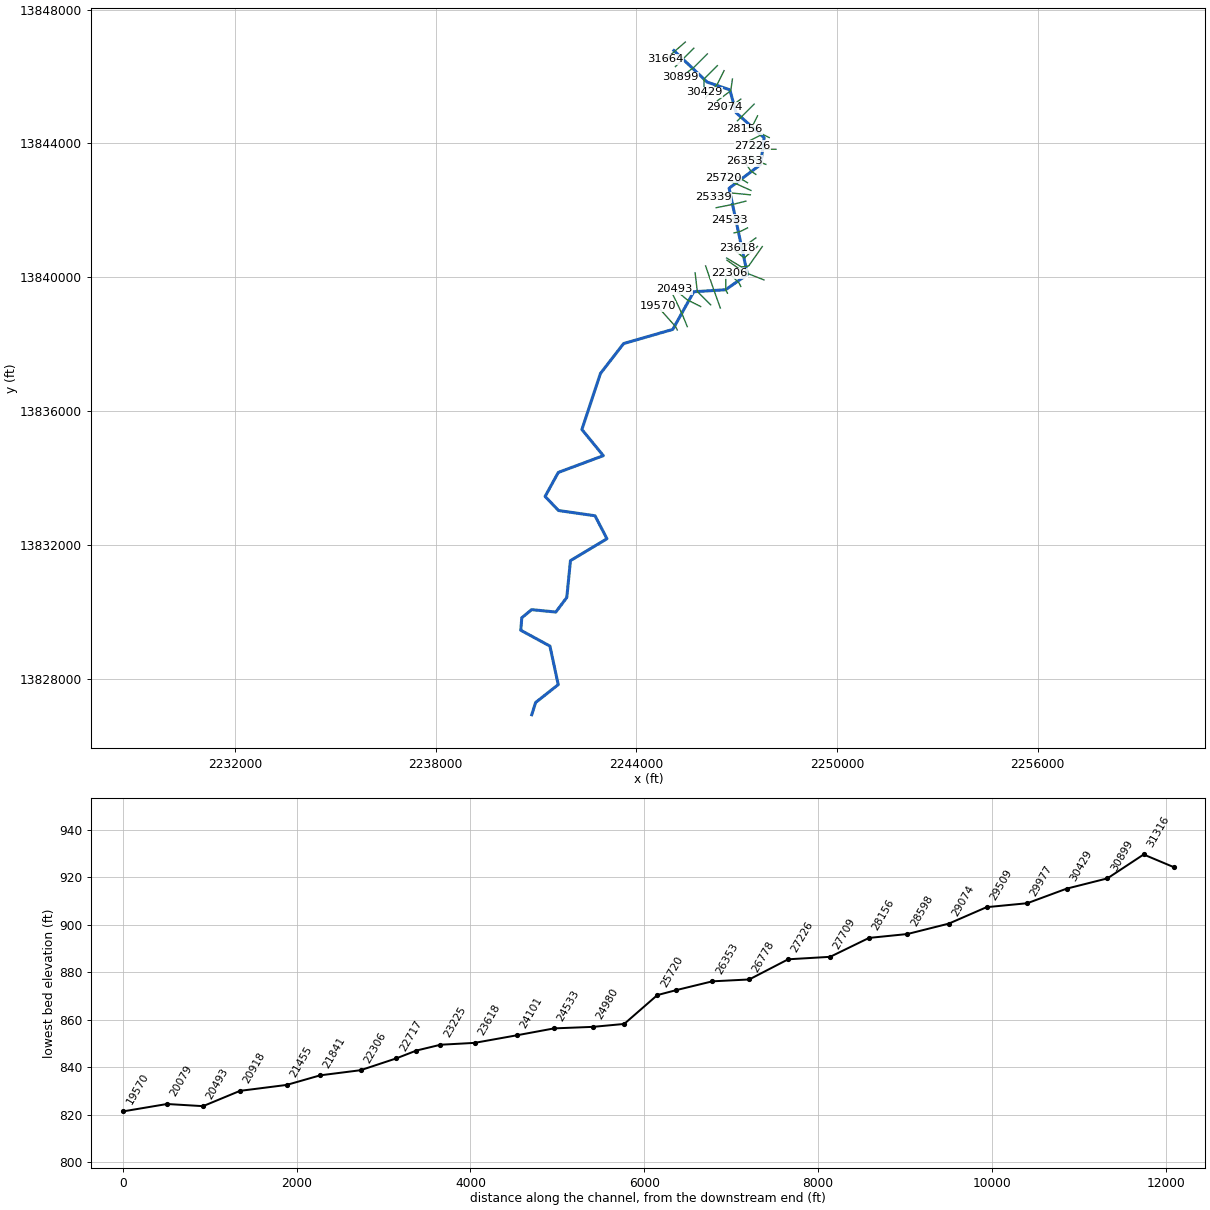
--- Isaac Creek.prj (project) ---

Proj Title=Isaac Creek Base Level Engineering
Current Plan=p01
Default Exp/Contr=0.3,0.1
English Units
Geom File=g01
Flow File=f01
Plan File=p01
Y Axis Title=Elevation
X Axis Title(PF)=Main Channel Distance
X Axis Title(XS)=Station
BEGIN DESCRIPTION:
Isaac Creek
END DESCRIPTION:
DSS Export Rating Curves= 0
DSS Export Rating Curve Sorted= 0
DSS Export Volume Flow Curves= 0
DXF OffsetX= 0
DXF OffsetY= 0
DXF ScaleX= 1
DXF ScaleY= 10

--- Isaac Creek.p01 (plan) ---

Plan Title=Multiple Run
Program Version=4.10
Short Identifier=Multiple
Geom File=g01
Flow File=f01
Subcritical Flow
K Sum by GR= 0
Std Step Tol= 0.01
Critical Tol= 0.01
Num of Std Step Trials= 20
Max Error Tol= 0.3
Flow Tol Ratio= 0.001
Split Flow NTrial= 30
Split Flow Tol= 0.02
Split Flow Ratio= 0.02
Log Output Level= 0
Friction Slope Method= 1
Unsteady Friction Slope Method= 2
Unsteady Bridges Friction Slope Method= 1
Parabolic Critical Depth
Global Vel Dist= 1 , 1 , 1
Global Log Level= 0
CheckData=True
Encroach Param=-1 ,0,0, 0
BEGIN DESCRIPTION:
Multiple Run
END DESCRIPTION:
Computation Interval=1HOUR
Output Interval=1HOUR
Run HTab= 0
Run UNet= 0
Run PostProcess= 0
Run WQNet= 0
UNET Theta= 1
UNET Theta Warmup= 1
UNET ZTol= 0.02
UNET ZSATol= 0.05
UNET MxIter= 20
UNET MaxInSteps= 0
UNET DtIC= 0
UNET DtMin= 0
UNET MaxCRTS= 20
UNET WFStab= 2
UNET SFStab= 1
UNET WFX= 1
UNET SFX= 1
UNET DSS MLevel= 4
UNET DZMax Abort= 100
UNET Convert EG Bridges= 0
UNET Use Existing IB Tables=-1
UNET Froude Reduction=False
UNET Froude Limit= 1
UNET Froude Power= 10
UNET Time Slicing=0,0, 5
UNET Junction Losses=0
Instantaneous Interval=1HOUR
Write IC File= 0
Write IC File at Sim End=0
Echo Input=False
Echo Parameters=False
Echo Output=False
Write Detailed= 0
WQ AD Non Conservative
WQ ULTIMATE=-1
WQ Max Comp Step=1HOUR
WQ Output Interval=15MIN
WQ Output Selected Increments= 0
WQ Output face flow=0
WQ Output face velocity=0
WQ Output face area=0
WQ Output face dispersion=0
WQ Output cell volume=0
WQ Output cell surface area=0
WQ Output cell continuity=0
WQ Output cumulative cell continuity=0
WQ Output face conc=0
WQ Output face dconc_dx=0
WQ Output face courant=0
WQ Output face peclet=0
WQ Output face adv mass=0
WQ Output face disp mass=0
WQ Output cell mass=0
WQ Output cell source sink temp=0
WQ Output cell source sink nsm=0
WQ Output MaxMinRange=-1
WQ Daily Max Min Mean=-1
WQ Daily Range=0
WQ Daily Time=0
WQ Create Restart=0
WQ Fixed Restart=0
WQ System Summary=0
WQ Use Fixed Temperature=0
Sorting and Armoring Iterations= 10
XS Update Threshold= 0.02
Hydraulics Update Threshold= 0.02
Energy Slope Method= 1
Volume Change Method= 0
XS Weighting Method= 0
Number of US Weighted Cross Sections= 1
Number of DS Weighted Cross Sections= 1
Upstream XS Weight=0.25
Main XS Weight=0.5
Downstream XS Weight=0.25
Number of DS XS's Weighted with US Boundary= 1
Upstream Boundary Weight= 1
Weight of XSs Associated with US Boundary= 0
Number of US XS's Weighted with DS Boundary= 1
Downstream Boundary Weight= 0.5
Weight of XSs Associated with DS Boundary= 0.5
Sediment Output Level= 4
Mass or Volume Output= 0
Output Increment Type= 1
Profile and TS Output Increment= 10
XS Output Flag= 0
XS Output Increment= 10
Disregard all LS=0
Disregard all Conn=0
Disregard all Breaches=0
Disregard all Pumps=0

--- Isaac Creek.f01 (steady flow) ---

Flow Title=Multiple
Number of Profiles=7
Profile Names=10-year,25-year,50-year,1pct_min,100-year,1pct_plu,500-year
River Rch & RM= Isaac Creek,Reach-1,31664
    1284    2168    3006    2016    4022    8026    7127
River Rch & RM= Isaac Creek,Reach-1,27709
    1797    3087    4328    2932    5850   11672   10582
River Rch & RM= Isaac Creek,Reach-1,25339
    1859    3191    4471    3026    6038   12047   10902
River Rch & RM= Isaac Creek,Reach-1,22717
    2593    4498    6343    4315    8610   17179   15708
River Rch & RM= Isaac Creek,Reach-1,14587
    3266    5709    8094    5530   11034   22016   20310
River Rch & RM= Isaac Creek,Reach-1,6362
    3599    6351    9062    6229   12428   24798   23165
River Rch & RM= Isaac Creek,Reach-1,1830
    3642    6432    9181    6314   12598   25136   23503
Boundary for River Rch & Prof#=Isaac Creek,Reach-1,1
Up Type=0
Dn Type=3
Dn Slope=0.005
Boundary for River Rch & Prof#=Isaac Creek,Reach-1,2
Up Type=0
Dn Type=3
Dn Slope=0.005
Boundary for River Rch & Prof#=Isaac Creek,Reach-1,3
Up Type=0
Dn Type=3
Dn Slope=0.005
Boundary for River Rch & Prof#=Isaac Creek,Reach-1,4
Up Type=0
Dn Type=3
Dn Slope=0.005
Boundary for River Rch & Prof#=Isaac Creek,Reach-1,5
Up Type=0
Dn Type=3
Dn Slope=0.005
Boundary for River Rch & Prof#=Isaac Creek,Reach-1,6
Up Type=0
Dn Type=3
Dn Slope=0.005
Boundary for River Rch & Prof#=Isaac Creek,Reach-1,7
Up Type=0
Dn Type=3
Dn Slope=0.005

--- Isaac Creek.g01 (geometry) ---

Geom Title=Existing Conditions
Program Version=4.10

River Reach=Isaac Creek     ,Reach-1
Reach XY= 30
        2245125.       13846775.      2246118.81     13845832.81
      2246798.52     13845602.01      2246982.86     13844918.83
      2247822.75     13844169.06      2247716.86     13843368.94
      2246775.38     13842659.84      2247324.18     13840085.34
      2246669.07     13839627.25      2245718.81     13839567.15
      2245091.68     13838441.64       2243622.7     13838019.17
      2242928.55     13837123.53      2242374.76     13835449.92
      2243015.76     13834668.45      2241668.83     13834167.14
      2241274.76     13833449.92      2241676.55     13833028.75
      2242767.02     13832872.08      2243123.95     13832185.43
      2242032.82     13831531.19       2241923.2     13830431.11
      2241595.09     13829994.78      2240871.68     13830066.96
      2240578.16     13829823.35      2240547.69     13829451.11
      2241419.17      13828977.3      2241667.25     13827824.91
      2240991.49     13827292.06        2240875.       13826925.

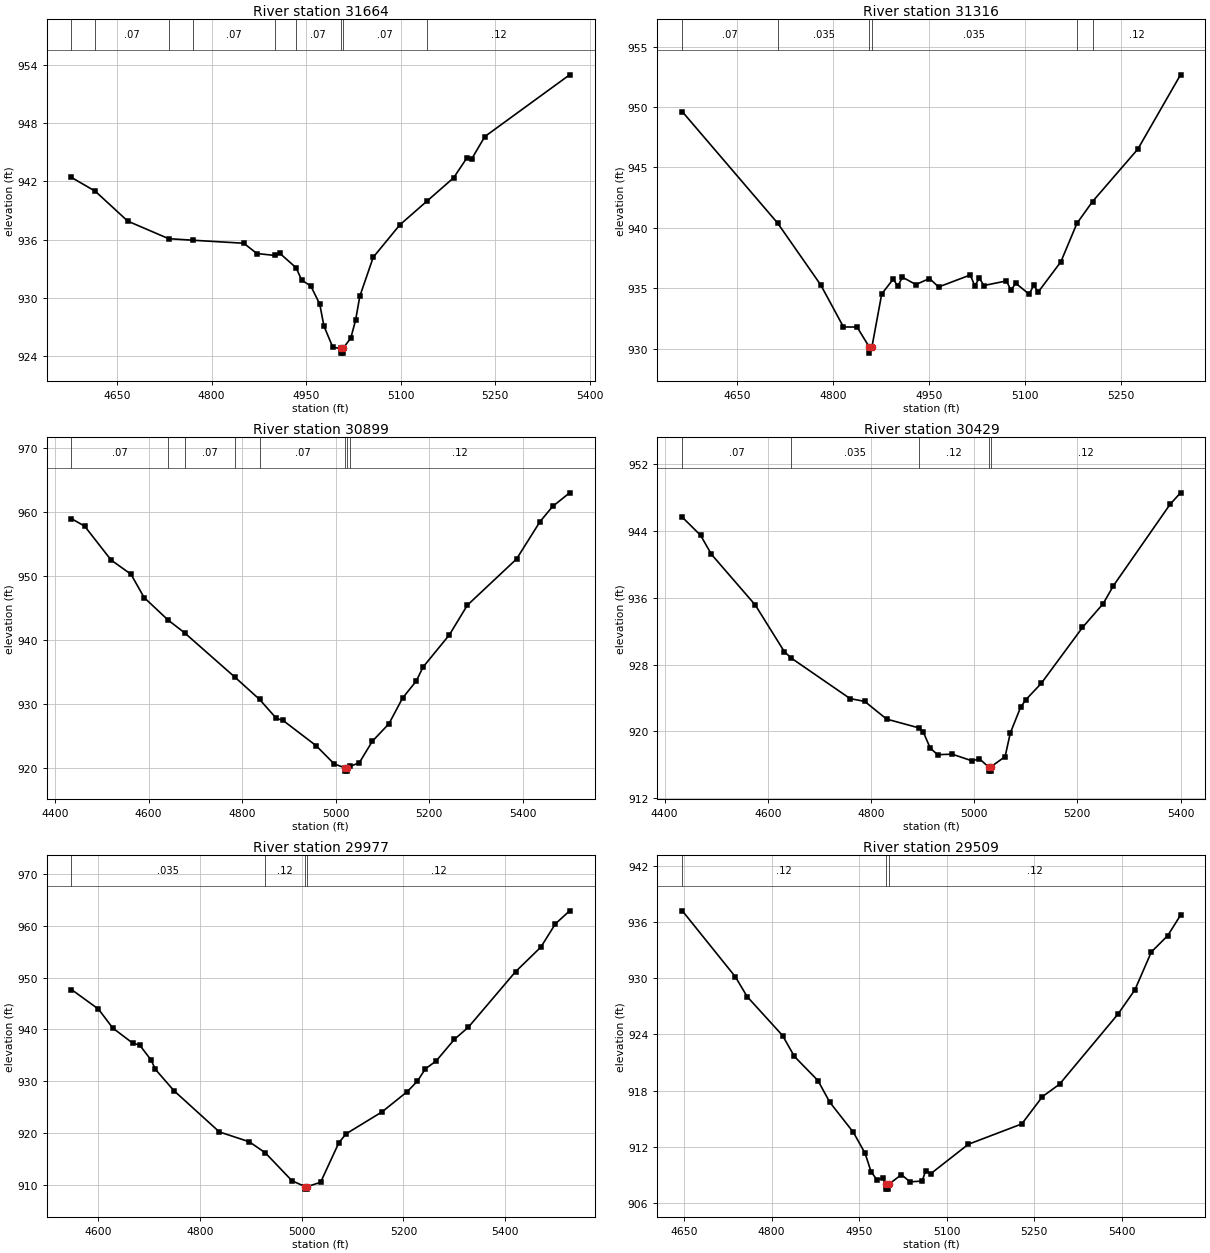
Type RM Length L Ch R = 1 ,31664   ,348,348,348
BEGIN DESCRIPTION:
A19455
END DESCRIPTION:
XS GIS Cut Line= 2
      2245466.14     13847029.69      2244869.96     13846510.29
#Sta/Elev= 30
  4577.6   942.4  4615.4  940.98  4666.9   937.9  4731.9  936.09  4770.4  935.93
  4851.1  935.62  4871.9  934.56  4901.1  934.36    4908   934.6  4934.1   933.1
  4943.2   931.8  4957.4  931.23  4971.7  929.35  4978.3   927.1  4992.5  924.89
  5004.7   924.8    5005   924.3  5008.5   924.3  5008.8   924.8    5021  925.86
  5028.6   927.7  5035.3  930.16  5056.6  934.18  5098.9  937.52  5142.4  939.99
  5184.3  942.37  5205.2  944.41  5212.8   944.3  5233.7  946.61  5368.3  952.97
#Mann= 9 ,-1 , 0
  4577.6     .12       0  4615.4     .07       0  4731.9     .12       0
  4770.4     .07       0  4901.1    .035       0  4934.1     .07       0
  5004.7     .05       0  5008.8     .07       0  5142.4     .12       0
Bank Sta=5004.7,5008.8
XS Rating Curve= 0 ,0
Exp/Cntr=0.3,0.1

Type RM Length L Ch R = 1 ,31316   ,417,417,417
BEGIN DESCRIPTION:
Isaac Creek 67.0
END DESCRIPTION:
XS GIS Cut Line= 3
      2245720.15     13846845.63      2245420.16     13846545.64
      2245170.16     13846295.64
#Sta/Elev= 30
  4564.6  949.61  4713.4   940.4  4780.8  935.28  4816.2  931.81  4837.4  931.81
  4856.5  930.15  4856.8  929.65  4860.6  930.15  4875.9  934.54    4894  935.78
    4901  935.17  4908.1  935.93  4929.3  935.32  4950.5  935.82  4964.7  935.12
  5014.2  936.11  5021.2  935.21  5028.3  935.85  5035.4  935.24  5070.7  935.62
  5077.8  934.83  5084.9  935.44  5106.1  934.52  5113.2  935.26  5120.2   934.7
  5155.6   937.2  5180.7  940.38    5205  942.18  5275.8  946.52  5342.4  952.66
#Mann= 6 ,-1 , 0
  4564.6     .07       0  4713.4    .035       0  4856.5    .035       0
  4860.6    .035       0  5180.7     .07       0    5205     .12       0
Bank Sta=4856.5,4860.6
XS Rating Curve= 0 ,0
Exp/Cntr=0.3,0.1

Type RM Length L Ch R = 1 ,30899   ,470,470,470
BEGIN DESCRIPTION:
Isaac Creek 66.0
END DESCRIPTION:
XS GIS Cut Line= 3
      2246124.98     13846674.98        2245725.       13846275.
      2245324.97     13845974.98
#Sta/Elev= 30
  4434.8  958.95  4463.1  957.78  4519.6   952.5  4562.1  950.29  4590.3  946.65
  4641.1  943.17    4677  941.14  4784.6  934.23  4837.1  930.78  4873.2  927.81
  4887.3   927.5    4958  923.57  4996.9  920.71  5020.3  920.09  5020.5  919.59
  5024.1  919.59  5024.4  920.09  5030.6  920.33  5050.5  920.89  5078.6  924.26
    5114  926.98  5143.2  930.99  5172.3  933.62  5186.9  935.81  5243.2  940.83
  5281.7  945.46  5386.9  952.66  5436.9  958.46    5464  960.85  5500.5  962.98
#Mann= 8 ,-1 , 0
  4434.8     .07       0  4641.1     .12       0    4677     .07       0
  4784.6     .12       0  4837.1     .07       0  5020.3     .05       0
  5024.4     .07       0  5030.6     .12       0
Bank Sta=5020.3,5024.4
XS Rating Curve= 0 ,0
Exp/Cntr=0.3,0.1

Type RM Length L Ch R = 1 ,30429   ,452,452,452
BEGIN DESCRIPTION:
Isaac Creek 65.0
END DESCRIPTION:
XS GIS Cut Line= 3
      2246424.99     13846324.99        2246025.       13845925.
        2246025.     13845524.97
#Sta/Elev= 30
  4434.3  945.65  4469.6  943.49  4490.8   941.2  4575.7  935.14  4632.3  929.53
  4645.8  928.77  4759.6  923.93  4787.8   923.6  4830.3  921.48  4893.9  920.41
    4901  919.98  4915.1  917.98  4929.3  917.22  4957.5  917.28  4996.4  916.47
    5010  916.74  5027.9  915.75  5028.2  915.25  5031.8  915.25  5032.1  915.75
    5060  916.99    5070   919.8    5090  922.89    5100  923.79    5130  925.75
    5210  932.45    5250  935.29    5270  937.45    5380  947.21    5400  948.57
#Mann= 5 ,-1 , 0
  4434.3     .07       0  4645.8    .035       0  4893.9     .12       0
  5027.9     .05       0  5032.1     .12       0
Bank Sta=5027.9,5032.1
XS Rating Curve= 0 ,0
Exp/Cntr=0.3,0.1

Type RM Length L Ch R = 1 ,29977   ,468,468,468
BEGIN DESCRIPTION:
Isaac Creek 64.0
END DESCRIPTION:
XS GIS Cut Line= 3
        2246625.       13846175.        2246425.       13845775.
      2246075.01     13845375.01
#Sta/Elev= 30
  4547.9  947.71    4601  943.92    4629  940.27  4668.1  937.36  4682.1  936.95
  4704.4  934.08  4712.8  932.28  4749.1  928.17  4838.6  920.18  4897.3  918.28
  4928.7  916.15  4981.1  910.75  5006.6  909.63  5006.9  909.13  5010.8  909.13
  5011.1  909.63  5037.3  910.44  5073.4  918.13  5087.6  919.83  5157.9  924.05
  5207.7  927.98  5227.6  930.01  5243.3  932.39  5264.2  933.88  5300.3  938.09
  5327.8  940.44  5420.3  951.15  5470.1  955.91  5498.6   960.4  5526.6  962.92
#Mann= 4 ,-1 , 0
  4547.9    .035       0  4928.7     .12       0  5006.6     .05       0
  5011.1     .12       0
Bank Sta=5006.6,5011.1
XS Rating Curve= 0 ,0
Exp/Cntr=0.3,0.1

Type RM Length L Ch R = 1 ,29509   ,435,435,435
BEGIN DESCRIPTION:
Isaac Creek 63.0
END DESCRIPTION:
XS GIS Cut Line= 3
        2246875.     13845925.03        2246825.       13845575.
      2246424.99     13845274.99
#Sta/Elev= 30
    4647  937.21  4737.9  930.16  4758.1  928.04  4818.8  923.88    4839  921.65
  4879.4  919.07  4899.6  916.76    4940  913.55  4960.2  911.29  4970.3  909.35
  4980.4  908.47  4990.5  908.66  4995.8  907.97  4996.1  907.47    5000  907.47
  5000.3  907.97  5022.5  909.02    5037  908.25  5057.9  908.33  5064.1  909.46
  5072.5  909.11    5137  912.26  5228.7  914.44  5264.1  917.36  5293.3  918.68
  5393.3  926.16  5422.5  928.77  5450.6  932.81  5478.7  934.56  5500.6  936.74
#Mann= 3 ,-1 , 0
    4647     .12       0  4995.8     .05       0  5000.3     .12       0
Bank Sta=4995.8,5000.3
XS Rating Curve= 0 ,0
Exp/Cntr=0.3,0.1

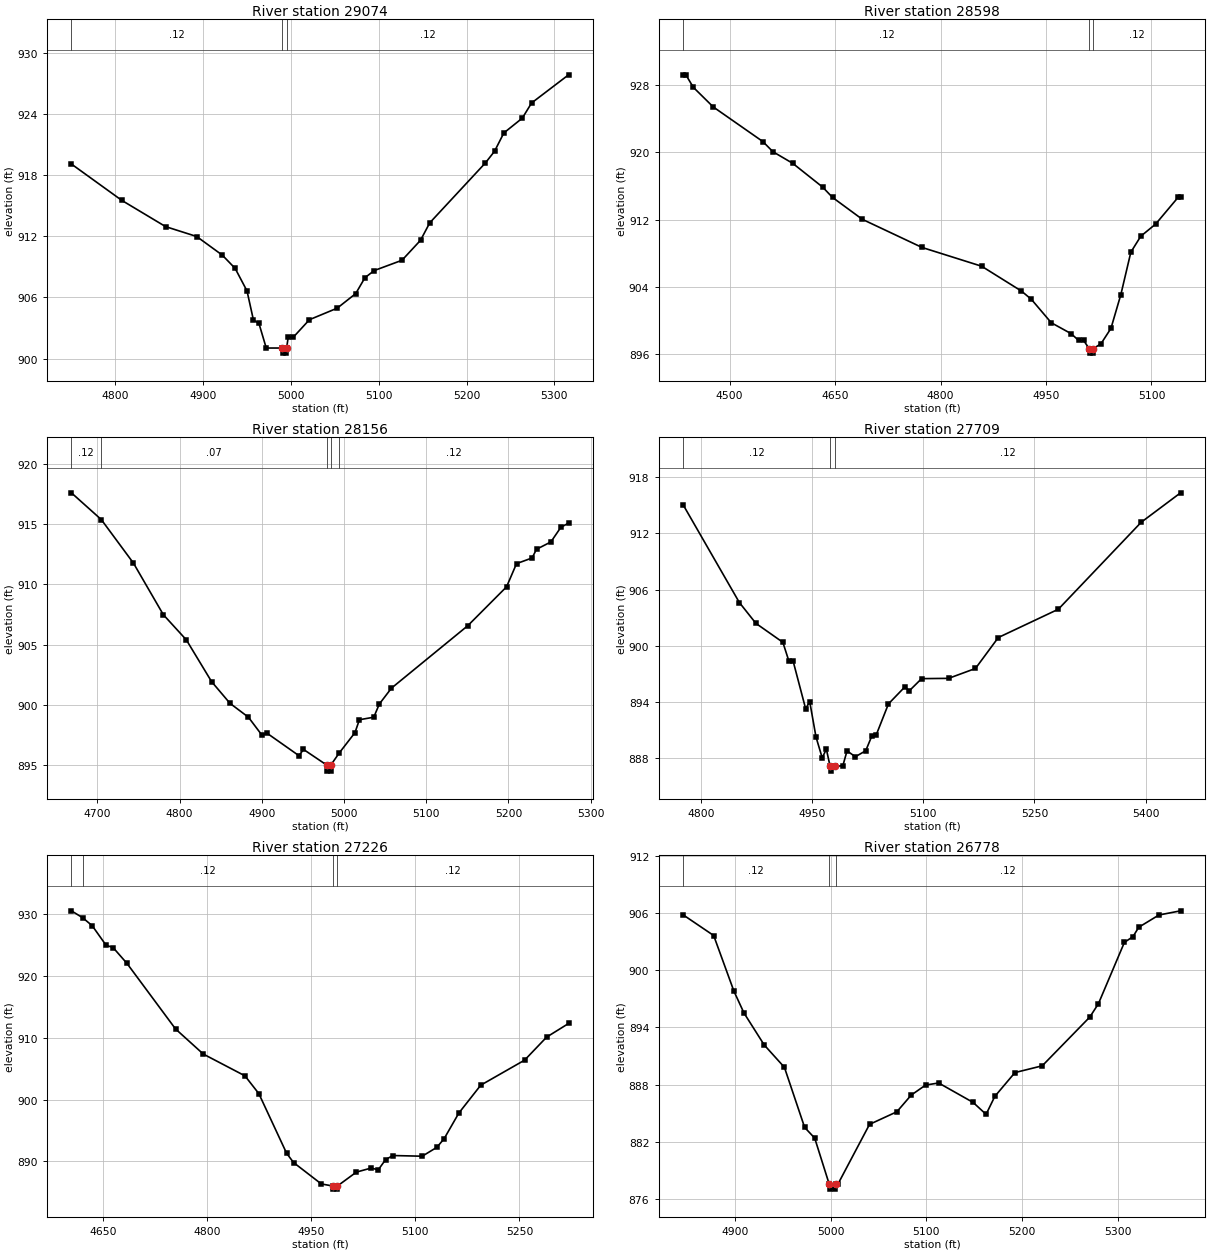
Type RM Length L Ch R = 1 ,29074   ,476,476,476
BEGIN DESCRIPTION:
Isaac Creek 62.0
END DESCRIPTION:
XS GIS Cut Line= 3
      2247125.02     13845325.01        2246925.       13845175.
      2246625.05     13845075.02
#Sta/Elev= 30
  4749.9  919.09  4807.2  915.53  4857.2  912.95  4892.6  911.98  4921.8  910.15
  4936.4  908.85  4949.9  906.64  4957.2  903.79  4963.5  903.45  4971.8  901.04
  4990.2  901.04  4990.6  900.54  4994.7  900.54    4995  901.04  4996.8   902.1
  5002.6   902.1    5021  903.82  5052.6  904.95  5073.7  906.38  5084.2  907.94
  5094.8  908.64  5126.4  909.65  5147.5  911.61    5158  913.32  5221.3  919.19
  5231.8  920.34  5242.4  922.14  5263.4  923.59    5274  925.08  5316.1  927.84
#Mann= 3 ,-1 , 0
  4749.9     .12       0  4990.2     .05       0    4995     .12       0
Bank Sta=4990.2,4995
XS Rating Curve= 0 ,0
Exp/Cntr=0.3,0.1

Type RM Length L Ch R = 1 ,28598   ,442,442,442
BEGIN DESCRIPTION:
Isaac Creek 61.0
END DESCRIPTION:
XS GIS Cut Line= 3
      2247524.98     13845174.98        2247125.       13844775.
      2247024.99     13844674.99
#Sta/Elev= 30
  4434.3  929.21  4437.8  929.21  4448.4  927.73  4476.7   925.4  4547.4  921.28
  4561.6  920.08  4589.8   918.7  4632.3  915.88  4646.4  914.65  4688.8  912.05
  4773.7  908.71  4858.5  906.48  4915.1  903.53  4929.2  902.55  4957.5  899.77
  4985.8  898.47  4996.4  897.67  5003.5  897.67  5011.7  896.66  5012.1  896.16
  5016.2  896.16  5016.5  896.66  5028.2  897.27  5042.4   899.1  5056.5  903.12
  5070.7  908.15  5084.8  910.04    5106  911.49  5137.8  914.65  5141.4  914.65
#Mann= 3 ,-1 , 0
  4434.3     .12       0  5011.7     .05       0  5016.5     .12       0
Bank Sta=5011.7,5016.5
XS Rating Curve= 0 ,0
Exp/Cntr=0.3,0.1

Type RM Length L Ch R = 1 ,28156   ,447,447,447
BEGIN DESCRIPTION:
Isaac Creek 60.0
END DESCRIPTION:
XS GIS Cut Line= 3
      2247625.02     13844825.04        2247475.       13844525.
      2247225.01       13844425.
#Sta/Elev= 30
  4668.5  917.59  4704.9  915.37    4744  911.76  4780.3  907.49  4808.3   905.4
    4839  901.94  4861.4  900.14  4883.8  898.99  4900.5  897.48  4906.1  897.68
  4945.3   895.8  4950.8  896.32  4979.1  895.02  4979.5  894.52  4983.7  894.52
    4984  895.02  4994.1  896.01  5013.4  897.71  5018.8  898.78  5036.3  898.99
    5043  900.08  5057.8   901.4  5150.7  906.58  5197.8   909.8  5209.9  911.72
  5228.8  912.19  5234.2  912.91  5251.7  913.52  5263.8  914.73  5273.2  915.08
#Mann= 5 ,-1 , 0
  4668.5     .12       0  4704.9     .07       0  4979.1     .05       0
    4984     .07       0  4994.1     .12       0
Bank Sta=4979.1,4984
XS Rating Curve= 0 ,0
Exp/Cntr=0.3,0.1

Type RM Length L Ch R = 1 ,27709   ,483,483,483
BEGIN DESCRIPTION:
Isaac Creek 59.0
END DESCRIPTION:
XS GIS Cut Line= 3
        2247975.       13844175.        2247775.       13844275.
      2247375.02     13844075.01
#Sta/Elev= 30
  4776.4  915.02  4851.9  904.61  4874.2  902.38  4910.6  900.35  4918.9   898.3
  4924.5  898.32  4941.3  893.25  4946.9  893.98  4955.3  890.22  4963.7  887.98
  4969.3  888.91  4974.4  887.06  4974.9  886.56  4980.8  887.06  4991.6  887.15
  4997.2  888.73  5008.4   888.1  5022.4  888.74  5030.8  890.35  5036.3  890.38
  5053.1  893.76  5075.5   895.6  5081.1  895.15  5097.8  896.46  5134.2  896.49
  5170.5  897.55  5201.3  900.86  5282.3  903.89  5394.1   913.2  5447.2  916.35
#Mann= 3 ,-1 , 0
  4776.4     .12       0  4974.4     .05       0  4980.8     .12       0
Bank Sta=4974.4,4980.8
XS Rating Curve= 0 ,0
Exp/Cntr=0.3,0.1

Type RM Length L Ch R = 1 ,27226   ,448,448,448
BEGIN DESCRIPTION:
Isaac Creek 58.0
END DESCRIPTION:
XS GIS Cut Line= 3
      2248174.96       13843825.        2247775.       13843825.
      2247474.99       13843925.
#Sta/Elev= 30
  4604.6   930.5    4621  929.37  4634.6  928.09  4654.6  924.93  4664.6  924.57
  4684.6  922.01  4754.6  911.41  4794.6  907.35  4854.6  903.83  4874.6  900.96
  4914.6  891.32  4924.6  889.82  4964.6  886.36  4981.3  886.02  4981.8  885.52
  4987.3  885.52  4987.8  886.02  5015.1  888.27  5036.2  888.92  5046.7  888.65
  5057.3   890.3  5067.8  890.95    5110  890.84  5131.1  892.28  5141.6  893.68
  5162.7  897.81  5194.3  902.32  5257.5  906.37  5289.2  910.09  5320.8  912.29
#Mann= 4 ,-1 , 0
  4604.6    .035       0    4621     .12       0  4981.3     .05       0
  4987.8     .12       0
Bank Sta=4981.3,4987.8
XS Rating Curve= 0 ,0
Exp/Cntr=0.3,0.1

Type RM Length L Ch R = 1 ,26778   ,425,425,425
BEGIN DESCRIPTION:
Isaac Creek 57.0
END DESCRIPTION:
XS GIS Cut Line= 3
      2247874.98     13843375.01        2247725.       13843425.
      2247424.96     13843625.03
#Sta/Elev= 30
  4846.5  905.77  4878.1  903.62  4899.2  897.79  4909.7   895.5  4930.8  892.15
  4951.9   889.8    4973   883.5  4983.5  882.38  4998.7  877.53  4999.2  877.03
  5004.7  877.03  5005.2  877.53  5007.6  877.53  5040.7  883.82  5069.2  885.14
  5084.2  886.89  5099.2  887.94  5112.8  888.16  5148.8  886.12  5162.3  884.87
  5171.4  886.75  5192.4  889.25  5220.9  889.96  5270.5  895.07  5279.5  896.47
  5306.6   902.9  5315.6  903.51  5321.6  904.49  5342.6  905.77  5365.2  906.21
#Mann= 3 ,-1 , 0
  4846.5     .12       0  4998.7     .05       0  5005.2     .12       0
Bank Sta=4998.7,5005.2
XS Rating Curve= 0 ,0
Exp/Cntr=0.3,0.1

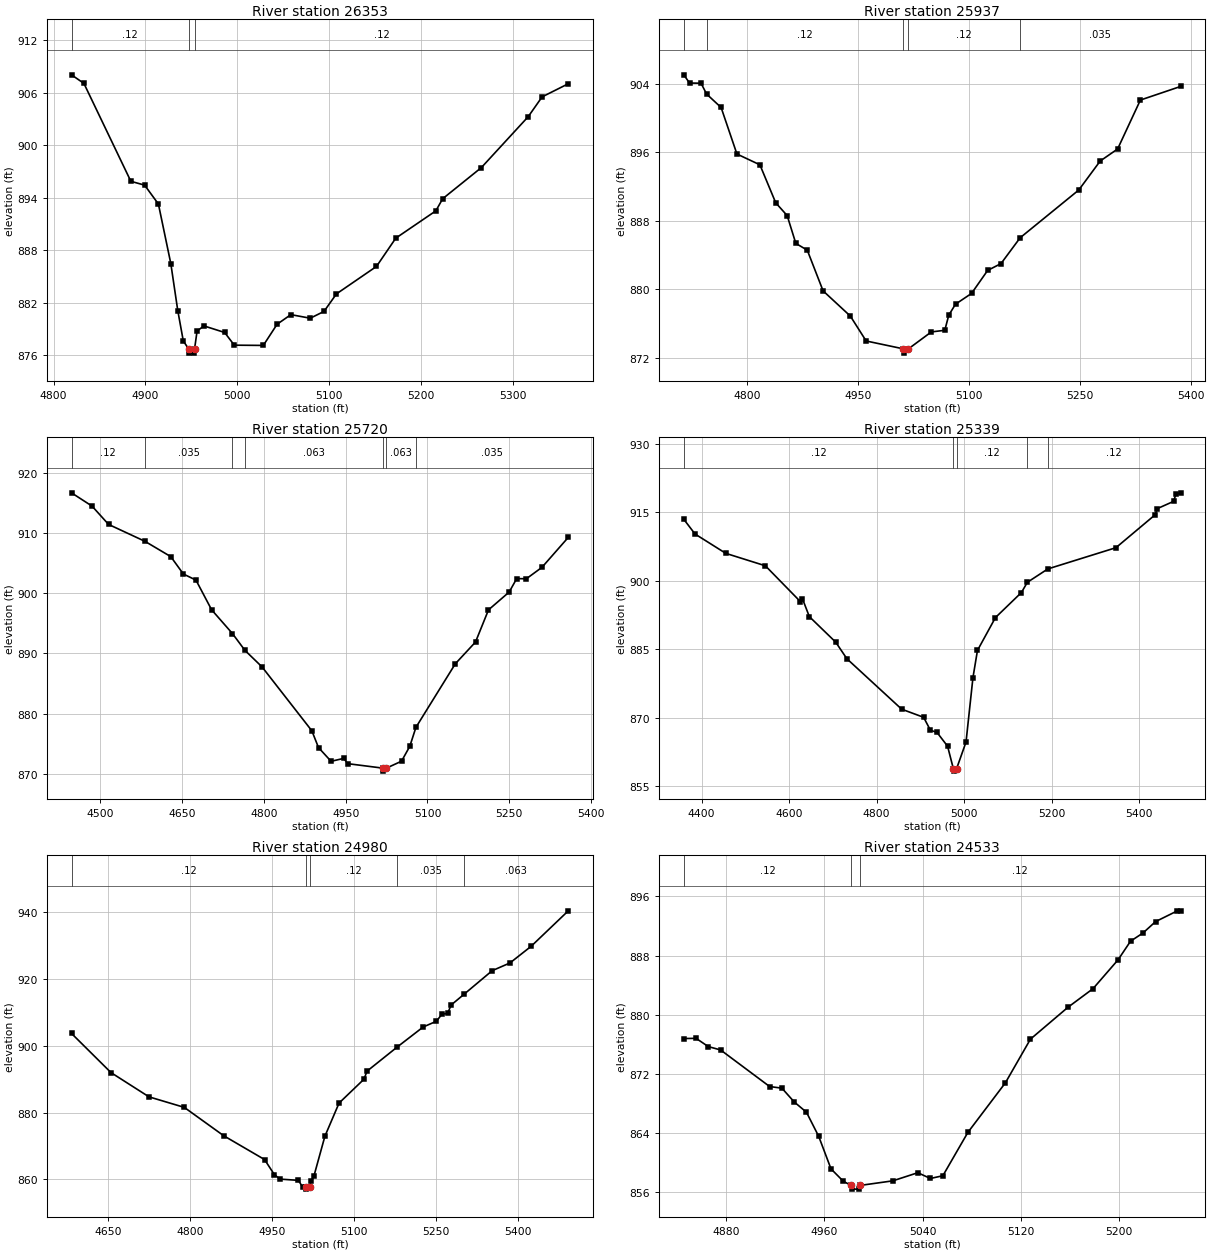
Type RM Length L Ch R = 1 ,26353   ,416,416,416
BEGIN DESCRIPTION:
Isaac Creek 56.0
END DESCRIPTION:
XS GIS Cut Line= 3
      2247574.98     13843075.01        2247425.       13843175.
      2247225.01     13843474.99
#Sta/Elev= 30
  4819.5  908.05    4833  907.07  4884.1  895.88  4899.1  895.44  4914.1  893.28
  4927.6  886.48  4935.2  881.09  4941.2  877.63  4946.9  876.74  4947.4  876.24
    4953  876.24  4953.5  876.74  4956.2  878.77  4963.7  879.35  4986.2   878.6
  4996.7  877.15  5028.3  877.12  5043.3  879.54  5058.3  880.64  5079.4  880.23
  5094.4  881.01  5107.9  883.01  5151.5  886.15  5172.5  889.38  5216.1   892.5
  5223.6  893.89  5265.7  897.45  5316.7  903.27  5331.8  905.53  5360.3  907.03
#Mann= 3 ,-1 , 0
  4819.5     .12       0  4946.9     .05       0  4953.5     .12       0
Bank Sta=4946.9,4953.5
XS Rating Curve= 0 ,0
Exp/Cntr=0.3,0.1

Type RM Length L Ch R = 1 ,25937   ,217,217,217
BEGIN DESCRIPTION:
Isaac Creek 55.0
END DESCRIPTION:
XS GIS Cut Line= 3
      2247324.98     13842825.01        2247075.       13842975.
      2246725.02     13843124.99
#Sta/Elev= 30
  4714.1  905.07  4721.9  904.11  4737.4  904.09    4745  902.82  4764.6  901.25
    4786  895.81  4817.1  894.55  4838.5  890.11    4854  888.61  4865.7  885.36
  4881.2  884.57  4902.6  879.81  4939.5  876.86  4960.9  873.95  5011.3  873.03
  5011.8  872.53  5018.1  873.03  5049.1  875.01  5067.3   875.2  5072.7  876.97
  5081.8  878.25  5103.5  879.51  5125.3   882.2  5143.4     883  5169.3  886.02
  5248.6   891.6  5277.6  894.99  5301.2   896.4    5332  902.12  5386.4  903.71
#Mann= 5 ,-1 , 0
  4714.1    .063       0    4745     .12       0  5011.3     .05       0
  5018.1     .12       0  5169.3    .035       0
Bank Sta=5011.3,5018.1
XS Rating Curve= 0 ,0
Exp/Cntr=0.3,0.1

Type RM Length L Ch R = 1 ,25720   ,381,381,381
BEGIN DESCRIPTION:
A19454
END DESCRIPTION:
XS GIS Cut Line= 2
      2247426.98     13842595.69      2246596.05     13842969.88
#Sta/Elev= 30
    4447  916.68  4484.7  914.47    4515  911.43  4581.8  908.62  4629.1  906.08
  4652.2  903.19  4675.3  902.18    4704  897.25  4742.2   893.3  4765.2   890.5
  4796.5  887.76  4887.9  877.14  4900.1  874.35  4923.2  872.07  4946.4  872.56
  4953.7  871.68  5017.9  870.94  5018.4  870.44  5024.7  870.94  5052.4  872.09
  5067.6  874.57  5078.8  877.71  5151.1  888.28  5188.1  891.89  5211.9  897.23
  5249.8  900.19  5263.7  902.43  5281.4   902.4    5310   904.3  5358.3  909.28
#Mann= 7 ,-1 , 0
    4447     .12       0  4581.8    .035       0  4742.2     .12       0
  4765.2    .063       0  5017.9    .063       0  5024.7    .063       0
  5078.8    .035       0
Bank Sta=5017.9,5024.7
XS Rating Curve= 0 ,0
Exp/Cntr=0.3,0.1

Type RM Length L Ch R = 1 ,25339   ,359,359,359
BEGIN DESCRIPTION:
Isaac Creek 54.0
END DESCRIPTION:
XS GIS Cut Line= 3
       2247410.5      13842463.6      2246849.16     13842518.63
      2246293.37     13842386.56
#Sta/Elev= 30
  4359.5  913.43  4385.1  910.21  4455.5  905.97  4545.9  903.25  4625.7  895.43
  4630.7  896.03  4646.4  892.12  4706.7  886.53  4732.2   882.9  4857.4  871.86
  4907.6  870.08  4923.1  867.25  4938.1  866.78  4962.3  863.76  4975.6   858.8
  4976.1   858.3  4982.8   858.8  5004.5  864.68  5020.3  878.76  5030.6  884.72
  5071.7  891.91  5131.1   897.4  5144.6  899.63  5191.4  902.56  5347.1  907.21
  5436.6  914.41  5441.8  915.77  5478.8  917.35    5484  918.88  5494.8  919.22
#Mann= 5 ,-1 , 0
  4359.5     .12       0  4975.6     .05       0  4982.8     .12       0
  5144.6    .063       0  5191.4     .12       0
Bank Sta=4975.6,4982.8
XS Rating Curve= 0 ,0
Exp/Cntr=0.3,0.1

Type RM Length L Ch R = 1 ,24980   ,447,447,447
BEGIN DESCRIPTION:
Isaac Creek 53.0
END DESCRIPTION:
XS GIS Cut Line= 3
        2247275.       13842275.        2246875.       13842175.
      2246388.46     13842078.68
#Sta/Elev= 30
    4583  903.67  4655.2  891.95  4724.7  884.69  4789.2  881.54  4861.3  873.05
    4936  865.92  4954.1  861.36  4964.4  860.07  4997.9  859.69  5005.5   857.7
  5012.1  857.57  5012.6  857.07  5019.3  857.57  5020.9  859.45    5026  860.85
  5046.3   872.9  5072.2  882.83  5117.6  889.95  5123.4  892.39  5178.4  899.59
  5225.9  905.59  5250.2  907.32  5260.4  909.46  5270.6  909.64  5277.1  912.18
  5300.5  915.37  5352.1  922.45  5384.7  924.77  5423.5  929.77  5491.3  940.37
#Mann= 5 ,-1 , 0
    4583     .12       0  5012.1     .05       0  5019.3     .12       0
  5178.4    .035       0  5300.5    .063       0
Bank Sta=5012.1,5019.3
XS Rating Curve= 0 ,0
Exp/Cntr=0.3,0.1

Type RM Length L Ch R = 1 ,24533   ,432,432,432
BEGIN DESCRIPTION:
Isaac Creek 52.0
END DESCRIPTION:
XS GIS Cut Line= 3
      2247175.02       13841775.        2247025.       13841775.
      2246774.97     13841724.99
#Sta/Elev= 30
  4845.3  876.79  4855.3  876.82  4865.3   875.7  4875.3  875.25  4915.3   870.3
  4925.3  870.08  4935.3  868.22  4945.3  866.83  4955.3  863.56  4965.3  859.17
  4975.3   857.5  4981.7  856.93  4982.2  856.43  4988.5  856.43    4989  856.93
  5015.7  857.55  5036.1  858.65  5046.3  857.87  5056.5  858.24  5076.9   864.1
  5107.5  870.81  5127.9  876.71  5158.5  881.02  5178.9  883.53  5199.3  887.43
  5209.5  889.95  5219.7  891.07  5229.9   892.6  5247.7  894.06  5250.3  894.06
#Mann= 3 ,-1 , 0
  4845.3     .12       0  4981.7     .05       0    4989     .12       0
Bank Sta=4981.7,4989
XS Rating Curve= 0 ,0
Exp/Cntr=0.3,0.1

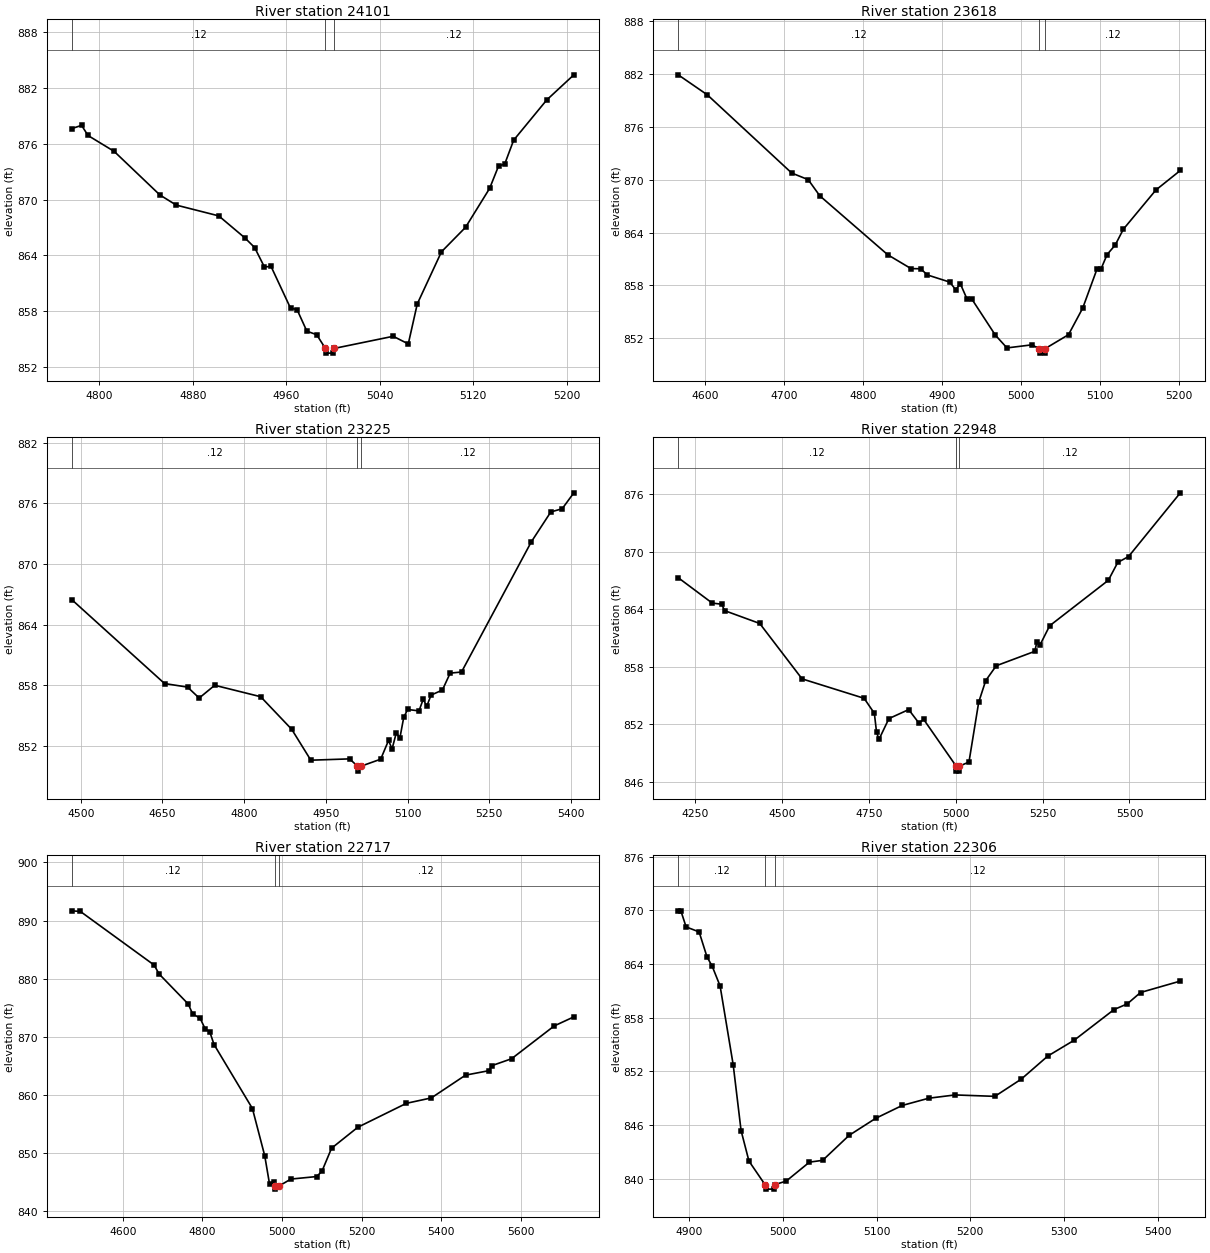
Type RM Length L Ch R = 1 ,24101   ,483,483,483
BEGIN DESCRIPTION:
Isaac Creek 51.0
END DESCRIPTION:
XS GIS Cut Line= 3
      2247324.98     13841474.99        2247125.       13841375.
      2246925.03     13841325.01
#Sta/Elev= 30
  4776.5  877.63  4784.9  877.98  4790.4  876.89  4812.8  875.18  4851.9   870.5
  4865.9  869.41  4902.3  868.25  4924.6  865.89    4933  864.85  4941.4  862.75
    4947  862.83  4963.7  858.34  4969.3  858.18  4977.7  855.86  4986.1  855.48
  4993.6     854  4994.1   853.5  5000.4   853.5  5000.9     854  5051.6  855.31
  5064.5  854.49  5072.2  858.79  5092.9  864.39  5113.5  867.02  5134.1   871.2
  5141.8  873.62    5147  873.81  5154.7  876.39    5183  880.71  5206.2  883.41
#Mann= 3 ,-1 , 0
  4776.5     .12       0  4993.6     .05       0  5000.9     .12       0
Bank Sta=4993.6,5000.9
XS Rating Curve= 0 ,0
Exp/Cntr=0.3,0.1

Type RM Length L Ch R = 1 ,23618   ,393,393,393
BEGIN DESCRIPTION:
Isaac Creek 50.0
END DESCRIPTION:
XS GIS Cut Line= 3
      2247575.02     13841175.01        2247225.       13840925.
      2247024.99       13840875.
#Sta/Elev= 30
  4565.6  881.87  4602.5   879.6  4709.4  870.74  4730.3  869.99    4745  868.16
  4831.1  861.48  4860.6  859.91  4872.8  859.89  4881.4  859.19  4909.7  858.38
  4917.1  857.53  4923.2  858.17  4931.8  856.42    4938  856.41  4967.5  852.37
  4982.2  850.92  5013.8  851.27    5023  850.83  5023.5  850.33  5029.9  850.33
  5030.4  850.83  5060.2  852.42  5078.2  855.43  5096.2  859.83  5101.4  859.87
  5109.1   861.5  5119.4  862.58  5129.7  864.37    5171  868.82  5201.9  871.03
#Mann= 3 ,-1 , 0
  4565.6     .12       0    5023     .05       0  5030.4     .12       0
Bank Sta=5023,5030.4
XS Rating Curve= 0 ,0
Exp/Cntr=0.3,0.1

Type RM Length L Ch R = 1 ,23225   ,277,277,277
BEGIN DESCRIPTION:
Isaac Creek 49.0
END DESCRIPTION:
XS GIS Cut Line= 3
      2247625.02     13840925.02        2247225.       13840575.
      2246925.04     13840824.97
#Sta/Elev= 30
  4483.4  866.48  4653.8  858.19    4696  857.84  4717.4  856.76  4745.9  858.02
  4830.3  856.89  4887.3  853.67  4922.4  850.62  4993.6  850.75  5007.9  850.04
  5008.4  849.54  5015.3  850.04  5050.7  850.72  5065.1  852.57  5071.6  851.73
  5079.4  853.33  5085.9   852.8    5093  854.85  5100.2  855.63    5121  855.49
  5128.8  856.64  5135.3  855.95  5143.2  857.05    5164  857.55  5178.3  859.22
  5199.1  859.33  5327.3  872.19  5363.1  875.14    5384  875.46  5405.4  877.03
#Mann= 3 ,-1 , 0
  4483.4     .12       0  5007.9     .05       0  5015.3     .12       0
Bank Sta=5007.9,5015.3
XS Rating Curve= 0 ,0
Exp/Cntr=0.3,0.1

Type RM Length L Ch R = 1 ,22948   ,231,231,231
BEGIN DESCRIPTION:
A19453
END DESCRIPTION:
XS GIS Cut Line= 4
      2247768.22      13840917.2      2247360.96     13840339.34
      2247146.34     13840306.32      2246700.56     13840575.98
#Sta/Elev= 30
  4201.2   867.3    4299  864.65  4326.2  864.53  4334.7  863.86  4435.7  862.52
  4557.6  856.73  4736.2   854.7  4765.7  853.13  4771.9  851.18  4778.9   850.4
  4807.6  852.58  4864.5  853.52  4893.8  852.12  4907.7  852.49  5001.5  847.59
    5002  847.09  5008.5  847.09    5009  847.59    5038  848.04    5066  854.29
  5086.2  856.55  5116.5   858.1  5227.6  859.61  5233.5  860.61  5243.1  860.32
  5270.3  862.28  5439.1  867.03  5466.3   868.9  5497.3  869.51  5646.3  876.17
#Mann= 3 ,-1 , 0
  4201.2     .12       0  5001.5     .05       0    5009     .12       0
Bank Sta=5001.5,5009
XS Rating Curve= 0 ,0
Exp/Cntr=0.3,0.1

Type RM Length L Ch R = 1 ,22717   ,411,411,411
BEGIN DESCRIPTION:
A19452
END DESCRIPTION:
XS GIS Cut Line= 3
      2247817.77     13839921.08      2247201.37     13840163.23
      2246711.61     13840509.91
#Sta/Elev= 30
  4471.4  891.67  4493.1  891.56  4678.5  882.34  4690.9  880.81  4764.2  875.64
  4775.2  873.95    4794   873.2  4807.4  871.28  4818.2  870.89  4829.1  868.67
  4925.6  857.66  4956.6  849.52  4968.6  844.68  4979.3  845.05  4981.3   844.3
  4981.8   843.8  4991.5   844.3  5022.3  845.53  5086.8  845.96  5100.2  846.85
  5124.6  850.84  5190.5  854.44  5312.7  858.56  5375.4  859.49  5461.5  863.41
  5520.6  864.18  5526.8  865.02  5577.2  866.23  5684.3  871.87  5733.7  873.43
#Mann= 3 ,-1 , 0
  4471.4     .12       0  4981.3     .05       0  4991.5     .12       0
Bank Sta=4981.3,4991.5
XS Rating Curve= 0 ,0
Exp/Cntr=0.3,0.1

Type RM Length L Ch R = 1 ,22306   ,465,465,465
BEGIN DESCRIPTION:
Isaac Creek 48.0
END DESCRIPTION:
XS GIS Cut Line= 3
      2247124.99     13839725.01        2247075.       13839825.
      2246774.97     13840125.03
#Sta/Elev= 30
  4888.2  869.96    4891  869.96  4896.6  868.16  4910.5   867.6  4918.9  864.81
  4924.5  863.75  4932.9  861.55  4946.9  852.72  4955.3  845.37  4963.7  841.96
  4980.9  839.32  4981.4  838.82  4990.7  838.82  4991.2  839.32  5003.5  839.72
  5028.3  841.84  5042.4  842.04  5070.7  844.84    5099  846.74  5127.3  848.18
  5155.6  848.99  5183.8  849.36  5226.3   849.2  5254.5  851.13  5282.8  853.71
  5311.1  855.49  5353.5  858.91  5367.7  859.55  5381.8  860.82  5424.3   862.1
#Mann= 3 ,-1 , 0
  4888.2     .12       0  4980.9     .05       0  4991.2     .12       0
Bank Sta=4980.9,4991.2
XS Rating Curve= 0 ,0
Exp/Cntr=0.3,0.1

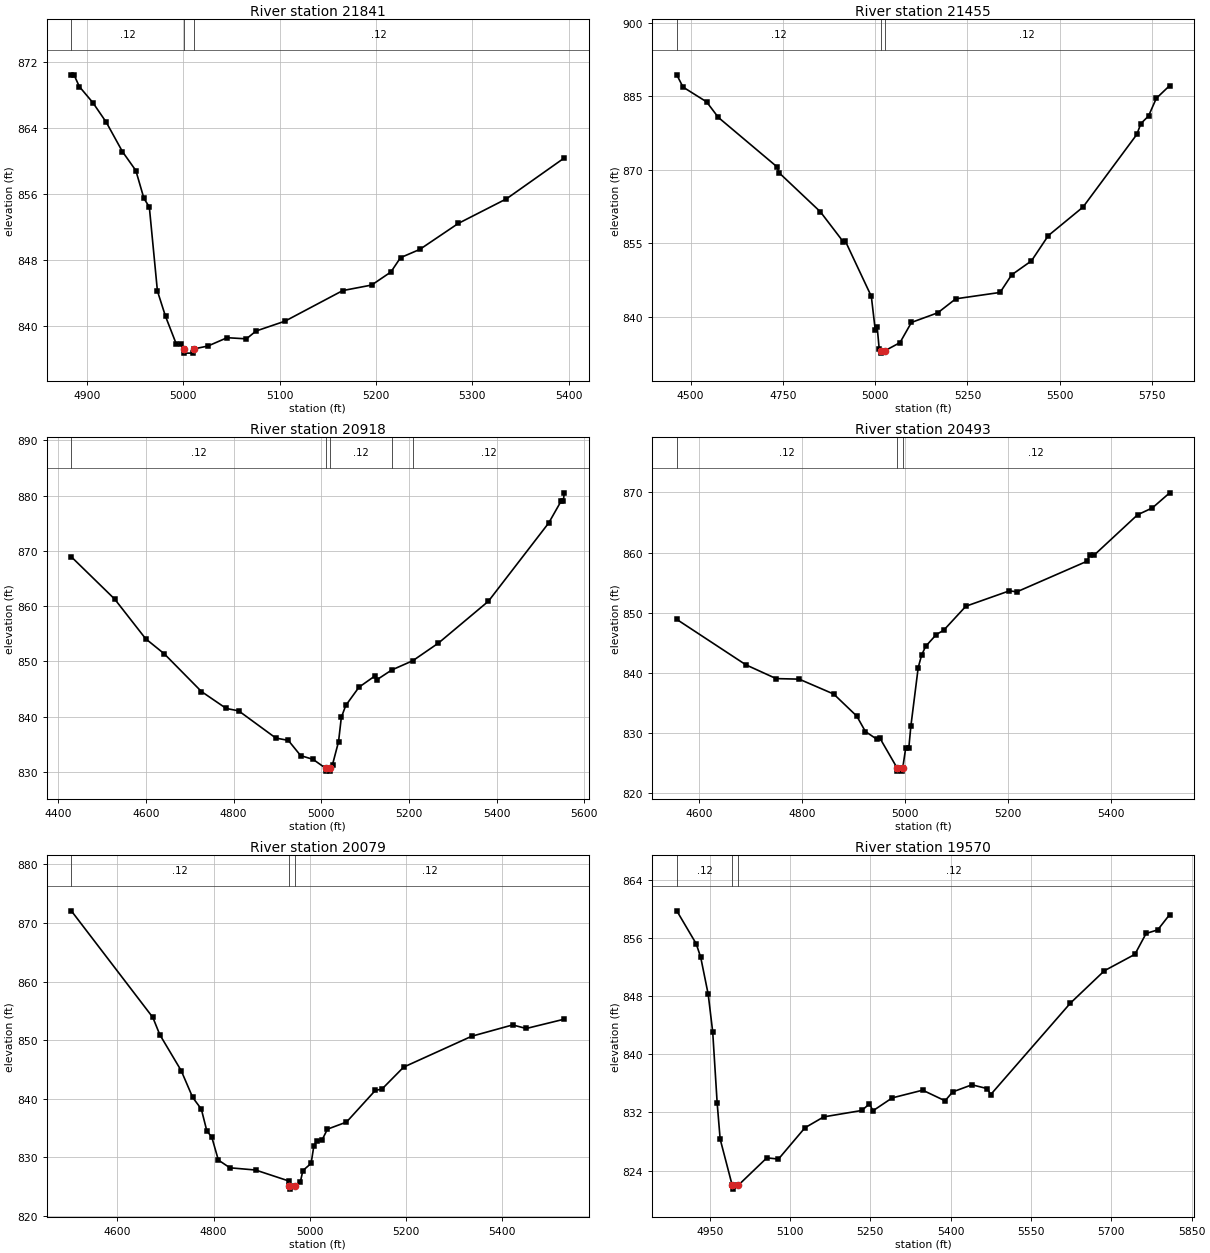
Type RM Length L Ch R = 1 ,21841   ,386,386,386
BEGIN DESCRIPTION:
Isaac Creek 47.0
END DESCRIPTION:
XS GIS Cut Line= 3
      2246724.98     13839525.04        2246675.       13839625.
        2246675.     13840025.04
#Sta/Elev= 30
  4883.7  870.39  4886.5  870.39    4892  868.97    4906  867.03    4920  864.64
  4936.8  861.08  4950.7  858.79  4959.1  855.41  4964.7  854.37  4973.1  844.19
  4981.5  841.12  4992.7  837.76    4998  837.76  5000.3  837.16  5000.8  836.66
  5010.1  836.66  5010.6  837.16  5025.5  837.52  5045.5  838.53  5065.5  838.39
  5075.5  839.34  5105.5  840.53  5165.5  844.24  5195.5  844.91  5215.5  846.49
  5225.5  848.23  5245.5  849.23  5285.5  852.38  5335.5  855.36  5395.5  860.31
#Mann= 3 ,-1 , 0
  4883.7     .12       0  5000.3     .05       0  5010.6     .12       0
Bank Sta=5000.3,5010.6
XS Rating Curve= 0 ,0
Exp/Cntr=0.3,0.1

Type RM Length L Ch R = 1 ,21455   ,537,537,537
BEGIN DESCRIPTION:
Isaac Creek 46.0
END DESCRIPTION:
XS GIS Cut Line= 3
      2246513.47     13839079.08      2246309.84     13839645.93
       2246073.2     13840339.35
#Sta/Elev= 30
  4462.8  889.39  4479.7  886.89  4543.5  883.88  4575.4   880.7  4734.3  870.62
  4739.7  869.42  4851.6  861.46  4913.4  855.37  4918.7  855.58  4989.7   844.2
  5000.3  837.35  5005.6  837.88    5011   833.5  5016.4  833.12  5016.9  832.62
  5026.8  833.12  5067.3  834.76  5098.3  838.88  5169.8  840.85  5218.4   843.7
  5338.4     845  5369.8  848.59  5423.4  851.44    5469  856.59    5563  862.41
  5708.7  877.23  5719.7  879.44  5740.4  880.99  5761.5  884.59  5797.8   887.2
#Mann= 3 ,-1 , 0
  4462.8     .12       0  5016.4     .05       0  5026.8     .12       0
Bank Sta=5016.4,5026.8
XS Rating Curve= 0 ,0
Exp/Cntr=0.3,0.1

Type RM Length L Ch R = 1 ,20918   ,425,425,425
BEGIN DESCRIPTION:
Isaac Creek 45.0
END DESCRIPTION:
XS GIS Cut Line= 3
      2246224.99     13839175.01        2245825.       13839575.
      2245759.53     13840130.08
#Sta/Elev= 30
  4429.9  868.91  4528.9  861.25  4599.6  854.07    4642  851.35  4726.9  844.52
  4783.4  841.46  4811.7  841.03  4896.6   836.1  4924.9  835.69  4953.1  832.93
  4981.4  832.25  5010.5  830.62    5011  830.12  5020.5  830.12    5021  830.62
  5025.8  831.29  5039.6  835.46  5045.9  839.83    5056     842  5086.2  845.31
  5122.5  847.34  5127.6  846.69  5160.8  848.42  5209.1  850.11  5267.4  853.29
  5381.5  860.87  5519.2  875.05  5547.4     879  5552.4  878.97  5554.5  880.49
#Mann= 5 ,-1 , 0
  4429.9     .12       0  5010.5     .05       0    5021     .12       0
  5160.8    .035       0  5209.1     .12       0
Bank Sta=5010.5,5021
XS Rating Curve= 0 ,0
Exp/Cntr=0.3,0.1

Type RM Length L Ch R = 1 ,20493   ,414,414,414
BEGIN DESCRIPTION:
Isaac Creek 44.0
END DESCRIPTION:
XS GIS Cut Line= 3
      2245925.03     13839124.98        2245525.       13839325.
      2245133.01     13839650.71
#Sta/Elev= 30
  4557.1   848.9  4691.3  841.35    4750  839.06  4794.7  838.97  4861.8  836.49
  4906.5  832.83  4923.3  830.26  4945.7  828.97  4951.2  829.19    4985  824.18
  4985.5  823.68  4995.2  823.68  4995.7  824.18  5001.6  827.57  5007.6  827.57
  5011.5  831.14  5025.8   840.9  5032.3  842.94  5040.2  844.42    5061  846.39
  5075.3   847.1  5118.3  851.09  5202.9  853.65  5217.2  853.48  5352.7  858.54
  5359.2  859.54    5367  859.56  5451.6  866.29  5480.3  867.43    5514  869.94
#Mann= 3 ,-1 , 0
  4557.1     .12       0    4985     .05       0  4995.7     .12       0
Bank Sta=4985,4995.7
XS Rating Curve= 0 ,0
Exp/Cntr=0.3,0.1

Type RM Length L Ch R = 1 ,20079   ,509,509,509
BEGIN DESCRIPTION:
Isaac Creek 43.0
END DESCRIPTION:
XS GIS Cut Line= 3
      2245525.02     13838524.96      2245363.28     13838919.49
      2245104.64     13839458.78
#Sta/Elev= 30
  4504.4  872.08  4673.9  853.88  4688.2  850.96  4732.7  844.82  4756.7  840.23
  4774.6  838.25  4786.1  834.51  4796.3  833.48    4810  829.55    4834  828.23
  4887.4  827.85  4957.5  825.95  4957.7  825.09  4958.2  824.59  4968.5  825.09
  4980.2  825.74  4985.7  827.76  5002.8  828.98  5008.4  831.91  5014.5  832.87
  5025.5  832.97  5036.7  834.82  5076.3  836.03  5136.5  841.46  5149.8  841.64
  5195.1  845.41  5336.6  850.68  5421.7  852.61  5449.9     852  5528.9  853.59
#Mann= 3 ,-1 , 0
  4504.4     .12       0  4957.7     .05       0  4968.5     .12       0
Bank Sta=4957.7,4968.5
XS Rating Curve= 0 ,0
Exp/Cntr=0.3,0.1

Type RM Length L Ch R = 1 ,19570   ,444,444,444
BEGIN DESCRIPTION:
Isaac Creek 42.0
END DESCRIPTION:
XS GIS Cut Line= 3
      2245224.99     13838425.02        2245175.       13838525.
      2244636.82     13839128.65
#Sta/Elev= 30
  4888.5  859.71  4924.8  855.18  4933.2  853.32  4947.2  848.23  4955.6  843.07
  4963.9  833.32  4969.5  828.34  4992.1  821.96  4992.6  821.46  5002.9  821.96
  5056.7  825.76  5078.4  825.59  5127.8  829.89  5162.9  831.39    5234  832.27
  5248.2  833.17  5254.9  832.23  5290.8     834  5347.7  835.06  5389.5   833.6
  5403.7  834.82  5439.6   835.8  5468.1  835.28  5474.8  834.46  5623.6  847.03
  5687.1  851.48    5744  853.73  5764.9   856.6  5786.6  857.09    5809   859.2
#Mann= 3 ,-1 , 0
  4888.5     .12       0  4992.1     .05       0  5002.9     .12       0
Bank Sta=4992.1,5002.9
XS Rating Curve= 0 ,0
Exp/Cntr=0.3,0.1