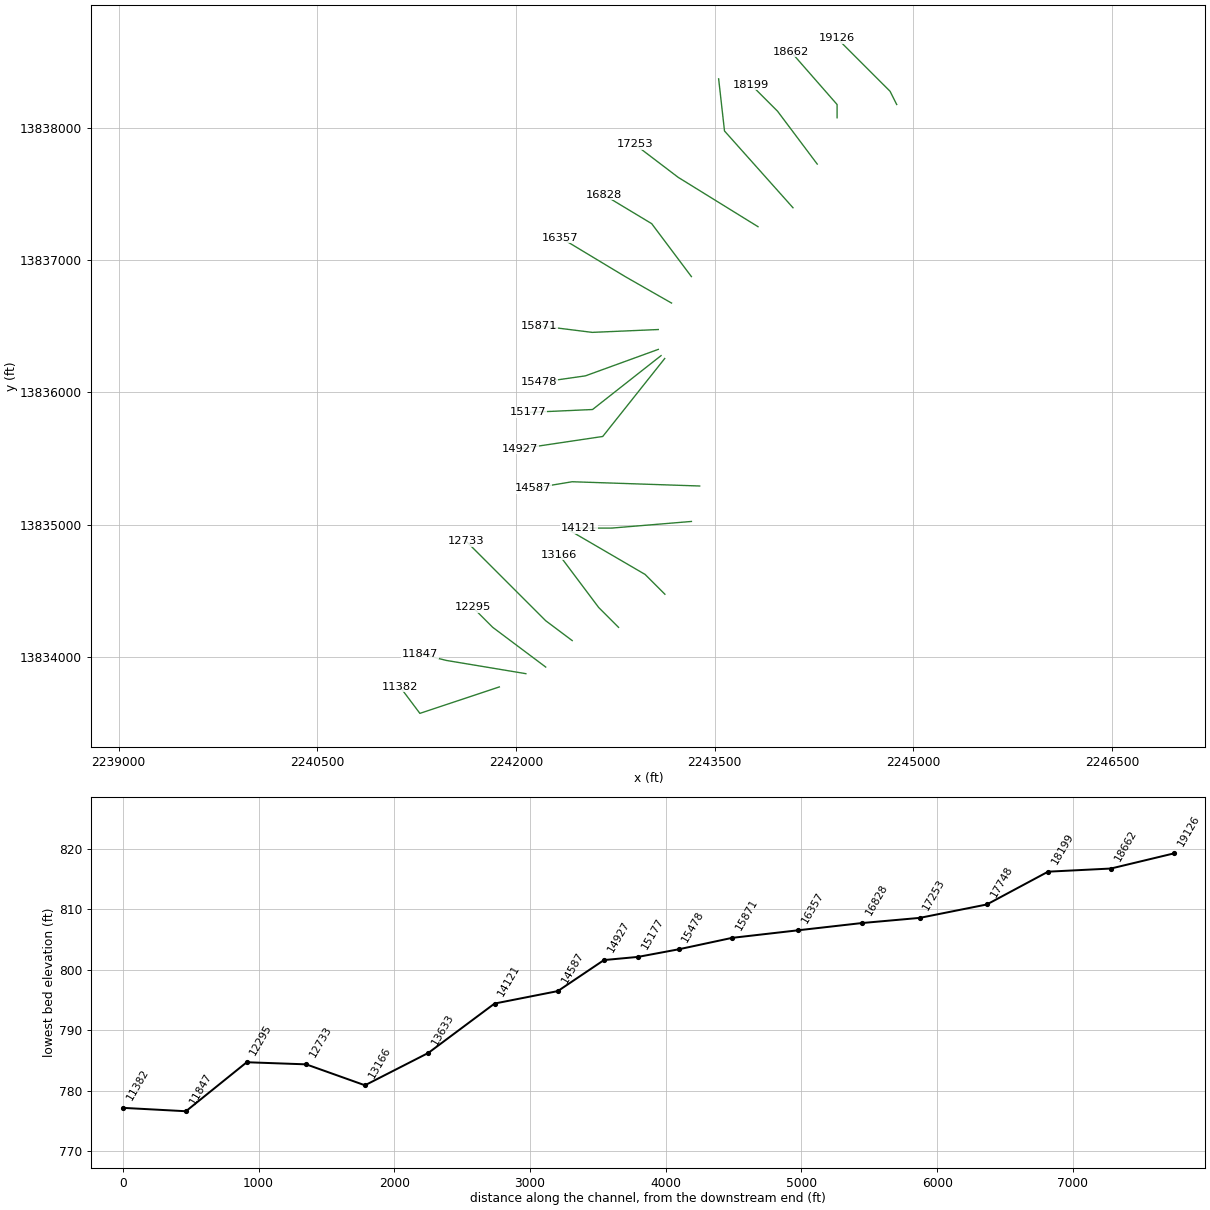
HEC-RAS study Isaac Creek.prj: Isaac Creek Base Level Engineering

--- Isaac Creek.g01 (geometry) --- (continued)

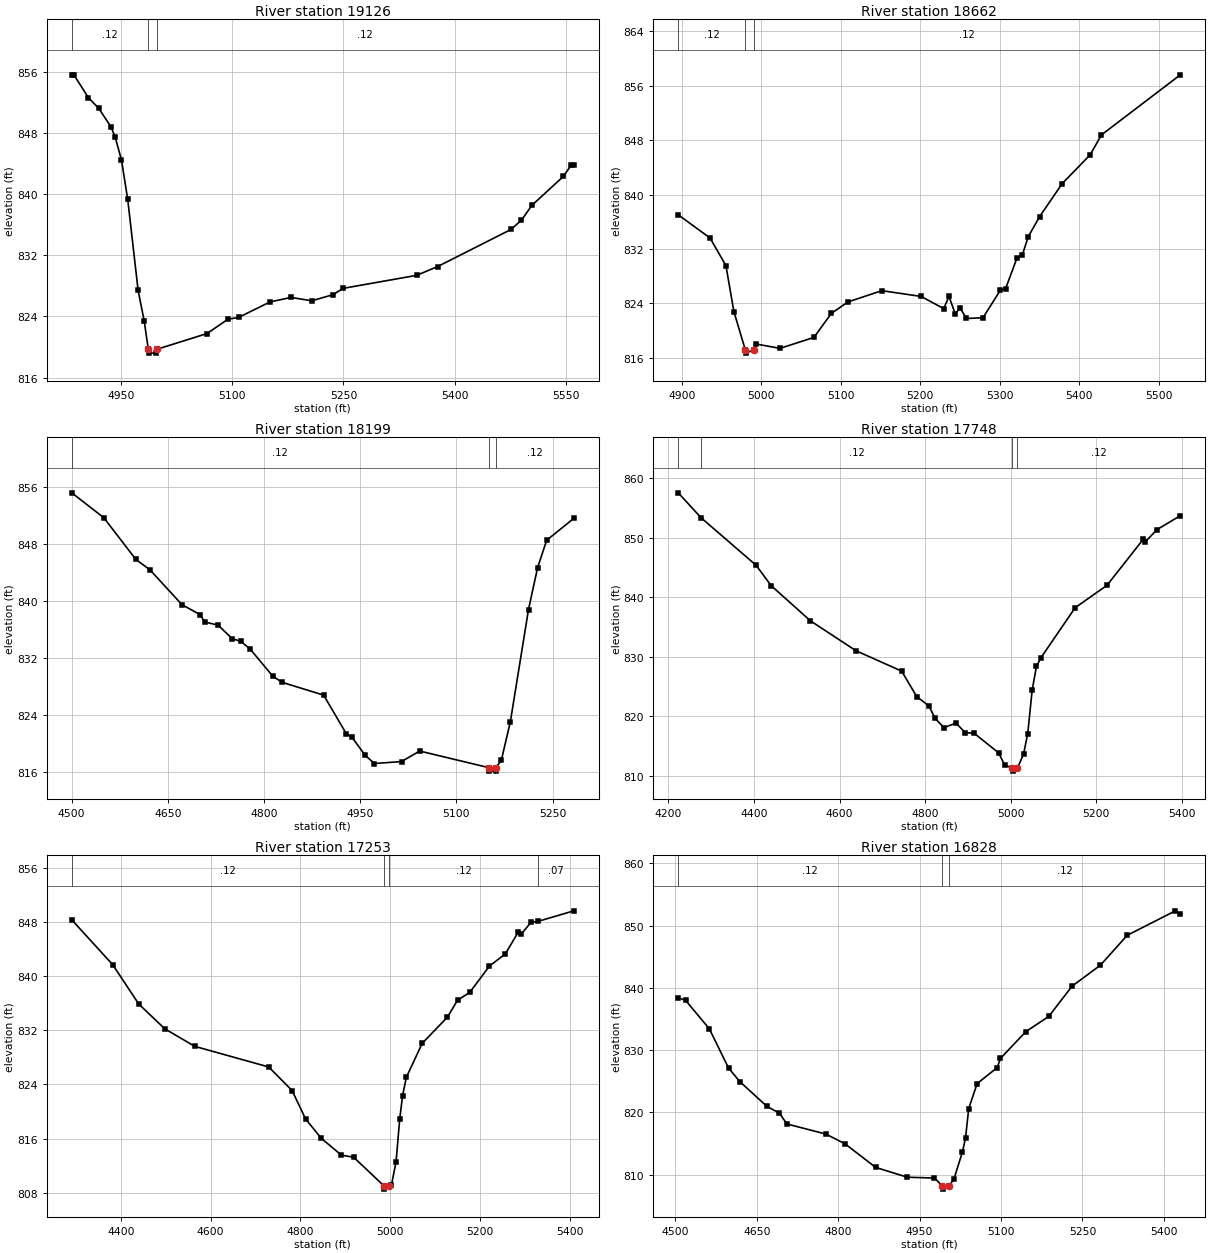
Type RM Length L Ch R = 1 ,19126   ,464,464,464
BEGIN DESCRIPTION:
Isaac Creek 41.0
END DESCRIPTION:
XS GIS Cut Line= 3
      2244875.01     13838174.99        2244825.       13838275.
        2244425.       13838675.
#Sta/Elev= 30
  4883.4  855.62  4886.2  855.62  4905.8  852.64  4919.7  851.24  4936.5  848.79
  4942.1  847.42  4950.5  844.46  4958.9  839.32  4972.9  827.43  4981.2  823.37
  4986.7   819.7  4987.2   819.2  4997.6   819.2  4998.1   819.7  5065.9  821.76
  5094.2  823.64  5108.4  823.87  5150.8  825.89  5179.1  826.49  5207.3  826.05
  5235.6  826.84  5249.8  827.68  5348.8  829.38  5377.1  830.53    5476  835.38
  5490.2   836.6  5504.3  838.54  5546.8  842.33  5557.4  843.81  5560.9  843.81
#Mann= 3 ,-1 , 0
  4883.4     .12       0  4986.7     .05       0  4998.1     .12       0
Bank Sta=4986.7,4998.1
XS Rating Curve= 0 ,0
Exp/Cntr=0.3,0.1

Type RM Length L Ch R = 1 ,18662   ,463,463,463
BEGIN DESCRIPTION:
Isaac Creek 40.0
END DESCRIPTION:
XS GIS Cut Line= 3
        2244425.     13838075.03        2244425.       13838175.
      2244074.98     13838575.02
#Sta/Elev= 30
  4895.6  837.03  4935.6  833.62  4955.6  829.56  4965.6  822.81  4979.9   817.2
  4980.4   816.7  4991.3   817.2  4993.1  818.05  5023.6   817.4  5066.3  819.01
  5088.1  822.53    5109  824.22  5151.7  825.88  5201.1  825.03  5229.5  823.25
  5236.2  825.03  5243.8  822.52  5250.4  823.31    5258  821.79  5278.9   821.9
  5300.7  825.93  5307.4  826.19  5321.6  830.66  5328.2  831.06  5335.8   833.8
  5350.1  836.76  5378.5  841.61  5413.7  845.84  5427.9  848.77  5527.1   857.6
#Mann= 3 ,-1 , 0
  4895.6     .12       0  4979.9     .05       0  4991.3     .12       0
Bank Sta=4979.9,4991.3
XS Rating Curve= 0 ,0
Exp/Cntr=0.3,0.1

Type RM Length L Ch R = 1 ,18199   ,451,451,451
BEGIN DESCRIPTION:
Isaac Creek 39.0
END DESCRIPTION:
XS GIS Cut Line= 3
        2244275.     13837725.01        2243975.       13838125.
      2243775.03     13838324.97
#Sta/Elev= 30
  4500.4  855.25  4550.4  851.75  4600.4  845.89  4622.3  844.44  4672.3  839.54
  4700.4  838.16  4707.7  837.12  4728.5  836.68  4750.4  834.78  4763.9   834.4
  4778.5  833.32  4813.9   829.5  4828.5  828.64  4893.1  826.85  4928.5  821.42
  4936.9  820.99  4957.7  818.41  4972.3  817.25  5014.5  817.52  5042.8     819
  5150.2  816.68  5150.7  816.18  5161.2  816.18  5161.7  816.68  5170.1  817.68
  5184.2  823.11  5212.5  838.87  5226.7  844.75  5240.8  848.59  5283.2  851.67
#Mann= 3 ,-1 , 0
  4500.4     .12       0  5150.2     .05       0  5161.7     .12       0
Bank Sta=5150.2,5161.7
XS Rating Curve= 0 ,0
Exp/Cntr=0.3,0.1

Type RM Length L Ch R = 1 ,17748   ,495,495,495
BEGIN DESCRIPTION:
Isaac Creek 38.0
END DESCRIPTION:
XS GIS Cut Line= 3
        2244092.     13837395.11        2243575.       13837975.
      2243530.69     13838369.12
#Sta/Elev= 30
  4222.8  857.58  4276.8  853.35  4404.8  845.39  4439.9  841.97  4531.9  836.04
  4638.1  831.02  4745.1  827.58  4780.2   823.3  4808.6  821.74  4822.9  819.66
  4843.8  818.08  4872.2  818.84  4893.1  817.25  4914.8  817.11  4971.7  813.83
  4985.9  811.76    5004  811.26  5004.5  810.76  5015.5  811.26  5029.9  813.61
  5039.7  817.09    5050  824.37  5060.1  828.37  5070.1  829.79  5150.6  838.26
  5224.8  842.01  5309.8  849.78  5314.8  849.37  5341.8  851.39  5396.3  853.74
#Mann= 4 ,-1 , 0
  4222.8     .07       0  4276.8     .12       0    5004     .05       0
  5015.5     .12       0
Bank Sta=5004,5015.5
XS Rating Curve= 0 ,0
Exp/Cntr=0.3,0.1

Type RM Length L Ch R = 1 ,17253   ,425,425,425
BEGIN DESCRIPTION:
Isaac Creek 37.0
END DESCRIPTION:
XS GIS Cut Line= 3
      2243827.87       13837252.        2243225.       13837625.
      2242898.94     13837873.01
#Sta/Elev= 30
  4290.8  848.31  4382.2  841.67  4440.1  835.87    4498  832.22  4564.6  829.63
  4729.6  826.58  4781.7   823.1  4811.6  818.92  4846.9  816.03  4891.6  813.56
  4918.8  813.25  4986.1  809.04  4986.6  808.54    4998  809.04  5002.9  809.09
  5013.3  812.59  5021.5  818.93  5027.8  822.33  5036.1  825.03  5071.5  830.07
  5127.6  833.93  5150.4  836.45  5177.5  837.59  5221.2  841.47  5256.5  843.26
  5285.6   846.5  5291.9  846.17  5313.8  847.93  5330.4   848.1  5409.4  849.64
#Mann= 4 ,-1 , 0
  4290.8     .12       0  4986.1     .05       0    4998     .12       0
  5330.4     .07       0
Bank Sta=4986.1,4998
XS Rating Curve= 0 ,0
Exp/Cntr=0.3,0.1

Type RM Length L Ch R = 1 ,16828   ,471,471,471
BEGIN DESCRIPTION:
Isaac Creek 36.0
END DESCRIPTION:
XS GIS Cut Line= 3
        2243325.     13836875.01        2243025.       13837275.
      2242661.19     13837494.13
#Sta/Elev= 30
  4505.5  838.41    4519  837.99  4562.8  833.42  4598.2  827.12    4619  824.94
    4669  820.96    4692  819.88  4705.5  818.15  4777.4  816.53  4812.8  814.96
    4869  811.18  4927.4   809.6  4977.4  809.47  4992.2  808.19  4992.7  807.69
  5004.2  808.19  5013.3   809.3  5028.8  813.64  5034.6   815.9  5040.5  820.62
    5056  824.63  5092.9  827.19  5098.9  828.66  5145.3  832.94    5188  835.42
  5230.8  840.26  5283.2  843.65  5332.4  848.43  5421.1  852.36  5430.2  851.91
#Mann= 3 ,-1 , 0
  4505.5     .12       0  4992.2     .05       0  5004.2     .12       0
Bank Sta=4992.2,5004.2
XS Rating Curve= 0 ,0
Exp/Cntr=0.3,0.1

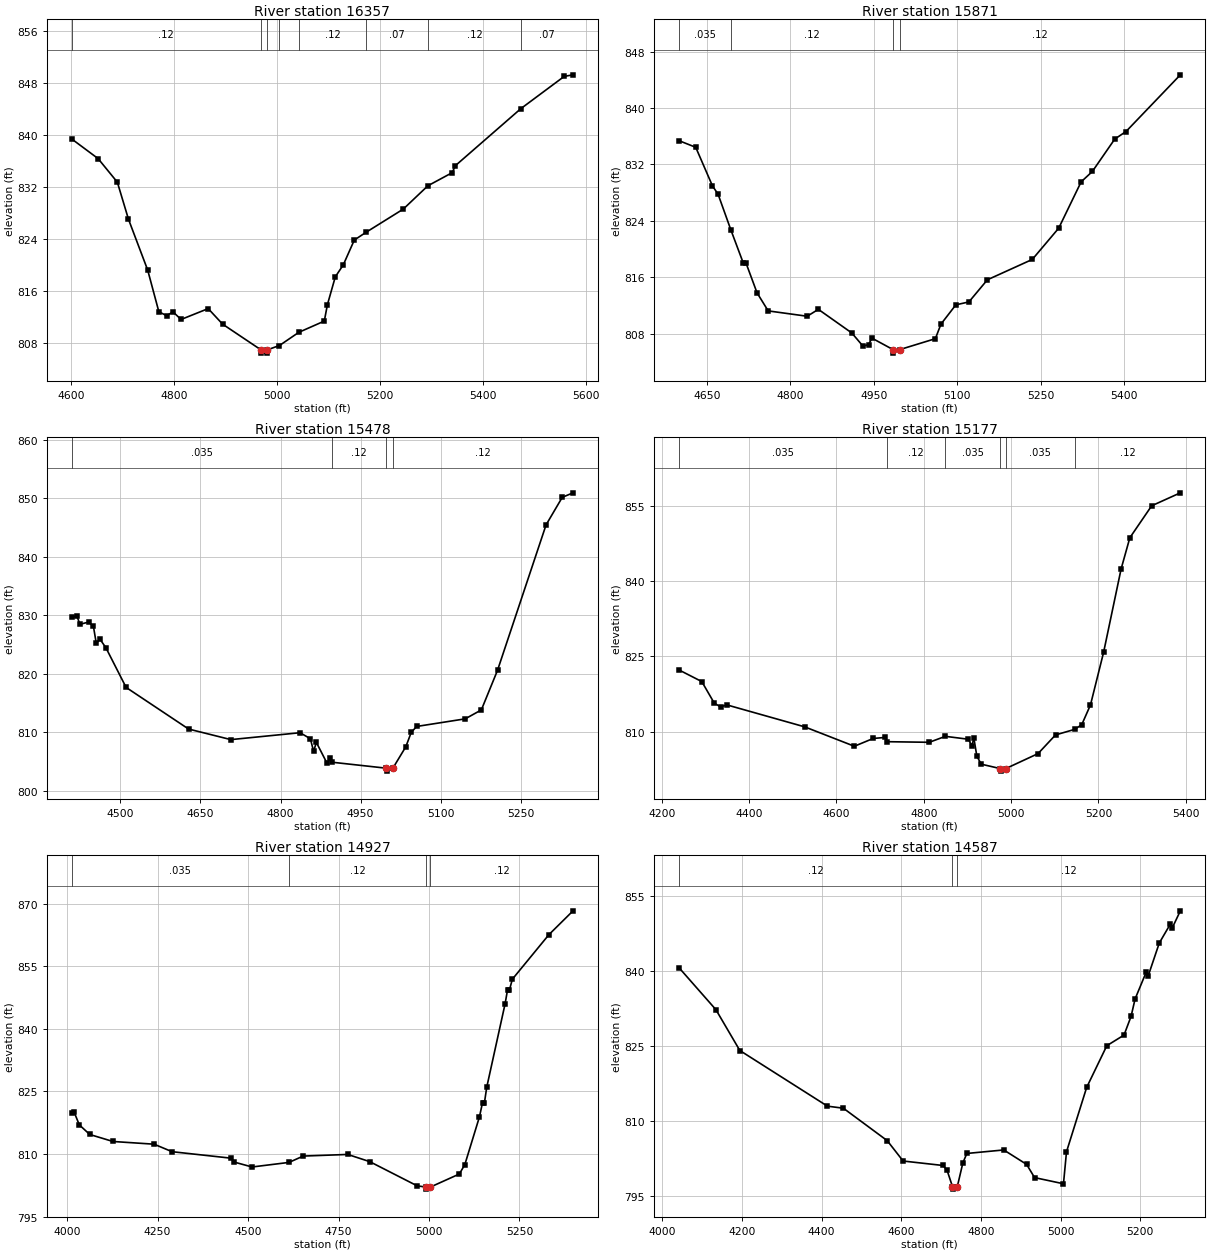
Type RM Length L Ch R = 1 ,16357   ,486,486,486
BEGIN DESCRIPTION:
Isaac Creek 35.0
END DESCRIPTION:
XS GIS Cut Line= 3
      2243175.04     13836674.98        2242825.       13836875.
      2242336.44     13837169.47
#Sta/Elev= 30
  4601.2  839.44  4652.4  836.42  4689.8  832.79  4711.4  827.09  4748.8  819.25
  4770.4  812.86  4785.5  812.25  4797.8  812.84  4813.6  811.67  4866.2  813.34
  4894.2  810.95  4968.8  806.99  4969.3  806.49  4980.3  806.49  4980.8  806.99
  5004.6  807.66  5042.2  809.69  5091.7  811.42  5097.8  813.96  5113.1  818.23
  5128.6  820.07    5150  823.89    5173  825.09  5245.1  828.65  5292.9  832.24
  5340.2  834.26  5346.1  835.32  5473.5  844.11  5557.7  849.07  5574.8  849.31
#Mann= 8 ,-1 , 0
  4601.2     .12       0  4968.8     .05       0  4980.8     .12       0
  5004.6     .07       0  5042.2     .12       0    5173     .07       0
  5292.9     .12       0  5473.5     .07       0
Bank Sta=4968.8,4980.8
XS Rating Curve= 0 ,0
Exp/Cntr=0.3,0.1

Type RM Length L Ch R = 1 ,15871   ,393,393,393
BEGIN DESCRIPTION:
Isaac Creek 34.0
END DESCRIPTION:
XS GIS Cut Line= 3
      2243074.99       13836475.      2242576.41     13836453.46
      2242178.16     13836503.24
#Sta/Elev= 30
  4600.1  835.37  4630.1  834.43  4660.1  828.96  4670.2  827.78  4693.3  822.69
  4715.6  817.99  4720.6  817.97  4740.2  813.79  4760.2  811.23  4830.3  810.47
  4850.3  811.45  4910.4   808.1  4930.4  806.24  4940.4  806.44  4946.5  807.37
  4984.5  805.74    4985  805.24  4996.5  805.74  5060.5  807.29  5070.5  809.35
  5097.3  812.09  5120.7   812.5  5153.9  815.64  5234.6  818.53    5282  822.96
  5322.3  829.53  5342.4     831  5382.7   835.6  5402.9  836.67  5500.5  844.71
#Mann= 4 ,-1 , 0
  4600.1    .035       0  4693.3     .12       0  4984.5     .05       0
  4996.5     .12       0
Bank Sta=4984.5,4996.5
XS Rating Curve= 0 ,0
Exp/Cntr=0.3,0.1

Type RM Length L Ch R = 1 ,15478   ,301,301,301
BEGIN DESCRIPTION:
Isaac Creek 33.0
END DESCRIPTION:
XS GIS Cut Line= 3
      2243075.02     13836325.01        2242525.       13836125.
      2242175.01       13836075.
#Sta/Elev= 30
    4409  829.69    4419  829.82  4424.3  828.46  4440.9  828.85  4449.6  828.11
  4454.9  825.25  4462.2  825.87  4472.9  824.47  4510.8  817.67  4627.8  810.55
    4707  808.74  4836.6  809.92  4855.9  808.89  4861.9  806.76  4867.2  808.25
  4887.2  804.68  4892.5  805.53  4895.8  804.88  4998.3  803.85  4998.8  803.35
  5010.4  803.85  5034.7  807.53  5044.8  809.98  5054.9  810.99  5145.8  812.29
  5176.1  813.82  5206.4   820.6  5297.3  845.47  5327.6  850.18  5347.8  850.95
#Mann= 4 ,-1 , 0
    4409    .035       0  4895.8     .12       0  4998.3     .05       0
  5010.4     .12       0
Bank Sta=4998.3,5010.4
XS Rating Curve= 0 ,0
Exp/Cntr=0.3,0.1

Type RM Length L Ch R = 1 ,15177   ,250,250,250
BEGIN DESCRIPTION:
A19451
END DESCRIPTION:
XS GIS Cut Line= 3
      2243095.94     13836277.93      2242578.62     13835870.68
       2242089.4     13835848.69
#Sta/Elev= 30
  4239.6   822.3  4291.7  819.98  4320.3  815.67  4334.7  814.93  4349.2  815.32
  4527.2  810.94  4641.1  807.06  4684.4  808.62  4711.7  808.82  4716.4  807.97
  4812.7  807.85  4849.5  809.04  4902.3  808.46  4909.9  807.15  4914.9  808.64
  4921.6  805.09  4931.6  803.48  4975.6  802.59  4976.1  802.09  4987.7  802.59
  5061.8  805.59  5101.8  809.32  5145.9  810.44  5161.9  811.37  5181.9  815.33
  5211.9  825.82    5252  842.47    5272  848.71    5322   855.1  5387.7  857.69
#Mann= 6 ,-1 , 0
  4239.6    .035       0  4716.4     .12       0  4849.5    .035       0
  4975.6    .035       0  4987.7    .035       0  5145.9     .12       0
Bank Sta=4975.6,4987.7
XS Rating Curve= 0 ,0
Exp/Cntr=0.3,0.1

Type RM Length L Ch R = 1 ,14927   ,340,340,340
BEGIN DESCRIPTION:
A19450
END DESCRIPTION:
XS GIS Cut Line= 3
      2243123.43     13836255.89      2242655.67     13835667.06
      2242029.11     13835573.63
#Sta/Elev= 30
  4012.7   819.8  4019.2  820.07  4033.6  816.99  4062.5  814.68  4126.6     813
  4240.3  812.35    4290  810.55  4453.4  808.99  4460.8  808.08  4511.1  806.88
  4613.2  807.98  4652.4   809.5  4775.5  809.89  4836.2  808.17  4967.6  802.35
  4991.9  802.07  4992.4  801.57    5004  802.07  5083.8  805.19    5099  807.42
  5139.5   818.9  5148.1  822.34  5153.1  822.18  5159.7  826.02  5210.3  845.98
  5217.3  849.43  5222.4  849.33  5230.5  851.93  5331.6  862.62  5398.2  868.33
#Mann= 4 ,-1 , 0
  4012.7    .035       0  4613.2     .12       0  4991.9     .05       0
    5004     .12       0
Bank Sta=4991.9,5004
XS Rating Curve= 0 ,0
Exp/Cntr=0.3,0.1

Type RM Length L Ch R = 1 ,14587   ,466,466,466
BEGIN DESCRIPTION:
Isaac Creek 32.0
END DESCRIPTION:
XS GIS Cut Line= 3
      2243387.58     13835292.84        2242425.       13835325.
      2242132.85     13835276.33
#Sta/Elev= 30
  4041.7  840.63  4134.3  832.26  4194.4  824.11  4414.5     813  4454.5  812.59
  4564.6  806.12  4604.6  802.05  4704.7  801.16  4714.7  800.27  4728.6  796.94
  4729.1  796.44  4740.7  796.94  4754.7  801.69  4764.7  803.56  4857.4  804.26
  4914.8  801.38  4934.8  798.74  5007.4  797.51    5015  803.89  5065.6  816.73
  5116.3  825.07  5159.5  827.19  5177.2  830.92  5187.3   834.4  5215.2  839.75
  5220.3  839.02  5248.1  845.57  5276.1  849.38  5281.1  848.65    5301  851.99
#Mann= 3 ,-1 , 0
  4041.7     .12       0  4728.6     .05       0  4740.7     .12       0
Bank Sta=4728.6,4740.7
XS Rating Curve= 0 ,0
Exp/Cntr=0.3,0.1

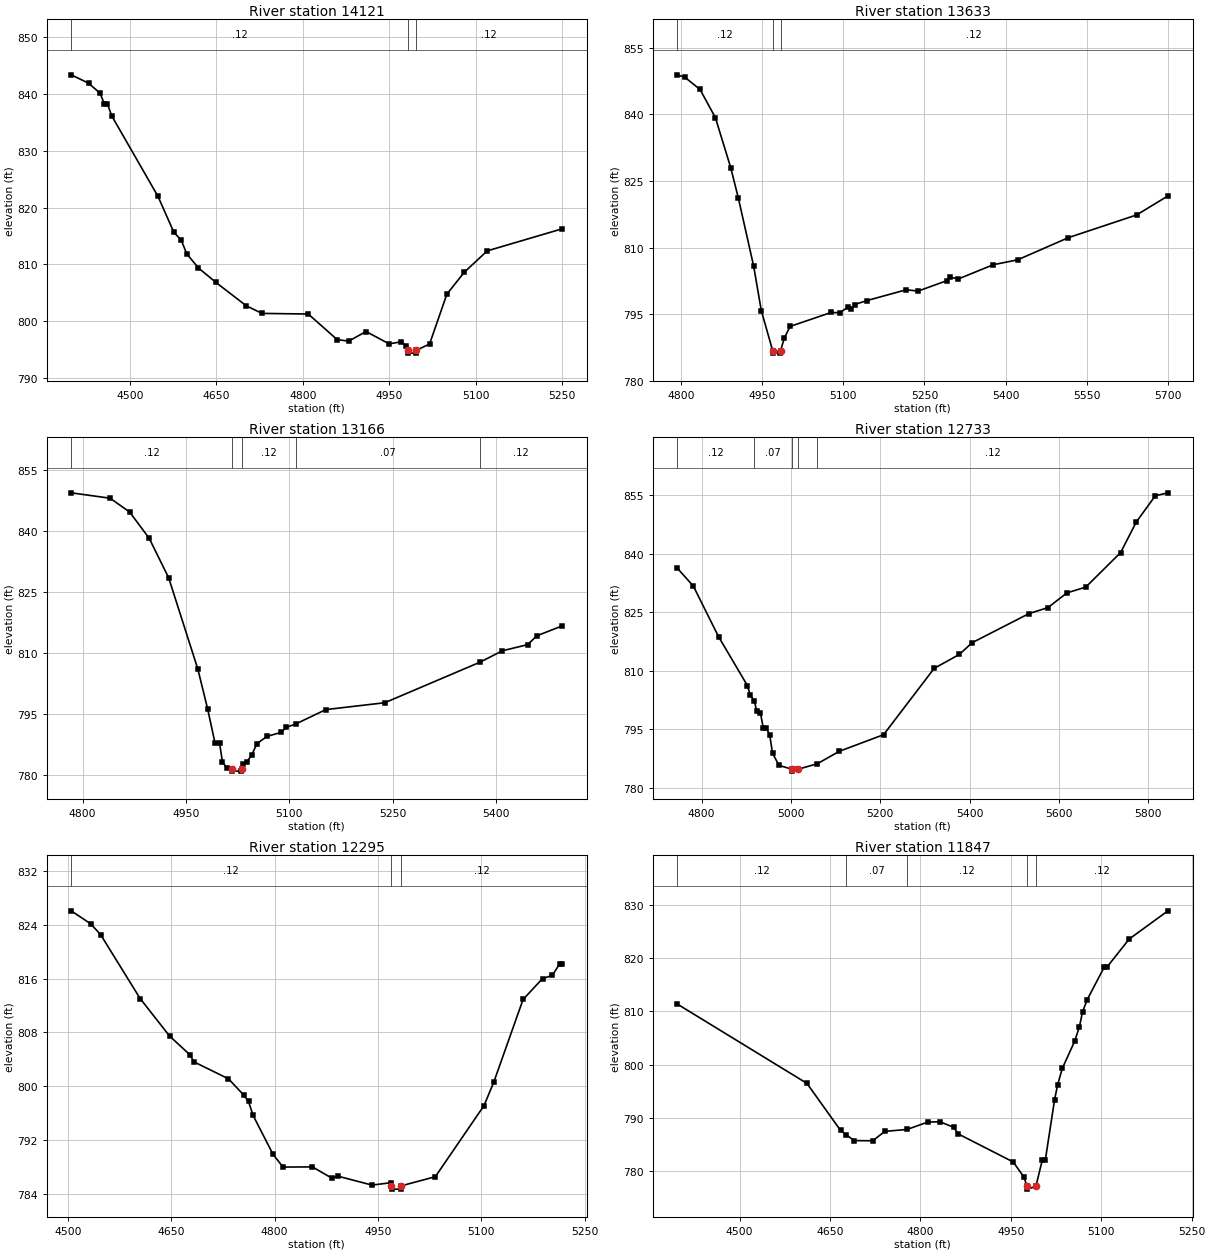
Type RM Length L Ch R = 1 ,14121   ,488,488,488
BEGIN DESCRIPTION:
Isaac Creek 31.0
END DESCRIPTION:
XS GIS Cut Line= 3
      2243325.03       13835025.        2242725.       13834975.
      2242475.01       13834975.
#Sta/Elev= 30
  4397.9  843.35    4428  841.88  4448.1   840.1  4455.6  838.17  4460.7  838.26
  4468.2  836.14  4548.5  821.97  4576.1  815.64  4588.6  814.31  4598.6  811.84
  4618.7  809.37  4648.8  806.85  4701.5  802.73  4729.1  801.37  4809.4  801.26
  4859.5  796.76  4879.6  796.49  4909.7  798.18  4949.8  796.01  4969.9  796.36
  4979.9  795.68  4982.8  794.88  4983.3  794.38  4996.6  794.38  4997.1  794.88
    5020  795.99    5050  804.75    5080  808.59    5120  812.37    5250  816.25
#Mann= 3 ,-1 , 0
  4397.9     .12       0  4982.8     .05       0  4997.1     .12       0
Bank Sta=4982.8,4997.1
XS Rating Curve= 0 ,0
Exp/Cntr=0.3,0.1

Type RM Length L Ch R = 1 ,13633   ,467,467,467
BEGIN DESCRIPTION:
Isaac Creek 30.0
END DESCRIPTION:
XS GIS Cut Line= 3
      2243124.97     13834475.03        2242975.       13834625.
      2242375.01     13834974.99
#Sta/Elev= 30
  4793.2  848.91  4807.3  848.38  4835.6  845.61  4863.9  839.26  4892.2  828.01
  4906.3  821.16  4934.6  805.81  4948.7  795.82  4969.8  786.72  4970.3  786.22
  4983.7  786.22  4984.2  786.72  4991.2   789.6  5001.8  792.23  5077.7  795.38
  5093.4  795.32  5109.1  796.59  5114.9  796.18  5121.1  797.17  5144.2  798.07
  5216.6   800.5  5238.1  800.19    5291  802.52  5296.8  803.37  5312.5  802.92
    5377  806.13  5422.1  807.23  5515.9  812.23    5642  817.35  5699.9  821.64
#Mann= 3 ,-1 , 0
  4793.2     .12       0  4969.8     .05       0  4984.2     .12       0
Bank Sta=4969.8,4984.2
XS Rating Curve= 0 ,0
Exp/Cntr=0.3,0.1

Type RM Length L Ch R = 1 ,13166   ,433,433,433
BEGIN DESCRIPTION:
Isaac Creek 29.0
END DESCRIPTION:
XS GIS Cut Line= 3
      2242774.98     13834225.02        2242625.       13834375.
        2242325.       13834775.
#Sta/Elev= 30
  4783.6  849.33  4840.1     848  4868.4   844.6  4896.7  838.15    4925  828.42
  4967.4  805.91  4981.6   796.1  4992.2  787.79  4998.8  787.79    5003  783.12
  5009.2  781.68  5016.6  781.37  5017.1  780.87  5030.5  780.87    5031  781.37
  5032.2  782.65  5038.4  783.14  5045.7  784.93    5053  787.63  5067.6  789.41
  5088.4  790.42  5095.7  791.66    5109  792.44    5153  796.01  5238.4  797.69
  5376.9  807.69  5409.2  810.48  5445.7  811.98  5459.2  814.17  5495.7  816.59
#Mann= 5 ,-1 , 0
  4783.6     .12       0  5016.6     .05       0    5031     .12       0
    5109     .07       0  5376.9     .12       0
Bank Sta=5016.6,5031
XS Rating Curve= 0 ,0
Exp/Cntr=0.3,0.1

Type RM Length L Ch R = 1 ,12733   ,438,438,438
BEGIN DESCRIPTION:
Isaac Creek 28.0
END DESCRIPTION:
XS GIS Cut Line= 3
      2242424.97     13834125.02        2242225.       13834275.
      2241624.99     13834875.01
#Sta/Elev= 30
  4745.4  836.35  4781.8  831.69  4838.1  818.76  4902.7  806.24  4908.9  803.84
  4918.4  802.27  4923.5  799.65  4931.8  799.27  4938.1  795.48  4945.4  795.29
  4952.7  793.57  4958.9  788.91  4973.5  785.79  5002.3  784.83  5002.8  784.33
  5016.7  784.83  5059.1  786.22  5108.5  789.41  5207.5  793.66  5320.6  810.63
  5377.2  814.22  5405.5   817.2  5532.8  824.66  5575.2  826.19  5617.6  829.95
    5660  831.45  5737.8  840.27  5773.2  848.15  5815.6  854.83  5843.9  855.58
#Mann= 5 ,-1 , 0
  4745.4     .12       0  4918.4     .07       0  5002.3     .05       0
  5016.7     .07       0  5059.1     .12       0
Bank Sta=5002.3,5016.7
XS Rating Curve= 0 ,0
Exp/Cntr=0.3,0.1

Type RM Length L Ch R = 1 ,12295   ,448,448,448
BEGIN DESCRIPTION:
Isaac Creek 27.0
END DESCRIPTION:
XS GIS Cut Line= 3
      2242225.03     13833924.98        2241825.       13834225.
      2241674.98     13834375.02
#Sta/Elev= 30
    4505  826.09  4533.2  824.16  4547.7  822.54    4605  813.04  4647.7  807.46
  4676.9   804.7  4683.2  803.61  4733.2  801.09    4755  798.71  4762.3  797.72
  4768.6  795.71  4797.7  789.88  4812.3  787.96    4855  787.99  4883.2  786.31
  4891.5  786.62  4941.5  785.28  4968.6  785.63  4969.7  785.18  4970.2  784.68
  4983.7  784.68  4984.2  785.18  5033.3  786.53    5104  797.12  5118.2  800.63
  5160.6   812.9  5188.9  816.02    5203  816.47  5213.6  818.19  5217.2  818.19
#Mann= 3 ,-1 , 0
    4505     .12       0  4969.7     .05       0  4984.2     .12       0
Bank Sta=4969.7,4984.2
XS Rating Curve= 0 ,0
Exp/Cntr=0.3,0.1

Type RM Length L Ch R = 1 ,11847   ,465,465,465
BEGIN DESCRIPTION:
Isaac Creek 26.0
END DESCRIPTION:
XS GIS Cut Line= 3
      2242074.97     13833875.01        2241475.       13833975.
        2241275.       13834025.
#Sta/Elev= 30
  4396.2  811.41  4611.6  796.47  4667.4  787.62  4677.2  786.76  4690.2  785.71
  4720.6  785.67  4740.9  787.44  4777.6   787.8  4811.8  789.18  4832.1  789.26
  4854.9  788.21  4862.5  786.97  4953.8  781.69  4971.5  778.87  4976.9  777.08
  4977.4  776.58  4991.4  777.08  5001.9  781.97    5007  781.97  5022.5  793.43
  5027.6  796.25  5035.4  799.32    5056  804.45  5063.7  807.15  5068.9  809.93
  5076.6  812.22  5104.9  818.35  5110.1  818.44  5146.2  823.61  5210.6  828.92
#Mann= 5 ,-1 , 0
  4396.2     .12       0  4677.2     .07       0  4777.6     .12       0
  4976.9     .05       0  4991.4     .12       0
Bank Sta=4976.9,4991.4
XS Rating Curve= 0 ,0
Exp/Cntr=0.3,0.1

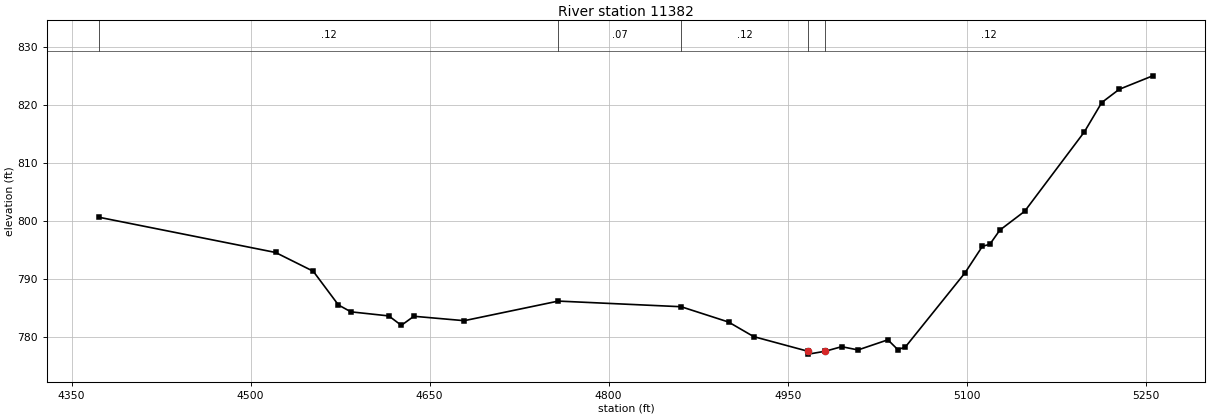
Type RM Length L Ch R = 1 ,11382   ,227,227,227
BEGIN DESCRIPTION:
Isaac Creek 25.0
END DESCRIPTION:
XS GIS Cut Line= 3
      2241875.02     13833775.01        2241275.       13833575.
      2241124.99     13833775.02
#Sta/Elev= 30
  4373.3  800.66  4520.9  794.62  4552.5  791.39  4573.6  785.59  4584.1  784.41
  4615.8  783.71  4626.3  782.09  4636.8  783.65    4679  782.89  4757.8  786.26
  4860.7  785.29  4900.4  782.66  4921.5  780.15  4966.8  777.64  4967.3  777.14
  4981.5  777.64  4995.2  778.42  5008.9  777.86  5033.9   779.6  5042.2  777.92
  5048.5  778.35  5098.5  791.11  5113.1  795.68  5119.3  796.02  5127.7  798.46
  5148.5   801.7  5198.5  815.35  5213.1   820.4  5227.7  822.67  5255.8  824.99
#Mann= 5 ,-1 , 0
  4373.3     .12       0  4757.8     .07       0  4860.7     .12       0
  4966.8     .05       0  4981.5     .12       0
Bank Sta=4966.8,4981.5
XS Rating Curve= 0 ,0
Exp/Cntr=0.3,0.1