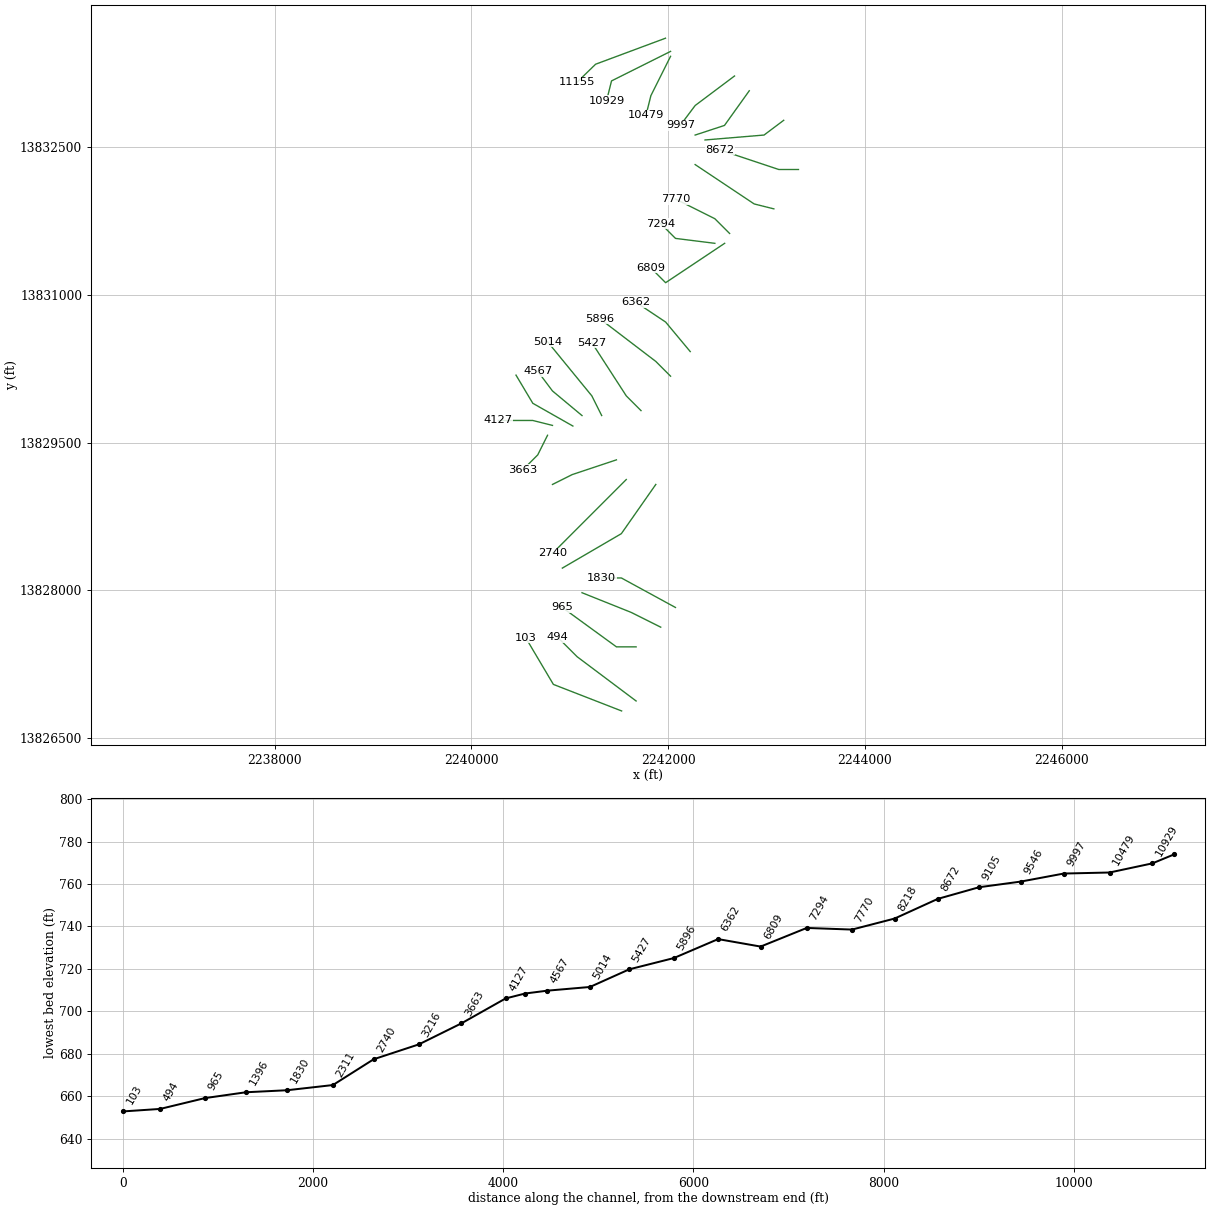
HEC-RAS study Isaac Creek.prj: Isaac Creek Base Level Engineering

--- Isaac Creek.g01 (geometry) --- (continued)

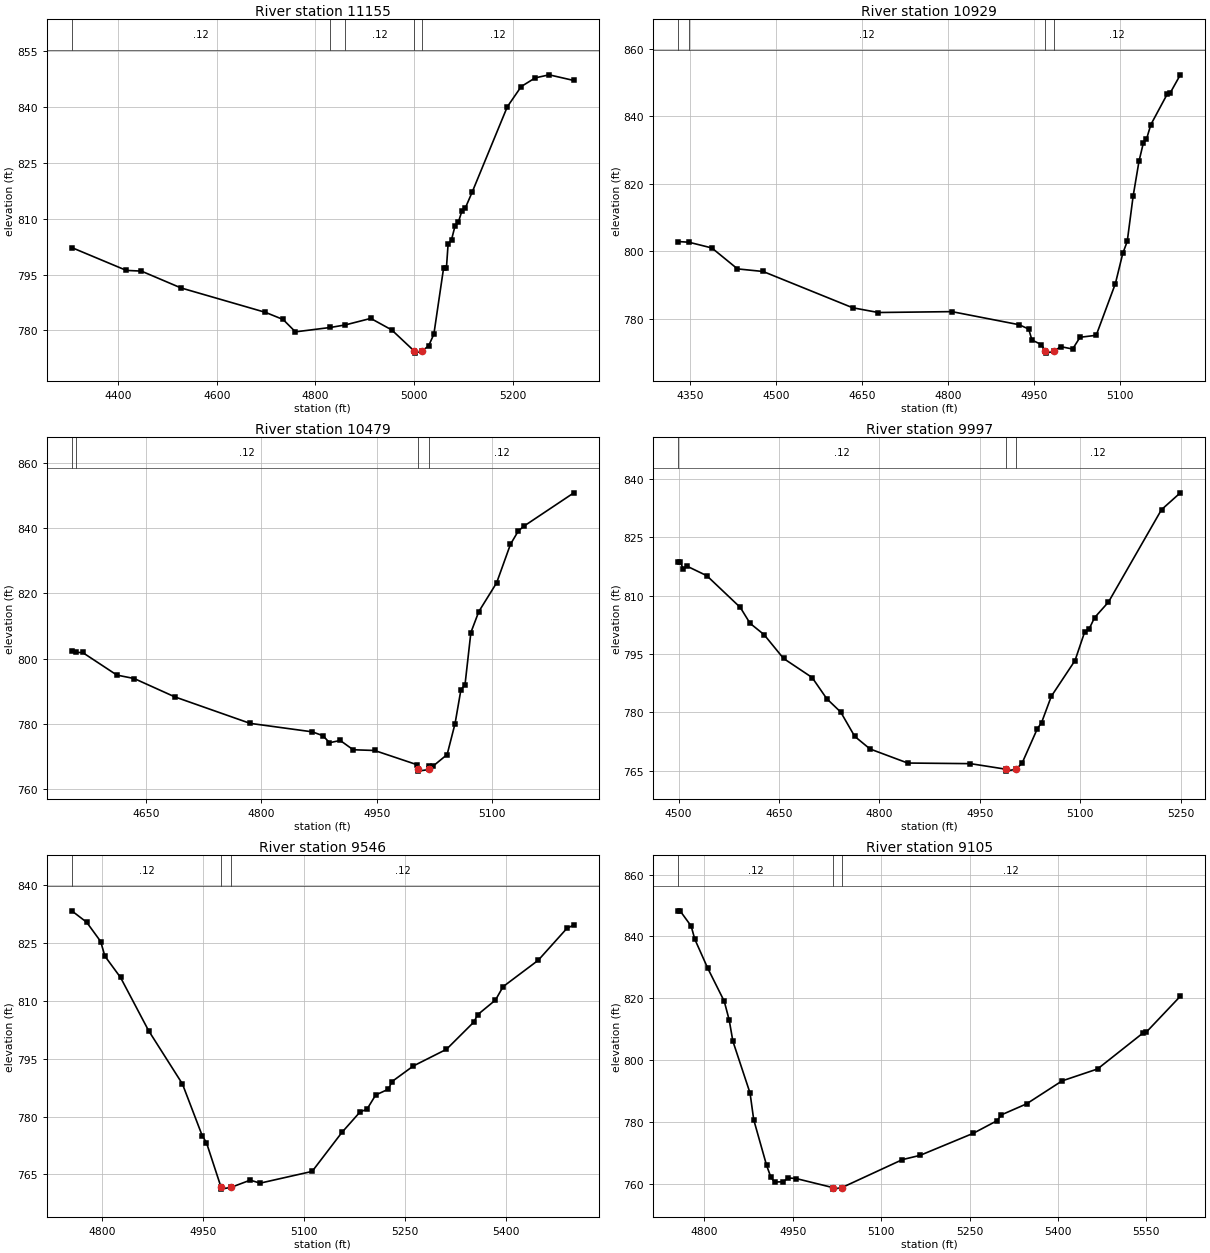
Type RM Length L Ch R = 1 ,11155   ,226,226,226
BEGIN DESCRIPTION:
A19449
END DESCRIPTION:
XS GIS Cut Line= 3
      2241973.29     13833608.85      2241263.34     13833344.68
       2241076.2     13833163.04
#Sta/Elev= 30
  4305.9  802.25  4416.7  796.12    4447  795.94  4527.4  791.42  4698.8  784.86
  4734.5  782.95  4759.5  779.63  4830.6  780.81    4861   781.5  4912.3  783.24
  4954.9  780.14  5000.9  774.42  5001.4  773.92  5015.6  774.42  5029.6  775.85
  5040.3  779.01  5059.9  796.64  5065.7  796.64  5069.1  803.08  5076.1  804.36
  5083.2  808.04  5090.2  809.15  5097.4  812.18  5104.4  812.97  5118.5   817.3
  5189.2  840.03  5217.5  845.48  5245.8   847.8  5274.1  848.62  5324.2   847.1
#Mann= 5 ,-1 , 0
  4305.9     .12       0  4830.6     .07       0    4861     .12       0
  5000.9     .05       0  5015.6     .12       0
Bank Sta=5000.9,5015.6
XS Rating Curve= 0 ,0
Exp/Cntr=0.3,0.1

Type RM Length L Ch R = 1 ,10929   ,450,450,450
BEGIN DESCRIPTION:
Isaac Creek 24.0
END DESCRIPTION:
XS GIS Cut Line= 3
      2242025.04     13833475.02        2241425.       13833175.
      2241375.01     13832975.02
#Sta/Elev= 30
  4328.6  802.84  4347.2  802.64  4387.3  800.94  4432.1  794.73  4476.8  793.96
  4633.3   783.2    4678  781.79  4806.6  782.05    4924  778.17  4940.8  776.88
  4946.4  773.63  4963.1  772.25  4969.8  770.24  4970.3  769.74  4984.5  770.24
  4996.7  771.67  5017.5  770.95  5030.4  774.44  5058.7  775.03  5092.2  790.37
  5105.1  799.33  5112.9  802.89  5123.2  816.33  5133.5  826.73  5141.2  832.19
  5146.4  833.13  5154.1  837.52  5182.4  846.47  5187.6  846.82  5205.6   852.3
#Mann= 4 ,-1 , 0
  4328.6     .07       0  4347.2     .12       0  4969.8     .05       0
  4984.5     .12       0
Bank Sta=4969.8,4984.5
XS Rating Curve= 0 ,0
Exp/Cntr=0.3,0.1

Type RM Length L Ch R = 1 ,10479   ,482,482,482
BEGIN DESCRIPTION:
Isaac Creek 23.0
END DESCRIPTION:
XS GIS Cut Line= 3
      2242025.02     13833425.03        2241825.       13833025.
        2241775.       13832825.
#Sta/Elev= 30
  4553.2  802.19  4558.9  801.86  4567.2  801.87  4611.9  794.92  4634.3  793.87
  4687.4  788.22  4785.2   780.1  4866.3  777.49  4880.3  776.28  4888.6  774.15
  4902.6  774.84  4919.4  771.99  4947.3  771.77    5003  767.36  5003.4  765.93
  5003.9  765.43  5018.2  765.93  5018.5  767.07  5023.6  767.01  5041.7  770.52
    5052  780.03  5059.7  790.49  5064.9  791.84  5072.6  807.99  5082.9  814.41
  5106.1  823.24  5124.1  835.07  5134.4  839.19  5142.2  840.74  5206.6  850.88
#Mann= 4 ,-1 , 0
  4553.2     .07       0  4558.9     .12       0  5003.4     .05       0
  5018.2     .12       0
Bank Sta=5003.4,5018.2
XS Rating Curve= 0 ,0
Exp/Cntr=0.3,0.1

Type RM Length L Ch R = 1 ,9997    ,451,451,451
BEGIN DESCRIPTION:
Isaac Creek 22.0
END DESCRIPTION:
XS GIS Cut Line= 3
      2242675.03     13833225.02        2242275.       13832925.
      2242125.02     13832725.03
#Sta/Elev= 30
  4499.5  818.67  4502.7  818.67  4506.8  816.93  4513.1  817.54  4542.2  815.13
  4592.2  806.98  4606.8   802.9  4627.7     800  4656.8  793.88  4699.5  788.98
  4721.4  783.53  4742.2  780.11  4763.1  773.87    4786  770.63  4842.2  767.02
    4936  766.86  4988.7  765.44  4989.2  764.94  5004.2  765.44  5013.1  766.98
    5036  775.86  5042.2  777.39  5056.8  784.16  5092.2  793.34  5106.8  800.77
  5113.1  801.39  5121.4  804.36  5142.2  808.37  5221.4   832.1  5249.5  836.42
#Mann= 3 ,-1 , 0
  4499.5     .12       0  4988.7     .05       0  5004.2     .12       0
Bank Sta=4988.7,5004.2
XS Rating Curve= 0 ,0
Exp/Cntr=0.3,0.1

Type RM Length L Ch R = 1 ,9546    ,441,441,441
BEGIN DESCRIPTION:
Isaac Creek 21.0
END DESCRIPTION:
XS GIS Cut Line= 3
      2242824.99     13833074.99      2242573.12     13832722.81
      2242275.03     13832625.01
#Sta/Elev= 30
  4754.7  833.36  4776.8  830.41  4797.7   825.4  4803.9  821.62  4827.2  816.08
  4868.9  802.29  4919.3  788.44  4948.8  774.98    4955  773.22  4976.7  761.66
  4977.2  761.16  4992.2  761.66  5020.1  763.49  5034.8  762.71  5112.2  765.76
  5156.5  775.88  5183.3  781.15  5193.8  781.91  5206.7  785.58  5225.6  787.09
  5230.9  789.06  5262.7  793.11    5312  797.44    5353  804.56  5358.2  806.39
  5384.8  810.21  5396.2  813.69  5448.4  820.53  5490.9  828.78  5501.4   829.7
#Mann= 3 ,-1 , 0
  4754.7     .12       0  4976.7     .05       0  4992.2     .12       0
Bank Sta=4976.7,4992.2
XS Rating Curve= 0 ,0
Exp/Cntr=0.3,0.1

Type RM Length L Ch R = 1 ,9105    ,433,433,433
BEGIN DESCRIPTION:
Isaac Creek 20.0
END DESCRIPTION:
XS GIS Cut Line= 3
        2243175.       13832775.        2242975.       13832625.
      2242374.97       13832575.
#Sta/Elev= 30
  4755.5  848.28  4758.6  848.28  4777.4  843.37  4783.6  839.13  4805.5  829.79
  4833.6  819.09    4842  813.03  4848.2  806.24  4877.4  789.46  4883.6  780.87
  4905.5  766.12  4912.8  762.27    4919  760.78  4933.6  760.84    4942   762.1
  4955.5   761.9  5017.8  758.98  5018.3  758.48  5033.3  758.98  5135.9     768
    5166  769.38  5256.4  776.51  5296.5  780.55    5304  782.45  5346.7     786
  5406.9   793.4  5467.1  797.25  5544.9  808.95  5549.9  809.14  5607.6  820.71
#Mann= 3 ,-1 , 0
  4755.5     .12       0  5017.8     .05       0  5033.3     .12       0
Bank Sta=5017.8,5033.3
XS Rating Curve= 0 ,0
Exp/Cntr=0.3,0.1

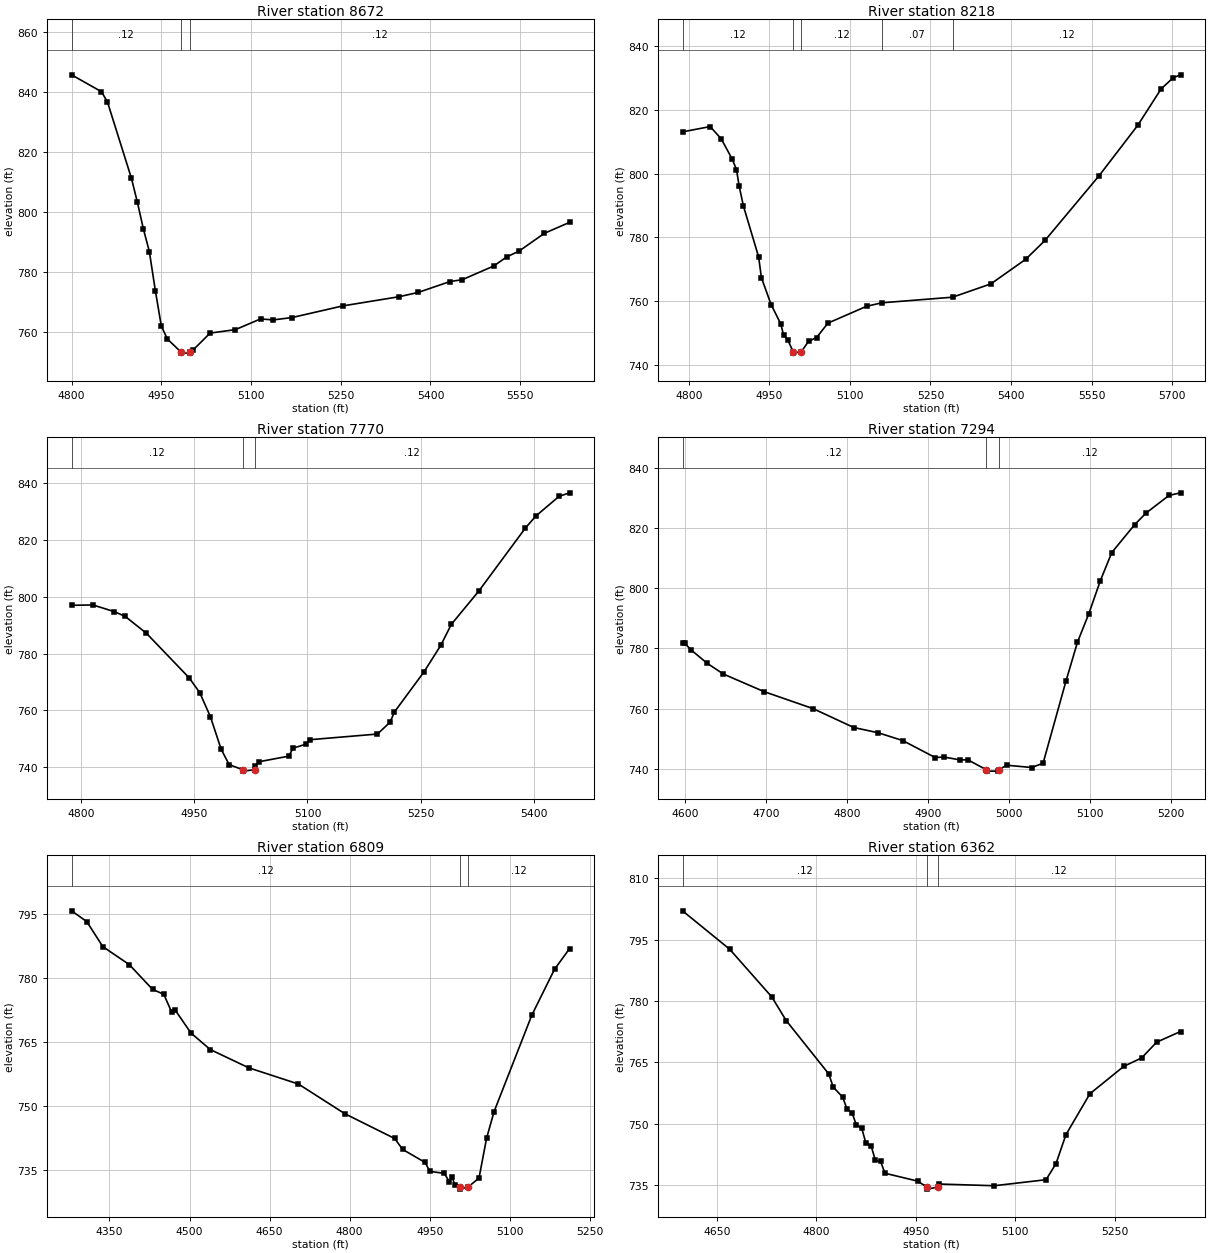
Type RM Length L Ch R = 1 ,8672    ,454,454,454
BEGIN DESCRIPTION:
Isaac Creek 19.0
END DESCRIPTION:
XS GIS Cut Line= 3
      2243324.99       13832275.        2243125.       13832275.
      2242525.04     13832474.99
#Sta/Elev= 30
  4800.1  845.59  4850.1  839.97  4860.1  836.56  4900.1  811.21  4910.1  803.21
  4920.1  794.34  4930.1   786.8  4940.1  773.82  4950.1  762.05  4960.1  757.72
  4982.3   753.5  4982.8     753  4997.4     753  4997.9   753.5  5002.7  753.95
  5031.7  759.67  5073.9  760.81    5116  764.38  5137.1  764.05  5168.7  764.84
  5253.1   768.7  5347.9  771.78  5379.6   773.2  5432.3   776.8  5453.3  777.44
  5506.1  782.02  5527.1  784.98  5548.2  786.96  5590.4  792.86  5632.5  796.51
#Mann= 3 ,-1 , 0
  4800.1     .12       0  4982.3     .05       0  4997.9     .12       0
Bank Sta=4982.3,4997.9
XS Rating Curve= 0 ,0
Exp/Cntr=0.3,0.1

Type RM Length L Ch R = 1 ,8218    ,448,448,448
BEGIN DESCRIPTION:
Isaac Creek 18.0
END DESCRIPTION:
XS GIS Cut Line= 3
      2243074.99       13831875.        2242875.       13831925.
      2242274.96     13832325.03
#Sta/Elev= 30
  4788.4  813.05  4839.9  814.71  4860.5  810.86  4881.2  804.44  4888.9  801.19
    4894  795.96  4901.8  789.83  4930.1  773.89  4935.3  767.38  4953.3  758.96
  4971.3  752.92  4976.5  749.44  4984.2  747.93  4994.3  744.23  4994.8  743.73
  5009.9  744.23  5023.1  747.43  5038.1  748.62  5059.1  753.12  5131.3  758.42
  5159.7   759.5  5291.2  761.25  5362.6  765.43  5427.2   773.1  5463.3  779.03
  5563.9  799.27    5636  815.08  5679.6  826.52  5702.1  830.01  5715.7  830.92
#Mann= 5 ,-1 , 0
  4788.4     .12       0  4994.3     .05       0  5009.9     .12       0
  5159.7     .07       0  5291.2     .12       0
Bank Sta=4994.3,5009.9
XS Rating Curve= 0 ,0
Exp/Cntr=0.3,0.1

Type RM Length L Ch R = 1 ,7770    ,476,476,476
BEGIN DESCRIPTION:
Isaac Creek 17.0
END DESCRIPTION:
XS GIS Cut Line= 3
      2242624.99     13831625.01        2242475.       13831775.
      2242075.03     13831974.98
#Sta/Elev= 30
  4787.7  797.03    4816  797.15  4844.3  794.79  4858.4  793.17  4886.7  787.19
  4943.3  771.47  4957.4  766.21  4971.5  757.74  4985.7  746.29  4996.3  740.83
  5014.4  739.04  5014.9  738.54    5030  739.04  5030.6  740.32  5036.2  741.87
  5075.3  743.83  5080.9  746.64  5097.7  748.02  5103.2  749.62  5192.7  751.62
  5209.5  755.84    5215  759.35  5254.2  773.52  5276.5   782.9  5290.5  790.32
  5326.8  802.04  5388.3  824.21  5402.3   828.5  5433.1  835.46    5447   836.7
#Mann= 3 ,-1 , 0
  4787.7     .12       0  5014.4     .05       0    5030     .12       0
Bank Sta=5014.4,5030
XS Rating Curve= 0 ,0
Exp/Cntr=0.3,0.1

Type RM Length L Ch R = 1 ,7294    ,485,485,485
BEGIN DESCRIPTION:
Isaac Creek 16.0
END DESCRIPTION:
XS GIS Cut Line= 3
      2242475.01       13831525.        2242075.       13831575.
      2241924.97     13831725.03
#Sta/Elev= 30
  4596.6  781.81  4599.1  781.81  4606.7  779.63  4626.8  775.14    4647  771.53
  4697.4  765.68  4757.9  760.05  4808.2  753.78  4838.5  752.03  4868.7  749.45
    4909  743.79  4919.1  744.01  4939.3  743.04  4949.3  743.05  4971.7  739.81
  4972.2  739.31  4986.9  739.31  4987.4  739.81  4997.2  741.27    5028  740.51
  5042.1  741.94  5070.4   769.2  5084.6   782.1  5098.7   791.6  5112.9  802.53
    5127  811.84  5155.3   821.1  5169.4  824.95  5197.7  830.78  5211.9  831.64
#Mann= 3 ,-1 , 0
  4596.6     .12       0  4971.7     .05       0  4987.4     .12       0
Bank Sta=4971.7,4987.4
XS Rating Curve= 0 ,0
Exp/Cntr=0.3,0.1

Type RM Length L Ch R = 1 ,6809    ,447,447,447
BEGIN DESCRIPTION:
Isaac Creek 15.0
END DESCRIPTION:
XS GIS Cut Line= 3
      2242574.99       13831525.        2241975.       13831125.
      2241825.03     13831274.97
#Sta/Elev= 30
    4279  795.65  4307.5  793.13  4337.6  787.27  4387.2  783.06  4430.7  777.28
  4451.8  776.12  4466.8  771.89  4472.8  772.49  4502.8  767.05  4538.9  763.19
    4611  758.92  4704.1  755.12  4791.3  748.16  4884.4  742.38  4899.4  739.82
  4941.5  736.77  4950.5  734.68  4977.6  734.22  4986.6  732.31  4992.6  733.29
  4997.1  731.42  5006.4  731.03  5006.9  730.53  5022.1  731.03  5042.5  733.12
  5056.7  742.45  5070.8  748.69  5141.5  771.25    5184  781.97  5212.2  786.81
#Mann= 3 ,-1 , 0
    4279     .12       0  5006.4     .05       0  5022.1     .12       0
Bank Sta=5006.4,5022.1
XS Rating Curve= 0 ,0
Exp/Cntr=0.3,0.1

Type RM Length L Ch R = 1 ,6362    ,466,466,466
BEGIN DESCRIPTION:
Isaac Creek 14.0
END DESCRIPTION:
XS GIS Cut Line= 3
      2242225.03     13830424.97        2241975.       13830725.
      2241675.01     13830924.99
#Sta/Elev= 30
  4598.3  802.03  4669.3  792.67  4733.1  780.97  4754.6  775.24    4819  762.16
  4825.5  759.01  4839.8  756.52  4846.3  753.65  4854.1  752.64  4860.6  749.67
  4868.4  749.05    4875  745.21  4882.8  744.56  4889.3  741.05  4897.1   740.8
  4903.6  737.93  4953.1     736  4966.8  734.55  4967.3  734.05  4983.5  734.55
  4985.6  735.29  5068.5  734.88  5146.6  736.35  5161.6  740.28  5176.6  747.35
  5212.7  757.34  5263.8  764.04  5290.8   766.1  5313.4  769.95  5349.4  772.55
#Mann= 3 ,-1 , 0
  4598.3     .12       0  4966.8     .05       0  4983.5     .12       0
Bank Sta=4966.8,4983.5
XS Rating Curve= 0 ,0
Exp/Cntr=0.3,0.1

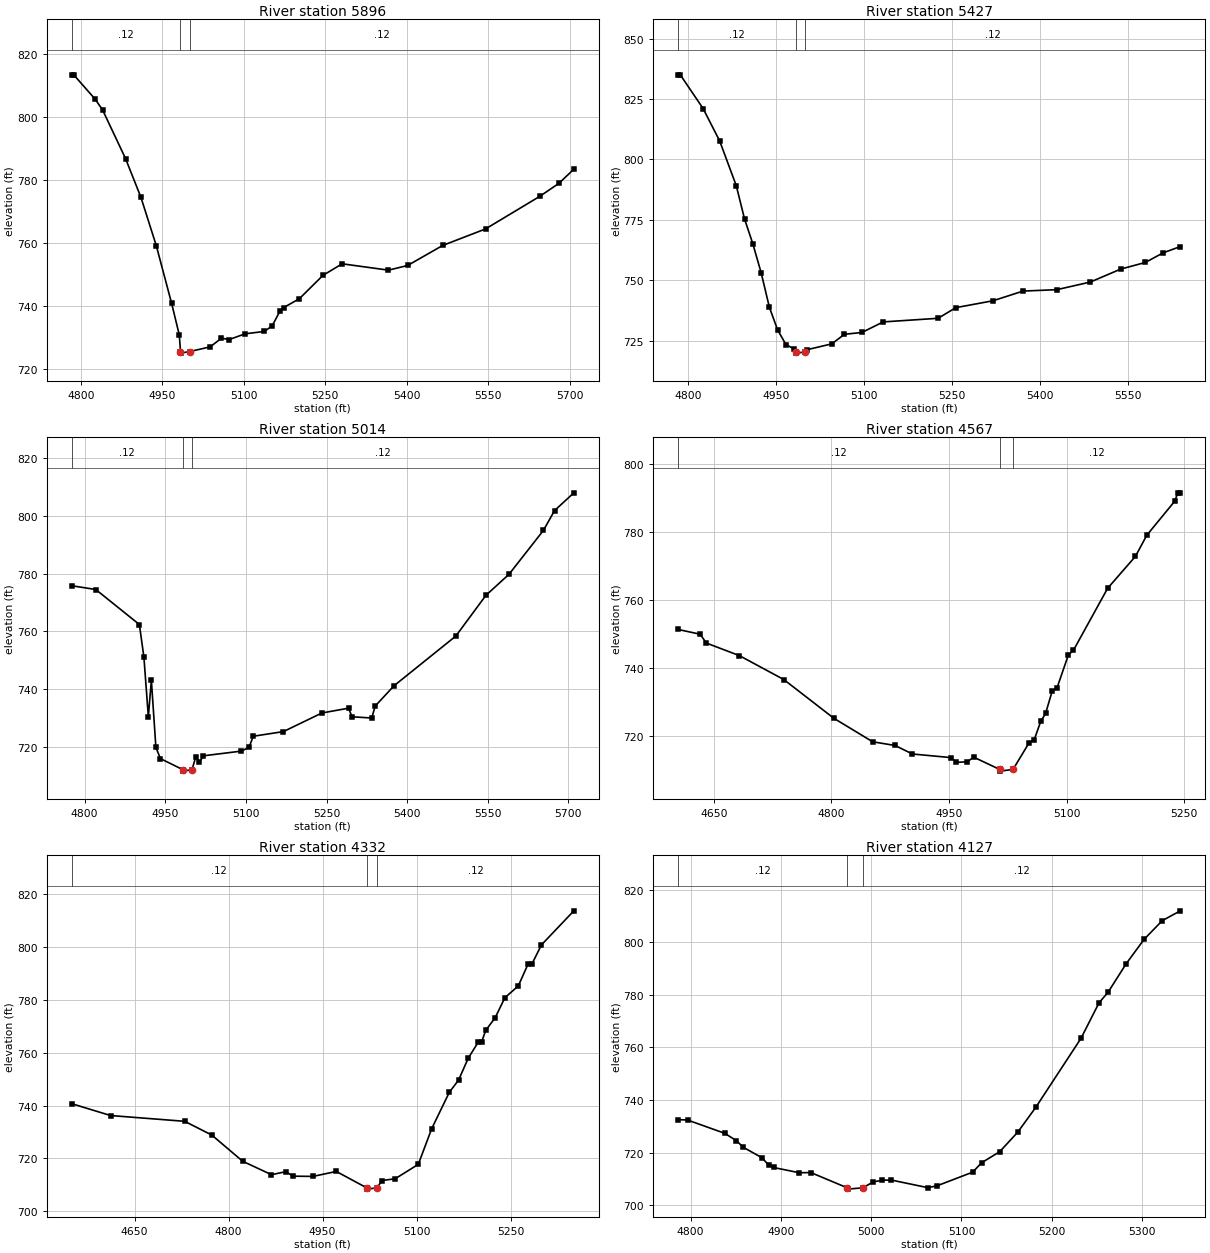
Type RM Length L Ch R = 1 ,5896    ,469,469,469
BEGIN DESCRIPTION:
Isaac Creek 13.0
END DESCRIPTION:
XS GIS Cut Line= 3
      2242025.02     13830174.98        2241875.       13830325.
       2241308.7     13830757.12
#Sta/Elev= 30
  4783.1   813.4  4786.7   813.4  4825.6  805.79  4839.7  802.32  4882.1  786.83
  4910.4  774.56  4938.7  759.21    4967  740.88  4981.1  730.86  4983.3  725.61
  4983.8  725.11  5000.1  725.61  5037.9  727.09  5058.7  729.84  5073.2  729.43
  5102.3  731.24  5137.7  731.99  5152.2  733.78  5166.7  738.54    5173  739.54
  5202.1  742.36  5245.7  749.79    5281  753.45  5366.3  751.43  5401.6  752.92
    5466  759.26    5545  764.51  5644.7  774.83  5680.1  778.97  5707.6  783.46
#Mann= 3 ,-1 , 0
  4783.1     .12       0  4983.3     .05       0  5000.1     .12       0
Bank Sta=4983.3,5000.1
XS Rating Curve= 0 ,0
Exp/Cntr=0.3,0.1

Type RM Length L Ch R = 1 ,5427    ,413,413,413
BEGIN DESCRIPTION:
Isaac Creek 12.0
END DESCRIPTION:
XS GIS Cut Line= 3
      2241724.97     13829825.03        2241575.       13829975.
      2241224.84     13830515.97
#Sta/Elev= 30
  4783.5     835    4787     835  4825.9  821.05  4854.2  807.62  4882.5  789.11
  4896.6  775.33  4910.7   765.1  4924.9   753.1    4939  738.78  4953.2   729.3
  4967.3  723.33  4981.5  721.48  4983.6   720.3  4984.1   719.8  5000.5   720.3
  5003.2  721.22  5045.4  723.63  5067.1  727.61  5096.8  728.34  5133.1  732.72
  5226.8  734.22  5257.1  738.63  5320.4  741.47  5371.8  745.49  5429.2  746.06
  5486.6  749.23    5538  754.56  5580.3  757.33  5610.6   761.3    5640  763.92
#Mann= 3 ,-1 , 0
  4783.5     .12       0  4983.6     .05       0  5000.5     .12       0
Bank Sta=4983.6,5000.5
XS Rating Curve= 0 ,0
Exp/Cntr=0.3,0.1

Type RM Length L Ch R = 1 ,5014    ,447,447,447
BEGIN DESCRIPTION:
Isaac Creek 11.0
END DESCRIPTION:
XS GIS Cut Line= 3
        2241325.     13829775.01        2241225.       13829975.
      2240775.02     13830524.98
#Sta/Elev= 30
    4776  775.76  4820.7  774.45  4901.8  762.31  4910.2  751.04  4918.5  730.35
  4924.1  743.01  4932.5  719.77  4940.9  715.84  4982.8  711.99  4983.3  711.49
  4999.7  711.99  5006.8  716.46  5013.2  714.52  5021.1   716.8  5091.5  718.43
  5105.8  719.72  5113.7  723.58  5169.7  725.19  5241.5  731.65    5291  733.31
  5297.5  730.33  5334.1   729.9  5340.6  734.05  5375.7   741.1  5490.6  758.31
  5546.6  772.43  5589.6  779.74  5653.5  794.92  5674.3  801.81  5710.2  807.97
#Mann= 3 ,-1 , 0
    4776     .12       0  4982.8     .05       0  4999.7     .12       0
Bank Sta=4982.8,4999.7
XS Rating Curve= 0 ,0
Exp/Cntr=0.3,0.1

Type RM Length L Ch R = 1 ,4567    ,235,235,235
BEGIN DESCRIPTION:
Isaac Creek 10.0
END DESCRIPTION:
XS GIS Cut Line= 3
        2241125.       13829775.        2240825.       13830025.
      2240675.01     13830224.99
#Sta/Elev= 30
  4604.5   751.4  4632.5  750.01  4640.3  747.42  4682.6  743.71  4739.2  736.68
    4803   725.3  4852.5  718.39  4881.1   717.3  4903.2   714.8  4952.7  713.73
  4959.2  712.33  4973.5  712.52  4981.3  713.88  5014.6  710.26  5015.1  709.76
  5031.6  710.26  5052.3  718.17  5058.6  718.96  5066.9  724.36  5073.1  726.71
  5081.5  733.25  5087.7  734.22  5102.3  743.99  5108.6  745.26  5152.3  763.52
  5187.7  772.88  5202.3  779.13  5237.7  789.07  5241.9  791.58    5245  791.58
#Mann= 3 ,-1 , 0
  4604.5     .12       0  5014.6     .05       0  5031.6     .12       0
Bank Sta=5014.6,5031.6
XS Rating Curve= 0 ,0
Exp/Cntr=0.3,0.1

Type RM Length L Ch R = 1 ,4332    ,205,205,205
BEGIN DESCRIPTION:
A19448
END DESCRIPTION:
XS GIS Cut Line= 3
      2241032.21     13829668.49      2240624.96     13829899.63
      2240454.38     13830185.77
#Sta/Elev= 30
  4549.7  740.72  4611.6  736.25  4729.9  734.06  4773.2  728.86  4822.5  718.95
  4868.5  713.87  4891.4  715.01  4902.9  713.31  4934.7  713.22  4971.9   715.1
  5020.4  708.91  5020.9  708.41  5037.4  708.91  5044.4  711.66  5065.8  712.32
  5102.8  717.78  5124.2  731.27  5152.3  745.02  5167.1  749.66  5182.6  757.98
  5198.2  763.89    5204  764.17  5210.5  768.48  5225.5  773.24    5241  780.81
  5262.4  785.26    5278  793.53  5283.9  793.43  5299.4   800.8  5351.1  813.68
#Mann= 3 ,-1 , 0
  4549.7     .12       0  5020.4     .05       0  5037.4     .12       0
Bank Sta=5020.4,5037.4
XS Rating Curve= 0 ,0
Exp/Cntr=0.3,0.1

Type RM Length L Ch R = 1 ,4127    ,464,464,464
BEGIN DESCRIPTION:
Isaac Creek 9.0
END DESCRIPTION:
XS GIS Cut Line= 3
      2240824.98       13829675.        2240625.       13829725.
      2240275.04       13829725.
#Sta/Elev= 30
  4786.3  732.53  4796.6  732.39  4837.8  727.33  4850.7  724.54  4858.4     722
  4879.1  718.01  4886.8  715.08  4891.9  714.32  4920.3  712.32  4933.2  712.38
  4973.5  706.58    4974  706.08  4990.7  706.58  5002.4  708.84  5012.4  709.48
  5022.4  709.53  5062.4  706.66  5072.4  707.27  5112.4  712.54  5122.4  716.14
  5142.4  720.34  5162.4  727.79  5182.4  737.26  5232.4  763.49  5252.4  777.03
  5262.4  781.04  5282.4  791.87  5302.4  801.22  5322.4  808.29  5342.4  812.03
#Mann= 3 ,-1 , 0
  4786.3     .12       0  4973.5     .05       0  4990.7     .12       0
Bank Sta=4973.5,4990.7
XS Rating Curve= 0 ,0
Exp/Cntr=0.3,0.1

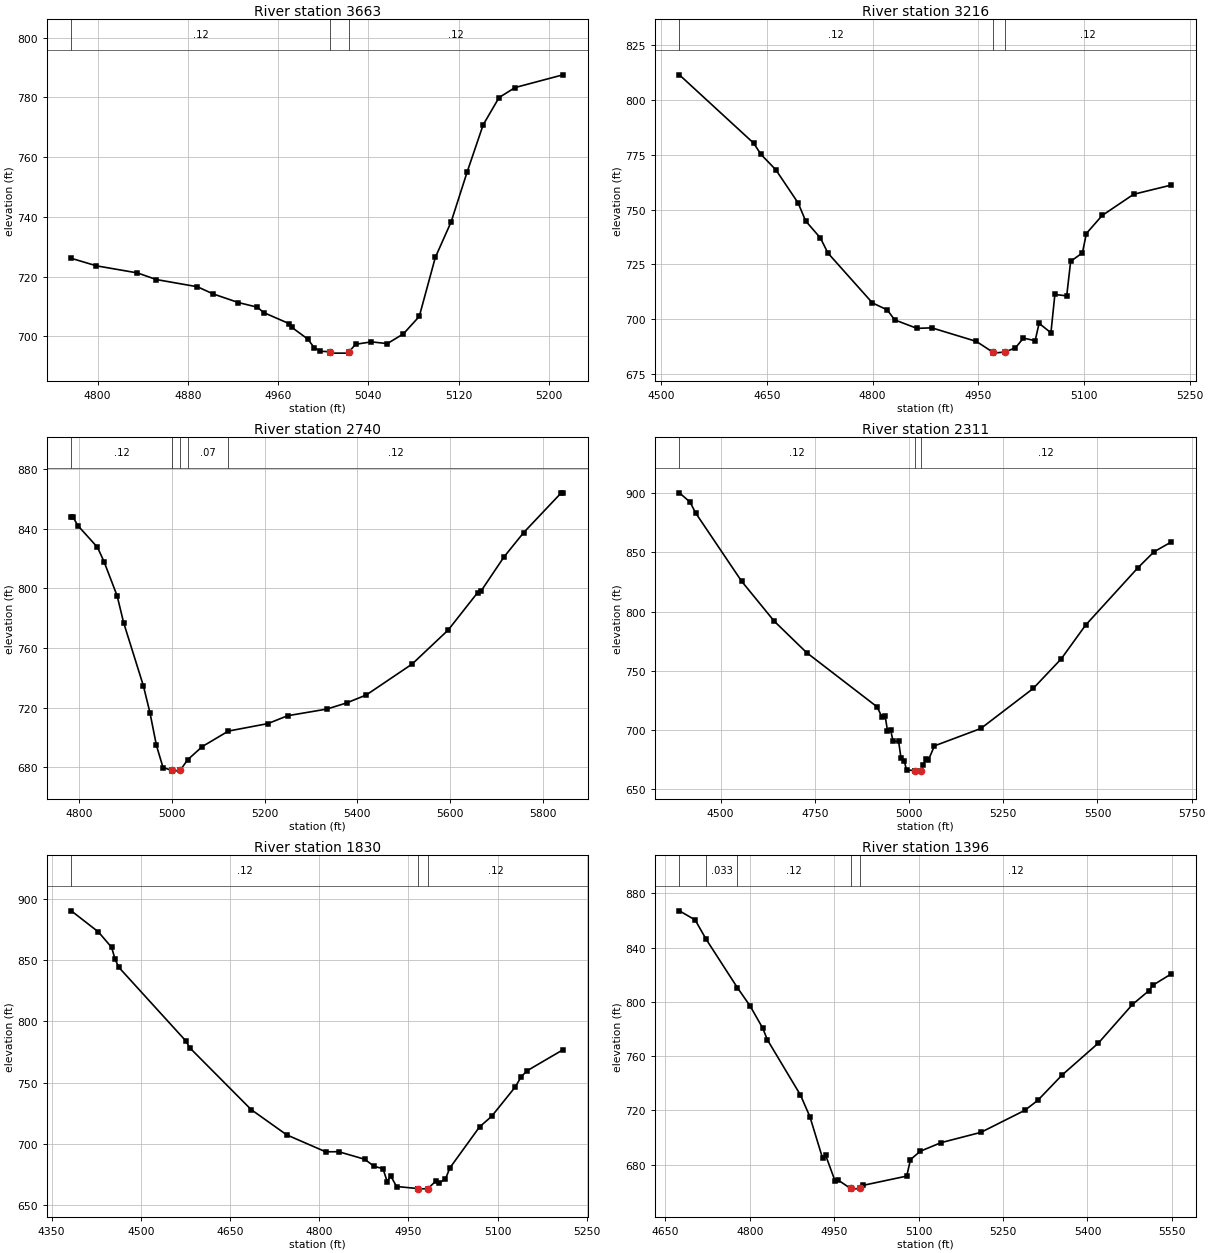
Type RM Length L Ch R = 1 ,3663    ,447,447,447
BEGIN DESCRIPTION:
Isaac Creek 8.0
END DESCRIPTION:
XS GIS Cut Line= 3
      2240774.98     13829574.97        2240675.       13829375.
        2240525.       13829225.
#Sta/Elev= 30
  4776.7  726.12    4799   723.6  4835.4  721.22  4852.1     719  4888.5  716.59
  4902.4  714.19  4924.8   711.3  4941.6  709.74  4947.2  707.95  4969.5  704.28
  4972.3  702.96  4986.3  699.06  4991.9  696.24  4997.5  694.96  5005.8  694.86
  5006.3  694.36  5022.5  694.36    5023  694.86  5028.6  697.32  5042.7  698.13
  5056.8  697.55    5071   700.8  5085.1  706.65  5099.3   726.4  5113.4  738.39
  5127.5  755.01  5141.7  770.81  5155.8  779.96    5170  783.31  5212.4  787.57
#Mann= 3 ,-1 , 0
  4776.7     .12       0  5005.8     .05       0    5023     .12       0
Bank Sta=5005.8,5023
XS Rating Curve= 0 ,0
Exp/Cntr=0.3,0.1

Type RM Length L Ch R = 1 ,3216    ,476,476,476
BEGIN DESCRIPTION:
Isaac Creek 7.0
END DESCRIPTION:
XS GIS Cut Line= 3
      2241474.96     13829324.99        2241025.       13829175.
      2240825.01       13829075.
#Sta/Elev= 30
  4525.7  811.46  4631.1  780.29  4641.6  775.13  4662.7  768.09  4694.3  752.97
  4704.9  744.79  4725.9  737.02  4736.5  730.15  4799.7  707.38  4820.8  704.19
  4831.3  699.63    4863  695.76    4884     696  4947.3   689.8  4970.3  684.96
  4970.8  684.46  4987.6  684.96  5002.8   686.9    5014   691.3  5030.7  690.16
  5036.3  698.05  5053.1  693.75  5058.7  711.23  5075.5  710.59  5081.1  726.35
  5097.8  730.21  5103.4  739.05  5125.8  747.27  5170.5  756.95  5223.6  761.13
#Mann= 3 ,-1 , 0
  4525.7     .12       0  4970.3     .05       0  4987.6     .12       0
Bank Sta=4970.3,4987.6
XS Rating Curve= 0 ,0
Exp/Cntr=0.3,0.1

Type RM Length L Ch R = 1 ,2740    ,429,429,429
BEGIN DESCRIPTION:
Isaac Creek 6.0
END DESCRIPTION:
XS GIS Cut Line= 3
        2241575.       13829125.        2241425.       13828975.
      2240824.97     13828374.97
#Sta/Elev= 30
  4783.1  847.95  4786.6  847.95  4797.2  842.08  4839.7  827.48  4853.8  817.89
  4882.1  794.94  4896.2  776.85  4938.7  734.65  4952.8  716.72  4966.9  694.64
  4981.1  679.83  5000.7  677.94  5001.2  677.44    5018  677.94  5034.3  685.09
  5065.9  693.93  5122.1  704.29  5207.4  709.31  5249.8  714.57  5334.6  719.05
  5377.1  723.16  5419.5  728.48  5518.5  749.23  5596.3  772.05  5659.9  797.17
    5667   798.1  5716.5  820.98  5758.9  837.29  5840.2  864.01  5843.8  864.01
#Mann= 5 ,-1 , 0
  4783.1     .12       0  5000.7     .05       0    5018     .12       0
  5034.3     .07       0  5122.1     .12       0
Bank Sta=5000.7,5018
XS Rating Curve= 0 ,0
Exp/Cntr=0.3,0.1

Type RM Length L Ch R = 1 ,2311    ,481,481,481
BEGIN DESCRIPTION:
Isaac Creek 5.0
END DESCRIPTION:
XS GIS Cut Line= 3
      2241874.98     13829074.97        2241525.       13828575.
      2240925.01       13828225.
#Sta/Elev= 30
  4390.4  900.28  4418.7   892.5  4433.5  883.31  4555.6  825.62  4641.9  791.98
  4728.2  765.33  4915.2  719.54  4927.9  711.03  4936.6  711.73  4942.7  699.44
  4951.4   699.7  4957.5   690.5  4972.3  690.38  4978.5  676.51  4987.2  673.91
  4993.3  666.26  5015.2  665.78  5015.7  665.28  5032.5  665.78  5035.8  670.59
  5045.8  675.52  5051.5  674.78  5067.3   686.6  5190.5  701.29  5329.4  735.06
  5403.8  760.06  5468.3  788.48  5607.2  836.95  5650.2  850.52  5695.3  858.65
#Mann= 3 ,-1 , 0
  4390.4     .12       0  5015.2     .05       0  5032.5     .12       0
Bank Sta=5015.2,5032.5
XS Rating Curve= 0 ,0
Exp/Cntr=0.3,0.1

Type RM Length L Ch R = 1 ,1830    ,434,434,434
BEGIN DESCRIPTION:
Isaac Creek 4.0
END DESCRIPTION:
XS GIS Cut Line= 3
      2242075.03     13827824.98        2241525.       13828125.
      2241325.03       13828125.
#Sta/Elev= 30
  4383.2  890.35  4428.8  873.12  4451.1  860.46  4456.8  850.84    4463  844.26
  4576.4  783.67  4582.1  778.53  4685.6  727.87  4745.4   707.2  4810.9  693.35
  4832.7  693.43  4876.4  687.27  4892.5  681.41  4907.2  679.62  4914.3  668.92
    4920  673.83    4930  664.97  4965.4  663.34  4965.9  662.84  4982.9  663.34
    4996   669.4  5001.7  667.86  5012.2  671.13  5019.7  680.21  5069.7  713.81
  5089.7  722.26  5129.7  746.44  5139.7  754.86  5149.7  759.68  5209.7  776.75
#Mann= 3 ,-1 , 0
  4383.2     .12       0  4965.4     .05       0  4982.9     .12       0
Bank Sta=4965.4,4982.9
XS Rating Curve= 0 ,0
Exp/Cntr=0.3,0.1

Type RM Length L Ch R = 1 ,1396    ,431,431,431
BEGIN DESCRIPTION:
Isaac Creek 3.0
END DESCRIPTION:
XS GIS Cut Line= 3
      2241925.01       13827625.        2241625.       13827775.
      2241125.03     13827974.99
#Sta/Elev= 30
  4674.7   867.2  4702.7   860.5  4722.1  846.34  4777.7  810.59  4800.5  796.97
  4822.8  780.69  4831.2     772  4889.9  731.32  4906.7  715.33  4929.1  684.87
  4934.7  686.84  4951.4  667.93    4957  668.52    4979  662.38  4979.5  661.88
  4996.5  662.38  5001.7  664.71  5078.8   671.5  5085.5  683.71    5103  689.83
  5139.4  696.12  5210.7  703.77  5288.8  720.05  5311.7  727.35  5354.8  746.01
  5419.4   769.6    5480  798.11  5509.6  808.38  5516.3  812.34  5548.6  820.55
#Mann= 5 ,-1 , 0
  4674.7     .12       0  4722.1    .033       0  4777.7     .12       0
    4979     .05       0  4996.5     .12       0
Bank Sta=4979,4996.5
XS Rating Curve= 0 ,0
Exp/Cntr=0.3,0.1

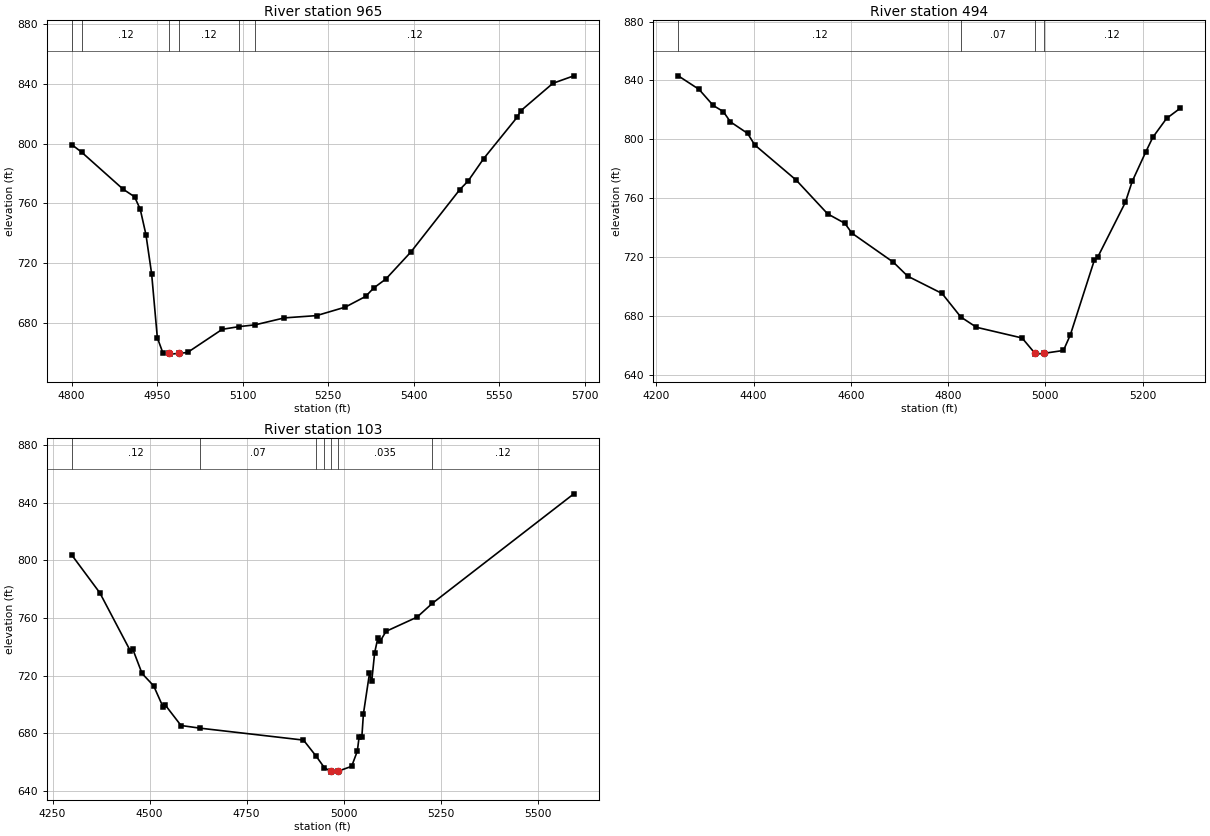
Type RM Length L Ch R = 1 ,965     ,471,471,471
BEGIN DESCRIPTION:
Isaac Creek 2.0
END DESCRIPTION:
XS GIS Cut Line= 3
      2241675.01       13827425.        2241475.       13827425.
      2240924.98     13827825.01
#Sta/Elev= 30
  4800.4  799.38  4817.8  794.27  4890.4  769.52  4910.4  764.47  4920.4  756.14
  4930.4  739.16  4940.4   712.9  4950.4  670.08  4960.4  659.66  4971.7  659.63
  4972.2  659.13  4989.2  659.63  5003.5  660.28  5064.2  675.75    5094  677.56
    5122  678.75  5173.1  683.39  5229.5  684.91  5279.8  690.59  5315.3  697.72
    5330  703.49  5350.9  709.37  5394.9  727.52  5480.7  769.32    5495  774.92
  5522.4  789.99  5581.2  817.73  5587.4  821.99  5643.8  840.41  5680.5  845.41
#Mann= 6 ,-1 , 0
  4800.4    .033       0  4817.8     .12       0  4971.7     .05       0
  4989.2     .12       0    5094     .07       0    5122     .12       0
Bank Sta=4971.7,4989.2
XS Rating Curve= 0 ,0
Exp/Cntr=0.3,0.1

Type RM Length L Ch R = 1 ,494     ,391,391,391
BEGIN DESCRIPTION:
Isaac Creek 1.0
END DESCRIPTION:
XS GIS Cut Line= 3
      2241674.99     13826875.01        2241075.       13827325.
      2240875.02     13827524.98
#Sta/Elev= 30
  4244.9  843.12  4287.6  833.94  4316.8  822.99  4337.6  818.83  4352.2  811.86
  4387.6  804.01  4402.2  796.19  4487.6  772.25  4552.2  749.34  4587.6  742.92
  4602.2  736.21  4687.6  716.44  4716.8  707.01  4787.6  695.24  4826.2  679.25
  4858.4  672.27  4952.2     665  4978.8  654.53  4979.3  654.03  4996.3  654.53
  5037.3  656.52  5051.5  667.13    5101  718.02    5108  720.05  5164.6  757.12
  5178.7  771.36    5207  791.66  5221.2  801.38  5249.4  814.16  5277.7  821.14
#Mann= 4 ,-1 , 0
  4244.9     .12       0  4826.2     .07       0  4978.8     .05       0
  4996.3     .12       0
Bank Sta=4978.8,4996.3
XS Rating Curve= 0 ,0
Exp/Cntr=0.3,0.1

Type RM Length L Ch R = 1 ,103     ,0,0,0
BEGIN DESCRIPTION:
A19447
END DESCRIPTION:
XS GIS Cut Line= 3
      2241527.46     13826773.79      2240834.09     13827043.44
      2240553.42     13827516.72
#Sta/Elev= 30
  4299.4  803.75  4371.7  777.46  4450.7  736.95    4456  738.75  4480.6   721.4
  4510.5  712.81    4535  697.92  4540.4  699.47    4581  685.25  4629.5  683.42
  4896.7  675.11  4929.5  663.88  4950.3  656.04  4966.9  653.35  4967.4  652.85
  4984.5  653.35  5020.9   656.9  5035.4  667.39  5040.2  677.48  5047.2  677.48
  5051.2   693.4  5066.8  721.43  5072.6  715.96  5080.1  735.76  5088.2  745.87
    5094  743.75  5109.6  750.71  5189.6  760.59  5228.8  770.16  5593.6  846.26
#Mann= 7 ,-1 , 0
  4299.4     .12       0  4629.5     .07       0  4929.5     .12       0
  4950.3    .035       0  4966.9    .035       0  4984.5    .035       0
  5228.8     .12       0
Bank Sta=4966.9,4984.5
XS Rating Curve= 0 ,0
Exp/Cntr=0.3,0.1

Chan Stop Cuts=-1
Use User Specified Reach Order=0
Composite Channel Slope=5