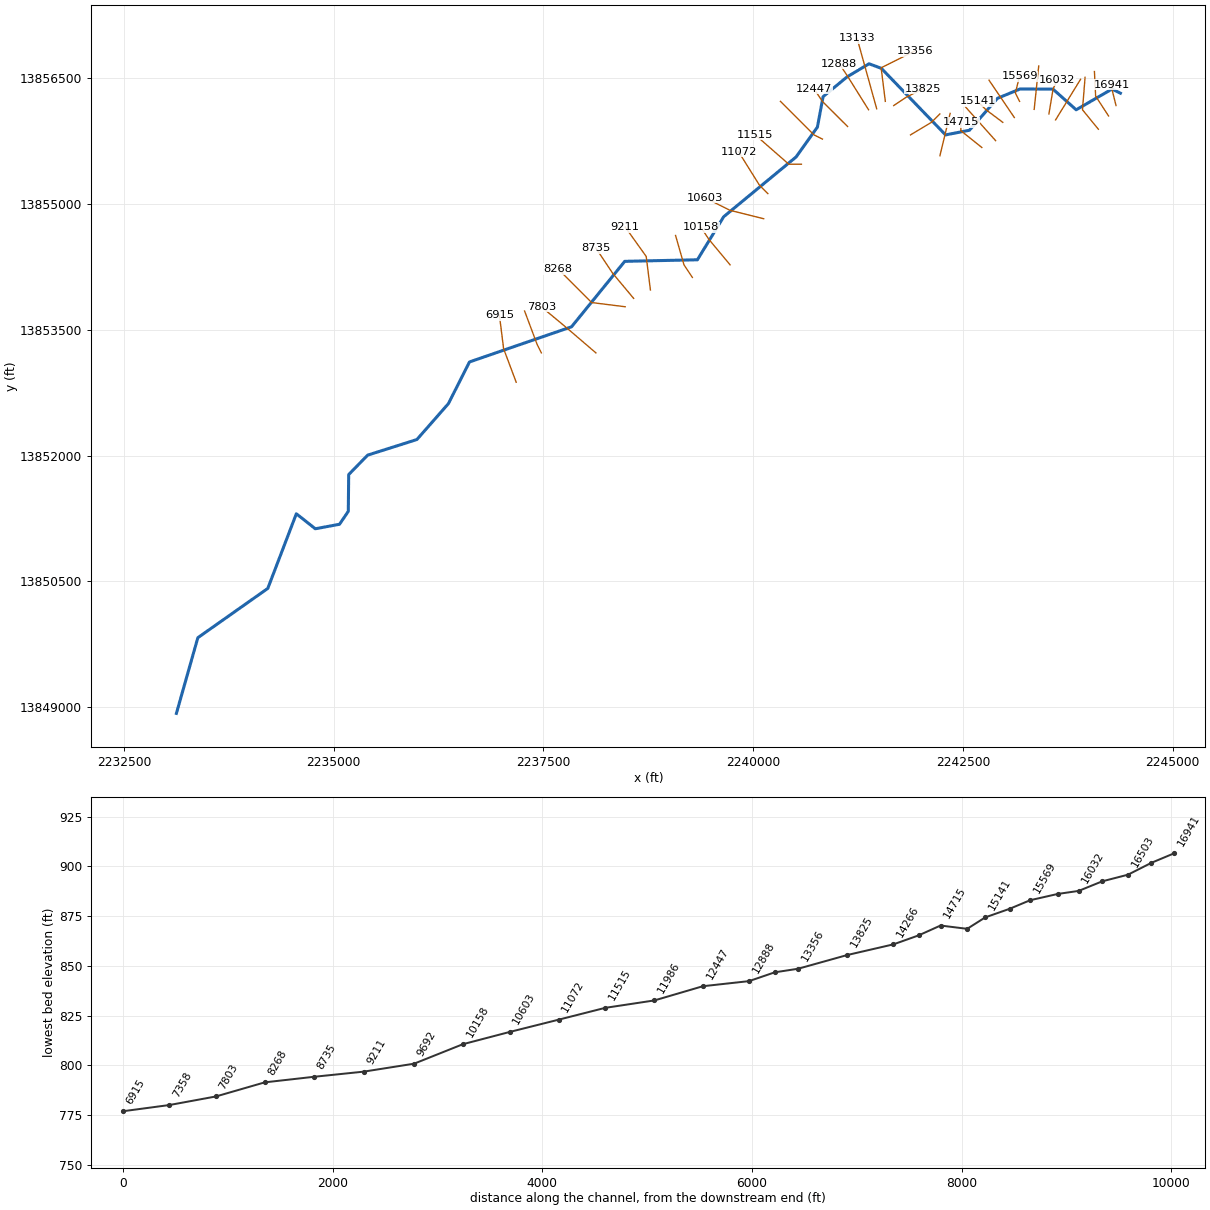
--- Jacobs Creek.prj (project) ---

Proj Title=Jacobs Creek Base Level Engineering
Current Plan=p01
Default Exp/Contr=0.3,0.1
English Units
Geom File=g01
Flow File=f01
Plan File=p01
Y Axis Title=Elevation
X Axis Title(PF)=Main Channel Distance
X Axis Title(XS)=Station
BEGIN DESCRIPTION:
Jacobs Creek
END DESCRIPTION:
DSS Export Rating Curves= 0
DSS Export Rating Curve Sorted= 0
DSS Export Volume Flow Curves= 0
DXF OffsetX= 0
DXF OffsetY= 0
DXF ScaleX= 1
DXF ScaleY= 10

--- Jacobs Creek.p01 (plan) ---

Plan Title=Multiple Run
Short Identifier=Multiple
Geom File=g01
Flow File=f01
Subcritical Flow
K Sum by GR= 0
Std Step Tol= 0.01
Critical Tol= 0.01
Num of Std Step Trials= 20
Max Error Tol= 0.3
Flow Tol Ratio= 0.001
Split Flow NTrial= 30
Split Flow Tol= 0.02
Split Flow Ratio= 0.02
Log Output Level= 0
Friction Slope Method= 1
Unsteady Friction Slope Method= 2
Unsteady Bridges Friction Slope Method= 1
Parabolic Critical Depth
Global Vel Dist=  1 , 1 , 1
Global Log Level= 0
CheckData=True
Encroach Param= -1, 0, 0, 0
BEGIN DESCRIPTION:
Multiple Run
END DESCRIPTION:

--- Jacobs Creek.f01 (steady flow) ---

Flow Title=Multiple
Number of Profiles=7
Profile Names=10-year,25-year,50-year,1pct_min,100-year,1pct_plu,500-year
River Rch & RM= Jacobs Creek,Reach-1,16941
     847    1404    1923    1278    2550    5088    4429
River Rch & RM= Jacobs Creek,Reach-1,16257
    1314    2238    3120    2106    4203    8385    7544
River Rch & RM= Jacobs Creek,Reach-1,14507
    1863    3226    4547    3099    6183   12337   11318
River Rch & RM= Jacobs Creek,Reach-1,9692
    2384    4170    5918    4057    8094   16149   14991
River Rch & RM= Jacobs Creek,Reach-1,3704
    2657    4663    6632    4554    9086   18129   16886
Boundary for River Rch & Prof#=Jacobs Creek,Reach-1,1
Up Type=0
Dn Type=3
Dn Slope=0.005
Boundary for River Rch & Prof#=Jacobs Creek,Reach-1,2
Up Type=0
Dn Type=3
Dn Slope=0.005
Boundary for River Rch & Prof#=Jacobs Creek,Reach-1,3
Up Type=0
Dn Type=3
Dn Slope=0.005
Boundary for River Rch & Prof#=Jacobs Creek,Reach-1,4
Up Type=0
Dn Type=3
Dn Slope=0.005
Boundary for River Rch & Prof#=Jacobs Creek,Reach-1,5
Up Type=0
Dn Type=3
Dn Slope=0.005
Boundary for River Rch & Prof#=Jacobs Creek,Reach-1,6
Up Type=0
Dn Type=3
Dn Slope=0.005
Boundary for River Rch & Prof#=Jacobs Creek,Reach-1,7
Up Type=0
Dn Type=3
Dn Slope=0.005

--- Jacobs Creek.g01 (geometry) ---

Geom Title=Existing Conditions
Program Version=4.10

River Reach=Jacobs Creek    ,Reach-1
Reach XY= 30
      2244377.47     13856322.53      2244276.68     13856371.69
      2243849.88     13856124.47      2243573.45     13856371.25
      2243180.94     13856372.74      2242911.78     13856261.38
      2242577.45     13855880.46      2242293.19      13855825.1
       2241527.3     13856619.17      2241381.04     13856673.38
      2241118.95     13856516.84      2240833.14     13856281.06
      2240765.59     13855918.38      2240511.38     13855561.76
      2239648.01     13854848.47       2239335.1     13854335.39
      2238468.94     13854316.86      2237834.71     13853535.75
      2236618.66     13853116.98      2236366.84     13852618.95
      2235991.79     13852191.44      2235404.91     13852005.22
      2235178.61      13851773.5      2235173.96     13851335.44
      2235069.39     13851180.59      2234780.85     13851127.06
      2234554.61     13851305.95      2234214.24     13850415.32
      2233380.52     13849827.43        2233125.       13848925.

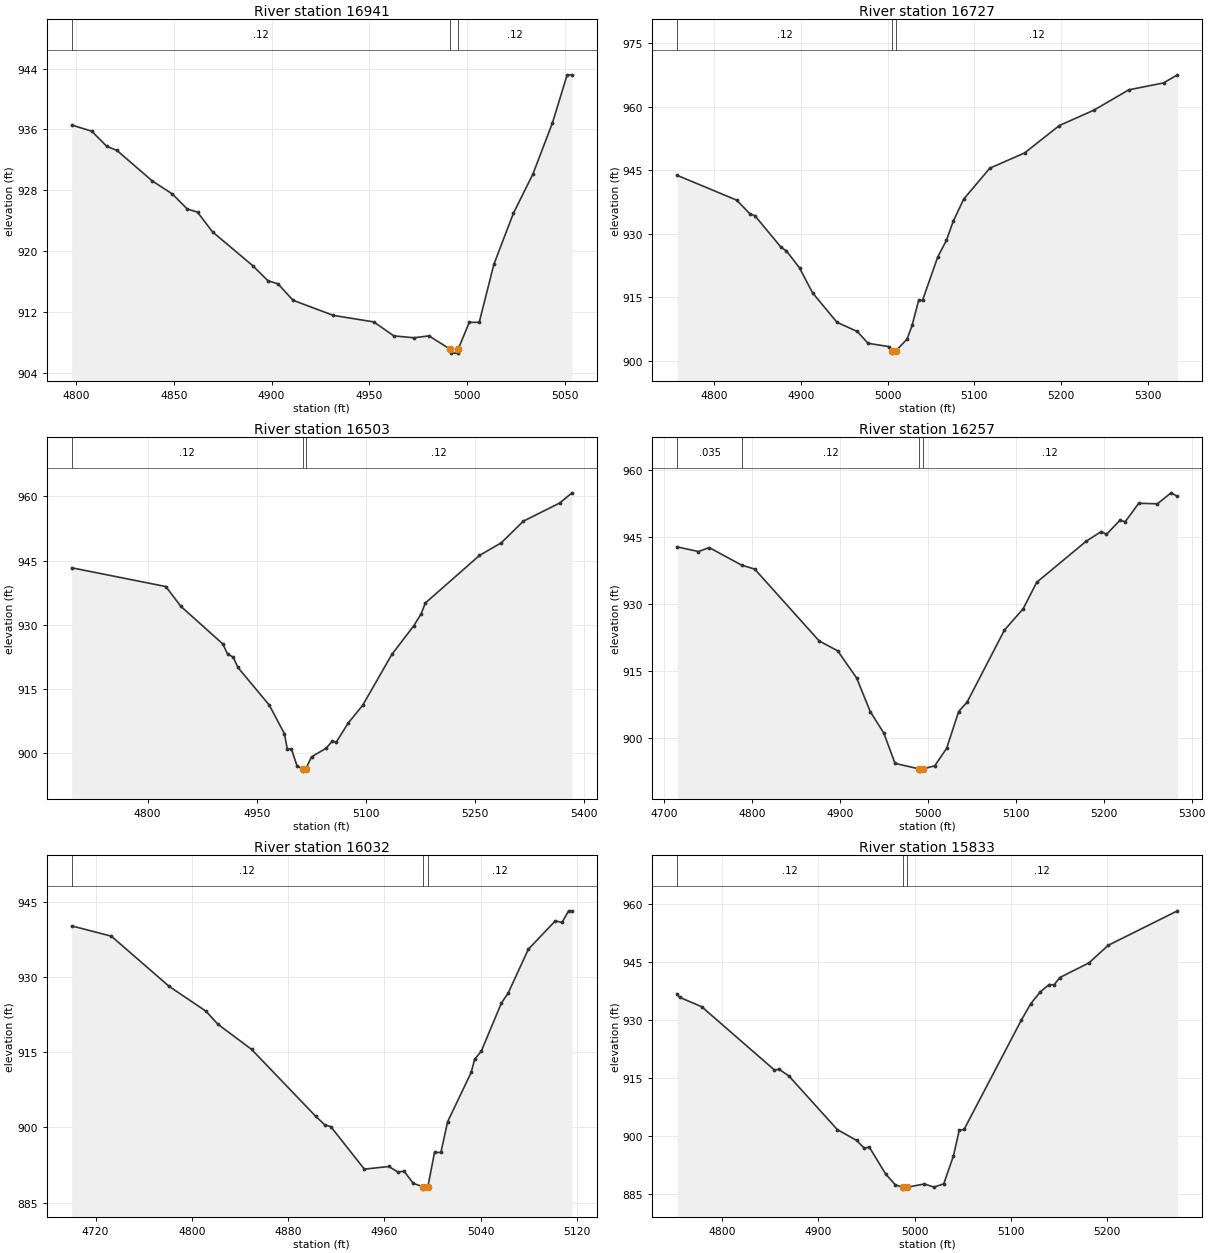
Type RM Length L Ch R = 1 ,16941   ,214,214,214
BEGIN DESCRIPTION:
Jacobs Creek 37.0
END DESCRIPTION:
XS GIS Cut Line= 3
      2244324.99     13856175.04        2244275.       13856375.
        2244275.     13856424.99
#Sta/Elev= 30
  4797.7  936.59    4808  935.77  4815.7  933.77  4820.8  933.26  4838.9  929.24
  4849.2  927.52  4856.9  925.53  4862.1  925.13  4869.8  922.53  4890.4  918.08
  4898.2  916.09  4903.3   915.7    4911  913.53  4931.7  911.54  4952.3  910.69
  4962.6  908.85  4972.9   908.6  4980.6  908.85  4991.5  907.08  4991.8  906.58
  4995.3  906.58  4995.5  907.08  5001.2  910.63  5006.3  910.63  5013.8  918.27
  5023.8  924.98  5033.8  930.15  5043.8  936.88  5051.3  943.19  5053.8  943.19
#Mann= 3 ,-1 , 0
  4797.7     .12       0  4991.5     .05       0  4995.5     .12       0
Bank Sta=4991.5,4995.5
XS Rating Curve= 0 ,0
Exp/Cntr=0.3,0.1

Type RM Length L Ch R = 1 ,16727   ,224,224,224
BEGIN DESCRIPTION:
A19506
END DESCRIPTION:
XS GIS Cut Line= 3
      2244236.23     13856050.59      2244081.87     13856287.52
      2244067.55     13856580.99
#Sta/Elev= 30
  4757.4  943.84    4826  937.98  4841.2  934.78  4847.1  934.28  4877.4   926.8
  4883.4     926  4898.5  921.97  4913.6  916.06  4941.7  909.13    4965  906.97
  4977.5  904.18  5001.2  903.41  5005.2  902.36  5005.4  901.86  5009.2  902.36
  5022.3  905.13  5028.2   908.4  5035.7  914.31  5040.2  914.31  5057.7  924.54
  5067.7  928.46  5075.6  932.99  5087.7  938.23  5117.8  945.53  5157.8  949.11
  5197.9  955.59  5237.9  959.24  5277.9  964.02    5318  965.65    5334  967.56
#Mann= 3 ,-1 , 0
  4757.4     .12       0  5005.2     .05       0  5009.2     .12       0
Bank Sta=5005.2,5009.2
XS Rating Curve= 0 ,0
Exp/Cntr=0.3,0.1

Type RM Length L Ch R = 1 ,16503   ,246,246,246
BEGIN DESCRIPTION:
Jacobs Creek 36.0
END DESCRIPTION:
XS GIS Cut Line= 3
      2244114.17     13855892.64        2243925.       13856125.
      2243956.07     13856511.83
#Sta/Elev= 30
  4695.7  943.31  4825.1  938.93  4845.9  934.29  4903.4  925.55  4909.9  923.21
  4917.8  922.45  4924.2  920.05  4967.3  911.28  4988.1   904.6  4992.1  901.01
  4997.8  901.01  5005.4  897.12  5013.4  896.38  5013.6  895.88  5017.4  896.38
  5025.4  899.22  5045.5  901.22  5054.1  902.94  5059.2  902.59  5075.6  907.06
  5095.6  911.22  5135.8  923.11  5165.9  929.78  5175.9  932.53  5181.8  935.09
  5256.2  946.19  5286.3  949.15  5316.4  954.17  5366.5  958.42  5383.4  960.79
#Mann= 3 ,-1 , 0
  4695.7     .12       0  5013.4     .05       0  5017.4     .12       0
Bank Sta=5013.4,5017.4
XS Rating Curve= 0 ,0
Exp/Cntr=0.3,0.1

Type RM Length L Ch R = 1 ,16257   ,225,225,225
BEGIN DESCRIPTION:
A19505
END DESCRIPTION:
XS GIS Cut Line= 2
      2243604.42     13856003.92      2243902.38     13856488.55
#Sta/Elev= 30
    4715   942.8  4739.3  941.75  4751.5  942.64  4788.6  938.68  4803.2  937.82
  4876.6   921.7  4897.5  919.51  4919.1  913.42  4934.6  905.87    4950  901.07
  4962.8  894.26  4990.4  893.03  4990.7  892.53  4994.6  893.03    5008  893.73
  5021.5  897.66  5035.1  905.89  5044.7  907.98  5087.2  924.15  5108.5  928.94
  5123.9  934.86    5180  944.04  5197.3  946.24  5203.2  945.61  5218.6  948.77
  5224.5  948.44  5239.9  952.57  5261.2  952.45  5276.6  954.91  5283.9  954.12
#Mann= 4 ,-1 , 0
    4715    .035       0  4788.6     .12       0  4990.4     .05       0
  4994.6     .12       0
Bank Sta=4990.4,4994.6
XS Rating Curve= 0 ,0
Exp/Cntr=0.3,0.1

Type RM Length L Ch R = 1 ,16032   ,199,199,199
BEGIN DESCRIPTION:
Jacobs Creek 35.0
END DESCRIPTION:
XS GIS Cut Line= 3
        2243525.       13856075.        2243575.       13856375.
      2243624.98     13856474.96
#Sta/Elev= 30
  4700.1  940.15    4733  938.11  4781.2  928.09  4811.6  923.18  4821.8  920.53
  4849.6  915.56  4902.9  902.24  4910.5  900.52  4915.5  900.16  4943.4   891.7
  4963.7  892.23  4971.3  891.12  4976.4   891.3    4984  888.87  4991.9  888.22
  4992.2  887.72  4996.2  888.22  5001.7  895.03    5007  895.03  5012.6  901.15
  5032.2  910.98    5035  913.58  5040.6  915.21  5057.3  924.79  5062.9  926.76
  5079.7   935.5  5102.1  941.15  5107.7  940.84  5113.2  943.15    5116  943.15
#Mann= 3 ,-1 , 0
  4700.1     .12       0  4991.9     .05       0  4996.2     .12       0
Bank Sta=4991.9,4996.2
XS Rating Curve= 0 ,0
Exp/Cntr=0.3,0.1

Type RM Length L Ch R = 1 ,15833   ,264,264,264
BEGIN DESCRIPTION:
A19504
END DESCRIPTION:
XS GIS Cut Line= 2
      2243349.53     13856129.54      2243403.39     13856646.54
#Sta/Elev= 30
  4753.2  936.74  4755.7  935.92  4778.8  933.45  4854.2  917.09  4859.3  917.23
  4869.3  915.53  4919.6  901.64  4939.7  898.82  4947.7  896.79  4952.8  897.11
  4969.8  890.15  4979.9   887.3  4987.8   886.7  4988.1   886.2  4992.1   886.7
    5010  887.53  5020.1  886.73  5030.2  887.57  5040.2  894.75  5046.3  901.44
  5051.3  901.66  5110.6   929.9  5120.6  934.26  5130.7  937.36  5139.8  939.21
  5144.8  939.13  5150.8  941.03    5181  944.81  5201.1  949.38    5273  958.31
#Mann= 3 ,-1 , 0
  4753.2     .12       0  4987.8     .05       0  4992.1     .12       0
Bank Sta=4987.8,4992.1
XS Rating Curve= 0 ,0
Exp/Cntr=0.3,0.1

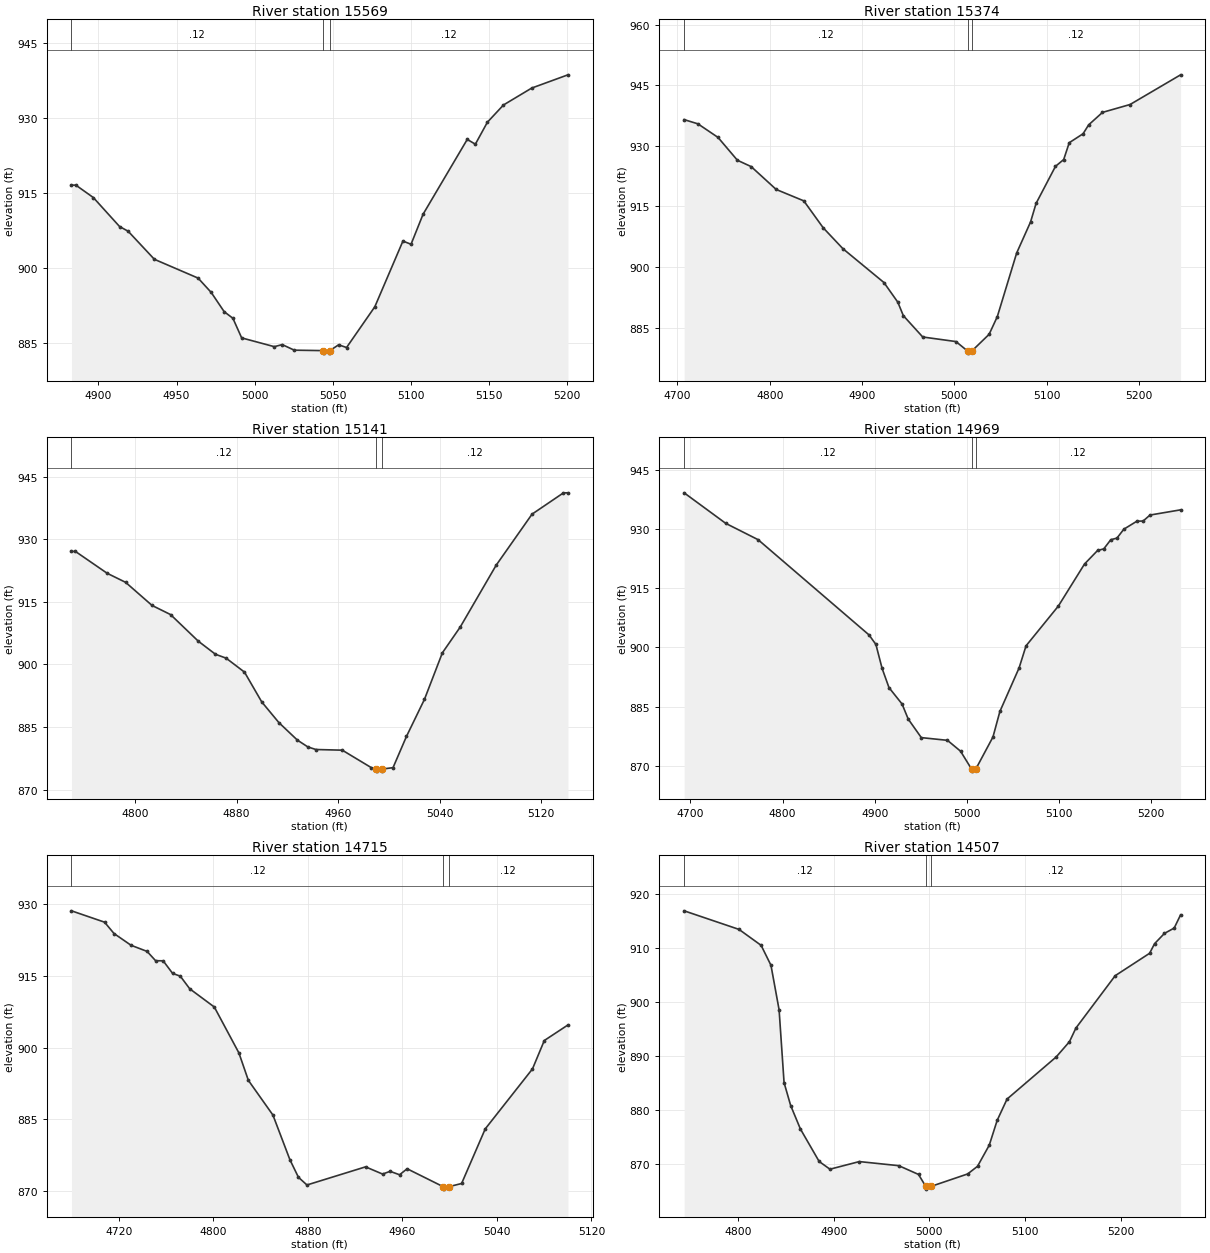
Type RM Length L Ch R = 1 ,15569   ,195,195,195
BEGIN DESCRIPTION:
Jacobs Creek 34.0
END DESCRIPTION:
XS GIS Cut Line= 3
      2243175.01     13856224.99        2243125.       13856325.
      2243175.01     13856525.03
#Sta/Elev= 30
  4882.7  916.55  4885.5  916.55  4896.7  914.07  4913.5  908.29    4919  907.35
  4935.8  901.75  4963.8     898  4972.2  895.14  4980.5   891.3  4986.1  889.98
  4991.7  886.07  5012.6  884.32  5017.7  884.73  5025.4  883.62  5043.9  883.53
  5044.2  883.03  5047.9  883.03  5048.2  883.53  5053.8  884.69  5058.9  884.15
    5077  892.28    5095  905.39  5100.2  904.75  5107.9  910.74  5136.2  925.67
  5141.4  924.72  5149.1   929.1  5159.4  932.54  5177.5  935.92  5200.7  938.56
#Mann= 3 ,-1 , 0
  4882.7     .12       0  5043.9     .05       0  5048.2     .12       0
Bank Sta=5043.9,5048.2
XS Rating Curve= 0 ,0
Exp/Cntr=0.3,0.1

Type RM Length L Ch R = 1 ,15374   ,233,233,233
BEGIN DESCRIPTION:
A19503
END DESCRIPTION:
XS GIS Cut Line= 2
       2243112.6     13856032.63      2242811.04     13856477.81
#Sta/Elev= 30
  4707.3  936.48  4722.2  935.44    4744  932.08    4765  926.43  4779.9  924.86
    4807  919.21  4836.9  916.39  4857.9  909.73  4879.3  904.55  4923.7  896.19
  4938.7  891.34  4944.7     888  4965.7  882.72  5001.7  881.59  5014.4  879.23
  5014.7  878.73  5018.8  879.23  5037.6  883.38  5046.5  887.76  5067.5  903.52
  5082.5  911.17  5088.5  915.77  5109.5  924.93  5118.4  926.61  5124.4  930.77
  5139.4  932.99  5145.4  935.18  5160.4  938.27  5190.3  940.22    5245  947.56
#Mann= 3 ,-1 , 0
  4707.3     .12       0  5014.4     .05       0  5018.8     .12       0
Bank Sta=5014.4,5018.8
XS Rating Curve= 0 ,0
Exp/Cntr=0.3,0.1

Type RM Length L Ch R = 1 ,15141   ,172,172,172
BEGIN DESCRIPTION:
Jacobs Creek 33.0
END DESCRIPTION:
XS GIS Cut Line= 3
      2242974.98     13855975.01        2242775.       13856125.
        2242675.       13856225.
#Sta/Elev= 30
  4749.8  927.05  4752.9  927.05  4777.9  921.82  4792.5  919.64  4813.3  914.11
  4827.9  911.92  4849.8  905.54  4863.3  902.41  4871.7  901.48  4886.2  898.13
  4899.8  890.99  4913.3  886.04  4927.9  881.84  4936.2   880.2  4942.5  879.59
  4963.3  879.43  4986.2  875.24  4990.2  874.91  4990.6  874.41  4994.4  874.41
  4994.7  874.91  5003.3  875.24  5013.9  882.73  5028.1  891.62  5042.2  902.75
  5056.3  908.94  5084.6  923.74  5112.9  935.98  5137.7  941.09  5141.2  941.09
#Mann= 3 ,-1 , 0
  4749.8     .12       0  4990.2     .05       0  4994.7     .12       0
Bank Sta=4990.2,4994.7
XS Rating Curve= 0 ,0
Exp/Cntr=0.3,0.1

Type RM Length L Ch R = 1 ,14969   ,254,254,254
BEGIN DESCRIPTION:
A19507
END DESCRIPTION:
XS GIS Cut Line= 2
      2242890.01     13855756.24      2242531.02      13856158.3
#Sta/Elev= 30
  4693.1  939.16  4738.3  931.42  4773.4  927.29  4893.8  903.17  4901.3  900.75
    4908   894.7  4915.5  889.82  4929.7  885.66  4936.4  881.84  4950.6  877.15
    4979  876.46  4993.2  873.71  5005.2  869.16  5005.5  868.66  5009.7  869.16
  5028.4  877.31  5035.9  883.77  5056.8  894.83  5064.3   900.4  5099.4  910.48
  5127.8  921.13    5142  924.56  5148.7  924.96  5156.3  927.28    5163  927.69
  5170.5  929.95  5184.7  931.98  5191.4  932.01  5198.9  933.53  5232.1  934.85
#Mann= 3 ,-1 , 0
  4693.1     .12       0  5005.2     .05       0  5009.7     .12       0
Bank Sta=5005.2,5009.7
XS Rating Curve= 0 ,0
Exp/Cntr=0.3,0.1

Type RM Length L Ch R = 1 ,14715   ,208,208,208
BEGIN DESCRIPTION:
Jacobs Creek 32.0
END DESCRIPTION:
XS GIS Cut Line= 3
        2242725.       13855675.        2242475.       13855875.
        2242475.     13855975.04
#Sta/Elev= 30
  4679.9  928.67  4707.9  926.29  4715.9  923.91  4730.3  921.45  4743.9  920.16
  4751.1  918.21  4757.5  918.19  4765.5  915.55    4772  914.97    4780  912.32
  4800.8   908.5  4821.6  898.88  4829.6  893.13  4850.4  885.85  4864.8  876.47
    4872   872.8  4879.2  871.19  4928.8  874.99  4943.2  873.48  4949.6  874.05
  4957.6  873.33    4964  874.59  4994.6  870.82  4994.9  870.32  4999.1  870.82
  5010.1   871.5  5030.1  882.95  5070.1  895.53  5080.1  901.48  5100.1  904.74
#Mann= 3 ,-1 , 0
  4679.9     .12       0  4994.6     .05       0  4999.1     .12       0
Bank Sta=4994.6,4999.1
XS Rating Curve= 0 ,0
Exp/Cntr=0.3,0.1

Type RM Length L Ch R = 1 ,14507   ,241,241,241
BEGIN DESCRIPTION:
A19502
END DESCRIPTION:
XS GIS Cut Line= 2
      2242225.91     13855576.74      2242347.62     13856081.48
#Sta/Elev= 30
  4743.6  916.91    4801  913.47  4824.1  910.52  4834.4  906.83  4842.9   898.6
  4848.1  885.11    4855  880.87  4865.2  876.52  4884.8  870.51  4896.1  869.08
  4926.8  870.49  4968.1  869.73  4988.7  868.11  4996.3  865.89  4996.7  865.39
  5001.7  865.89  5040.1   868.2  5050.4  869.61  5062.7  873.53    5071  878.13
  5081.3  882.06  5132.7  889.86  5146.6  892.69  5153.3   895.2  5194.4   904.9
  5230.4  909.05  5235.6  910.83  5245.9  912.73  5256.1  913.72  5262.8  916.17
#Mann= 3 ,-1 , 0
  4743.6     .12       0  4996.3     .05       0  5001.7     .12       0
Bank Sta=4996.3,5001.7
XS Rating Curve= 0 ,0
Exp/Cntr=0.3,0.1

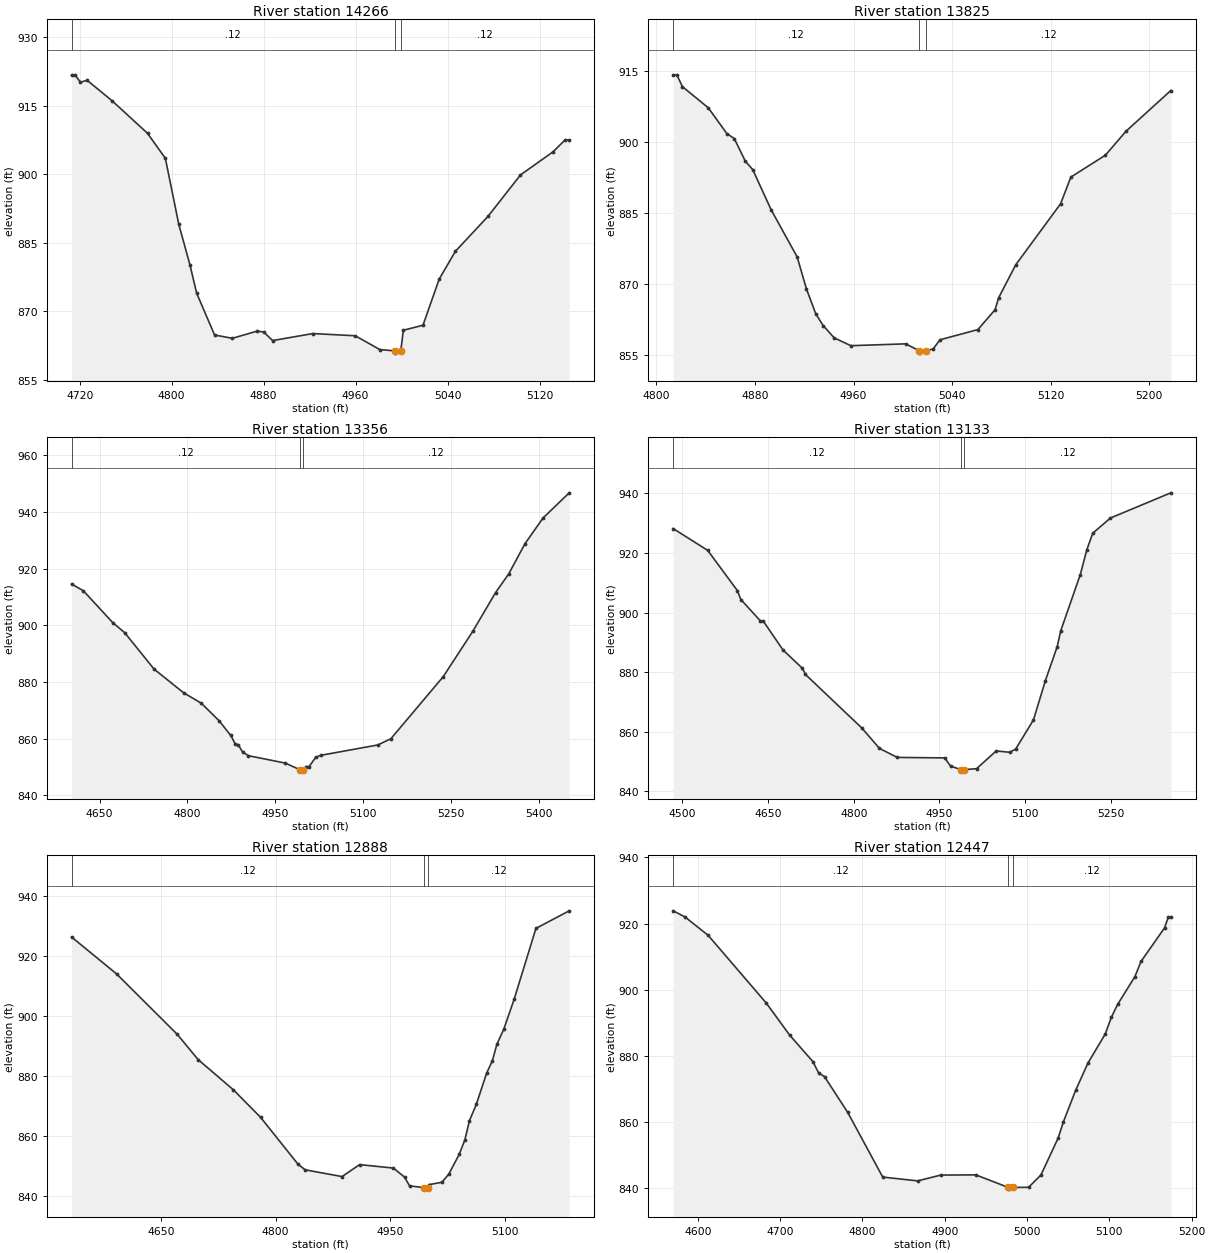
Type RM Length L Ch R = 1 ,14266   ,441,441,441
BEGIN DESCRIPTION:
Jacobs Creek 31.0
END DESCRIPTION:
XS GIS Cut Line= 3
      2241875.02     13855825.01        2242125.       13855975.
      2242224.97     13856074.97
#Sta/Elev= 30
  4712.9  921.76  4715.8  921.76  4720.6  920.15  4726.5  920.55  4747.9  916.14
    4779  908.96  4794.5  903.49  4806.2  889.03  4815.9  880.16  4821.7     874
  4837.3  864.83  4852.8   864.1  4874.2  865.67    4880   865.5  4887.8  863.61
  4922.8  865.14  4959.7  864.66  4981.1  861.63  4993.9  861.36  4994.3  860.86
  4999.3  861.36  5001.5  865.87  5018.6  866.96  5032.7  877.05  5046.8  883.14
  5075.1  890.77  5103.4  899.85  5131.7  904.91  5142.3  907.53  5145.8  907.53
#Mann= 3 ,-1 , 0
  4712.9     .12       0  4993.9     .05       0  4999.3     .12       0
Bank Sta=4993.9,4999.3
XS Rating Curve= 0 ,0
Exp/Cntr=0.3,0.1

Type RM Length L Ch R = 1 ,13825   ,469,469,469
BEGIN DESCRIPTION:
Jacobs Creek 30.0
END DESCRIPTION:
XS GIS Cut Line= 3
      2241675.01     13856175.01        2241825.       13856275.
      2242025.03     13856375.01
#Sta/Elev= 30
  4813.6  914.24  4816.6  914.24  4821.1  911.75  4842.1  907.28  4857.2  901.83
  4863.2  900.79  4872.2     896  4878.2  894.23  4893.2  885.71  4914.2  875.82
  4921.8  869.03  4929.3  863.81  4935.3  861.32  4944.3  858.71  4957.8  857.06
  5002.2  857.45  5013.5  855.99  5013.9  855.49    5019  855.99  5024.6  856.37
  5030.2  858.31  5060.9  860.46  5074.9  864.66  5077.7  867.15  5091.7  874.16
    5128     887  5136.4  892.66  5164.4  897.27  5181.1  902.32  5217.5  910.93
#Mann= 3 ,-1 , 0
  4813.6     .12       0  5013.5     .05       0    5019     .12       0
Bank Sta=5013.5,5019
XS Rating Curve= 0 ,0
Exp/Cntr=0.3,0.1

Type RM Length L Ch R = 1 ,13356   ,223,223,223
BEGIN DESCRIPTION:
Jacobs Creek 29.0
END DESCRIPTION:
XS GIS Cut Line= 3
      2241574.99     13856225.05        2241525.       13856625.
      2241925.02     13856825.01
#Sta/Elev= 30
    4602  914.57  4622.1  912.21  4672.5  900.93  4692.7  897.43    4743  884.57
  4793.4  876.22  4823.7  872.54  4853.9   866.4  4874.1  861.16  4881.6  858.22
  4886.7   857.9  4894.2  855.36  4904.3  854.03  4967.3  851.42  4992.2  849.09
  4992.6  848.59  4997.8  849.09  5002.5  850.19  5007.9  850.19    5019   853.4
  5027.4  854.15  5125.3  857.82  5147.6  860.01  5237.1  881.92  5287.4  897.84
  5326.5  911.56  5348.9  918.12  5376.8  928.81  5407.6  937.85  5452.3  946.73
#Mann= 3 ,-1 , 0
    4602     .12       0  4992.2     .05       0  4997.8     .12       0
Bank Sta=4992.2,4997.8
XS Rating Curve= 0 ,0
Exp/Cntr=0.3,0.1

Type RM Length L Ch R = 1 ,13133   ,245,245,245
BEGIN DESCRIPTION:
A19501
END DESCRIPTION:
XS GIS Cut Line= 2
      2241472.04     13856136.72      2241238.68     13856976.81
#Sta/Elev= 30
  4483.7  928.19  4544.2  920.87  4596.1   907.4  4602.3  904.37  4636.6   897.2
  4641.8  897.08    4676  887.47  4710.2  881.28  4715.5  879.22    4814  861.31
  4845.2  854.41  4876.3  851.39  4959.3  851.23  4969.7   848.5  4987.7  847.29
  4988.1  846.79  4993.3  847.29  5015.4  847.62  5049.7  853.57  5073.5  853.11
  5083.9  854.23    5115     864  5135.8  877.14  5156.5  888.53  5162.8  893.92
    5197  912.74  5208.4  921.02  5218.8  926.63  5249.9  931.73  5355.6  940.18
#Mann= 3 ,-1 , 0
  4483.7     .12       0  4987.7     .05       0  4993.3     .12       0
Bank Sta=4987.7,4993.3
XS Rating Curve= 0 ,0
Exp/Cntr=0.3,0.1

Type RM Length L Ch R = 1 ,12888   ,441,441,441
BEGIN DESCRIPTION:
Jacobs Creek 28.0
END DESCRIPTION:
XS GIS Cut Line= 3
        2241375.       13856125.        2241125.       13856525.
      2241024.99     13856675.02
#Sta/Elev= 30
  4532.7   926.3  4591.7  914.01  4671.3  893.87  4698.4  885.52  4744.4   875.5
  4780.3  866.29  4829.3   850.7  4838.7   848.8  4887.1  846.55  4910.1  850.53
  4954.3  849.38    4969  846.38  4975.5  843.47  4993.9  842.87  4994.4  842.37
  4999.5  842.87  5001.5  843.89  5017.9  844.65  5026.9  847.36  5040.5   853.9
    5048  858.77    5054  865.18    5063  870.57  5076.5  880.97    5084  885.08
    5090  890.62    5099  895.62  5112.6  905.61  5141.1  929.16  5184.7  935.01
#Mann= 3 ,-1 , 0
  4532.7     .12       0  4993.9     .05       0  4999.5     .12       0
Bank Sta=4993.9,4999.5
XS Rating Curve= 0 ,0
Exp/Cntr=0.3,0.1

Type RM Length L Ch R = 1 ,12447   ,461,461,461
BEGIN DESCRIPTION:
Jacobs Creek 27.0
END DESCRIPTION:
XS GIS Cut Line= 3
      2241125.01     13855924.99        2240825.       13856225.
      2240724.98     13856375.04
#Sta/Elev= 30
    4570  923.84  4584.2  922.02  4612.4  916.47  4683.2  895.97  4711.4  886.35
  4739.7  878.32  4746.8  874.86  4753.9  873.76  4782.1  862.96  4824.6  843.44
    4867  842.29  4895.3  844.05  4937.7   844.1  4977.3   840.3  4977.8   839.8
    4983   840.3  5001.8  840.35  5016.8  844.07  5037.8  855.25  5043.9  859.99
  5058.9  869.59  5073.9  877.86  5094.9  886.63  5102.4  891.71    5110  895.59
    5131  903.99  5138.5   908.6    5167  918.69  5171.6  921.99  5174.6  921.99
#Mann= 3 ,-1 , 0
    4570     .12       0  4977.3     .05       0    4983     .12       0
Bank Sta=4977.3,4983
XS Rating Curve= 0 ,0
Exp/Cntr=0.3,0.1

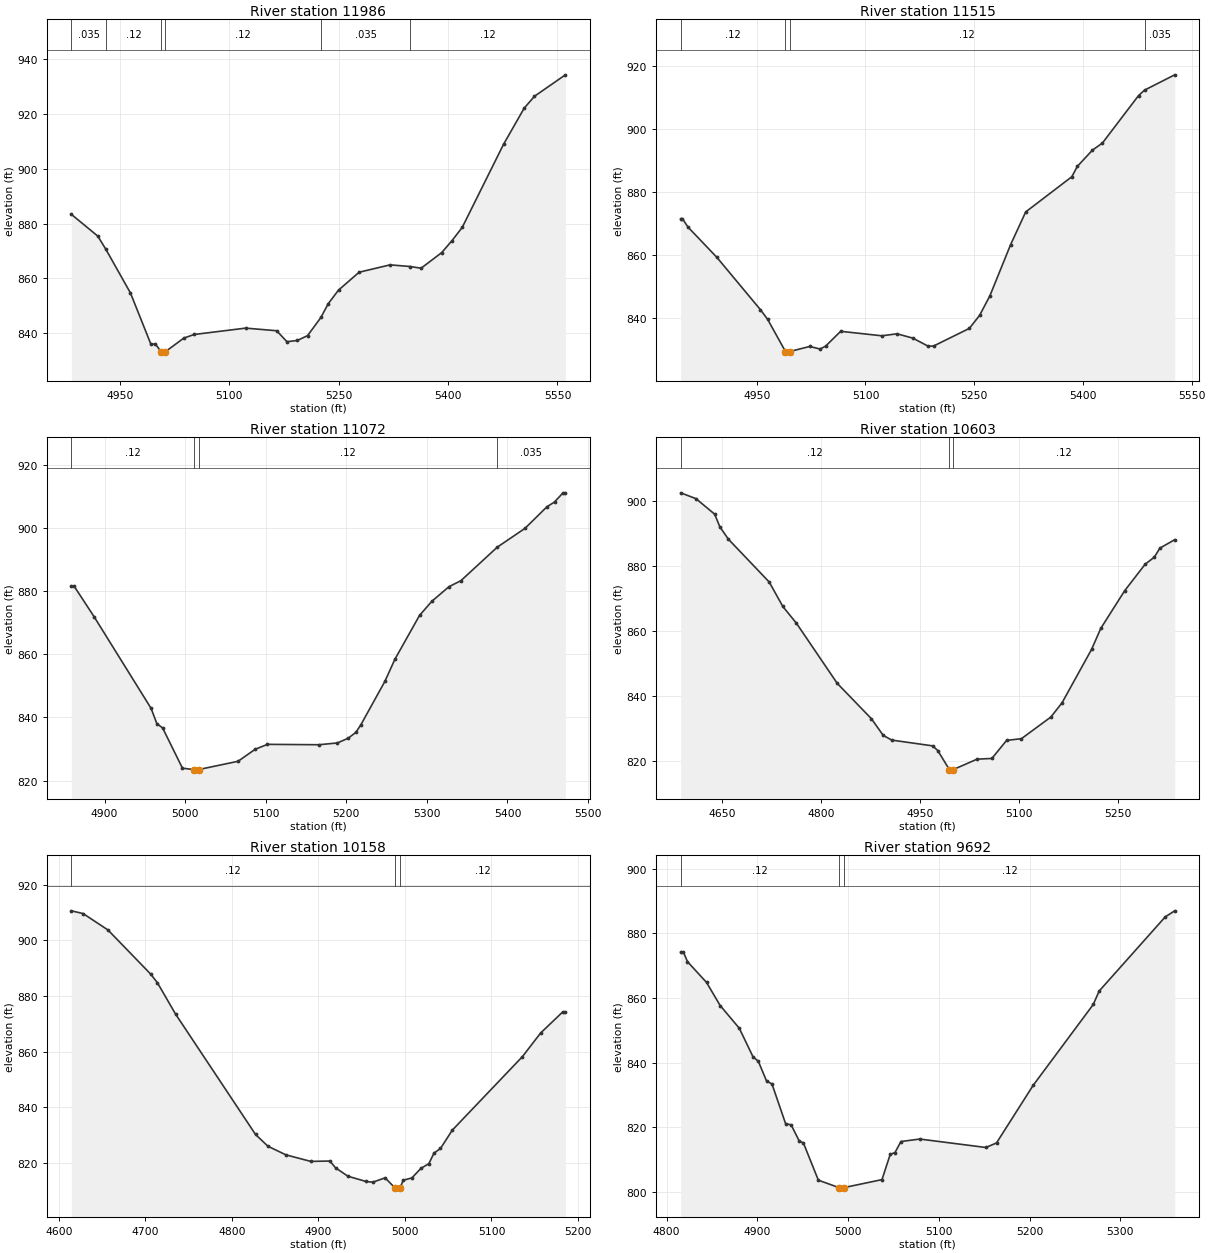
Type RM Length L Ch R = 1 ,11986   ,471,471,471
BEGIN DESCRIPTION:
Jacobs Creek 26.0
END DESCRIPTION:
XS GIS Cut Line= 3
      2240824.96     13855775.02        2240725.       13855825.
      2240325.03     13856224.97
#Sta/Elev= 30
  4883.5  883.39  4919.8  875.42  4930.8  870.61  4964.5  854.67  4992.5  835.97
  4998.8  835.97  5006.6  833.17    5007  832.67  5012.3  833.17  5037.7  838.17
  5051.8  839.48  5122.5  841.81    5165  840.85  5179.1  836.85  5193.3  837.29
  5207.4  839.07  5225.7  845.72  5235.7  850.73  5249.8   855.7  5278.1  862.24
  5320.5  864.93  5348.4  864.32    5363   863.7  5391.2  869.38  5405.4  873.77
  5419.5  878.65  5476.1  908.99  5504.4  922.19  5518.5  926.54  5560.9  934.38
#Mann= 6 ,-1 , 0
  4883.5    .035       0  4930.8     .12       0  5006.6     .05       0
  5012.3     .12       0  5225.7    .035       0  5348.4     .12       0
Bank Sta=5006.6,5012.3
XS Rating Curve= 0 ,0
Exp/Cntr=0.3,0.1

Type RM Length L Ch R = 1 ,11515   ,443,443,443
BEGIN DESCRIPTION:
Jacobs Creek 25.0
END DESCRIPTION:
XS GIS Cut Line= 3
      2240574.96       13855475.        2240425.       13855475.
      2240024.97     13855825.02
#Sta/Elev= 30
  4845.1  871.49  4847.6  871.49  4855.1  868.87  4895.1  859.24  4955.1  842.69
  4965.1  839.61  4989.7  829.42  4990.2  828.92  4995.4  829.42  5023.1  831.03
  5037.3  830.23  5044.9   831.1  5065.8  835.83  5122.7  834.41  5143.6  835.04
  5165.4  833.67  5186.3  831.14  5193.9  831.16  5243.3  836.75  5257.5  840.88
  5271.7  847.09  5300.2  863.25  5321.1  873.65  5384.7  884.79  5392.3  888.07
  5413.1  893.21  5426.9  895.46  5476.7  910.49    5485  912.22  5526.6  917.07
#Mann= 4 ,-1 , 0
  4845.1     .12       0  4989.7     .05       0  4995.4     .12       0
    5485    .035       0
Bank Sta=4989.7,4995.4
XS Rating Curve= 0 ,0
Exp/Cntr=0.3,0.1

Type RM Length L Ch R = 1 ,11072   ,469,469,469
BEGIN DESCRIPTION:
Jacobs Creek 24.0
END DESCRIPTION:
XS GIS Cut Line= 3
      2240175.01     13855124.99        2240075.       13855225.
      2239825.02     13855624.97
#Sta/Elev= 30
  4858.8  881.49  4862.4  881.49  4887.1  871.86  4957.8  842.84  4964.9     838
    4972  836.69  4996.7  823.91  5010.9  823.49  5011.4  822.99  5016.8  823.49
  5065.7  826.11  5086.9  829.91  5102.2  831.47  5165.9  831.35  5188.9  831.91
  5202.5  833.43  5211.9  835.28  5217.8  837.54  5247.9  851.42  5260.3  858.41
  5290.9  872.31  5306.3  876.81  5327.5  881.42  5342.2   883.3  5387.4  893.93
  5421.8  899.88  5448.9  906.69  5458.4  908.23    5469  911.13  5471.9  911.13
#Mann= 4 ,-1 , 0
  4858.8     .12       0  5010.9     .05       0  5016.8     .12       0
  5387.4    .035       0
Bank Sta=5010.9,5016.8
XS Rating Curve= 0 ,0
Exp/Cntr=0.3,0.1

Type RM Length L Ch R = 1 ,10603   ,445,445,445
BEGIN DESCRIPTION:
Jacobs Creek 23.0
END DESCRIPTION:
XS GIS Cut Line= 3
      2240124.96     13854825.01        2239725.       13854925.
      2239424.99     13855075.01
#Sta/Elev= 30
  4587.7  902.61  4610.9  900.81  4639.2  896.02  4646.9  892.17  4659.8  888.34
  4721.7  875.11  4742.3  867.57  4762.9   862.4  4824.7  843.85  4876.3  832.97
  4894.3  827.81  4907.2  826.36  4969.1  824.58  4976.8  823.14  4994.3  817.29
  4994.8  816.79  5000.5  817.29  5036.3  820.48  5058.7   820.7    5081  826.27
  5103.4  826.79  5148.1  833.49  5164.9  837.86  5209.6  854.33  5223.6  860.83
  5259.9  872.48  5290.7  880.59  5304.6  882.78    5313  885.56  5335.4  888.15
#Mann= 3 ,-1 , 0
  4587.7     .12       0  4994.3     .05       0  5000.5     .12       0
Bank Sta=4994.3,5000.5
XS Rating Curve= 0 ,0
Exp/Cntr=0.3,0.1

Type RM Length L Ch R = 1 ,10158   ,466,466,466
BEGIN DESCRIPTION:
Jacobs Creek 22.0
END DESCRIPTION:
XS GIS Cut Line= 3
      2239724.98     13854275.03        2239475.       13854575.
      2239374.97     13854725.04
#Sta/Elev= 30
  4614.6  910.61  4628.2  909.62  4656.9  903.73  4706.3  887.87  4714.1  884.74
    4735  873.52  4827.4  830.28  4841.7  826.06  4862.5  822.96  4891.2  820.61
  4913.3  820.74  4919.8  818.32  4934.1  815.29    4955   813.4  4962.8  813.14
  4977.1   814.7  4988.3  811.15  4988.8  810.65  4994.6  811.15  4997.9  813.82
  5008.1  814.69  5018.6  818.14  5027.6  819.78  5033.6  823.59  5041.1  825.26
  5054.7  831.82  5135.8  858.26  5156.8  866.73  5182.3  874.29  5185.4  874.29
#Mann= 3 ,-1 , 0
  4614.6     .12       0  4988.3     .05       0  4994.6     .12       0
Bank Sta=4988.3,4994.6
XS Rating Curve= 0 ,0
Exp/Cntr=0.3,0.1

Type RM Length L Ch R = 1 ,9692    ,481,481,481
BEGIN DESCRIPTION:
Jacobs Creek 21.0
END DESCRIPTION:
XS GIS Cut Line= 3
      2239274.98     13854125.02        2239175.       13854275.
      2239074.99     13854625.04
#Sta/Elev= 30
  4815.6  874.18  4818.6  874.18  4823.1  871.22  4844.1  864.79  4859.1  857.65
  4880.2  850.61  4895.2  841.85  4901.2  840.37  4910.2  834.31  4916.2  833.38
  4931.2  821.11  4937.3  820.73  4946.3  815.71  4950.8  815.16  4967.3  803.62
  4989.7  801.35  4990.2  800.85    4996  801.35  5037.4  803.79  5046.5  811.61
  5051.7  812.16  5058.3  815.58  5079.1  816.34  5151.9  813.73  5163.6  815.14
  5203.9  832.93  5270.2  857.98  5276.7  862.13  5349.5  885.07  5359.9  886.94
#Mann= 3 ,-1 , 0
  4815.6     .12       0  4989.7     .05       0    4996     .12       0
Bank Sta=4989.7,4996
XS Rating Curve= 0 ,0
Exp/Cntr=0.3,0.1

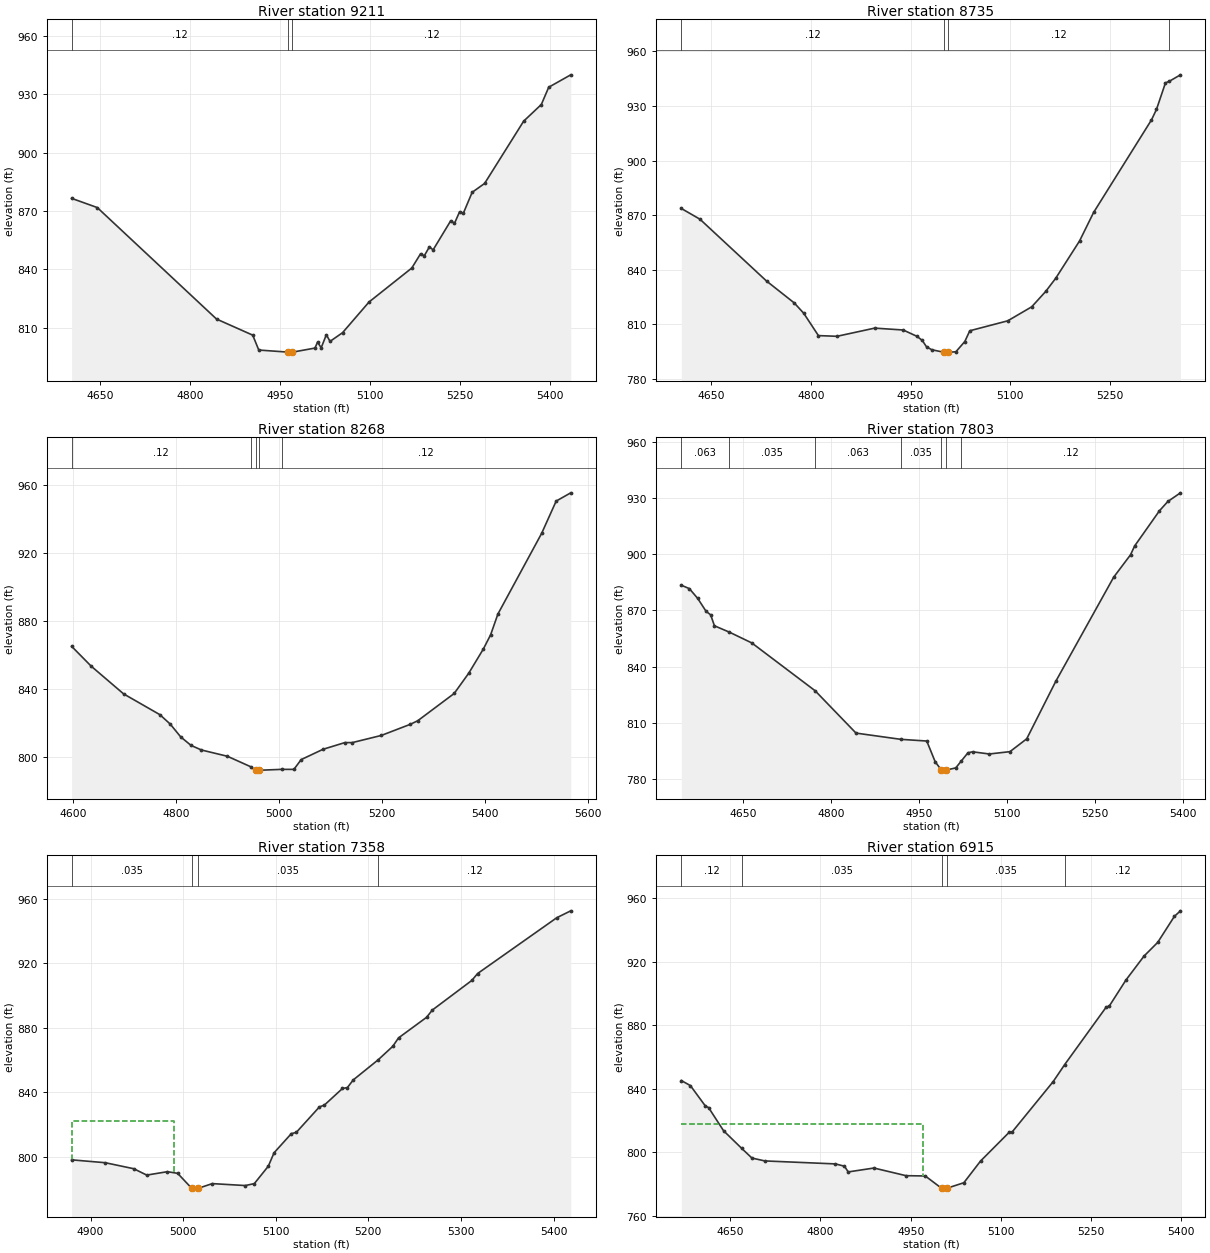
Type RM Length L Ch R = 1 ,9211    ,476,476,476
BEGIN DESCRIPTION:
Jacobs Creek 20.0
END DESCRIPTION:
XS GIS Cut Line= 3
        2238775.       13853975.        2238725.       13854375.
      2238475.01     13854724.98
#Sta/Elev= 30
  4601.8  876.44  4644.6   871.7  4843.7  814.37  4904.1   806.1  4914.2  798.44
  4963.8  797.35  4964.3  796.85  4970.4  797.35    5008  799.45  5012.3  802.48
  5018.4  799.61    5027  806.29  5033.2  802.89  5054.1  807.37  5098.3  823.15
  5169.6  840.59  5184.3  847.94  5190.5  846.91  5199.1  851.53  5205.2  849.93
  5234.7  864.94  5240.9  863.57  5249.5  869.57  5255.6   868.7  5270.4  879.53
  5291.2   884.1  5356.4  916.13  5385.9  924.69  5398.2  933.57    5435  939.95
#Mann= 3 ,-1 , 0
  4601.8     .12       0  4963.8     .05       0  4970.4     .12       0
Bank Sta=4963.8,4970.4
XS Rating Curve= 0 ,0
Exp/Cntr=0.3,0.1

Type RM Length L Ch R = 1 ,8735    ,467,467,467
BEGIN DESCRIPTION:
Jacobs Creek 19.0
END DESCRIPTION:
XS GIS Cut Line= 3
      2238575.01     13853874.99        2238325.       13854175.
      2238124.99     13854475.02
#Sta/Elev= 30
    4605  873.67    4633  867.79  4733.2  833.84  4774.9  821.82  4789.2  816.14
  4811.3  803.87  4839.3  803.49  4895.9  807.98  4938.9  806.95  4959.7  803.45
  4967.5  801.24    4974   797.7  4981.9  796.11  4999.7  794.75  5000.2  794.25
  5006.3  794.75  5018.1  794.97  5031.6  800.62  5039.1  806.53  5096.2  811.99
  5132.2  819.66  5153.3  828.11  5168.3  835.31  5204.3  855.86  5225.4  871.48
  5312.5  922.31    5320  928.05  5333.5   942.6  5339.5  943.55  5356.1  947.05
#Mann= 4 ,-1 , 0
    4605     .12       0  4999.7     .05       0  5006.3     .12       0
  5339.5     .07       0
Bank Sta=4999.7,5006.3
XS Rating Curve= 0 ,0
Exp/Cntr=0.3,0.1

Type RM Length L Ch R = 1 ,8268    ,465,465,465
BEGIN DESCRIPTION:
Jacobs Creek 18.0
END DESCRIPTION:
XS GIS Cut Line= 3
      2238475.02       13853775.        2238075.       13853825.
      2237675.01     13854224.99
#Sta/Elev= 30
  4596.9  864.89  4634.7  853.26  4697.7  836.93  4768.2  824.68  4788.4  819.11
  4808.6  811.61  4828.7   806.6  4848.9   803.9  4899.3  800.21  4944.3  794.08
  4953.8  791.97  4954.3  791.47  4960.5  791.97  5004.5  792.51  5028.3   792.5
  5042.5  798.26  5084.9  804.32  5127.3  808.26  5141.5  808.24    5198  812.46
  5254.6  819.05  5268.7  821.11  5339.4  837.14  5367.7  849.08    5396  863.28
  5410.2  871.69  5424.3  883.88  5509.1  931.28  5537.4  950.33  5565.7  955.18
#Mann= 5 ,-1 , 0
  4596.9     .12       0  4944.3    .035       0  4953.8    .035       0
  4960.5    .035       0  5004.5     .12       0
Bank Sta=4953.8,4960.5
XS Rating Curve= 0 ,0
Exp/Cntr=0.3,0.1

Type RM Length L Ch R = 1 ,7803    ,445,445,445
BEGIN DESCRIPTION:
Jacobs Creek 17.0
END DESCRIPTION:
XS GIS Cut Line= 3
      2238125.02     13853224.99        2237775.       13853525.
      2237475.01     13853774.99
#Sta/Elev= 30
  4544.3  883.47    4558  881.65  4572.3  876.42  4586.6  869.52  4594.3   867.7
  4600.8  861.84  4626.4  858.44  4664.5  852.72  4772.5  827.24  4842.3  804.66
  4918.6  801.34    4963  800.43  4977.3  789.43  4988.1  784.89  4988.6  784.39
    4995  784.89  5012.5  786.11  5021.6  789.67  5033.3  794.17  5041.1  794.69
  5069.7  793.53  5104.9  794.77  5133.5  801.59    5183   832.2  5281.9  887.76
  5310.6  899.67  5317.7  904.42    5360  923.16  5374.3   928.1  5395.8  932.71
#Mann= 7 ,-1 , 0
  4544.3    .063       0  4626.4    .035       0  4772.5    .063       0
  4918.6    .035       0  4988.1    .035       0    4995    .035       0
  5021.6     .12       0
Bank Sta=4988.1,4995
XS Rating Curve= 0 ,0
Exp/Cntr=0.3,0.1

Type RM Length L Ch R = 1 ,7358    ,443,443,443
BEGIN DESCRIPTION:
Jacobs Creek 16.0
END DESCRIPTION:
XS GIS Cut Line= 3
      2237475.01     13853224.99        2237425.       13853325.
      2237275.01     13853724.98
#Sta/Elev= 30
  4879.6  798.22  4915.9  796.45  4946.7  792.72  4960.7  788.77    4983  790.88
  4994.1  789.86  5009.3  780.57  5009.8  780.07  5016.3  780.57  5031.5  783.49
  5067.1  782.29  5076.9  783.49    5092  794.29  5098.2   802.6  5116.9  814.49
  5122.2  815.23  5147.2  831.06  5152.5  832.15  5172.1  842.48  5177.4  843.03
  5183.7  847.76  5210.5  860.18  5226.4   868.6  5232.6  873.82  5262.9  886.59
  5269.1  891.08  5311.8  909.47    5318  913.73  5403.5  948.33  5418.6  952.61
#Mann= 4 ,-1 , 0
  4879.6    .035       0  5009.3    .035       0  5016.3    .035       0
  5210.5     .12       0
#XS Ineff= 2 , 0
       0  4989.8  822.44               0
Permanent Ineff=
       F       F
Bank Sta=5009.3,5016.3
XS Rating Curve= 0 ,0
Exp/Cntr=0.3,0.1

Type RM Length L Ch R = 1 ,6915    ,449,449,449
BEGIN DESCRIPTION:
Jacobs Creek 15.0
END DESCRIPTION:
XS GIS Cut Line= 3
      2237174.99     13852875.04        2237025.       13853275.
        2236975.     13853675.03
#Sta/Elev= 30
  4568.5  845.19  4583.6  842.01  4608.5  829.19  4613.8  828.21  4638.8  813.63
  4668.7  802.65  4685.9  796.49  4707.3  794.68  4824.8   792.8  4839.9  791.35
  4846.1  787.76  4888.9  790.21  4942.3   785.4  4974.3  785.22  5001.6  777.45
  5002.1  776.95  5009.8  777.45  5038.5  780.97  5066.2  794.58  5114.1  812.75
  5119.1  813.01  5187.1  844.54  5206.3  855.27  5275.3  891.36  5280.4     892
  5308.1  908.36  5338.3  923.46    5361  932.04  5388.7  948.38  5398.8  951.86
#Mann= 5 ,-1 , 0
  4568.5     .12       0  4668.7    .035       0  5001.6    .035       0
  5009.8    .035       0  5206.3     .12       0
#XS Ineff= 2 , 0
       0  4970.9  817.94               0
Permanent Ineff=
       F       F
Bank Sta=5001.6,5009.8
XS Rating Curve= 0 ,0
Exp/Cntr=0.3,0.1