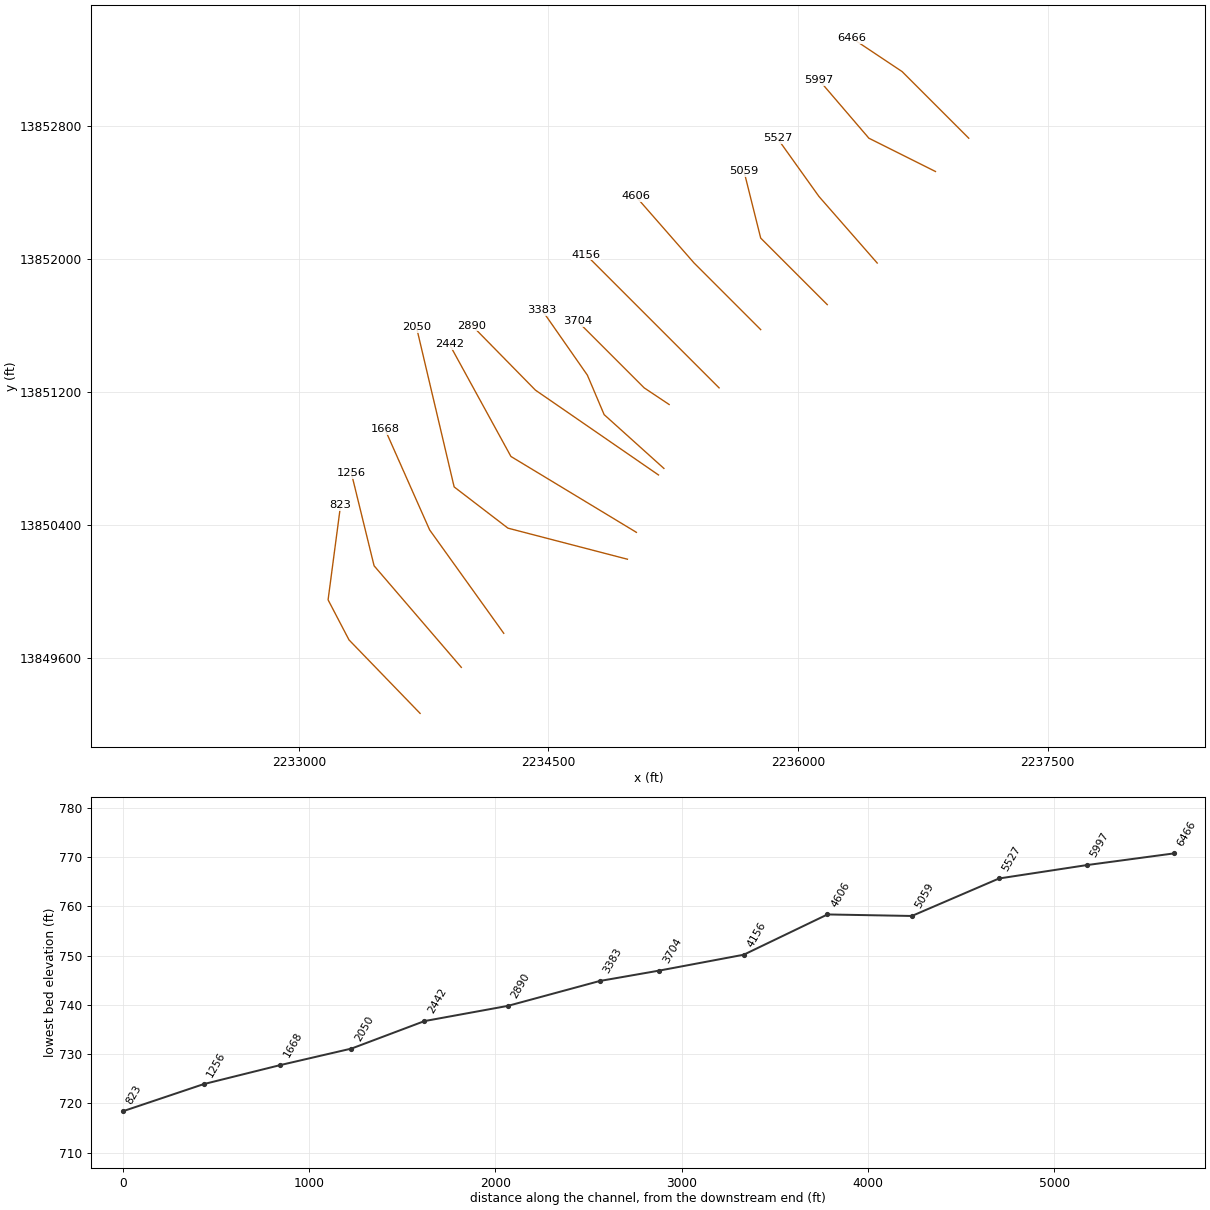
HEC-RAS study Jacobs Creek.prj: Jacobs Creek Base Level Engineering

--- Jacobs Creek.g01 (geometry) --- (continued)

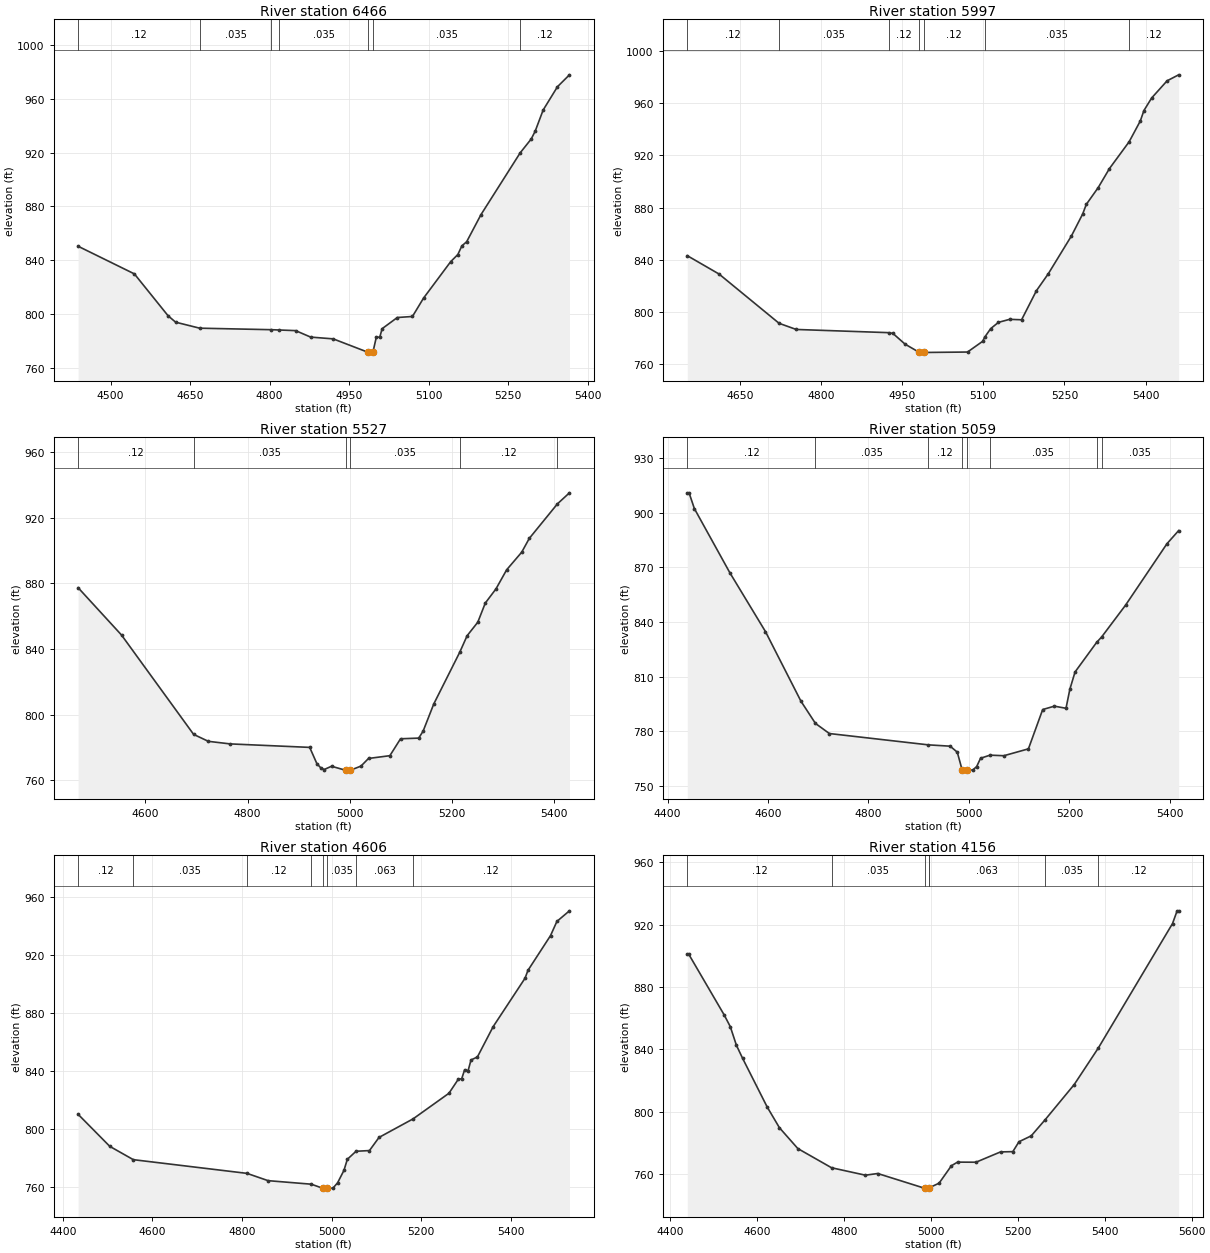
Type RM Length L Ch R = 1 ,6466    ,469,469,469
BEGIN DESCRIPTION:
Jacobs Creek 14.0
END DESCRIPTION:
XS GIS Cut Line= 3
      2237025.02     13852724.98        2236625.       13853125.
      2236324.97     13853325.02
#Sta/Elev= 30
  4438.9  850.31    4545  829.73  4608.6  798.52  4622.8  793.78  4668.1  789.32
  4803.3  788.19    4818  787.97    4849   787.5  4877.3  782.68  4919.8  781.37
  4986.3  771.25  4986.8  770.75  4994.6  771.25  5001.1  782.63  5007.6  782.63
  5012.1  788.96  5040.7  797.26  5069.2  798.03  5090.2  811.74  5141.3  838.83
  5154.8  844.14  5162.4   850.6  5171.4  853.64  5198.4  873.83  5272.4  919.88
  5293.1  930.14  5300.6  935.93  5315.6  951.69  5342.6  969.04  5365.2  977.91
#Mann= 7 ,-1 , 0
  4438.9     .12       0  4668.1    .035       0  4803.3     .12       0
    4818    .035       0  4986.3    .035       0  4994.6    .035       0
  5272.4     .12       0
Bank Sta=4986.3,4994.6
XS Rating Curve= 0 ,0
Exp/Cntr=0.3,0.1

Type RM Length L Ch R = 1 ,5997    ,470,470,470
BEGIN DESCRIPTION:
Jacobs Creek 13.0
END DESCRIPTION:
XS GIS Cut Line= 3
      2236825.01     13852524.99        2236425.       13852725.
        2236125.       13853075.
#Sta/Elev= 30
  4552.8  843.12  4611.5  829.04  4722.5  791.24  4754.1  786.53  4924.7  784.08
  4932.9  783.48  4955.3  775.27  4981.9  768.87  4982.4  768.37  4990.3  768.87
  5070.8  769.21  5098.8  777.45  5102.5  780.61  5113.6  787.17  5127.9  791.98
  5148.7   794.3  5170.7  793.95  5198.1  816.24  5220.1  829.27  5262.9  858.31
  5283.7  875.19  5290.3  882.46  5312.3  895.34  5333.1  909.95  5369.5  930.51
  5390.2  946.51  5396.8  954.44  5411.1   964.1  5439.6  977.25    5461  981.86
#Mann= 7 ,-1 , 0
  4552.8     .12       0  4722.5    .035       0  4924.7     .12       0
  4981.9     .05       0  4990.3     .12       0  5102.5    .035       0
  5369.5     .12       0
Bank Sta=4981.9,4990.3
XS Rating Curve= 0 ,0
Exp/Cntr=0.3,0.1

Type RM Length L Ch R = 1 ,5527    ,468,468,468
BEGIN DESCRIPTION:
Jacobs Creek 12.0
END DESCRIPTION:
XS GIS Cut Line= 3
      2236475.03     13851974.96        2236125.       13852375.
      2235874.98     13852725.02
#Sta/Elev= 30
  4468.2  877.31  4553.2  848.48  4694.3  788.02  4723.1   783.8  4765.8  782.23
  4921.5  780.11  4935.7  770.11  4943.3  767.63  4949.9  766.65  4964.2  768.62
  4992.1  766.16  4992.6  765.66  5000.7  766.16  5021.9  768.73  5036.6  773.37
  5078.4  775.06  5099.3  785.35  5134.9  785.76  5143.5  790.02  5164.4  806.58
  5215.3  838.09  5229.6  848.07  5250.5   856.3  5265.2  867.97  5286.1  876.58
    5307   888.2  5336.5  898.93  5351.2  907.27  5406.5  928.37  5429.9  935.05
#Mann= 6 ,-1 , 0
  4468.2     .12       0  4694.3    .035       0  4992.1    .035       0
  5000.7    .035       0  5215.3     .12       0  5406.5    .035       0
Bank Sta=4992.1,5000.7
XS Rating Curve= 0 ,0
Exp/Cntr=0.3,0.1

Type RM Length L Ch R = 1 ,5059    ,453,453,453
BEGIN DESCRIPTION:
Jacobs Creek 11.0
END DESCRIPTION:
XS GIS Cut Line= 3
      2236174.97     13851725.03        2235775.       13852125.
      2235674.99     13852525.04
#Sta/Elev= 30
  4439.4  910.86  4442.9  910.86  4453.5  902.19  4524.2  866.93  4594.9  834.71
  4665.6  796.45  4694.5  784.24  4722.2  778.69  4918.9  772.48  4962.6  771.75
  4976.8  768.45  4986.6  758.55  4987.1  758.05  4995.2  758.55  5007.6  758.67
  5015.4  760.55  5023.1  765.11    5042  766.82  5069.5  766.51  5118.4  770.28
  5146.8  791.87    5170  793.72  5193.2  792.56  5200.9  803.03  5211.2  812.49
  5254.1  828.71  5264.3  831.77  5311.7  849.17  5394.2  882.93  5417.4  890.13
#Mann= 8 ,-1 , 0
  4439.4     .12       0  4694.5    .035       0  4918.9     .12       0
  4986.6     .05       0  4995.2     .12       0    5042    .035       0
  5254.1     .12       0  5264.3    .035       0
Bank Sta=4986.6,4995.2
XS Rating Curve= 0 ,0
Exp/Cntr=0.3,0.1

Type RM Length L Ch R = 1 ,4606    ,450,450,450
BEGIN DESCRIPTION:
Jacobs Creek 10.0
END DESCRIPTION:
XS GIS Cut Line= 3
      2235774.98     13851575.02        2235375.       13851975.
      2235024.98     13852375.03
#Sta/Elev= 30
  4434.1  809.95  4504.8  787.86  4557.4  778.67  4811.3  769.22  4858.3   764.2
  4954.9  761.76  4981.3  758.86  4981.8  758.36    4990  758.86  5003.1  759.03
  5013.5  762.69  5027.8  771.33  5035.3  778.93  5054.8  784.47  5084.7  784.94
  5106.1  794.02  5182.2  806.81  5262.2  824.45  5283.1  834.12  5290.7  834.49
  5297.3   840.7  5304.9  839.92  5311.5   847.4  5325.8   849.5  5360.9  870.36
  5432.1  903.76  5438.7  909.21    5489  933.13  5503.3  942.95  5531.3  950.24
#Mann= 8 ,-1 , 0
  4434.1     .12       0  4557.4    .035       0  4811.3     .12       0
  4954.9    .035       0  4981.3    .035       0    4990    .035       0
  5054.8    .063       0  5182.2     .12       0
Bank Sta=4981.3,4990
XS Rating Curve= 0 ,0
Exp/Cntr=0.3,0.1

Type RM Length L Ch R = 1 ,4156    ,452,452,452
BEGIN DESCRIPTION:
Jacobs Creek 9.0
END DESCRIPTION:
XS GIS Cut Line= 3
      2235524.98     13851225.02        2235125.       13851625.
      2234725.03     13852024.97
#Sta/Elev= 30
  4438.8  900.93  4442.3  900.93  4523.6  862.09  4537.8  854.51  4551.9  842.53
  4566.1  834.19  4622.6  802.98  4650.9  789.62  4693.3  776.23    4771   763.9
  4848.9  759.13  4877.2  760.21  4985.9  750.68  4986.4  750.18  4994.7  750.68
  4996.3   751.1  5018.6  754.02  5046.9  765.21    5061  767.52  5103.5  767.46
    5160  774.08  5188.3  774.25  5202.5  780.61  5230.7   784.4    5263  794.83
  5329.7  817.35  5385.3  840.85    5556   920.7  5566.6  928.88  5570.1  928.88
#Mann= 7 ,-1 , 0
  4438.8     .12       0    4771    .035       0  4985.9    .063       0
  4994.7    .035       0  4996.3    .063       0    5263    .035       0
  5385.3     .12       0
Bank Sta=4985.9,4994.7
XS Rating Curve= 0 ,0
Exp/Cntr=0.3,0.1

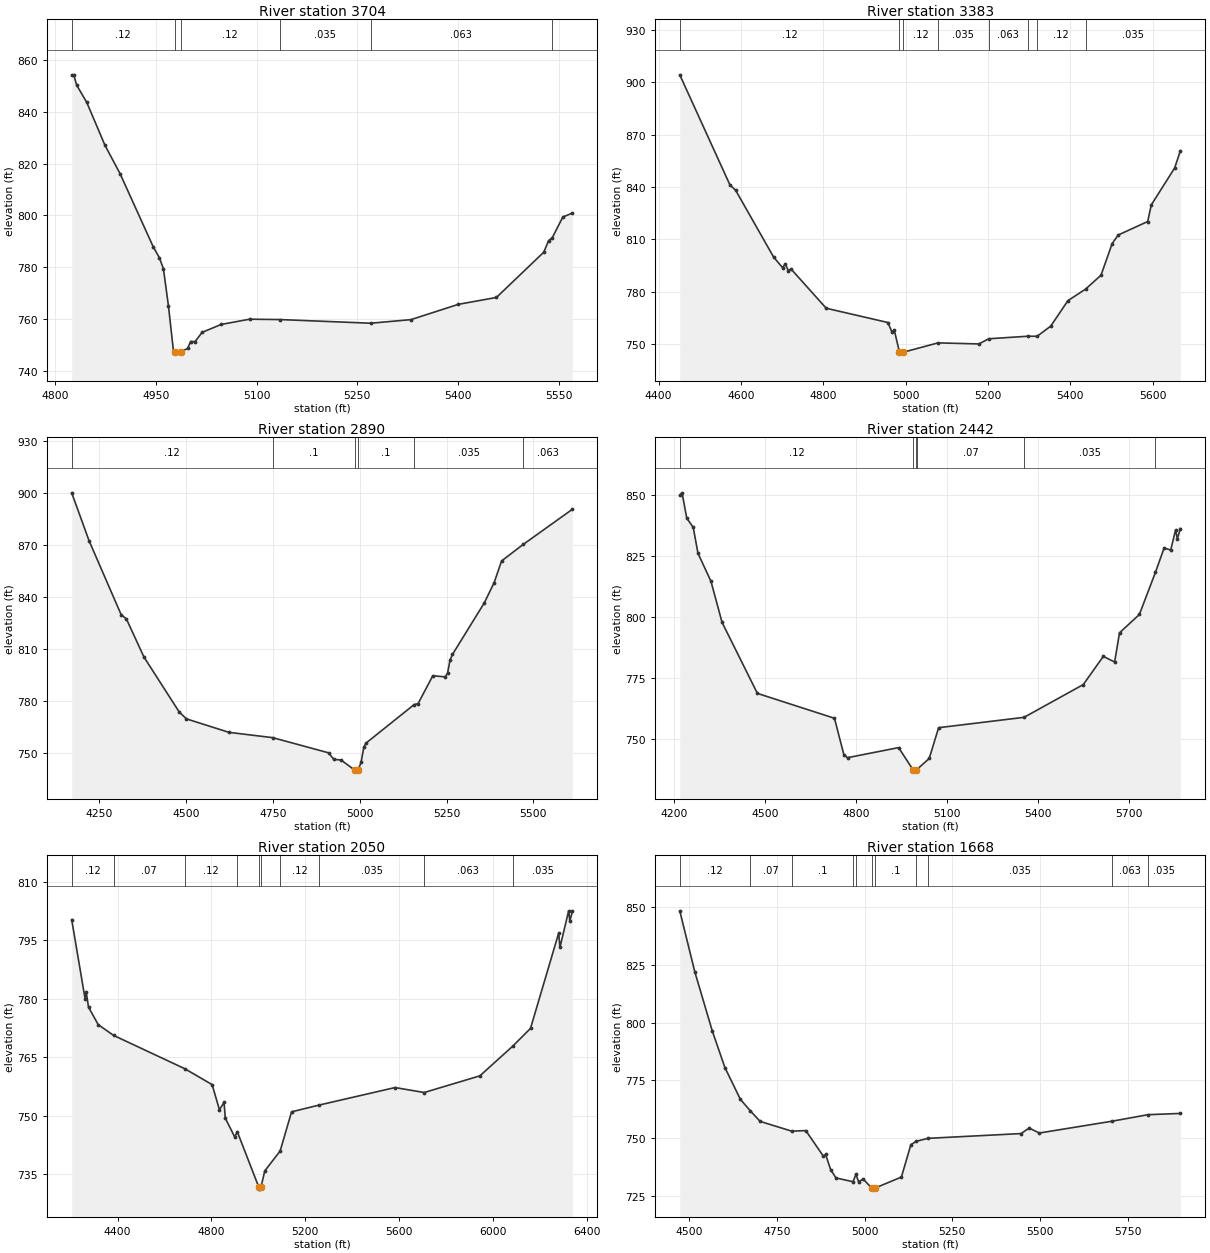
Type RM Length L Ch R = 1 ,3704    ,321,321,321
BEGIN DESCRIPTION:
Jacobs Creek 8.0
END DESCRIPTION:
XS GIS Cut Line= 3
      2235224.97     13851125.02        2235075.       13851225.
      2234675.02     13851624.98
#Sta/Elev= 30
  4824.5  854.16  4827.5  854.16    4832  850.15    4847  843.52    4874  827.07
  4896.6  816.07  4946.1  787.86  4955.2   783.7  4961.2  779.43  4968.7  765.06
  4976.2  747.63  4977.8  747.47  4978.3  746.97  4986.7  747.47  4997.2  748.78
  5001.7  751.43  5008.3  751.43  5018.9  754.97  5047.2  758.02  5089.6  760.04
  5134.9   759.9    5270  758.49    5330  759.87  5400.7  765.77  5457.3  768.41
    5528  785.88  5535.1  790.34  5540.2  791.26  5556.3   799.4  5570.4  800.89
#Mann= 6 ,-1 , 0
  4824.5     .12       0  4977.8     .05       0  4986.7     .12       0
  5134.9    .035       0    5270    .063       0  5540.2    .035       0
Bank Sta=4977.8,4986.7
XS Rating Curve= 0 ,0
Exp/Cntr=0.3,0.1

Type RM Length L Ch R = 1 ,3383    ,493,493,493
BEGIN DESCRIPTION:
A19500
END DESCRIPTION:
XS GIS Cut Line= 4
      2235193.34     13850741.19      2234834.38     13851064.26
      2234733.86     13851301.19      2234461.91     13851691.23
#Sta/Elev= 30
  4451.6  904.23  4573.3  841.25  4587.5  838.04  4679.4  799.91  4701.1  793.83
  4707.8   795.9  4715.3  792.12    4722     793  4807.2  770.56  4957.1  762.38
  4966.9   756.9  4972.4  758.22  4985.2  745.35  4985.7  744.85  4994.1  745.35
  5078.7  750.72    5178  750.11    5202  753.08  5296.9  754.53  5319.5   754.5
  5352.5  760.31  5394.3  774.91    5437  781.48  5474.6  789.47  5501.7  807.58
  5516.5  812.51    5588  820.22  5596.8  829.76  5653.5  850.88  5667.4   860.8
#Mann= 8 ,-1 , 0
  4451.6     .12       0  4985.2     .05       0  4994.1     .12       0
  5078.7    .035       0    5202    .063       0  5296.9    .035       0
  5319.5     .12       0    5437    .035       0
Bank Sta=4985.2,4994.1
XS Rating Curve= 0 ,0
Exp/Cntr=0.3,0.1

Type RM Length L Ch R = 1 ,2890    ,448,448,448
BEGIN DESCRIPTION:
A19499
END DESCRIPTION:
XS GIS Cut Line= 3
      2235161.07     13850701.68      2234421.54     13851211.45
      2234041.05     13851599.12
#Sta/Elev= 30
  4170.8  900.34  4220.7  872.76  4313.3     830  4328.2  827.64  4378.9  805.61
  4480.4  773.91  4501.3  769.94  4623.7  762.16  4749.6  759.11  4910.4  750.36
  4925.3   746.6  4946.3  746.21  4986.4   740.3  4986.9   739.8  4995.4   740.3
  5004.1  744.93  5011.9  753.58  5017.9  755.92  5156.9   778.2  5168.1  778.72
  5210.5  794.82  5245.8  794.18    5253  796.28    5260  803.79  5267.1  807.09
    5359  836.94  5387.3  848.61  5408.5  861.04  5470.9  870.58  5612.2  890.82
#Mann= 6 ,-1 , 0
  4170.8     .12       0  4749.6      .1       0  4986.4     .05       0
  4995.4      .1       0  5156.9    .035       0  5470.9    .063       0
Bank Sta=4986.4,4995.4
XS Rating Curve= 0 ,0
Exp/Cntr=0.3,0.1

Type RM Length L Ch R = 1 ,2442    ,392,392,392
BEGIN DESCRIPTION:
A19498
END DESCRIPTION:
XS GIS Cut Line= 3
      2235028.19     13850357.08      2234274.36     13850812.97
      2233904.61     13851487.86
#Sta/Elev= 30
  4219.4   849.8    4227  850.76  4242.5  840.34  4263.9  836.58  4279.4  825.97
  4322.1  814.55  4358.9  797.65  4475.3  768.57  4729.5  758.37  4760.5  743.41
  4772.4  742.22  4940.9  746.35  4988.8  737.21  4989.3  736.71  4997.8  737.21
  5003.1  737.59  5041.8   741.9  5072.8  754.51  5354.5  758.76  5549.8  772.19
  5615.8  783.74  5653.1  781.43  5669.2  793.39  5734.7  800.91  5787.6  818.15
  5816.2  828.14    5838  827.33  5854.1  835.58  5859.8  831.94  5869.9  836.11
#Mann= 6 ,-1 , 0
  4219.4     .12       0  4988.8     .05       0  4997.8     .12       0
  5003.1     .07       0  5354.5    .035       0  5787.6     .12       0
Bank Sta=4988.8,4997.8
XS Rating Curve= 0 ,0
Exp/Cntr=0.3,0.1

Type RM Length L Ch R = 1 ,2050    ,382,382,382
BEGIN DESCRIPTION:
A19497
END DESCRIPTION:
XS GIS Cut Line= 4
       2234974.4     13850195.51      2234256.41     13850382.19
      2233933.32     13850629.89      2233707.16     13851588.39
#Sta/Elev= 30
  4204.5  800.32  4261.4  780.07  4266.6  781.64  4276.2  777.86  4317.5  773.37
  4382.9  770.61  4685.5  762.08  4803.2  757.96  4834.2  751.51  4853.9  753.42
  4859.1  749.37  4899.6   744.5  4910.2  745.89  5002.1  731.63  5002.6  731.13
  5011.2  731.63  5027.5  735.82  5092.9  740.91  5141.7  750.98  5258.7  752.71
  5582.6  757.21  5707.1  755.94  5944.4  760.22    6084  767.82  6160.1   772.4
  6280.3  796.89  6285.5  793.18  6322.7  802.59  6327.8  799.96  6338.3  802.44
#Mann= 10 ,-1 , 0
  4204.5     .12       0  4382.9     .07       0  4685.5     .12       0
  4910.2      .1       0  5002.1     .05       0  5011.2      .1       0
  5092.9     .12       0  5258.7    .035       0  5707.1    .063       0
    6084    .035       0
Bank Sta=5002.1,5011.2
XS Rating Curve= 0 ,0
Exp/Cntr=0.3,0.1

Type RM Length L Ch R = 1 ,1668    ,412,412,412
BEGIN DESCRIPTION:
A19496
END DESCRIPTION:
XS GIS Cut Line= 3
      2234231.29     13849750.36      2233786.14     13850371.42
      2233516.88     13850978.14
#Sta/Elev= 30
  4472.5  848.51  4515.2  822.14  4565.5  796.27  4601.2  780.54  4645.3  766.76
  4673.4  761.79  4701.8  757.16  4791.9  752.93    4832  753.17  4882.4     742
  4888.5  742.82  4902.7  736.29    4918  732.65  4966.5  730.99  4975.1  734.19
  4982.6  730.94  4995.4  732.17  5019.8  728.28  5020.3  727.78    5030  728.28
  5104.7  733.02  5131.7  747.07  5147.5  748.55  5180.4  749.81  5445.9  751.88
  5469.2  754.27  5497.9  752.12  5704.4  757.22  5808.5  760.08  5900.4  760.62
#Mann= 11 ,-1 , 0
  4472.5     .12       0  4673.4     .07       0  4791.9      .1       0
  4966.5     .07       0  4975.1      .1       0  5019.8     .05       0
    5030      .1       0  5147.5     .12       0  5180.4    .035       0
  5704.4    .063       0  5808.5    .035       0
Bank Sta=5019.8,5030
XS Rating Curve= 0 ,0
Exp/Cntr=0.3,0.1

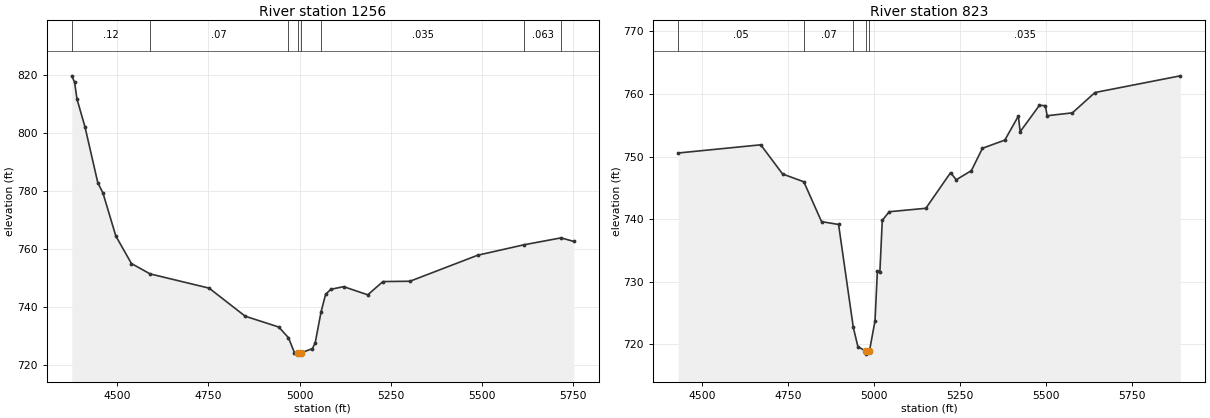
Type RM Length L Ch R = 1 ,1256    ,433,433,433
BEGIN DESCRIPTION:
A19495
END DESCRIPTION:
XS GIS Cut Line= 3
      2233976.37     13849545.78      2233452.28     13850156.03
      2233316.18     13850711.18
#Sta/Elev= 30
  4375.5  819.64  4383.2  817.45  4389.8  811.64  4411.7  802.09  4446.8   782.9
  4461.1  779.29  4496.2  764.55    4539  755.08  4590.1  751.51  4751.9  746.61
  4850.7  736.96  4942.8  733.23  4969.4  729.55  4985.6  724.45  4994.8  724.41
  4995.3  723.91    5005  724.41    5035  725.81  5042.7  727.84  5058.9  738.55
  5071.2  744.48  5085.5  746.21  5120.6  747.12  5186.7  744.31  5228.3  748.87
  5302.4  748.98  5488.2  757.94  5615.9  761.55  5716.5   763.9  5751.5  762.67
#Mann= 8 ,-1 , 0
  4375.5     .12       0  4590.1     .07       0  4969.4     .12       0
  4994.8     .05       0    5005     .12       0  5058.9    .035       0
  5615.9    .063       0  5716.5    .035       0
Bank Sta=4994.8,5005
XS Rating Curve= 0 ,0
Exp/Cntr=0.3,0.1

Type RM Length L Ch R = 1 ,823     ,0,0,0
BEGIN DESCRIPTION:
A19494
END DESCRIPTION:
XS GIS Cut Line= 4
      2233728.68     13849269.35       2233301.5     13849710.88
      2233175.86     13849951.41      2233251.11     13850521.14
#Sta/Elev= 30
  4429.6  750.57  4669.6  751.88  4733.2  747.21  4794.9  745.97  4846.4   739.6
    4896  739.14  4938.8  722.69  4952.3  719.58  4975.4  718.91  4975.9  718.41
  4985.8  718.91    5002  723.75  5008.9  731.72  5016.1  731.52  5023.1   739.8
  5043.3  741.18  5149.9  741.73  5221.7  747.42  5238.2  746.29  5282.3  747.75
  5314.5  751.33  5379.5  752.63    5419  756.48  5424.1  753.97  5480.3   758.2
  5497.6  758.13  5502.6  756.53  5576.1  756.99  5641.7  760.24    5890  762.91
#Mann= 5 ,-1 , 0
  4429.6     .05       0  4794.9     .07       0  4938.8    .035       0
  4975.4    .035       0  4985.8    .035       0
Bank Sta=4975.4,4985.8
XS Rating Curve= 0 ,0
Exp/Cntr=0.3,0.1

Chan Stop Cuts=-1
Use User Specified Reach Order=0
Composite Channel Slope=5