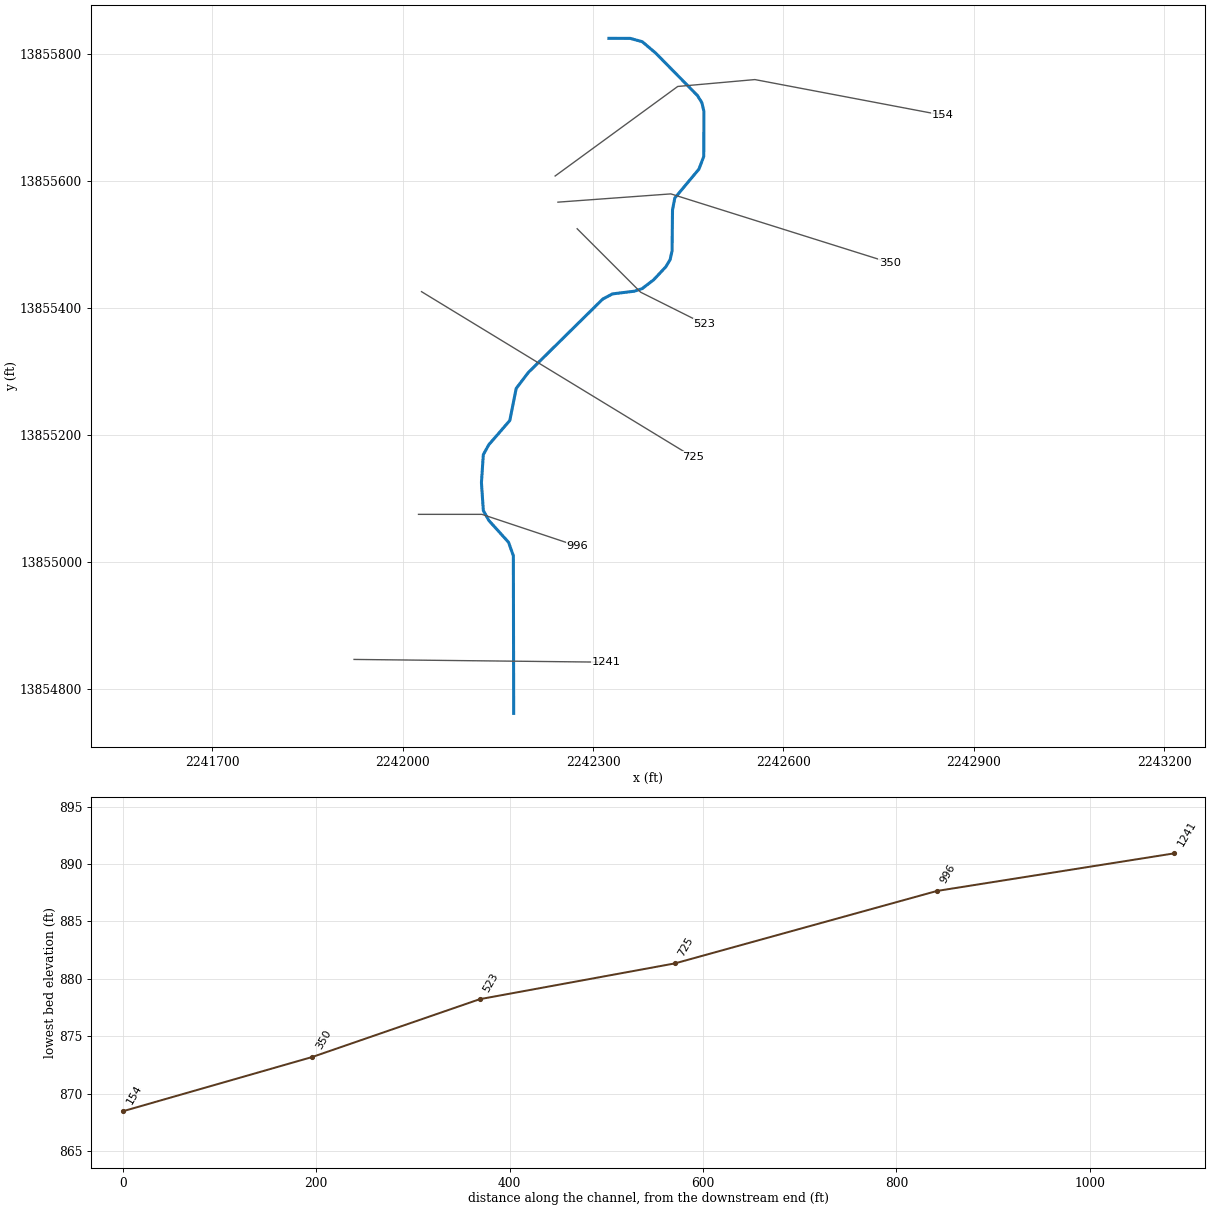
--- Jacobs Tributary 3.prj (project) ---

Proj Title=Jacobs Tributary 3 Base Level Engineering
Current Plan=p01
Default Exp/Contr=0.3,0.1
English Units
Geom File=g01
Flow File=f01
Plan File=p01
BEGIN DESCRIPTION:
Jacobs Tributary 3
END DESCRIPTION:

--- Jacobs Tributary 3.p01 (plan) ---

Plan Title=Multiple Run
Short Identifier=Multiple
Geom File=g01
Flow File=f01
Subcritical Flow
K Sum by GR= 0
Std Step Tol= 0.01
Critical Tol= 0.01
Num of Std Step Trials= 20
Max Error Tol= 0.3
Flow Tol Ratio= 0.001
Split Flow NTrial= 30
Split Flow Tol= 0.02
Split Flow Ratio= 0.02
Log Output Level= 0
Friction Slope Method= 1
Unsteady Friction Slope Method= 2
Unsteady Bridges Friction Slope Method= 1
Parabolic Critical Depth
Global Vel Dist=  1 , 1 , 1
Global Log Level= 0
CheckData=True
Encroach Param= -1, 0, 0, 0
BEGIN DESCRIPTION:
Multiple Run
END DESCRIPTION:

--- Jacobs Tributary 3.f01 (steady flow) ---

Flow Title=Multiple
Number of Profiles=7
Profile Names=10-year,25-year,50-year,1pct_min,100-year,1pct_plu,500-year
River Rch & RM= Jacobs Tributary,Reach-1,1241
     687    1129    1538    1018    2032    4054    3498
Boundary for River Rch & Prof#=Jacobs Tributary,Reach-1,1
Up Type=0
Dn Type=3
Dn Slope=0.005
Boundary for River Rch & Prof#=Jacobs Tributary,Reach-1,2
Up Type=0
Dn Type=3
Dn Slope=0.005
Boundary for River Rch & Prof#=Jacobs Tributary,Reach-1,3
Up Type=0
Dn Type=3
Dn Slope=0.005
Boundary for River Rch & Prof#=Jacobs Tributary,Reach-1,4
Up Type=0
Dn Type=3
Dn Slope=0.005
Boundary for River Rch & Prof#=Jacobs Tributary,Reach-1,5
Up Type=0
Dn Type=3
Dn Slope=0.005
Boundary for River Rch & Prof#=Jacobs Tributary,Reach-1,6
Up Type=0
Dn Type=3
Dn Slope=0.005
Boundary for River Rch & Prof#=Jacobs Tributary,Reach-1,7
Up Type=0
Dn Type=3
Dn Slope=0.005

--- Jacobs Tributary 3.g01 (geometry) ---

Geom Title=Existing Conditions

River Reach=Jacobs Tributary,Reach-1
Reach XY= 30
      2242175.00     13854761.42      2242174.48     13855009.78
      2242166.85     13855031.06      2242135.81     13855065.37
      2242127.17     13855080.98      2242124.18     13855125.00
      2242127.14     13855169.03      2242135.75     13855184.65
      2242168.85     13855222.83      2242178.94     13855273.37
      2242198.01     13855298.47      2242315.34     13855414.21
      2242330.68     13855422.34      2242365.38     13855426.63
      2242377.57     13855430.74      2242395.57     13855444.59
      2242414.61     13855464.90      2242421.48     13855476.28
      2242424.53     13855490.09      2242425.25     13855554.89
      2242428.86     13855573.40      2242466.92     13855618.96
      2242474.46     13855638.98      2242474.76     13855709.79
      2242471.55     13855723.52      2242464.59     13855734.81
      2242398.52     13855801.99      2242377.54     13855819.70
      2242358.64     13855824.93      2242325.00     13855825.00

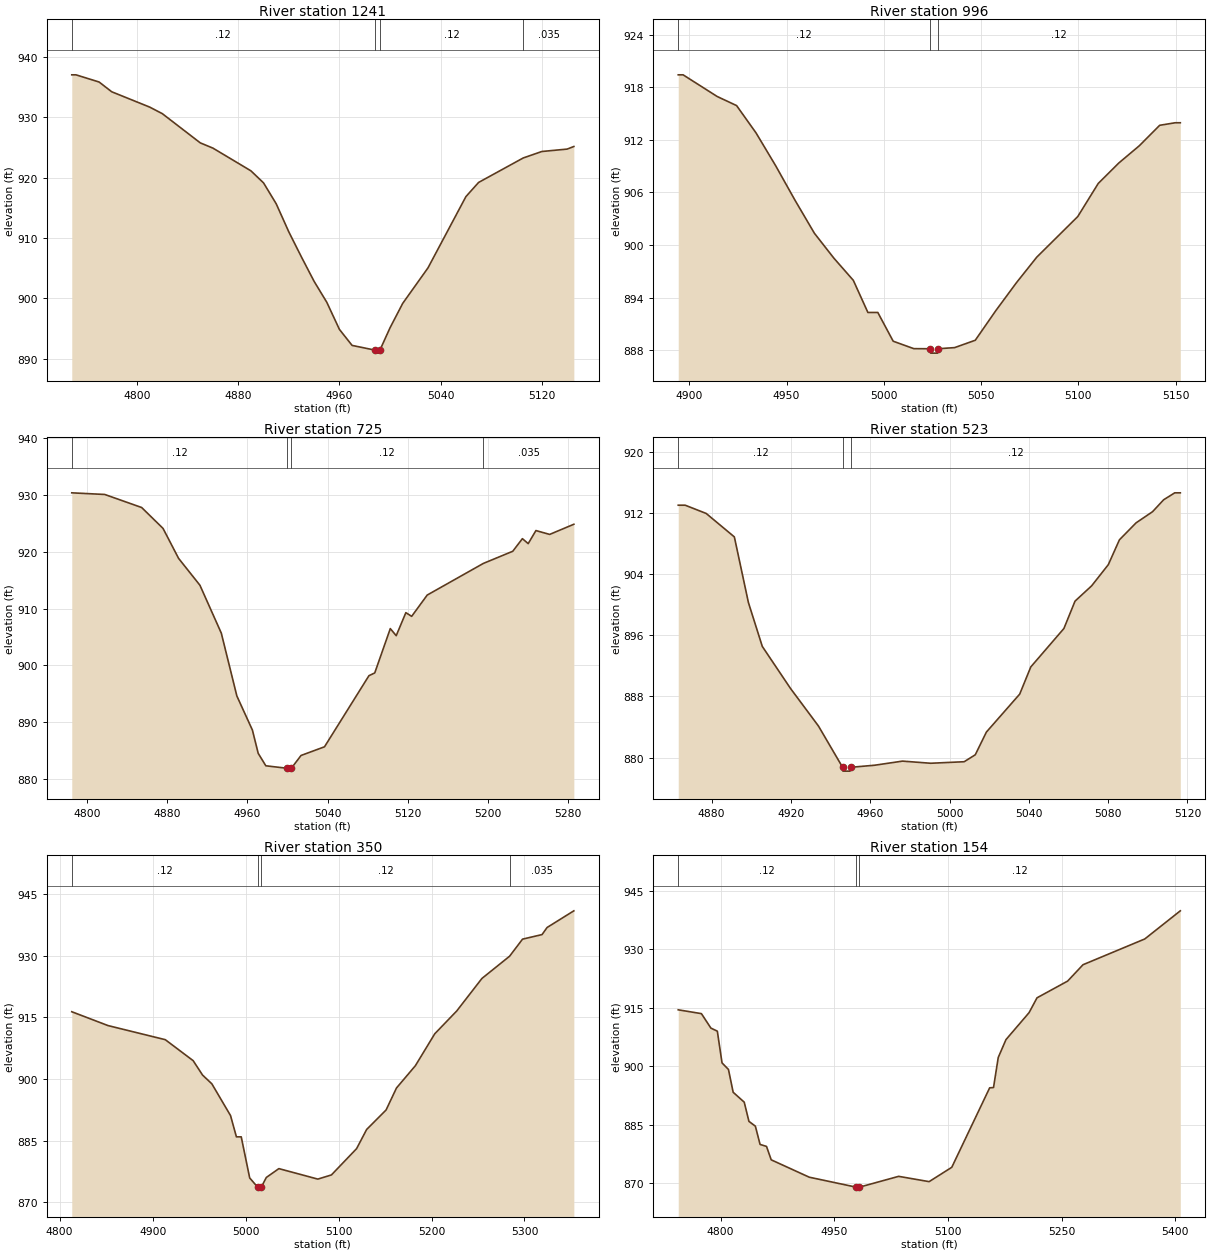
Type RM Length L Ch R = 1,1241,245,245,245
BEGIN DESCRIPTION:
A19511
END DESCRIPTION:
XS GIS Cut Line= 2
      2241923.44     13854846.41      2242320.32     13854842.07
#Sta/Elev= 30
  4748.4  937.06  4751.7  937.06  4770.0  935.87  4780.0  934.25  4810.0  931.71
  4820.0  930.62  4850.0  925.78  4860.0  924.91  4890.0  921.15  4900.0  919.15
  4910.0  915.69  4920.0  911.02  4930.0  906.85  4940.0  902.82  4950.0  899.36
  4960.0  894.86  4970.0  892.21  4988.0  891.43  4988.2  890.93  4991.7  890.93
  4992.0  891.43  5000.0  895.13  5010.0  899.17  5030.0  905.06  5060.0  916.88
  5070.0  919.22  5105.3  923.28  5120.0  924.35  5140.0  924.75  5145.3  925.18
#Mann=4,-1,0
  4748.4    0.12       0  4988.0    0.05       0  4992.0    0.12       0
  5105.3   0.035       0
Bank Sta=4988,4992
Exp/Cntr=0.3,0.1

Type RM Length L Ch R = 1,996,271,271,271
BEGIN DESCRIPTION:
Jacobs Tributary 3 2.0
END DESCRIPTION:
XS GIS Cut Line= 3
      2242025.03     13855075.00      2242125.00     13855075.00
      2242275.01     13855025.00
#Sta/Elev= 30
  4894.3  919.42  4896.8  919.42  4914.3  916.95  4924.3  915.91  4934.3  912.79
  4944.3  909.08  4954.3  905.12  4964.3  901.34  4974.3  898.50  4984.3  895.97
  4991.8  892.30  4996.9  892.30  5004.8  889.02  5015.4  888.17  5023.9  888.16
  5024.1  887.66  5027.6  887.66  5027.9  888.16  5036.4  888.29  5047.0  889.13
  5057.5  892.49  5068.1  895.68  5078.6  898.61  5099.7  903.25  5110.2  907.02
  5120.8  909.36  5131.3  911.32  5141.8  913.66  5149.8  913.95  5152.4  913.95
#Mann=3,-1,0
  4894.3    0.12       0  5023.9    0.05       0  5027.9    0.12       0
Bank Sta=5023.9,5027.9
Exp/Cntr=0.3,0.1

Type RM Length L Ch R = 1,725,202,202,202
BEGIN DESCRIPTION:
A19510
END DESCRIPTION:
XS GIS Cut Line= 2
      2242029.78     13855425.86      2242457.31     13855165.43
#Sta/Elev= 30
  4784.9  930.40  4817.8  930.11  4854.6  927.81  4875.9  924.13  4891.4  918.85
  4912.7  914.11  4934.0  905.67  4949.5  894.60  4965.0  888.59  4970.8  884.48
  4978.4  882.29  4999.8  881.85  5000.0  881.35  5003.8  881.85  5013.5  884.11
  5036.9  885.64  5081.2  898.17  5087.0  898.66  5102.5  906.47  5108.4  905.22
  5118.0  909.28  5123.8  908.63  5139.3  912.38  5195.3  917.96  5224.6  920.10
  5234.2  922.32  5240.0  921.45  5247.7  923.75  5261.4  923.07  5285.5  924.86
#Mann=4,-1,0
  4784.9    0.12       0  4999.8    0.05       0  5003.8    0.12       0
  5195.3   0.035       0
Bank Sta=4999.8,5003.8
Exp/Cntr=0.3,0.1

Type RM Length L Ch R = 1,523,173,173,173
BEGIN DESCRIPTION:
Jacobs Tributary 3 1.0
END DESCRIPTION:
XS GIS Cut Line= 3
      2242275.00     13855525.00      2242375.00     13855425.00
      2242474.98     13855375.01
#Sta/Elev= 30
  4863.2  913.04  4866.7  913.04  4877.3  911.96  4891.5  908.89  4898.6  900.29
  4905.6  894.55  4919.8  889.06  4933.9  884.14  4946.1  878.73  4946.3  878.23
  4949.8  878.23  4950.1  878.73  4962.2  879.00  4976.3  879.54  4990.5  879.26
  5007.4  879.46  5013.0  880.37  5018.6  883.34  5035.4  888.31  5041.0  891.87
  5057.7  896.90  5063.3  900.48  5071.7  902.49  5080.1  905.26  5085.7  908.51
  5094.1  910.73  5102.4  912.19  5108.0  913.75  5113.6  914.66  5116.4  914.66
#Mann=3,-1,0
  4863.2    0.12       0  4946.1    0.05       0  4950.1    0.12       0
Bank Sta=4946.1,4950.1
Exp/Cntr=0.3,0.1

Type RM Length L Ch R = 1,350,196,196,196
BEGIN DESCRIPTION:
A19509
END DESCRIPTION:
XS GIS Cut Line= 3
      2242244.70     13855566.89      2242422.62     13855579.91
      2242767.67     13855471.41
#Sta/Elev= 30
  4813.0  916.36  4852.0  912.99  4913.6  909.56  4943.6  904.45  4953.7  900.95
  4963.7  898.82  4983.8  891.09  4990.1  885.92  4995.3  885.92  5004.4  875.92
  5012.9  873.70  5013.1  873.20  5016.9  873.70  5022.3  876.04  5035.8  878.19
  5077.7  875.64  5092.3  876.65  5119.4  883.05  5130.2  887.71  5151.1  892.45
  5162.3  897.80  5182.6  903.22  5203.5  911.00  5227.1  916.54  5254.2  924.45
  5284.0  929.87  5297.9  934.02  5318.9  935.13  5324.3  936.85  5353.1  940.91
#Mann=4,-1,0
  4813.0    0.12       0  5012.9    0.05       0  5016.9    0.12       0
  5284.0   0.035       0
Bank Sta=5012.9,5016.9
Exp/Cntr=0.3,0.1

Type RM Length L Ch R = 1,154,0,0,0
BEGIN DESCRIPTION:
A19508
END DESCRIPTION:
XS GIS Cut Line= 4
      2242240.31     13855608.11      2242433.47     13855749.18
      2242555.00     13855760.03      2242851.11     13855703.84
#Sta/Elev= 30
  4744.1  914.48  4774.7  913.50  4787.2  909.79  4795.7  909.00  4801.9  900.86
  4810.4  899.17  4816.6  893.32  4831.2  890.78  4837.4  885.86  4845.9  884.62
  4852.1  879.94  4860.6  879.43  4866.8  875.99  4917.0  871.53  4979.1  868.97
  4979.4  868.47  4983.1  868.97  5035.0  871.75  5075.2  870.39  5105.1  874.07
  5155.1  894.46  5160.2  894.54  5166.4  902.23  5176.6  906.83  5207.1  913.75
  5217.6  917.56  5258.0  921.85  5278.3  926.05  5359.8  932.66  5406.7  939.88
#Mann=3,-1,0
  4744.1    0.12       0  4979.1    0.05       0  4983.1    0.12       0
Bank Sta=4979.1,4983.1
Exp/Cntr=0.3,0.1

Chan Stop Cuts=-1