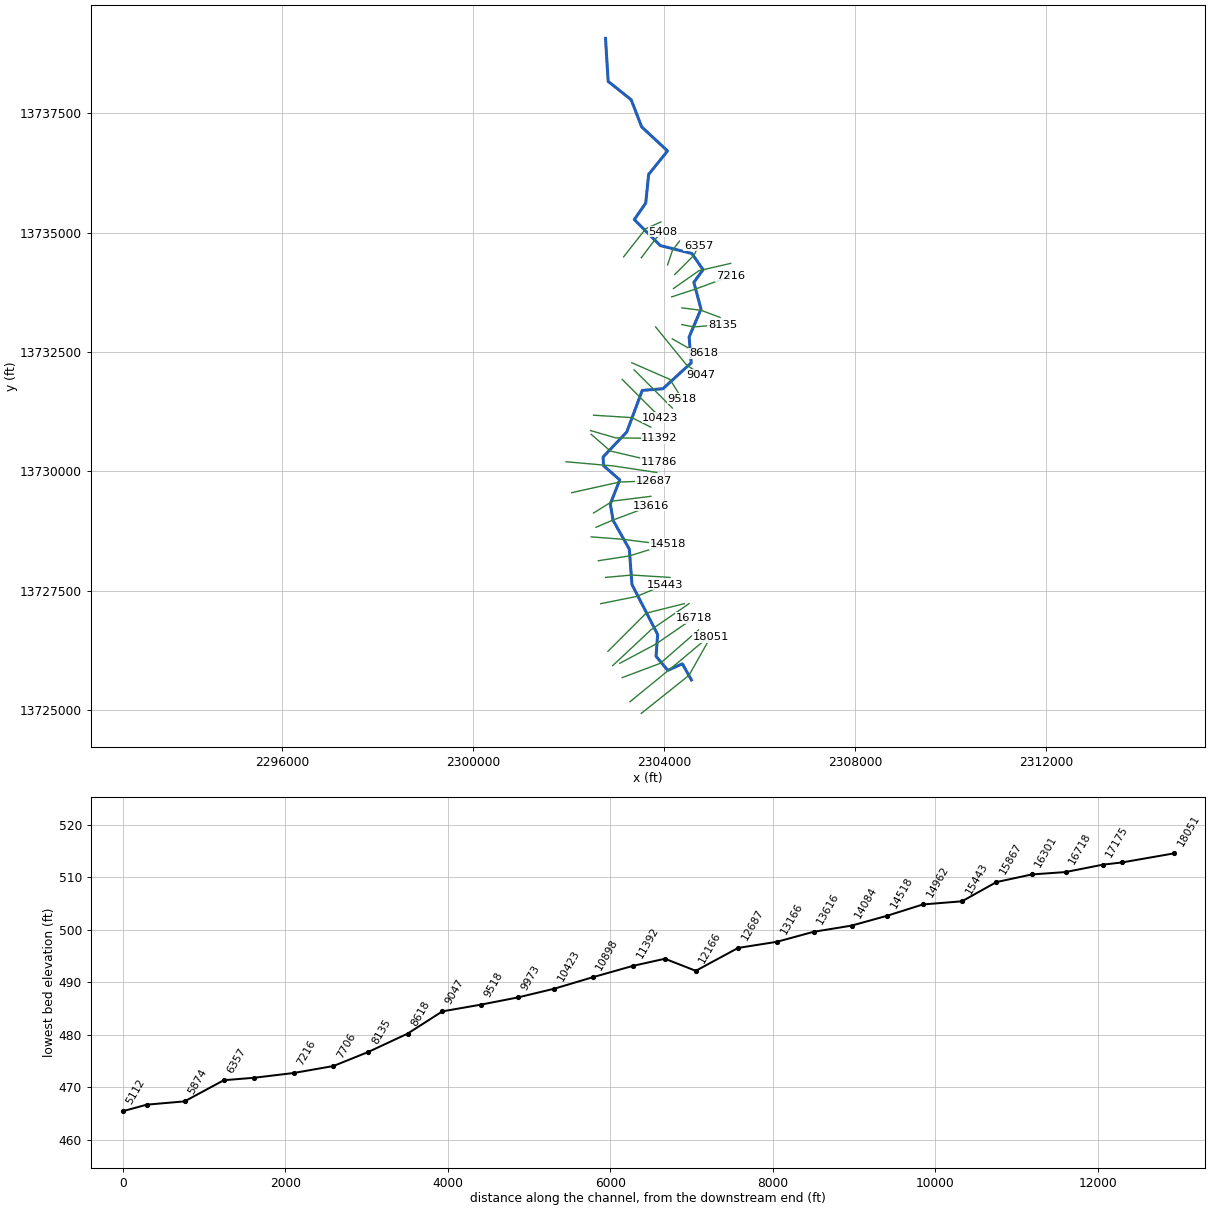
--- KONDE BRANCH.prj (project) ---

Proj Title=KONDE BRANCH Base Level Engineering
Current Plan=p01
Default Exp/Contr=0.3,0.1
English Units
Geom File=g01
Flow File=f01
Plan File=p01
Y Axis Title=Elevation
X Axis Title(PF)=Main Channel Distance
X Axis Title(XS)=Station
BEGIN DESCRIPTION:
KONDE BRANCH
END DESCRIPTION:
DSS Export Rating Curves= 0
DSS Export Rating Curve Sorted= 0
DSS Export Volume Flow Curves= 0
DXF OffsetX= 0
DXF OffsetY= 0
DXF ScaleX= 1
DXF ScaleY= 10

--- KONDE BRANCH.p01 (plan) ---

Plan Title=Multiple Run
Short Identifier=Multiple
Geom File=g01
Flow File=f01
Subcritical Flow
K Sum by GR= 0
Std Step Tol= 0.01
Critical Tol= 0.01
Num of Std Step Trials= 20
Max Error Tol= 0.3
Flow Tol Ratio= 0.001
Split Flow NTrial= 30
Split Flow Tol= 0.02
Split Flow Ratio= 0.02
Log Output Level= 0
Friction Slope Method= 1
Unsteady Friction Slope Method= 2
Unsteady Bridges Friction Slope Method= 1
Parabolic Critical Depth
Global Vel Dist=  1 , 1 , 1
Global Log Level= 0
CheckData=True
Encroach Param= -1, 0, 0, 0
BEGIN DESCRIPTION:
Multiple Run
END DESCRIPTION:

--- KONDE BRANCH.f01 (steady flow) ---

Flow Title=Multiple
Number of Profiles=7
Profile Names=10-year,25-year,50-year,1pct_min,100-year,1pct_plu,500-year
River Rch & RM= KONDE BRANCH,Reach-1,18051
     636    1027    1381     899    1793    3578    2998
River Rch & RM= KONDE BRANCH,Reach-1,17175
     932    1532    2082    1368    2730    5447    4653
River Rch & RM= KONDE BRANCH,Reach-1,12166
    1178    1951    2666    1758    3509    7001    6029
River Rch & RM= KONDE BRANCH,Reach-1,7706
    1299    2156    2949    1947    3885    7752    6687
Boundary for River Rch & Prof#=KONDE BRANCH,Reach-1,1
Up Type=0
Dn Type=3
Dn Slope=0.005
Boundary for River Rch & Prof#=KONDE BRANCH,Reach-1,2
Up Type=0
Dn Type=3
Dn Slope=0.005
Boundary for River Rch & Prof#=KONDE BRANCH,Reach-1,3
Up Type=0
Dn Type=3
Dn Slope=0.005
Boundary for River Rch & Prof#=KONDE BRANCH,Reach-1,4
Up Type=0
Dn Type=3
Dn Slope=0.005
Boundary for River Rch & Prof#=KONDE BRANCH,Reach-1,5
Up Type=0
Dn Type=3
Dn Slope=0.005
Boundary for River Rch & Prof#=KONDE BRANCH,Reach-1,6
Up Type=0
Dn Type=3
Dn Slope=0.005
Boundary for River Rch & Prof#=KONDE BRANCH,Reach-1,7
Up Type=0
Dn Type=3
Dn Slope=0.005

--- KONDE BRANCH.g01 (geometry) ---

Geom Title=Existing Conditions
Program Version=4.10

River Reach=KONDE BRANCH    ,Reach-1
Reach XY= 30
        2304575.       13725625.      2304385.32     13725964.18
      2304080.72     13725826.91      2303833.24     13726121.77
      2303867.02     13726578.35      2303328.75     13727626.55
      2303273.01     13728369.32      2302933.24     13728971.77
      2302875.77     13729314.31      2303073.15      13729819.2
      2302732.81     13730118.81      2302724.67     13730300.21
      2303219.46     13730822.58       2303544.6     13731695.25
      2303977.47     13731730.45      2304569.64      13732272.3
       2304526.2      13732814.5      2304775.21     13733399.91
      2304625.36     13733959.73      2304817.93       13734225.
        2304585.     13734564.37      2303922.69     13734730.82
      2303378.45     13735276.49      2303617.21     13735621.58
      2303678.54     13736223.54      2304073.97     13736714.56
      2303532.69     13737218.52      2303311.77     13737788.72
      2302830.52     13738172.57        2302775.       13739075.

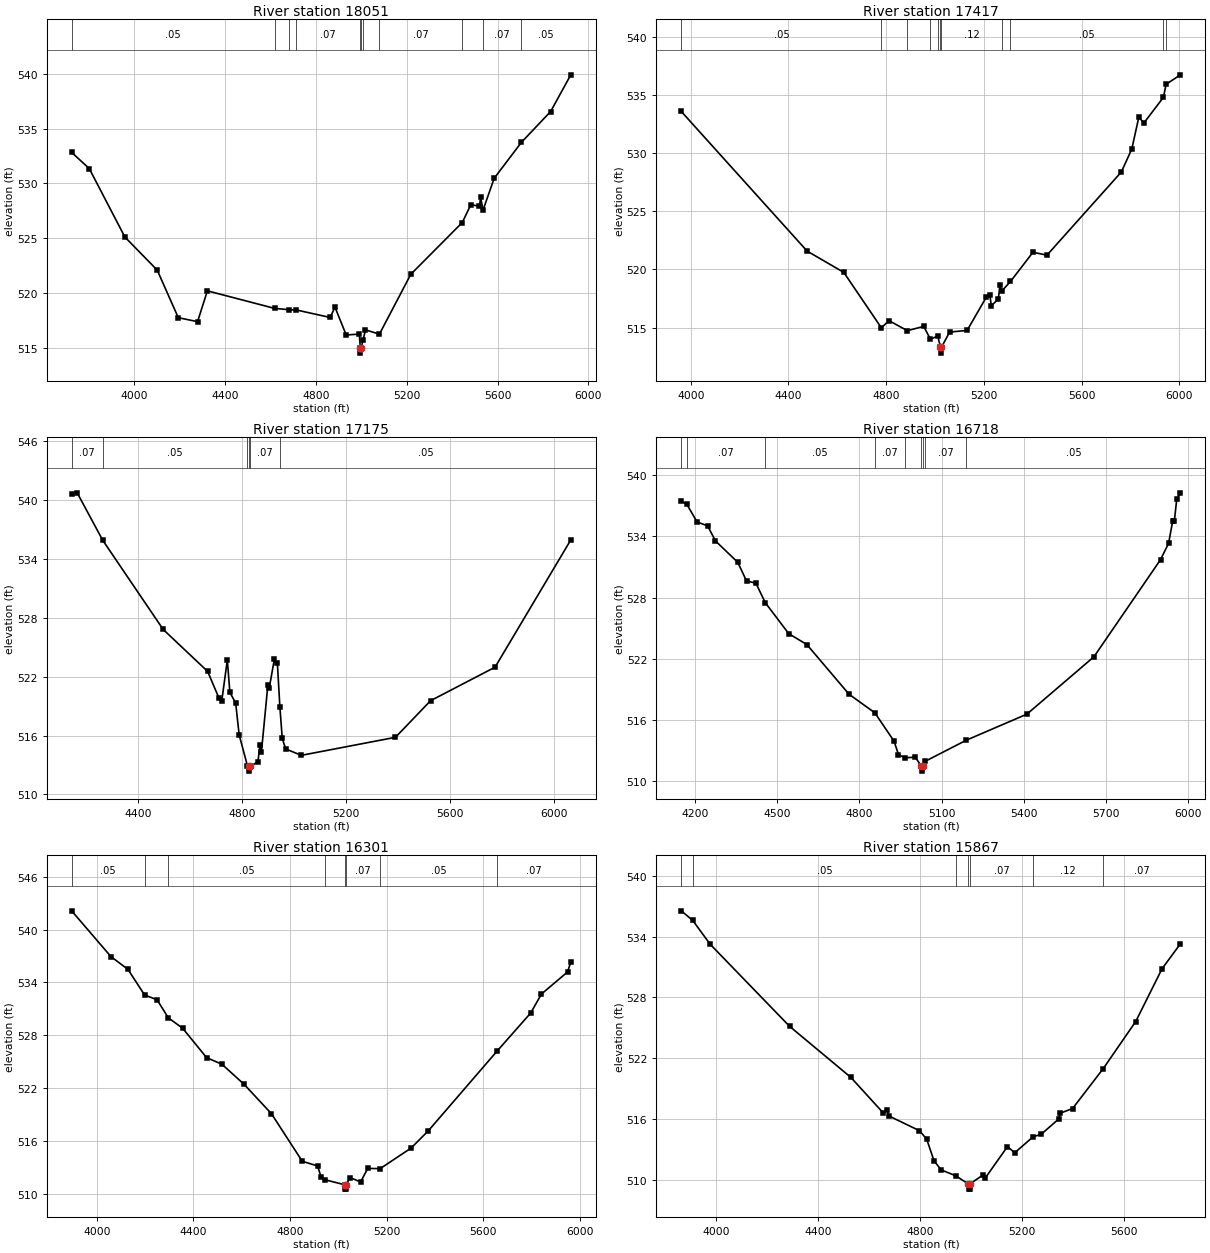
Type RM Length L Ch R = 1 ,18051   ,634,634,634
BEGIN DESCRIPTION:
KONDE BRANCH 39.0
END DESCRIPTION:
XS GIS Cut Line= 3
      2303524.99     13724924.99        2304525.       13725725.
      2304974.99     13726524.99
#Sta/Elev= 30
    3724  532.83  3801.7  531.35  3958.5  525.11    4101  522.09  4193.8  517.75
  4278.7  517.39  4321.9   520.2    4618   518.6  4682.1  518.48  4713.2  518.46
    4863  517.77  4883.8  518.72  4933.4  516.17    4991  516.26  4995.4  515.02
  4995.7  514.52  4999.5  515.02    5008  515.75  5018.3  516.64  5079.6  516.25
  5217.9  521.71  5444.5  526.43  5482.4  528.06    5520  527.92  5525.7  528.74
  5535.6  527.54    5585  530.46  5705.3  533.75  5833.6  536.55  5922.5   539.9
#Mann= 11 ,-1 , 0
    3724     .05       0    4618     .07       0  4682.1     .05       0
  4713.2     .07       0  4995.4     .05       0  4999.5     .07       0
    5008     .12       0  5079.6     .07       0  5444.5     .05       0
  5535.6     .07       0  5705.3     .05       0
Bank Sta=4995.4,4999.5
XS Rating Curve= 0 ,0
Exp/Cntr=0.3,0.1

Type RM Length L Ch R = 1 ,17417   ,242,242,242
BEGIN DESCRIPTION:
KONDE BRANCH 38.0
END DESCRIPTION:
XS GIS Cut Line= 3
      2303286.54     13725168.17      2304275.23     13725975.61
      2304861.51     13726468.74
#Sta/Elev= 30
  3961.4  533.58  4476.3  521.58  4626.3  519.75    4780  514.99  4811.5   515.6
  4886.6  514.74  4953.6  515.11    4981  513.99  5010.7  514.29    5022  513.31
  5022.2  512.81  5026.1  513.31  5059.2  514.62    5131  514.76  5209.3  517.61
  5223.6  517.84  5230.1  516.89  5258.7  517.45  5265.3  518.66  5271.7  518.12
  5308.5  518.97  5400.5  521.48  5457.7  521.23  5762.1  528.38    5805  530.36
  5833.6  533.09  5854.4  532.59  5934.1  534.79  5945.4  535.92    6004  536.73
#Mann= 11 ,-1 , 0
  3961.4     .05       0    4780     .07       0  4886.6     .12       0
    4981     .07       0  5010.7     .12       0    5022     .05       0
  5026.1     .12       0  5271.7     .07       0  5308.5     .05       0
  5934.1     .07       0  5945.4     .05       0
Bank Sta=5022,5026.1
XS Rating Curve= 0 ,0
Exp/Cntr=0.3,0.1

Type RM Length L Ch R = 1 ,17175   ,457,457,457
BEGIN DESCRIPTION:
KONDE BRANCH 37.0
END DESCRIPTION:
XS GIS Cut Line= 3
      2303124.96     13725674.98        2303925.       13725975.
      2304725.03     13726675.03
#Sta/Elev= 30
    4146  540.62  4167.4  540.75  4265.3  535.92  4497.6  526.82  4668.5  522.54
  4712.1  519.81  4722.8  519.54  4744.1   523.7  4753.9   520.4  4776.2  519.31
  4789.5  516.08  4821.2  512.93  4827.1  512.87  4827.4  512.37  4832.1  512.87
  4861.6  513.31  4869.6  515.05    4875   514.3  4899.9  521.16  4905.2  520.85
  4924.8  523.78  4936.4  523.37  4945.9  518.95  4955.1   515.7  4968.4  514.63
  5028.4  513.98  5390.1  515.82  5524.8  519.55  5772.6  522.97  6063.5  535.95
#Mann= 6 ,-1 , 0
    4146     .07       0  4265.3     .05       0  4821.2     .07       0
  4827.1     .05       0  4832.1     .07       0  4945.9     .05       0
Bank Sta=4827.1,4832.1
XS Rating Curve= 0 ,0
Exp/Cntr=0.3,0.1

Type RM Length L Ch R = 1 ,16718   ,417,417,417
BEGIN DESCRIPTION:
KONDE BRANCH 36.0
END DESCRIPTION:
XS GIS Cut Line= 3
      2303074.99     13725974.99        2303825.       13726375.
      2304624.97     13726924.98
#Sta/Elev= 30
  4150.4  537.43  4169.6  537.19  4208.1  535.41  4246.4  535.03  4275.1  533.55
  4356.2  531.46  4388.4  529.62  4422.4  529.41  4456.9  527.49  4542.5  524.45
  4608.3  523.39  4762.4  518.51  4856.5  516.69  4926.4  513.91  4942.7  512.59
  4965.9  512.27  5003.4  512.34  5026.3  511.47  5026.7  510.97  5031.4  511.47
  5039.9  511.93  5190.5  514.01  5411.1  516.56  5655.7  522.19  5898.4  531.71
  5927.9  533.31  5942.8  535.49  5948.9   535.5  5957.7  537.66  5971.2  538.27
#Mann= 9 ,-1 , 0
  4150.4     .05       0  4169.6     .07       0  4456.9     .05       0
  4856.5     .07       0  4965.9     .05       0  5026.3     .05       0
  5031.4     .05       0  5039.9     .07       0  5190.5     .05       0
Bank Sta=5026.3,5031.4
XS Rating Curve= 0 ,0
Exp/Cntr=0.3,0.1

Type RM Length L Ch R = 1 ,16301   ,434,434,434
BEGIN DESCRIPTION:
KONDE BRANCH 35.0
END DESCRIPTION:
XS GIS Cut Line= 3
      2302925.03     13725925.03        2303725.       13726675.
      2304525.03     13727225.02
#Sta/Elev= 30
  3895.6  542.13  4058.4  536.93  4128.8  535.48    4198  532.56  4249.4  532.03
  4295.8  529.98  4355.4  528.79  4454.6  525.45  4518.1   524.7  4609.9  522.42
  4723.2  519.08  4850.7  513.68  4914.2  513.14  4928.4  511.93    4947  511.56
    5026  511.01  5026.3  510.51  5030.7  510.51  5031.1  511.01  5050.3  511.81
  5092.3  511.32    5122  512.86  5173.5  512.84  5301.3  515.17    5373  517.14
  5657.6  526.19  5797.2  530.53  5841.6  532.68  5949.4  535.18    5963   536.3
#Mann= 8 ,-1 , 0
  3895.6     .05       0    4198     .07       0  4295.8     .05       0
    4947     .07       0    5026     .05       0  5031.1     .07       0
  5173.5     .05       0  5657.6     .07       0
Bank Sta=5026,5031.1
XS Rating Curve= 0 ,0
Exp/Cntr=0.3,0.1

Type RM Length L Ch R = 1 ,15867   ,424,424,424
BEGIN DESCRIPTION:
KONDE BRANCH 34.0
END DESCRIPTION:
XS GIS Cut Line= 3
      2302825.03     13726225.03        2303625.       13727025.
      2304425.05     13727225.01
#Sta/Elev= 30
  3864.4  536.54  3909.3  535.59  3977.5  533.24  4288.6  525.14    4529  520.09
  4656.3  516.57  4670.5   516.9  4677.5  516.29  4797.7  514.83    4826     514
  4854.3  511.88  4882.6  510.96  4940.6  510.37  4989.6  509.56    4990  509.06
  4994.4  509.06  4994.8  509.56  5047.3  510.47    5055  510.14  5142.6  513.26
    5171  512.65  5243.5  514.24    5274  514.46  5343.6  515.99  5348.8  516.55
  5397.7  517.02  5517.8  520.96  5645.1  525.61  5748.2  530.82  5820.4  533.29
#Mann= 7 ,-1 , 0
  3864.4    .035       0  3909.3     .05       0  4940.6     .07       0
  4989.6     .05       0  4994.8     .07       0  5243.5     .12       0
  5517.8     .07       0
Bank Sta=4989.6,4994.8
XS Rating Curve= 0 ,0
Exp/Cntr=0.3,0.1

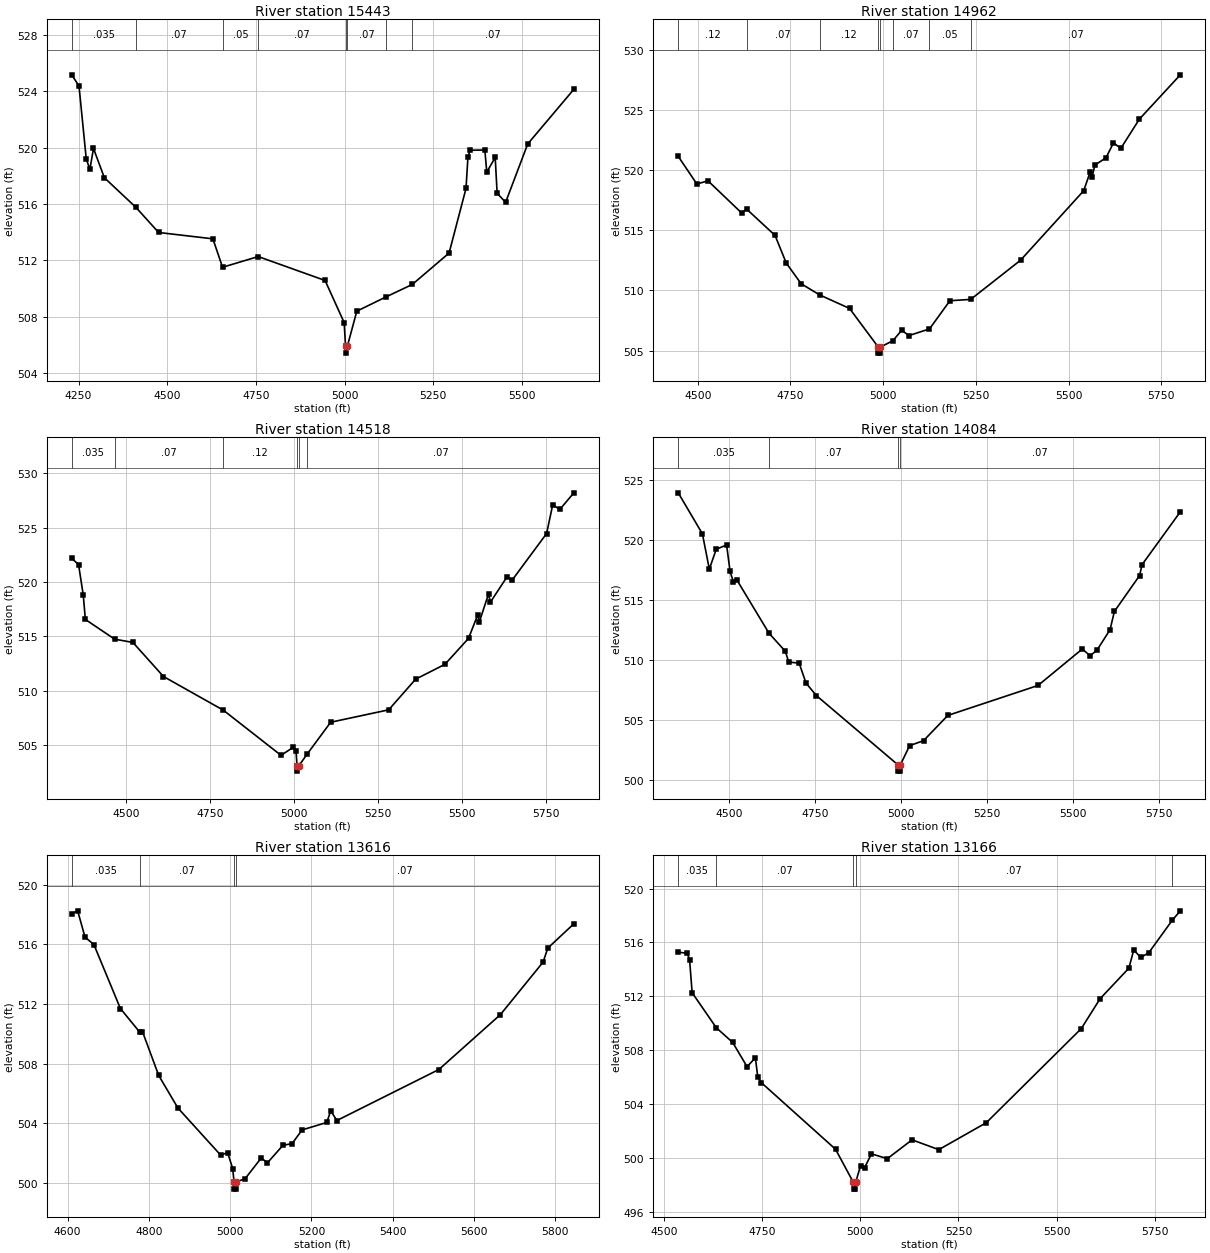
Type RM Length L Ch R = 1 ,15443   ,481,481,481
BEGIN DESCRIPTION:
KONDE BRANCH 33.0
END DESCRIPTION:
XS GIS Cut Line= 3
      2302674.99       13727225.        2303425.       13727375.
      2304025.04     13727625.02
#Sta/Elev= 30
    4231  525.17  4251.4  524.37  4271.8   519.2    4282  518.45  4292.2  519.94
  4322.8  517.86  4411.2  515.77  4475.8  513.97  4628.7  513.52  4655.9   511.5
  4756.4  512.26  4944.9  510.56  4998.6  507.57  5002.5   505.9  5002.9   505.4
  5007.7   505.9  5034.3  508.38  5115.4  509.38  5190.7  510.28  5294.3  512.51
    5342   517.1  5347.4   519.3  5353.4  519.81  5395.1  519.83  5400.5  518.26
  5424.3   519.3  5429.7  516.76  5453.6  516.11  5515.9  520.26  5645.9  524.14
#Mann= 8 ,-1 , 0
    4231    .035       0  4411.2     .07       0  4655.9     .05       0
  4756.4     .07       0  5002.5     .05       0  5007.7     .07       0
  5115.4     .05       0  5190.7     .07       0
Bank Sta=5002.5,5007.7
XS Rating Curve= 0 ,0
Exp/Cntr=0.3,0.1

Type RM Length L Ch R = 1 ,14962   ,444,444,444
BEGIN DESCRIPTION:
KONDE BRANCH 32.0
END DESCRIPTION:
XS GIS Cut Line= 3
      2302775.01       13727775.        2303325.       13727825.
      2304124.98       13727775.
#Sta/Elev= 30
  4447.4  521.13  4497.6  518.84  4527.7   519.1  4618.1  516.44  4631.6  516.76
  4708.5  514.57  4738.6  512.28  4778.8  510.56  4828.8  509.63  4909.3  508.51
  4986.8   505.3  4987.3   504.8    4992   504.8  4992.4   505.3  5026.1  505.83
  5049.8  506.69  5069.8  506.26  5124.9  506.81    5180  509.15    5236  509.26
  5370.4  512.51  5540.7  518.28  5558.2  519.84  5563.3  519.43  5570.8  520.41
  5600.8  521.01  5620.9  522.25  5640.9   521.8    5691  524.23  5801.2   527.9
#Mann= 8 ,-1 , 0
  4447.4     .12       0  4631.6     .07       0  4828.8     .12       0
  4986.8     .05       0  4992.4     .12       0  5026.1     .07       0
  5124.9     .05       0    5236     .07       0
Bank Sta=4986.8,4992.4
XS Rating Curve= 0 ,0
Exp/Cntr=0.3,0.1

Type RM Length L Ch R = 1 ,14518   ,434,434,434
BEGIN DESCRIPTION:
KONDE BRANCH 31.0
END DESCRIPTION:
XS GIS Cut Line= 3
      2302624.99       13728125.        2303275.       13728225.
      2304074.99       13728475.
#Sta/Elev= 30
  4338.2  522.17  4358.4   521.6  4372.4  518.81  4378.7  516.56  4465.9  514.75
  4520.3  514.45  4611.4  511.32  4789.6  508.23  4961.7  504.08  4998.5  504.83
  5006.3  504.47  5009.3  503.13  5009.7  502.63  5014.9  503.13  5038.9  504.17
  5109.5  507.12  5282.4  508.26  5362.5  511.07    5450  512.44  5520.2  514.82
  5547.5  516.97  5552.7  516.36  5579.9  518.91  5585.2  518.14  5634.9  520.47
  5650.1  520.17  5752.8  524.45  5771.1   527.1  5792.1  526.66    5834  528.19
#Mann= 6 ,-1 , 0
  4338.2    .035       0  4465.9     .07       0  4789.6     .12       0
  5009.3     .05       0  5014.9     .12       0  5038.9     .07       0
Bank Sta=5009.3,5014.9
XS Rating Curve= 0 ,0
Exp/Cntr=0.3,0.1

Type RM Length L Ch R = 1 ,14084   ,468,468,468
BEGIN DESCRIPTION:
KONDE BRANCH 30.0
END DESCRIPTION:
XS GIS Cut Line= 3
      2302474.96       13728625.        2303125.       13728575.
      2303925.01       13728475.
#Sta/Elev= 30
  4352.9   523.9  4423.1  520.49  4443.2  517.56  4463.3  519.21  4493.4  519.57
  4503.4  517.37  4513.4  516.47  4523.4  516.65  4616.3  512.24  4663.9  510.73
  4673.9  509.83    4704  509.75    4724  508.09  4754.1  507.05  4991.9  501.27
  4992.4  500.77  4997.2  500.77  4997.7  501.27    5025  502.89  5065.3   503.3
  5135.9   505.4  5397.9  507.89  5526.4  510.92  5549.1  510.36  5569.2  510.83
    5607  512.52  5619.6  514.04  5692.7  517.02  5700.2  517.94  5811.1  522.32
#Mann= 4 ,-1 , 0
  4352.9    .035       0  4616.3     .07       0  4991.9     .05       0
  4997.7     .07       0
Bank Sta=4991.9,4997.7
XS Rating Curve= 0 ,0
Exp/Cntr=0.3,0.1

Type RM Length L Ch R = 1 ,13616   ,450,450,450
BEGIN DESCRIPTION:
KONDE BRANCH 29.0
END DESCRIPTION:
XS GIS Cut Line= 3
      2302575.03     13728825.01        2302925.       13728975.
      2303725.04     13729275.01
#Sta/Elev= 30
  4610.4  518.07  4624.9  518.25    4643  516.48  4664.8  515.99    4730   511.7
  4778.1   510.1  4784.4  510.15  4824.3  507.21  4871.5  505.03  4976.7  501.87
  4993.8  502.04  5006.3  500.97  5009.6  500.09  5010.1  499.59    5015  499.59
  5015.4  500.09  5036.6  500.28  5076.6  501.68  5091.7  501.35    5130  502.53
  5152.3  502.64  5177.2  503.56  5237.7  504.06  5247.5  504.84  5262.6  504.19
  5513.6  507.61  5664.9  511.29  5769.9  514.81  5781.5  515.75  5845.6  517.38
#Mann= 4 ,-1 , 0
  4610.4    .035       0  4778.1     .07       0  5009.6     .05       0
  5015.4     .07       0
Bank Sta=5009.6,5015.4
XS Rating Curve= 0 ,0
Exp/Cntr=0.3,0.1

Type RM Length L Ch R = 1 ,13166   ,479,479,479
BEGIN DESCRIPTION:
KONDE BRANCH 28.0
END DESCRIPTION:
XS GIS Cut Line= 3
      2302524.97     13729124.98        2302925.       13729375.
      2303725.04       13729475.
#Sta/Elev= 30
  4536.7  515.28  4559.7   515.2  4565.6  514.71  4572.1  512.27  4633.6  509.67
  4675.3  508.58  4711.9  506.78  4733.1  507.44    4739  506.05  4748.4  505.59
  4937.1  500.65  4982.5  498.19    4983  497.69  4987.9  497.69  4988.3  498.19
  5000.8  499.44    5011  499.28  5028.6  500.31  5068.9  499.95  5131.9  501.35
  5199.9  500.62  5320.8  502.62  5562.7  509.61  5610.6  511.83  5683.7  514.09
  5696.2  515.44  5713.9   514.9    5734  515.22  5794.2  517.65  5814.7  518.35
#Mann= 5 ,-1 , 0
  4536.7    .035       0  4633.6     .07       0  4982.5     .05       0
  4988.3     .07       0  5794.2     .05       0
Bank Sta=4982.5,4988.3
XS Rating Curve= 0 ,0
Exp/Cntr=0.3,0.1

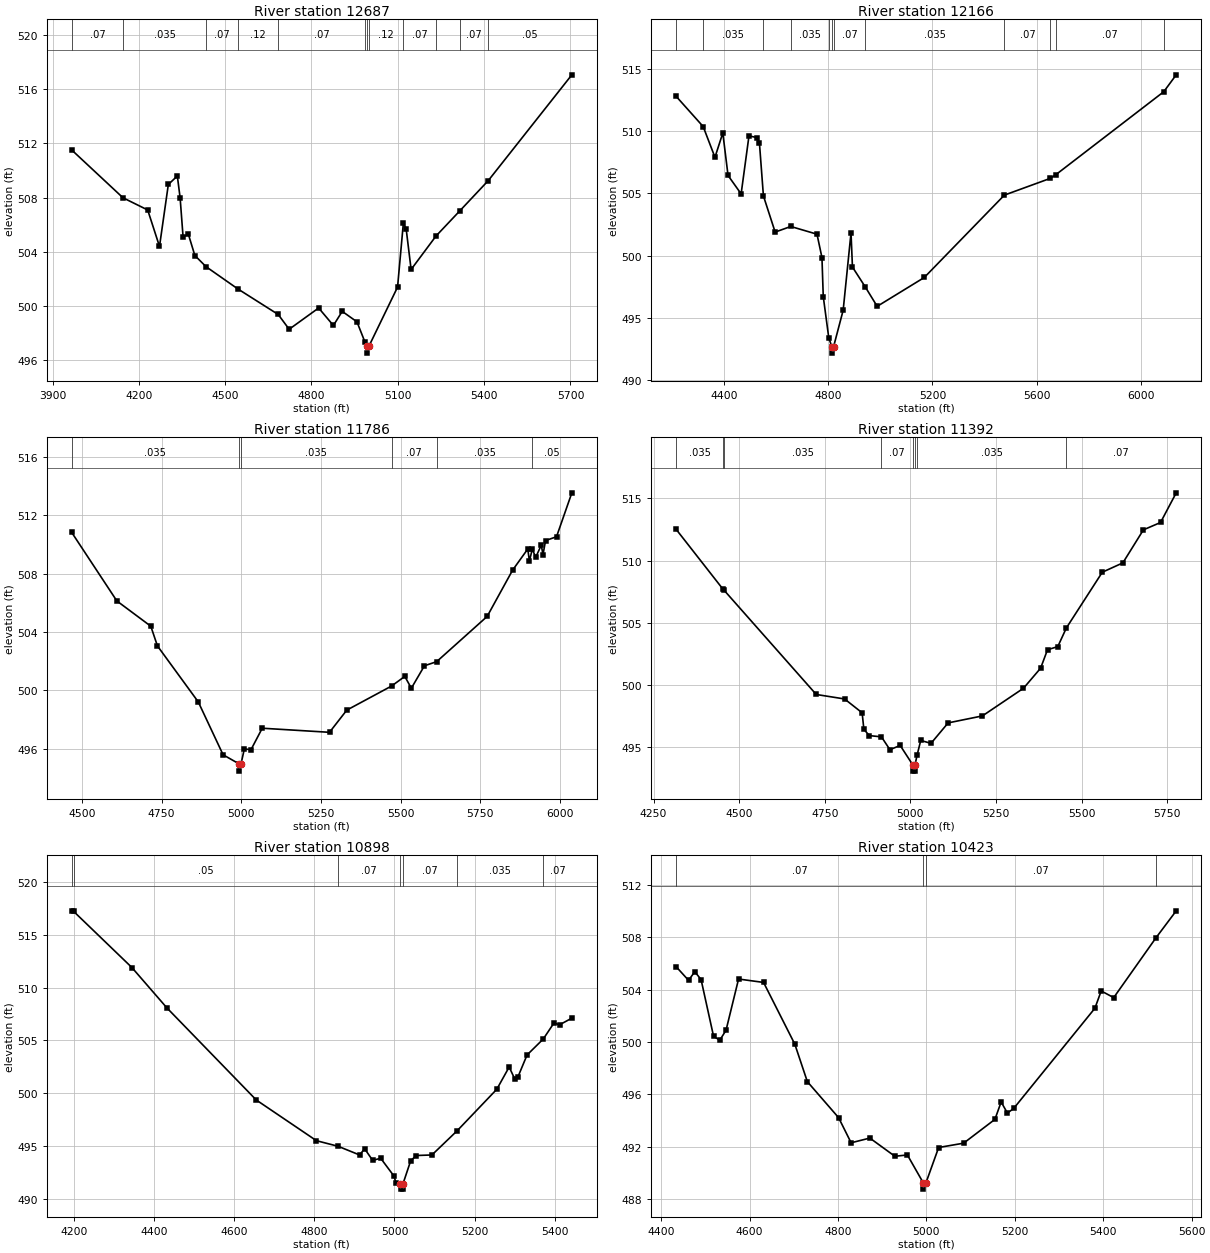
Type RM Length L Ch R = 1 ,12687   ,521,521,521
BEGIN DESCRIPTION:
KONDE BRANCH 27.0
END DESCRIPTION:
XS GIS Cut Line= 3
      2302067.08     13729551.48        2303075.       13729775.
       2303780.4     13729798.65
#Sta/Elev= 30
  3966.6  511.51  4144.9  507.98  4230.8  507.08  4271.8  504.39  4302.5  508.96
  4333.8  509.59  4343.5  507.97  4353.7   505.1  4372.3  505.28  4394.7  503.72
  4433.4   502.9  4543.1  501.27  4684.4  499.37  4722.4  498.28  4824.9  499.85
  4876.1  498.56  4906.8   499.6    4958  498.83  4985.7  497.34  4993.5  497.02
    4994  496.52  4999.4  497.02  5099.1  501.39  5119.3  506.12  5129.1  505.67
  5146.2  502.69  5232.8  505.16  5316.1  507.03  5414.5  509.25  5704.8  517.05
#Mann= 12 ,-1 , 0
  3966.6     .07       0  4144.9    .035       0  4433.4     .07       0
  4543.1     .12       0  4684.4     .07       0  4985.7     .12       0
  4993.5     .05       0  4999.4     .12       0  5119.3     .07       0
  5232.8     .12       0  5316.1     .07       0  5414.5     .05       0
Bank Sta=4993.5,4999.4
XS Rating Curve= 0 ,0
Exp/Cntr=0.3,0.1

Type RM Length L Ch R = 1 ,12166   ,380,380,380
BEGIN DESCRIPTION:
A19575
END DESCRIPTION:
XS GIS Cut Line= 3
      2301946.28     13730199.64      2302940.46     13730111.76
      2303851.13     13729974.61
#Sta/Elev= 30
  4216.1  512.81  4320.2  510.37  4365.4   507.9  4395.5  509.86  4415.6  506.44
  4465.8  504.96  4495.9  509.62    4526  509.49  4536.1  509.03  4551.3   504.8
  4596.3  501.89  4656.3  502.34  4756.9  501.72  4775.9  499.84  4780.9  496.71
    4802   493.4    4814  492.66  4814.5  492.16  4820.3  492.66  4857.3  495.61
  4887.4  501.83  4892.9  499.08  4942.1  497.48  4987.8  495.92  5168.5  498.24
  5475.7  504.86  5652.3  506.21  5672.5  506.49  6087.2  513.17  6135.1  514.53
#Mann= 12 ,-1 , 0
  4216.1     .05       0  4320.2    .035       0  4551.3     .12       0
  4656.3    .035       0    4802     .07       0    4814    .035       0
  4820.3     .07       0  4942.1    .035       0  5475.7     .07       0
  5652.3     .12       0  5672.5     .07       0  6087.2     .05       0
Bank Sta=4814,4820.3
XS Rating Curve= 0 ,0
Exp/Cntr=0.3,0.1

Type RM Length L Ch R = 1 ,11786   ,394,394,394
BEGIN DESCRIPTION:
KONDE BRANCH 26.0
END DESCRIPTION:
XS GIS Cut Line= 3
      2302475.03     13730774.97        2302875.       13730425.
      2303885.26     13730188.65
#Sta/Elev= 30
    4468  510.82  4609.8  506.12  4716.2  504.39    4737  503.04  4865.2   499.2
    4943  495.58    4993  494.96  4993.5  494.46  4999.3  494.96  5009.7  495.99
  5030.3  495.92  5065.8   497.4  5276.8  497.12    5331  498.64  5471.4  500.29
    5513  500.95  5533.5  500.14  5574.6  501.68  5612.9  501.96  5771.3  505.06
  5851.1  508.23  5898.7  509.68  5903.9  508.86  5912.8  509.66  5923.8  509.12
  5941.2  509.95  5946.4  509.29  5954.6  510.26  5988.9  510.52    6037  513.53
#Mann= 6 ,-1 , 0
    4468    .035       0    4993    .035       0  4999.3    .035       0
  5471.4     .07       0  5612.9    .035       0  5912.8     .05       0
Bank Sta=4993,4999.3
XS Rating Curve= 0 ,0
Exp/Cntr=0.3,0.1

Type RM Length L Ch R = 1 ,11392   ,494,494,494
BEGIN DESCRIPTION:
KONDE BRANCH 25.0
END DESCRIPTION:
XS GIS Cut Line= 3
      2302462.56      13730853.3      2302989.89      13730699.5
      2303900.82     13730688.52
#Sta/Elev= 30
  4315.7  512.51  4452.4  507.71  4455.4  507.63    4725  499.25  4807.8  498.89
    4859  497.78  4864.1  496.45  4880.1  495.95  4915.4  495.85  4940.1  494.82
  4970.1  495.16  5006.9   493.6  5007.4   493.1  5012.9   493.1  5013.4   493.6
  5019.5  494.39  5030.1  495.56  5060.1  495.33  5110.1  496.97  5210.1  497.53
  5330.1  499.75  5380.1  501.36  5400.2  502.84  5430.2  503.09  5455.1  504.58
  5560.2  509.06  5620.2  509.81  5680.2  512.46  5730.2  513.05    5776  515.43
#Mann= 8 ,-1 , 0
  4315.7    .035       0  4452.4     .05       0  4455.4    .035       0
  4915.4     .07       0  5006.9     .05       0  5013.4     .07       0
  5019.5    .035       0  5455.1     .07       0
Bank Sta=5006.9,5013.4
XS Rating Curve= 0 ,0
Exp/Cntr=0.3,0.1

Type RM Length L Ch R = 1 ,10898   ,475,475,475
BEGIN DESCRIPTION:
KONDE BRANCH 24.0
END DESCRIPTION:
XS GIS Cut Line= 3
      2302524.98       13731175.        2303325.       13731125.
        2303725.       13730925.
#Sta/Elev= 30
  4194.1  517.26  4198.9  517.21  4344.4   511.9  4432.1  508.07    4655  499.37
  4805.3  495.52  4859.5  494.99    4913  494.17  4925.5  494.76  4945.6  493.66
  4965.6  493.86  4998.5  492.19  5004.1  491.51  5014.8  491.44  5015.3  490.94
  5020.8  490.94  5021.3  491.44  5040.4  493.61  5054.4  494.12  5093.5  494.17
  5156.3  496.45  5255.6  500.39  5286.4  502.49  5300.3  501.36  5308.7  501.59
  5331.1  503.63  5371.6  505.14  5398.2  506.65  5412.1  506.48  5442.9  507.11
#Mann= 7 ,-1 , 0
  4194.1    .035       0  4198.9     .05       0  4859.5     .07       0
  5014.8     .05       0  5021.3     .07       0  5156.3    .035       0
  5371.6     .07       0
Bank Sta=5014.8,5021.3
XS Rating Curve= 0 ,0
Exp/Cntr=0.3,0.1

Type RM Length L Ch R = 1 ,10423   ,450,450,450
BEGIN DESCRIPTION:
KONDE BRANCH 23.0
END DESCRIPTION:
XS GIS Cut Line= 3
        2303125.       13731925.        2303525.       13731525.
      2303925.02     13731124.98
#Sta/Elev= 30
  4433.7  505.75    4462   504.7  4476.1  505.36  4490.3  504.76  4518.6  500.42
  4532.7  500.13  4546.8  500.89  4575.1   504.8  4631.7  504.54  4702.4  499.82
  4730.7  496.96  4801.4  494.21  4829.7  492.29  4872.1  492.65  4928.7  491.26
    4957  491.36  4992.6  489.25  4993.1  488.75  4999.2  489.25  5027.7  491.93
  5084.2  492.26    5155  494.08  5169.1  495.41  5183.2  494.56  5197.4  494.91
  5381.2  502.57  5395.4  503.89  5423.7  503.38  5519.1  507.94  5565.1  510.01
#Mann= 4 ,-1 , 0
  4433.7     .07       0  4992.6     .05       0  4999.2     .07       0
  5519.1    .035       0
Bank Sta=4992.6,4999.2
XS Rating Curve= 0 ,0
Exp/Cntr=0.3,0.1

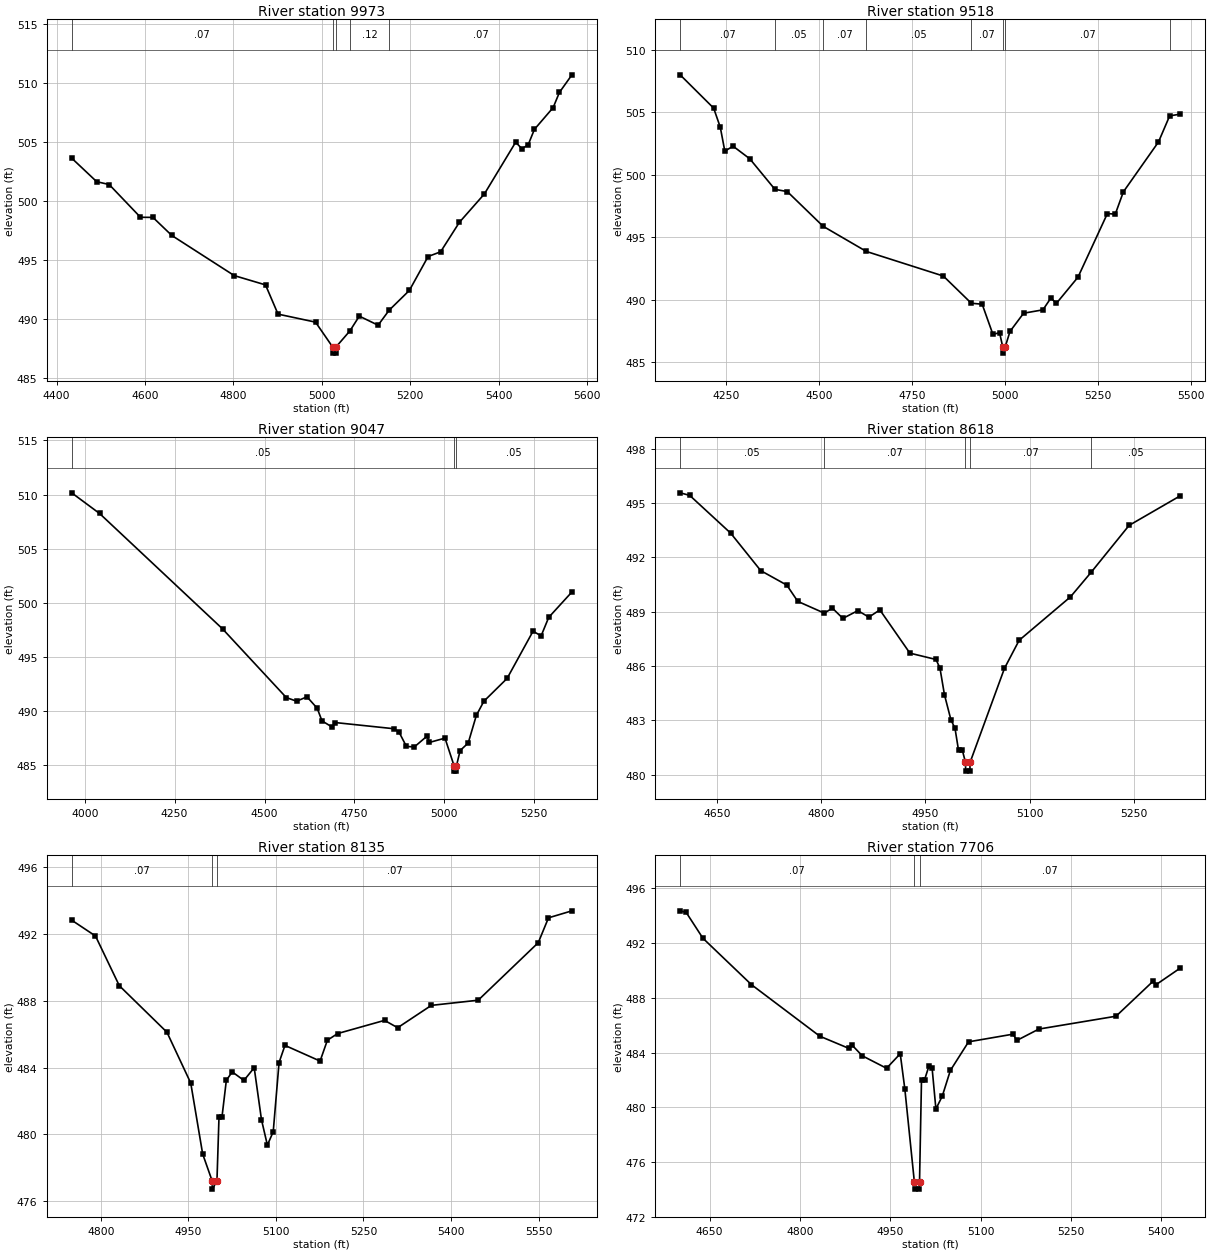
Type RM Length L Ch R = 1 ,9973    ,455,455,455
BEGIN DESCRIPTION:
KONDE BRANCH 22.0
END DESCRIPTION:
XS GIS Cut Line= 3
        2303375.       13732125.        2303775.       13731725.
      2304175.02     13731324.98
#Sta/Elev= 30
  4434.2  503.63  4490.8  501.63    4519  501.39  4589.8  498.61    4618   498.6
  4660.5  497.07  4801.9  493.66  4872.6  492.87  4900.9  490.39  4985.7  489.71
  5024.8  487.58  5025.3  487.08    5031  487.08  5031.5  487.58  5063.5  488.97
  5084.7  490.22  5127.2  489.45  5152.1  490.72  5197.9   492.4  5240.3  495.28
  5268.6  495.68    5311  498.18  5367.6  500.59  5438.3  504.98  5452.4  504.43
  5466.6  504.76  5480.7  506.07  5523.1  507.92  5537.3  509.21  5565.6   510.7
#Mann= 5 ,-1 , 0
  4434.2     .07       0  5024.8     .05       0  5031.5     .07       0
  5063.5     .12       0  5152.1     .07       0
Bank Sta=5024.8,5031.5
XS Rating Curve= 0 ,0
Exp/Cntr=0.3,0.1

Type RM Length L Ch R = 1 ,9518    ,471,471,471
BEGIN DESCRIPTION:
KONDE BRANCH 21.0
END DESCRIPTION:
XS GIS Cut Line= 3
      2303324.97     13732275.01        2304125.       13731925.
      2304374.98     13731525.04
#Sta/Elev= 30
    4127  508.02  4217.1  505.35    4235  503.81  4247.1   501.9  4269.3   502.3
  4314.2  501.29  4381.8  498.84  4415.1  498.66  4511.3  495.88  4627.7  493.86
  4834.6  491.89  4909.8  489.71    4939  489.63  4967.9  487.21  4985.8  487.35
  4994.2  486.21  4994.7  485.71  5000.9  486.21  5013.8  487.45  5050.4  488.91
  5102.3  489.18  5123.5  490.12  5138.8  489.71  5196.6   491.8  5275.6   496.9
  5296.8  496.85  5318.6  498.64    5413  502.64    5443  504.73  5471.9  504.87
#Mann= 8 ,-1 , 0
    4127     .07       0  4381.8     .05       0  4511.3     .07       0
  4627.7     .05       0  4909.8     .07       0  4994.2     .05       0
  5000.9     .07       0    5443     .05       0
Bank Sta=4994.2,5000.9
XS Rating Curve= 0 ,0
Exp/Cntr=0.3,0.1

Type RM Length L Ch R = 1 ,9047    ,429,429,429
BEGIN DESCRIPTION:
KONDE BRANCH 20.0
END DESCRIPTION:
XS GIS Cut Line= 3
      2303824.98     13733025.02        2304475.       13732225.
      2304775.03     13732024.98
#Sta/Elev= 30
  3963.7  510.16  4041.3  508.25  4383.2  497.59  4560.6  491.24  4589.4   490.9
  4618.1  491.31  4646.6  490.25  4659.8  489.09  4688.5   488.5  4696.4  488.93
  4859.5  488.36  4873.8  488.07  4894.7  486.72    4917  486.68  4952.1  487.68
  4958.6  487.09    5002  487.49  5027.2  484.94  5027.7  484.44  5033.5  484.44
    5034  484.94  5044.1  486.34  5066.6  487.04  5089.2  489.59  5110.2   490.9
  5174.8  493.01  5246.9  497.37  5269.4  496.94  5290.5  498.65  5355.1     501
#Mann= 3 ,-1 , 0
  3963.7     .05       0  5027.2     .05       0    5034     .05       0
Bank Sta=5027.2,5034
XS Rating Curve= 0 ,0
Exp/Cntr=0.3,0.1

Type RM Length L Ch R = 1 ,8618    ,483,483,483
BEGIN DESCRIPTION:
KONDE BRANCH 19.0
END DESCRIPTION:
XS GIS Cut Line= 3
      2304174.98     13732775.01        2304525.       13732575.
      2304825.03     13732474.99
#Sta/Elev= 30
  4597.3  495.57    4611  495.43    4670  493.34  4713.2  491.27  4750.7  490.47
  4766.5  489.57  4804.7  488.92  4816.2   489.2  4831.3  488.63  4852.9  489.06
  4868.7   488.7  4884.5   489.1  4927.7  486.71  4965.2  486.36  4970.9  485.89
  4977.4  484.41  4986.8  483.01  4992.5  482.57  4997.6  481.35  5003.1  481.35
  5007.5  480.69    5008  480.19  5013.9  480.19  5014.4  480.69  5063.7  485.87
  5084.8  487.42  5158.6  489.82  5188.8   491.2  5242.9  493.77  5316.7  495.41
#Mann= 5 ,-1 , 0
  4597.3     .05       0  4804.7     .07       0  5007.5     .05       0
  5014.4     .07       0  5188.8     .05       0
Bank Sta=5007.5,5014.4
XS Rating Curve= 0 ,0
Exp/Cntr=0.3,0.1

Type RM Length L Ch R = 1 ,8135    ,429,429,429
BEGIN DESCRIPTION:
KONDE BRANCH 18.0
END DESCRIPTION:
XS GIS Cut Line= 3
      2304374.97     13733075.01        2304625.       13733025.
      2305225.04       13733075.
#Sta/Elev= 30
  4750.1  492.84  4790.9  491.89  4831.7  488.91  4913.3  486.12  4954.1  483.07
  4974.5  478.82  4990.7  477.21  4991.2  476.71    4999  477.21  5002.5  481.03
  5007.6  481.03  5015.1  483.24  5025.2  483.74  5045.2  483.23  5062.8  483.99
  5075.3  480.87  5085.4  479.35  5095.4  480.15  5105.4   484.3  5115.5  485.33
  5175.7  484.39  5188.2  485.64  5205.8  486.04  5286.1  486.83  5308.6  486.39
  5366.3  487.73  5446.6  488.04  5549.5  491.49    5567  492.98  5607.2   493.4
#Mann= 3 ,-1 , 0
  4750.1     .07       0  4990.7     .05       0    4999     .07       0
Bank Sta=4990.7,4999
XS Rating Curve= 0 ,0
Exp/Cntr=0.3,0.1

Type RM Length L Ch R = 1 ,7706    ,490,490,490
BEGIN DESCRIPTION:
KONDE BRANCH 17.0
END DESCRIPTION:
XS GIS Cut Line= 3
      2304375.02       13733425.        2304775.       13733375.
        2305175.       13733225.
#Sta/Elev= 30
  4601.2  494.34  4611.3  494.22    4639  492.34  4719.6  488.95    4833  485.19
  4880.8  484.31  4885.9  484.57  4903.5  483.76  4943.8  482.85  4966.5  483.91
  4974.1  481.35    4990  474.53  4990.5  474.03    4998  474.03  4998.5  474.53
  5001.8  482.03    5007  482.03  5014.1     483  5019.4  482.86  5025.7  479.88
  5036.3  480.82  5049.7  482.69  5079.9  484.78  5153.8  485.34    5160  484.88
  5196.5  485.71  5324.7  486.65  5386.1   489.2  5391.4  488.96  5431.5  490.17
#Mann= 3 ,-1 , 0
  4601.2     .07       0    4990     .05       0  4998.5     .07       0
Bank Sta=4990,4998.5
XS Rating Curve= 0 ,0
Exp/Cntr=0.3,0.1

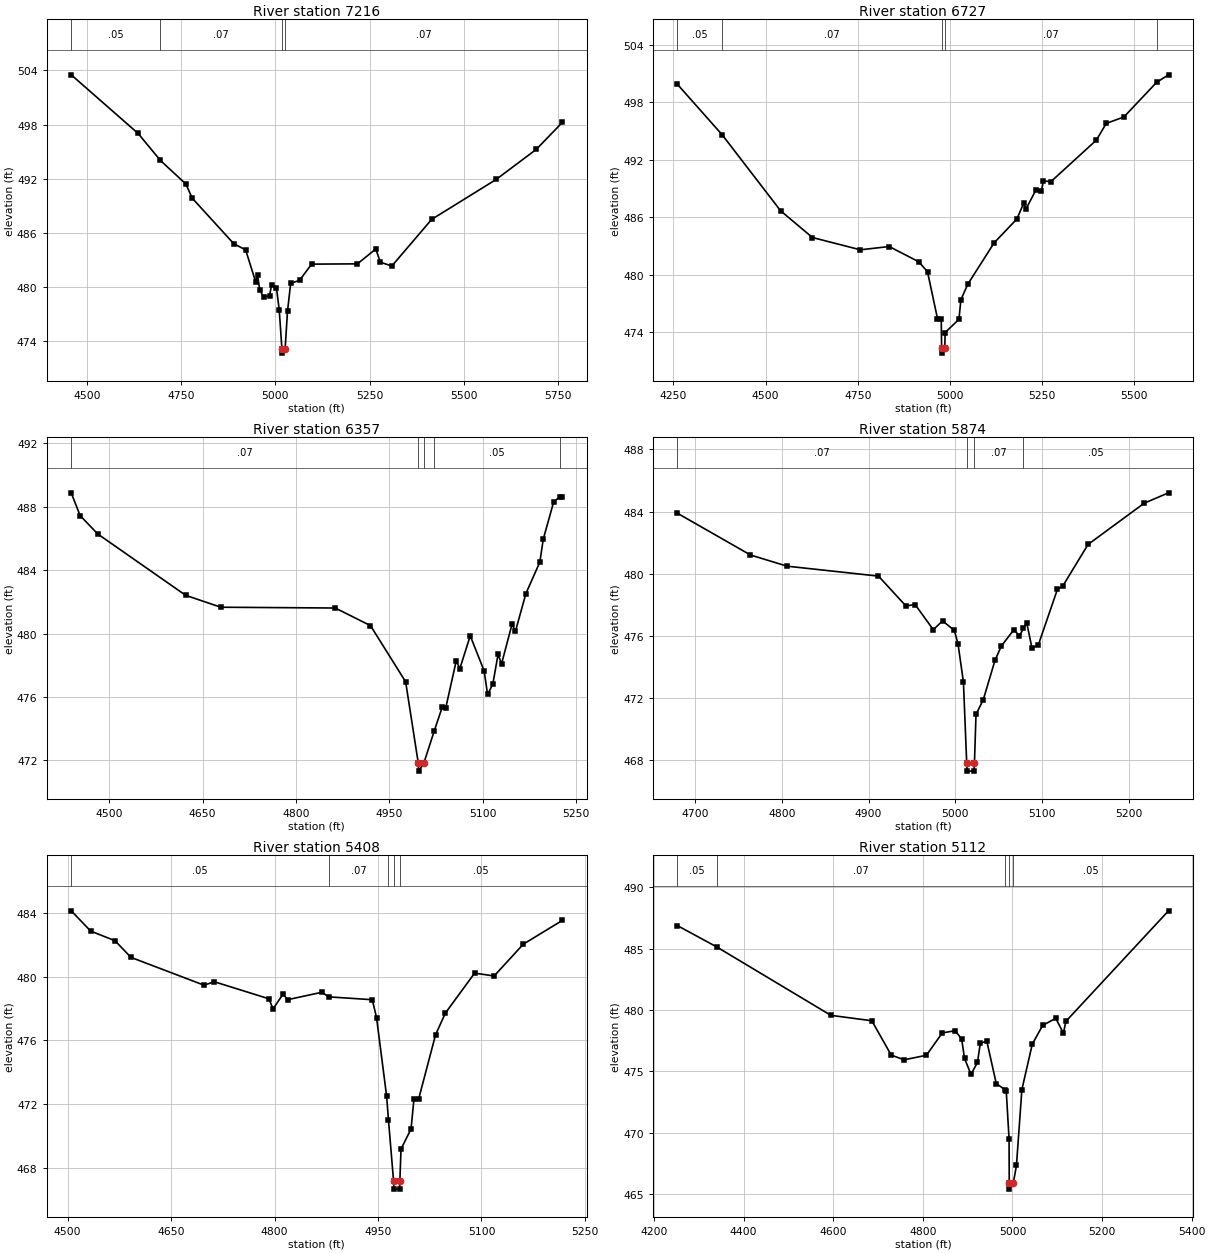
Type RM Length L Ch R = 1 ,7216    ,489,489,489
BEGIN DESCRIPTION:
KONDE BRANCH 16.0
END DESCRIPTION:
XS GIS Cut Line= 3
      2304159.86     13733654.67        2304675.       13733825.
      2305390.11     13734088.55
#Sta/Elev= 30
  4457.7   503.5  4635.4  497.01  4694.7  494.02  4762.3  491.41  4779.1  489.85
  4889.2  484.82    4921  484.12  4947.4  480.62  4952.7  481.38  4958.1  479.74
  4968.7  478.89  4984.4  479.05  4989.7   480.2  5002.9  479.92  5010.2  477.49
  5017.3   473.2  5017.8   472.7  5025.9   473.2  5032.2  477.34  5040.6  480.43
  5064.2  480.75  5096.2  482.55    5218  482.58  5266.7  484.23  5278.8  482.76
  5309.3  482.34  5415.1   487.5  5586.4  491.92    5693  495.25  5762.4  498.24
#Mann= 4 ,-1 , 0
  4457.7     .05       0  4694.7     .07       0  5017.3     .05       0
  5025.9     .07       0
Bank Sta=5017.3,5025.9
XS Rating Curve= 0 ,0
Exp/Cntr=0.3,0.1

Type RM Length L Ch R = 1 ,6727    ,370,370,370
BEGIN DESCRIPTION:
KONDE BRANCH 15.0
END DESCRIPTION:
XS GIS Cut Line= 3
      2304198.34     13733830.46      2304731.14     13734203.96
       2305395.8     13734357.77
#Sta/Elev= 30
  4260.4  499.87  4382.1  494.59  4540.8  486.65  4627.1  483.86    4757  482.58
  4835.4  482.92  4915.6  481.33  4939.3  480.29  4966.4   475.4  4976.6  475.39
  4977.6  472.29  4978.1  471.79  4986.3  472.29  4987.1  473.94  5024.7  475.32
  5029.8  477.35  5048.5  478.98  5120.4  483.32  5181.9   485.8  5200.6  487.47
  5205.8  486.79  5233.2   488.8  5248.5  488.76  5253.8  489.77  5274.3   489.7
  5397.5  494.03  5424.4  495.78  5472.3  496.45  5561.2  500.07  5593.3  500.85
#Mann= 5 ,-1 , 0
  4260.4     .05       0  4382.1     .07       0  4977.6     .05       0
  4986.3     .07       0  5561.2     .05       0
Bank Sta=4977.6,4986.3
XS Rating Curve= 0 ,0
Exp/Cntr=0.3,0.1

Type RM Length L Ch R = 1 ,6357    ,483,483,483
BEGIN DESCRIPTION:
KONDE BRANCH 14.0
END DESCRIPTION:
XS GIS Cut Line= 3
      2304224.98     13734124.98        2304625.       13734525.
      2304724.99     13734724.98
#Sta/Elev= 30
  4438.9  488.87  4453.1  487.44  4481.4  486.28  4622.8  482.41  4679.3  481.66
  4863.2  481.61  4919.8   480.5  4976.3  476.96  4996.6  471.83  4997.1  471.33
  5005.5  471.83  5022.3  473.87  5035.4   475.4  5040.9  475.34  5057.7   478.3
  5063.3  477.78  5080.1  479.86  5102.4  477.65    5108  476.16  5116.4  476.82
  5124.8  478.69  5130.4  478.09  5147.2  480.58  5152.8  480.15  5169.5  482.52
  5191.9   484.5  5197.5  485.96  5214.2   488.3  5223.6   488.6  5228.2  488.62
#Mann= 5 ,-1 , 0
  4438.9     .07       0  4996.6     .05       0  5005.5     .07       0
  5022.3     .05       0  5223.6     .07       0
Bank Sta=4996.6,5005.5
XS Rating Curve= 0 ,0
Exp/Cntr=0.3,0.1

Type RM Length L Ch R = 1 ,5874    ,466,466,466
BEGIN DESCRIPTION:
KONDE BRANCH 13.0
END DESCRIPTION:
XS GIS Cut Line= 3
        2304075.     13734325.01        2304175.       13734625.
      2304324.99     13734824.99
#Sta/Elev= 30
  4679.5   483.9  4763.8  481.21    4806  480.49  4911.4  479.85    4943  477.93
  4953.6  478.02  4974.6   476.4  4985.2  476.97  4998.8  476.36    5003  475.51
  5009.3  473.04  5013.1   467.8  5013.6   467.3  5021.5   467.3    5022   467.8
  5023.8  470.95  5032.2   471.9  5045.7  474.43    5053  475.35  5067.6  476.41
  5073.8  475.99  5078.5  476.48  5082.2  476.86  5088.4   475.2  5095.7  475.43
  5117.6  478.99  5123.8  479.21    5153  481.89  5217.6  484.54  5245.7  485.21
#Mann= 4 ,-1 , 0
  4679.5     .07       0  5013.1     .05       0    5022     .07       0
  5078.5     .05       0
Bank Sta=5013.1,5022
XS Rating Curve= 0 ,0
Exp/Cntr=0.3,0.1

Type RM Length L Ch R = 1 ,5408    ,296,296,296
BEGIN DESCRIPTION:
KONDE BRANCH 12.0
END DESCRIPTION:
XS GIS Cut Line= 3
      2303524.98     13734474.97        2303825.       13734875.
      2303975.02     13735025.02
#Sta/Elev= 30
  4505.2  484.14  4533.4  482.87  4568.8  482.26  4591.7  481.22  4697.9  479.47
  4712.5  479.69  4791.7  478.62  4797.9  477.99  4812.5  478.92  4818.8  478.56
  4868.8  479.03  4878.3  478.74  4941.7  478.56  4947.9  477.44  4962.5  472.51
  4965.2  471.01  4972.6  467.17  4973.1  466.67  4981.2  466.67  4981.7  467.17
  4983.4  469.19  4997.9  470.44  5002.1   472.3  5008.8   472.3  5033.5  476.36
  5047.7  477.72  5090.1  480.23  5118.4  480.05  5160.8  482.05  5217.4  483.54
#Mann= 5 ,-1 , 0
  4505.2     .05       0  4878.3     .07       0  4965.2     .05       0
  4972.6     .05       0  4981.7     .05       0
Bank Sta=4972.6,4981.7
XS Rating Curve= 0 ,0
Exp/Cntr=0.3,0.1

Type RM Length L Ch R = 1 ,5112    ,197,197,197
BEGIN DESCRIPTION:
A19574
END DESCRIPTION:
XS GIS Cut Line= 3
      2303154.67     13734495.07      2303616.08     13735082.83
       2303934.7     13735225.66
#Sta/Elev= 30
  4251.9  486.88  4339.9  485.14  4594.7  479.57    4686  479.13  4729.4  476.33
  4758.3  475.95    4808  476.32  4843.3  478.14  4872.2  478.32  4886.6  477.64
    4893  476.07  4907.4  474.76  4921.9  475.74  4928.2   477.3  4942.7  477.47
  4963.8  474.02  4983.5  473.51  4986.1  473.43  4992.4  469.51  4992.8  465.92
  4993.3  465.42  5001.9  465.92  5008.9  467.35    5021  473.52  5044.2  477.22
  5067.4  478.75  5096.6  479.33  5113.7  478.12  5119.2  479.08  5348.3  488.08
#Mann= 5 ,-1 , 0
  4251.9     .05       0  4339.9     .07       0  4983.5     .05       0
  4992.8     .05       0  5001.9     .05       0
Bank Sta=4992.8,5001.9
XS Rating Curve= 0 ,0
Exp/Cntr=0.3,0.1