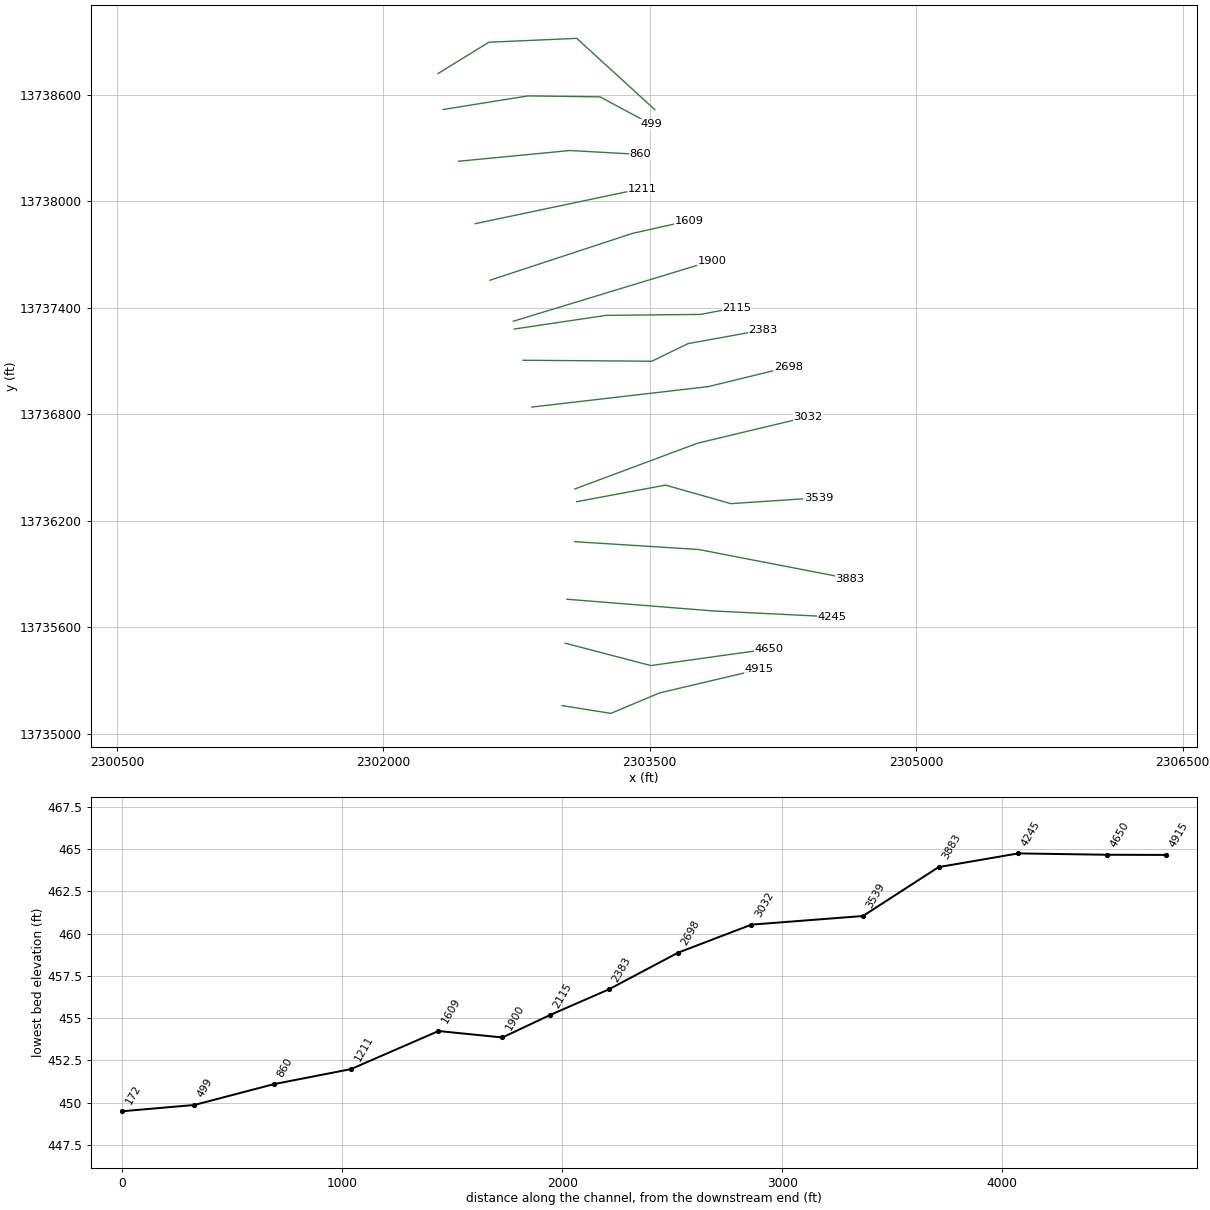
HEC-RAS study KONDE BRANCH.prj: KONDE BRANCH Base Level Engineering

--- KONDE BRANCH.g01 (geometry) --- (continued)

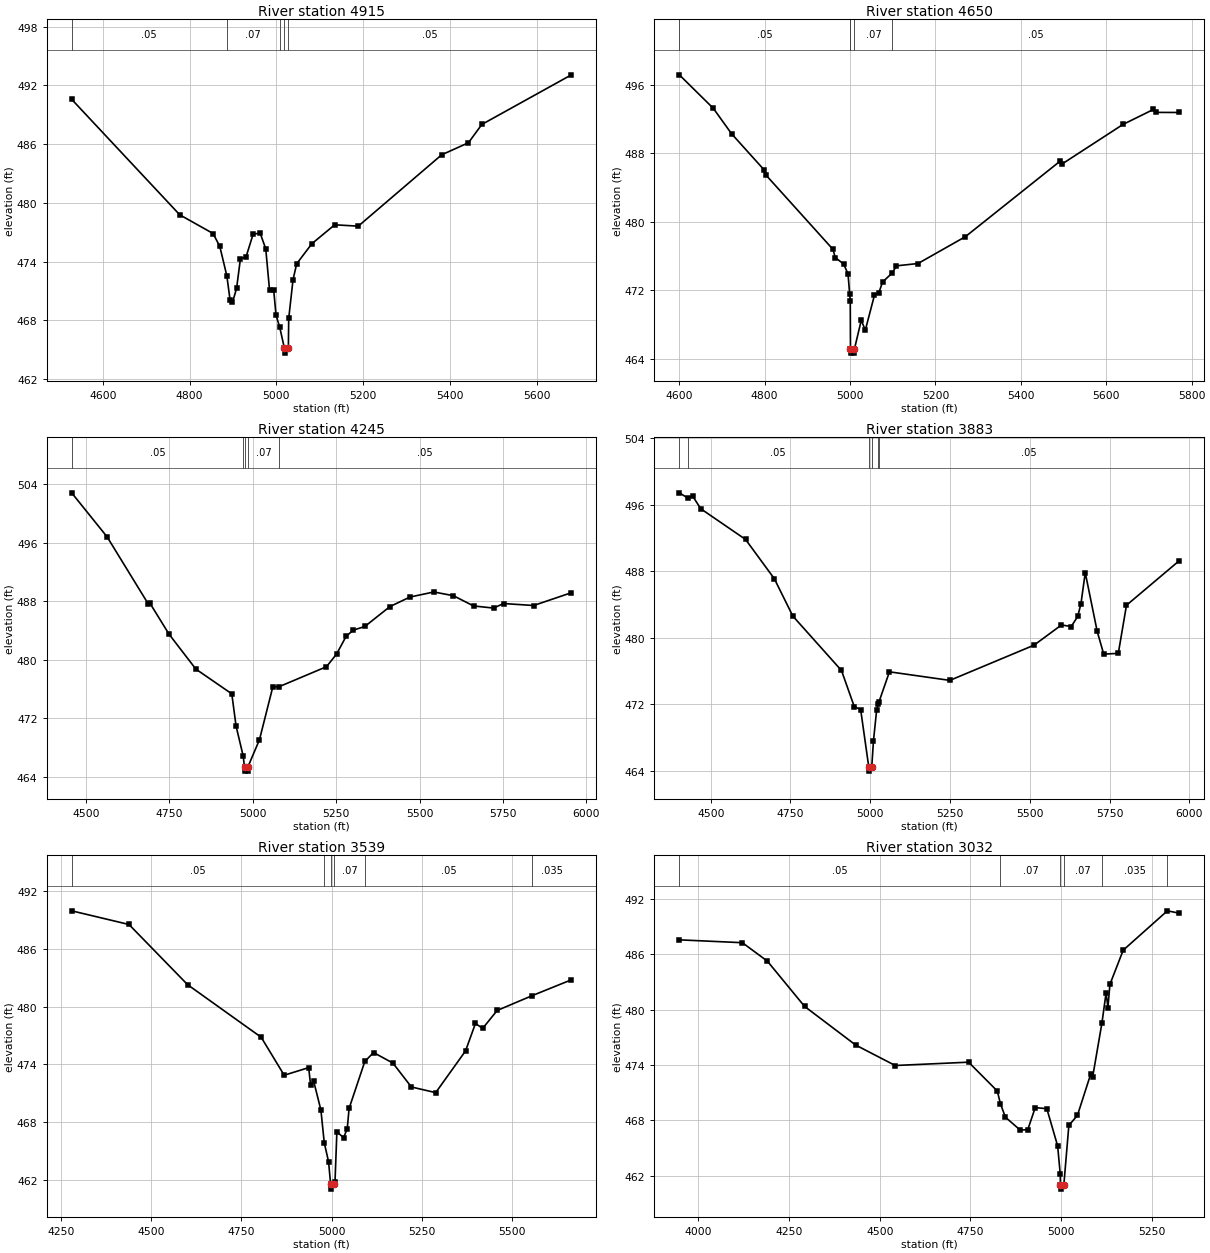
Type RM Length L Ch R = 1 ,4915    ,265,265,265
BEGIN DESCRIPTION:
KONDE BRANCH 11.0
END DESCRIPTION:
XS GIS Cut Line= 4
      2303006.36     13735159.73      2303281.02     13735115.78
      2303555.66     13735231.13      2304115.93     13735362.96
#Sta/Elev= 30
  4528.4  490.58  4777.5  478.78  4854.3  476.87  4869.8  475.55    4886  472.55
  4893.6  470.03    4899  469.83  4908.5  471.27  4917.3  474.29  4930.2  474.47
  4946.5  476.79  4962.7  476.92  4975.7   475.3  4984.4   471.1    4994  471.09
  4999.4  468.52  5007.9  467.29  5018.7  465.15  5019.2  464.65  5027.8  465.15
  5028.6  468.19  5038.6  472.17    5047  473.78    5082  475.83  5134.6  477.76
  5188.9  477.62  5381.1  484.91  5442.8  486.14  5473.6  488.01    5680  493.08
#Mann= 5 ,-1 , 0
  4528.4     .05       0    4886     .07       0  5007.9     .05       0
  5018.7     .05       0  5027.8     .05       0
Bank Sta=5018.7,5027.8
XS Rating Curve= 0 ,0
Exp/Cntr=0.3,0.1

Type RM Length L Ch R = 1 ,4650    ,405,405,405
BEGIN DESCRIPTION:
A19573
END DESCRIPTION:
XS GIS Cut Line= 3
      2303022.88     13735511.27      2303506.23     13735384.94
      2304170.42     13735478.25
#Sta/Elev= 30
  4600.3  497.18    4680  493.26  4722.7  490.29  4798.4   486.1  4803.5  485.45
  4960.2  476.78  4965.3  475.83  4984.9  475.08  4995.3  473.93  4999.2  471.59
  5000.6  470.75  5001.1  465.16  5001.6  464.66    5010  464.66  5010.5  465.16
  5026.3  468.49  5035.9  467.35  5057.3  471.44  5067.6  471.73  5076.3  472.97
    5099  474.03  5108.7  474.86  5159.2  475.13  5270.3  478.27  5491.5  487.07
  5496.6  486.76  5639.2  491.38  5710.4  493.13  5715.5  492.79  5770.6  492.78
#Mann= 5 ,-1 , 0
  4600.3     .05       0  4999.2     .07       0  5001.1     .05       0
  5010.5     .07       0    5099     .05       0
Bank Sta=5001.1,5010.5
XS Rating Curve= 0 ,0
Exp/Cntr=0.3,0.1

Type RM Length L Ch R = 1 ,4245    ,362,362,362
BEGIN DESCRIPTION:
A19572
END DESCRIPTION:
XS GIS Cut Line= 3
      2303033.88     13735758.45      2303857.77     13735692.54
      2304527.94     13735659.58
#Sta/Elev= 30
  4457.6   502.8  4563.8  496.78  4686.7  487.64  4691.7  487.74  4749.7  483.45
  4829.9  478.69  4937.5  475.31  4950.3   470.9  4971.6  466.82  4975.7  465.24
  4976.2  464.74  4984.6  464.74  4985.1  465.24  5020.5  469.05  5060.4  476.26
  5078.9  476.28  5221.2  479.02  5251.3  480.74  5280.2  483.18  5301.4  484.02
  5336.1  484.52  5411.5  487.25  5471.6  488.55    5543  489.24  5601.7  488.73
  5661.8  487.33  5721.9  487.04  5751.9  487.66    5842  487.39  5955.1  489.14
#Mann= 5 ,-1 , 0
  4457.6     .05       0  4971.6     .07       0  4975.7     .05       0
  4985.1     .07       0  5078.9     .05       0
Bank Sta=4975.7,4985.1
XS Rating Curve= 0 ,0
Exp/Cntr=0.3,0.1

Type RM Length L Ch R = 1 ,3883    ,344,344,344
BEGIN DESCRIPTION:
A19571
END DESCRIPTION:
XS GIS Cut Line= 3
       2303077.8     13736082.53      2303775.38     13736038.59
      2304626.82      13735873.8
#Sta/Elev= 30
  4401.7  497.42  4427.6  496.81    4443  497.05    4469   495.5  4609.3  491.81
  4699.5  487.08  4757.4  482.59  4909.9  476.04    4950  471.69    4970  471.34
  4995.4  464.43  4995.9  463.93  5004.8  464.43  5010.1  467.56  5020.1  471.27
  5025.3  471.98  5027.2  472.24  5060.2  475.88  5249.5  474.85  5513.5  479.09
  5599.4  481.52  5629.9  481.33  5650.3  482.54  5660.5  484.09  5673.9  487.81
  5711.4  480.74  5731.8  478.01  5777.5   478.1  5803.1  483.89  5967.9  489.23
#Mann= 6 ,-1 , 0
  4401.7     .07       0  4427.6     .05       0  4995.4     .05       0
  5004.8     .05       0  5025.3     .07       0  5027.2     .05       0
Bank Sta=4995.4,5004.8
XS Rating Curve= 0 ,0
Exp/Cntr=0.3,0.1

Type RM Length L Ch R = 1 ,3539    ,507,507,507
BEGIN DESCRIPTION:
A19570
END DESCRIPTION:
XS GIS Cut Line= 4
      2303088.74     13736307.74      2303588.62     13736401.12
      2303956.64     13736296.76      2304450.49     13736329.68
#Sta/Elev= 30
  4279.3  489.97  4438.3  488.55    4601  482.29  4804.9  476.83  4868.8  472.88
  4936.7  473.67  4941.9  471.88  4950.4  472.28  4970.6  469.26  4979.9  465.86
  4991.9  463.88  4997.6  461.54  4998.1  461.04    5007  461.54  5009.7  461.79
  5014.9     467  5033.5  466.39  5043.6  467.31  5048.8  469.43  5092.4  474.31
  5116.6  475.24  5170.4  474.14  5221.5  471.66    5289  471.07  5371.8  475.41
  5399.2  478.26  5419.3  477.75  5459.4  479.61  5555.7  481.14  5665.3   482.8
#Mann= 6 ,-1 , 0
  4279.3     .05       0  4979.9     .07       0  4997.6     .05       0
    5007     .07       0  5092.4     .05       0  5555.7    .035       0
Bank Sta=4997.6,5007
XS Rating Curve= 0 ,0
Exp/Cntr=0.3,0.1

Type RM Length L Ch R = 1 ,3032    ,334,334,334
BEGIN DESCRIPTION:
A19569
END DESCRIPTION:
XS GIS Cut Line= 3
      2303077.76     13736379.14      2303769.88     13736637.32
      2304390.31     13736785.56
#Sta/Elev= 30
    3948  487.59  4121.6  487.28  4190.5  485.28  4292.9  480.37  4433.8  476.17
  4542.7  473.95  4744.9  474.31  4823.9  471.18  4832.5  469.81  4846.2  468.34
  4887.3  466.93  4907.9  466.99  4928.4  469.38  4960.4  469.26  4990.1  465.23
  4997.4  462.13  4997.7  461.03  4998.2  460.53  5007.3  461.03    5021  467.44
  5044.6  468.53  5081.5  473.05  5086.7  472.73  5112.3   478.6  5123.6  481.84
  5128.7  480.24  5134.1  482.75  5170.8  486.47  5292.4  490.74  5324.6  490.49
#Mann= 6 ,-1 , 0
    3948     .05       0  4832.5     .07       0  4997.7     .05       0
  5007.3     .07       0  5112.3    .035       0  5292.4     .05       0
Bank Sta=4997.7,5007.3
XS Rating Curve= 0 ,0
Exp/Cntr=0.3,0.1

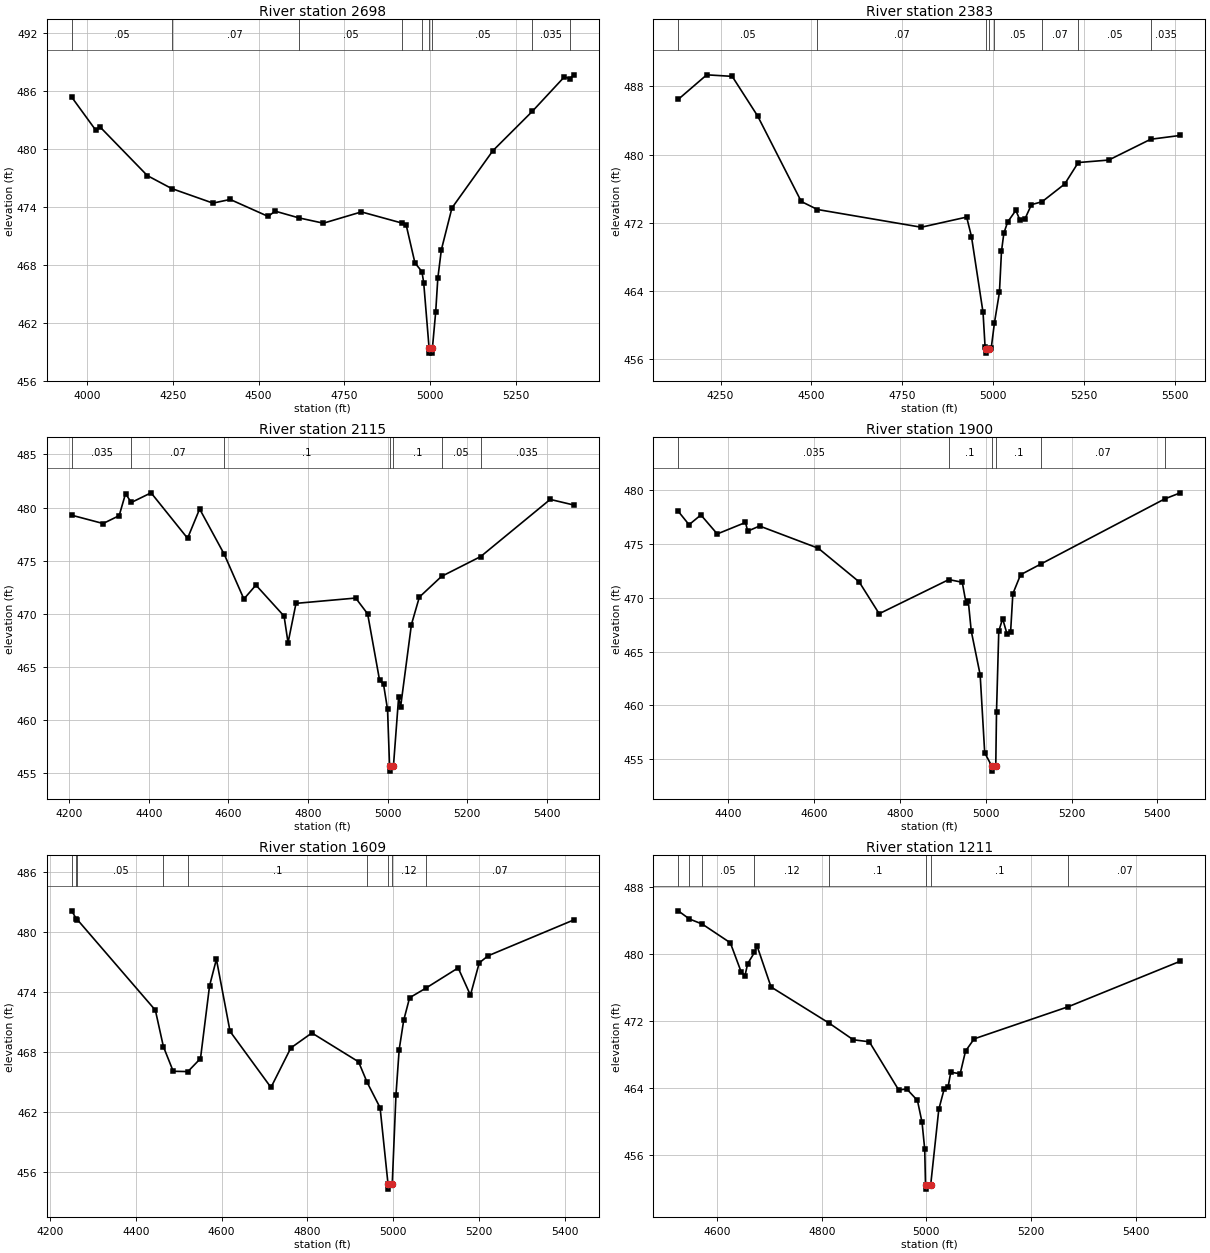
Type RM Length L Ch R = 1 ,2698    ,315,315,315
BEGIN DESCRIPTION:
A19568
END DESCRIPTION:
XS GIS Cut Line= 3
      2302836.05     13736840.55      2303830.31      13736955.9
      2304280.39     13737065.68
#Sta/Elev= 30
  3955.1  485.38  4024.5  481.99  4038.4  482.27  4175.5  477.26  4246.4  475.92
  4366.8  474.41  4417.1  474.79  4527.9  473.03    4548  473.58  4617.5  472.88
  4688.9  472.33  4799.7   473.5  4918.4  472.34  4930.5  472.12  4955.9  468.21
  4976.2  467.32  4981.4  466.18  4997.2  459.37  4997.7  458.87  5006.3  458.87
  5006.8  459.37  5016.5  463.17  5022.6  466.63  5032.9  469.57  5063.8  473.91
  5183.2  479.84    5298  483.91  5391.7  487.49  5407.1   487.3  5419.3   487.7
#Mann= 9 ,-1 , 0
  3955.1     .05       0  4246.4     .07       0  4617.5     .05       0
  4918.4     .07       0  4976.2     .05       0  4997.2     .05       0
  5006.8     .05       0    5298    .035       0  5407.1     .05       0
Bank Sta=4997.2,5006.8
XS Rating Curve= 0 ,0
Exp/Cntr=0.3,0.1

Type RM Length L Ch R = 1 ,2383    ,268,268,268
BEGIN DESCRIPTION:
A19567
END DESCRIPTION:
XS GIS Cut Line= 4
      2302786.61     13737104.21      2303511.72     13737098.72
      2303714.96     13737197.59      2304137.88     13737274.49
#Sta/Elev= 30
  4133.7  486.47  4212.1  489.35  4282.1  489.17  4352.1  484.52  4472.1  474.49
  4516.5  473.55  4802.1  471.47    4927  472.66  4940.3  470.37  4972.1  461.47
  4977.7  457.43    4980   457.2  4980.5   456.7  4989.6   457.2  4994.6  457.29
  5003.5  460.27  5017.2  463.84  5022.8  468.64  5029.3  470.76  5039.7  472.08
  5062.3  473.45  5073.8  472.28  5087.4  472.45  5105.2  474.12  5134.4  474.46
  5196.7  476.54    5234  479.06  5317.7  479.35  5433.1  481.79  5514.7  482.24
#Mann= 8 ,-1 , 0
  4133.7     .05       0  4516.5     .07       0    4980     .05       0
  4989.6     .07       0  5003.5     .05       0  5134.4     .07       0
    5234     .05       0  5433.1    .035       0
Bank Sta=4980,4989.6
XS Rating Curve= 0 ,0
Exp/Cntr=0.3,0.1

Type RM Length L Ch R = 1 ,2115    ,215,215,215
BEGIN DESCRIPTION:
A19566
END DESCRIPTION:
XS GIS Cut Line= 4
      2302737.21     13737279.98      2303253.55     13737356.89
      2303786.36     13737362.38      2303989.58     13737400.82
#Sta/Elev= 30
  4206.2  479.28  4284.9   478.5  4325.3  479.24  4341.3  481.31  4355.8  480.48
  4405.5  481.39  4497.2  477.11  4527.5  479.87  4589.4   475.6  4638.7  471.39
    4669   472.7  4739.7  469.78  4749.7  467.27  4769.7  470.98  4919.7  471.48
  4949.7  469.99  4979.7  463.74  4989.7  463.35  4999.7     461  5004.8  455.68
  5005.3  455.18  5014.6  455.68  5027.6  462.14  5032.6  461.24  5059.7  468.98
  5079.7  471.57  5135.4  473.52  5233.9  475.39  5408.5  480.77  5467.9  480.24
#Mann= 7 ,-1 , 0
  4206.2    .035       0  4355.8     .07       0  4589.4      .1       0
  5004.8     .05       0  5014.6      .1       0  5135.4     .05       0
  5233.9    .035       0
Bank Sta=5004.8,5014.6
XS Rating Curve= 0 ,0
Exp/Cntr=0.3,0.1

Type RM Length L Ch R = 1 ,1900    ,291,291,291
BEGIN DESCRIPTION:
A19565
END DESCRIPTION:
XS GIS Cut Line= 2
      2302731.76     13737323.94       2303851.1     13737664.13
#Sta/Elev= 30
  4283.5  478.06  4308.7  476.81  4336.3  477.72  4374.4  475.95  4440.2  477.02
  4445.4  476.21    4473  476.69  4609.8  474.62    4705  471.49  4751.7  468.52
  4914.1   471.7  4945.3  471.45  4954.2  469.49  4959.4  469.68  4966.2  466.92
    4987  462.84  4997.6  455.57  5013.6  454.36  5014.1  453.86  5023.4  454.36
  5025.1  459.35  5030.4   466.9  5039.4  468.06  5049.9  466.59    5058  466.86
  5063.2  470.38  5081.2  472.15  5129.9  473.18  5416.9  479.21  5453.4  479.78
#Mann= 6 ,-1 , 0
  4283.5    .035       0  4914.1      .1       0  5013.6     .05       0
  5023.4      .1       0  5129.9     .07       0  5416.9     .05       0
Bank Sta=5013.6,5023.4
XS Rating Curve= 0 ,0
Exp/Cntr=0.3,0.1

Type RM Length L Ch R = 1 ,1609    ,398,398,398
BEGIN DESCRIPTION:
A19564
END DESCRIPTION:
XS GIS Cut Line= 3
      2302599.89     13737554.63      2303401.86     13737818.29
      2303720.26     13737889.65
#Sta/Elev= 30
  4250.6  482.13  4261.3  481.31  4263.9  481.23  4445.5  472.17  4464.2  468.52
  4487.1  466.05  4521.3  466.02  4550.7  467.33  4571.8  474.61  4587.8  477.28
  4619.6  470.05    4715  464.43  4761.3  468.39  4810.4  469.89  4919.2     467
  4939.3  464.93  4969.4   462.4  4987.9  454.74  4988.4  454.24  4997.7  454.74
  5006.4  463.68  5013.9  468.23  5024.4  471.15  5038.2  473.42  5076.1  474.38
  5151.4  476.41    5180  473.68  5200.5  476.91    5221  477.62  5421.1  481.22
#Mann= 9 ,-1 , 0
  4250.6     .05       0  4261.3     .07       0  4263.9     .05       0
  4464.2     .12       0  4521.3      .1       0  4939.3     .12       0
  4987.9     .05       0  4997.7     .12       0  5076.1     .07       0
Bank Sta=4987.9,4997.7
XS Rating Curve= 0 ,0
Exp/Cntr=0.3,0.1

Type RM Length L Ch R = 1 ,1211    ,351,351,351
BEGIN DESCRIPTION:
A19563
END DESCRIPTION:
XS GIS Cut Line= 2
      2302517.55     13737873.23      2303456.76     13738070.96
#Sta/Elev= 30
  4525.7  485.14  4546.9  484.17  4571.4  483.57  4625.3  481.33  4645.7  477.91
  4653.2  477.39  4658.4  478.84  4671.4  480.18  4676.4  480.96  4703.1  476.07
  4814.2  471.76  4860.3  469.78    4891  469.54  4947.1   463.8  4962.5  463.92
    4983  462.55  4991.8  459.94  4996.9  456.73  4998.4  452.49  4998.9  451.99
  5008.3  452.49  5023.8  461.49  5034.1  463.92  5041.6  464.17  5046.7  465.91
  5064.7  465.74  5074.9  468.43  5091.4  469.89  5271.4  473.72  5485.5  479.14
#Mann= 8 ,-1 , 0
  4525.7     .05       0  4546.9     .07       0  4571.4     .05       0
  4671.4     .12       0  4814.2      .1       0  4998.4     .05       0
  5008.3      .1       0  5271.4     .07       0
Bank Sta=4998.4,5008.3
XS Rating Curve= 0 ,0
Exp/Cntr=0.3,0.1

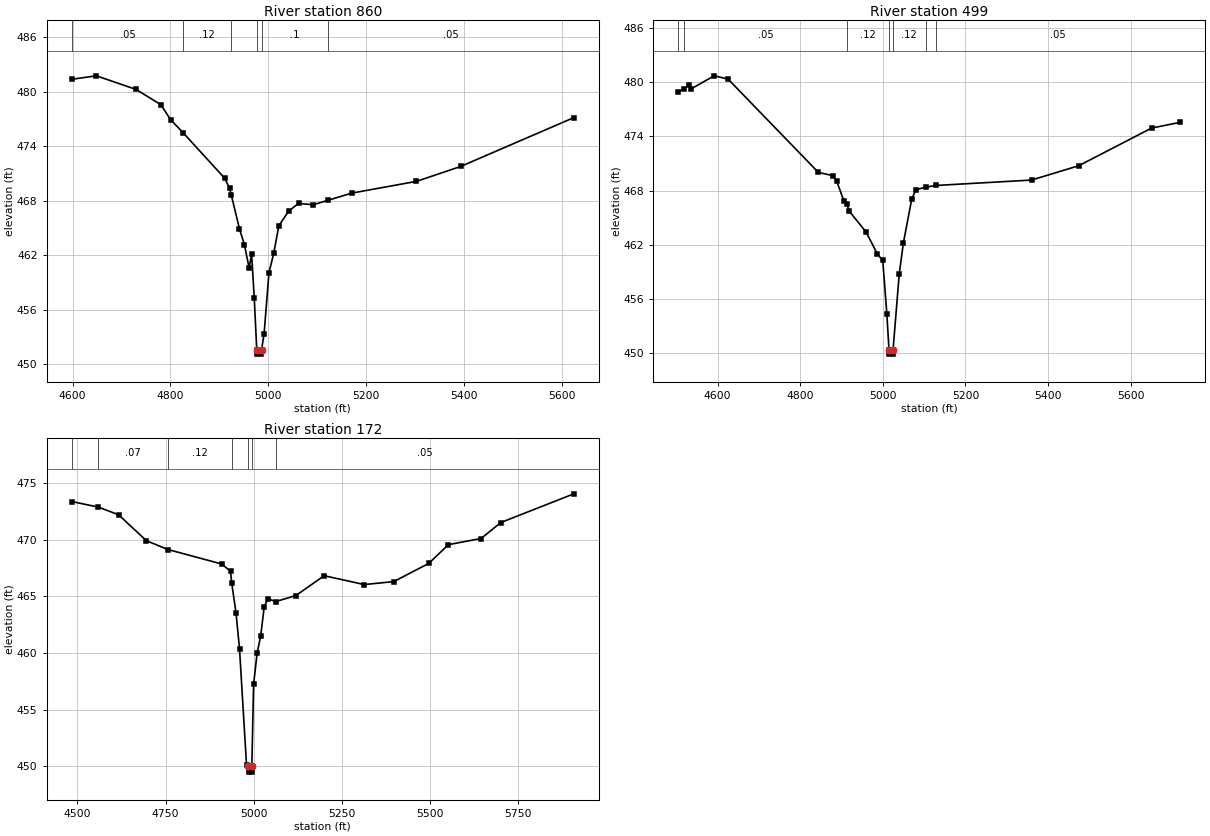
Type RM Length L Ch R = 1 ,860     ,361,361,361
BEGIN DESCRIPTION:
A19562
END DESCRIPTION:
XS GIS Cut Line= 3
      2302424.16     13738224.77      2303050.32     13738285.18
      2303445.84     13738263.21
#Sta/Elev= 30
  4598.5  481.36  4648.8  481.74  4729.9  480.24  4780.2  478.57  4800.3  476.92
  4825.4   475.5  4910.8  470.46  4920.8  469.35    4924  468.67  4940.9   464.9
    4951  463.15  4960.7  460.58  4965.7  462.15  4971.1  457.29  4976.2   451.6
  4976.7   451.1  4985.6   451.1  4986.1   451.6  4991.2  453.34  5001.2  460.07
  5011.2  462.28  5021.3  465.23  5041.4  466.85  5061.5  467.69  5091.6  467.55
  5121.3  468.03  5170.3  468.83  5302.4  470.12  5392.5  471.76  5623.7  477.14
#Mann= 6 ,-1 , 0
  4598.5     .05       0  4825.4     .12       0    4924      .1       0
  4976.2     .05       0  4986.1      .1       0  5121.3     .05       0
Bank Sta=4976.2,4986.1
XS Rating Curve= 0 ,0
Exp/Cntr=0.3,0.1

Type RM Length L Ch R = 1 ,499     ,327,327,327
BEGIN DESCRIPTION:
A19561
END DESCRIPTION:
XS GIS Cut Line= 4
      2302336.22     13738515.88      2302814.12     13738592.79
       2303220.6     13738587.29      2303506.26     13738433.48
#Sta/Elev= 30
  4504.9  478.92  4519.8  479.29  4529.9  479.71    4535  479.24  4591.8  480.71
  4625.2  480.36  4844.2     470  4878.4  469.66  4888.6  469.02  4906.1   466.8
  4912.5  466.51  4918.9   465.7  4959.5   463.4  4986.9  460.95  4999.8  460.25
  5009.8  454.27  5014.9  450.37  5015.4  449.87  5024.3  449.87  5024.8  450.37
  5039.8   458.8  5049.8  462.21  5069.8  467.01  5079.8  468.08  5103.6  468.37
  5128.7  468.56  5359.9  469.16  5474.2  470.75  5650.3  474.92  5719.9  475.56
#Mann= 7 ,-1 , 0
  4504.9     .07       0  4519.8     .05       0  4912.5     .12       0
  5014.9     .05       0  5024.8     .12       0  5103.6     .07       0
  5128.7     .05       0
Bank Sta=5014.9,5024.8
XS Rating Curve= 0 ,0
Exp/Cntr=0.3,0.1

Type RM Length L Ch R = 1 ,172     ,0,0,0
BEGIN DESCRIPTION:
A19560
END DESCRIPTION:
XS GIS Cut Line= 4
       2302308.8     13738719.14      2302594.41      13738894.9
      2303088.77     13738916.87      2303528.21     13738515.87
#Sta/Elev= 30
  4483.9  473.36  4559.5  472.87  4616.8  472.19    4696   469.9  4756.8  469.13
  4909.9  467.85  4934.6   467.2  4937.8  466.19    4950  463.57    4960   460.4
    4980   450.1  4985.1     450  4985.6   449.5  4994.5   449.5    4995     450
    5000  457.23    5010  460.01    5020  461.48  5030.1  464.06  5040.1  464.79
    5063  464.54  5120.1  465.07  5200.2  466.82  5314.1  466.04  5397.7   466.3
    5497   467.9  5553.1  469.56  5645.7   470.1  5701.8  471.51    5909  474.04
#Mann= 7 ,-1 , 0
  4483.9     .05       0  4559.5     .07       0  4756.8     .12       0
  4937.8      .1       0  4985.1     .05       0    4995      .1       0
    5063     .05       0
Bank Sta=4985.1,4995
XS Rating Curve= 0 ,0
Exp/Cntr=0.3,0.1

Chan Stop Cuts=-1
Use User Specified Reach Order=0
Composite Channel Slope=5