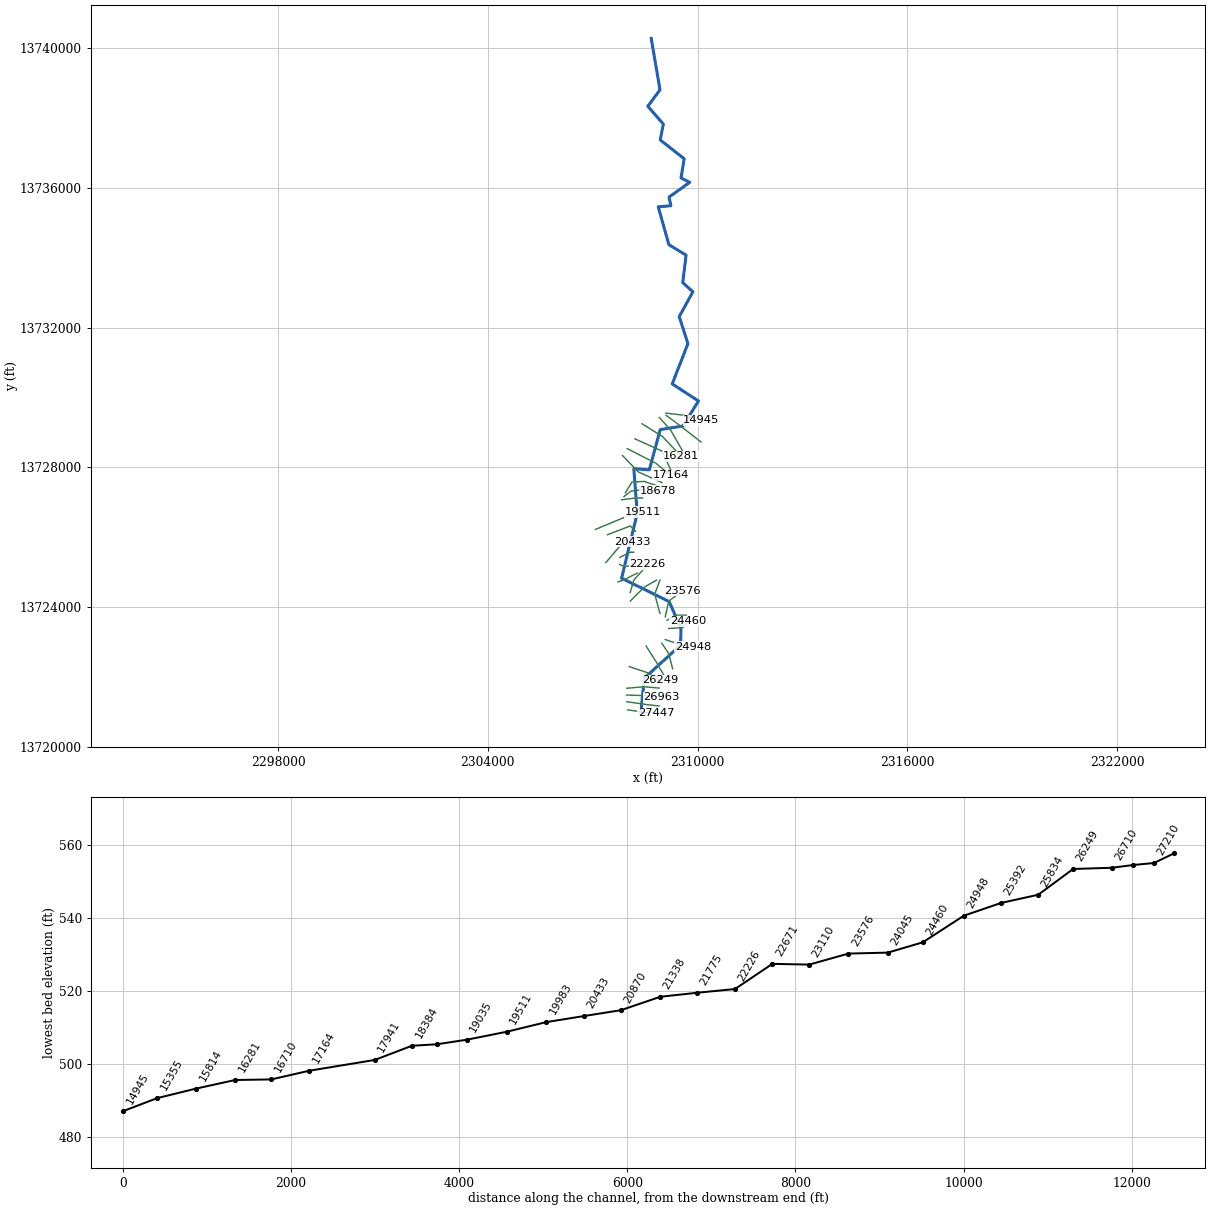
--- KRAMS CREEK.prj (project) ---

Proj Title=KRAMS CREEK Base Level Engineering
Current Plan=p01
Default Exp/Contr=0.3,0.1
English Units
Geom File=g01
Flow File=f01
Plan File=p01
Y Axis Title=Elevation
X Axis Title(PF)=Main Channel Distance
X Axis Title(XS)=Station
BEGIN DESCRIPTION:
KRAMS CREEK
END DESCRIPTION:
DSS Export Rating Curves= 0
DSS Export Rating Curve Sorted= 0
DSS Export Volume Flow Curves= 0
DXF OffsetX= 0
DXF OffsetY= 0
DXF ScaleX= 1
DXF ScaleY= 10

--- KRAMS CREEK.p01 (plan) ---

Plan Title=Multiple Run
Short Identifier=Multiple
Geom File=g01
Flow File=f01
Subcritical Flow
K Sum by GR= 0
Std Step Tol= 0.01
Critical Tol= 0.01
Num of Std Step Trials= 20
Max Error Tol= 0.3
Flow Tol Ratio= 0.001
Split Flow NTrial= 30
Split Flow Tol= 0.02
Split Flow Ratio= 0.02
Log Output Level= 0
Friction Slope Method= 1
Unsteady Friction Slope Method= 2
Unsteady Bridges Friction Slope Method= 1
Parabolic Critical Depth
Global Vel Dist=  1 , 1 , 1
Global Log Level= 0
CheckData=True
Encroach Param= -1, 0, 0, 0
BEGIN DESCRIPTION:
Multiple Run
END DESCRIPTION:

--- KRAMS CREEK.f01 (steady flow) ---

Flow Title=Multiple
Number of Profiles=7
Profile Names=10-year,25-year,50-year,1pct_min,100-year,1pct_plu,500-year
River Rch & RM= KRAMS CREEK,Reach-1,27447
     689    1133    1542    1017    2030    4050    3484
River Rch & RM= KRAMS CREEK,Reach-1,24948
     968    1614    2215    1472    2937    5859    5116
River Rch & RM= KRAMS CREEK,Reach-1,17941
    1092    1827    2514    1673    3339    6662    5839
River Rch & RM= KRAMS CREEK,Reach-1,13974
    2478    4289    6039    4100    8180   16320   14891
River Rch & RM= KRAMS CREEK,Reach-1,6986
    2554    4425    6233    4233    8446   16851   15387
River Rch & RM= KRAMS CREEK,Reach-1,4088
    2637    4572    6442    4376    8731   17420   15913
Boundary for River Rch & Prof#=KRAMS CREEK,Reach-1,1
Up Type=0
Dn Type=3
Dn Slope=0.005
Boundary for River Rch & Prof#=KRAMS CREEK,Reach-1,2
Up Type=0
Dn Type=3
Dn Slope=0.005
Boundary for River Rch & Prof#=KRAMS CREEK,Reach-1,3
Up Type=0
Dn Type=3
Dn Slope=0.005
Boundary for River Rch & Prof#=KRAMS CREEK,Reach-1,4
Up Type=0
Dn Type=3
Dn Slope=0.005
Boundary for River Rch & Prof#=KRAMS CREEK,Reach-1,5
Up Type=0
Dn Type=3
Dn Slope=0.005
Boundary for River Rch & Prof#=KRAMS CREEK,Reach-1,6
Up Type=0
Dn Type=3
Dn Slope=0.005
Boundary for River Rch & Prof#=KRAMS CREEK,Reach-1,7
Up Type=0
Dn Type=3
Dn Slope=0.005

--- KRAMS CREEK.g01 (geometry) ---

Geom Title=Existing Conditions
Program Version=4.10

River Reach=KRAMS CREEK     ,Reach-1
Reach XY= 30
        2308375.       13720975.      2308478.82     13721973.41
      2309517.19     13722918.81      2309525.36     13723395.15
      2309188.33     13724161.61      2307827.06     13724830.85
      2308274.69      13726690.4      2308175.99     13727964.94
      2308619.59     13727930.16      2308932.85     13729081.82
       2309584.7     13729185.74      2310025.54     13729900.12
      2309275.24     13730390.22      2309724.76     13731540.22
      2309476.09     13732314.46      2309867.46     13733025.02
      2309576.03     13733285.44      2309671.86     13734073.36
      2309180.08     13734372.69      2308874.74     13735455.07
      2309235.54     13735485.47      2309185.18      13735734.7
      2309775.12      13736155.1      2309526.96     13736280.65
      2309615.87     13736831.74      2308932.76     13737368.83
      2309021.25     13737823.45      2308577.14     13738330.97
       2308925.3     13738799.88        2308675.       13740275.

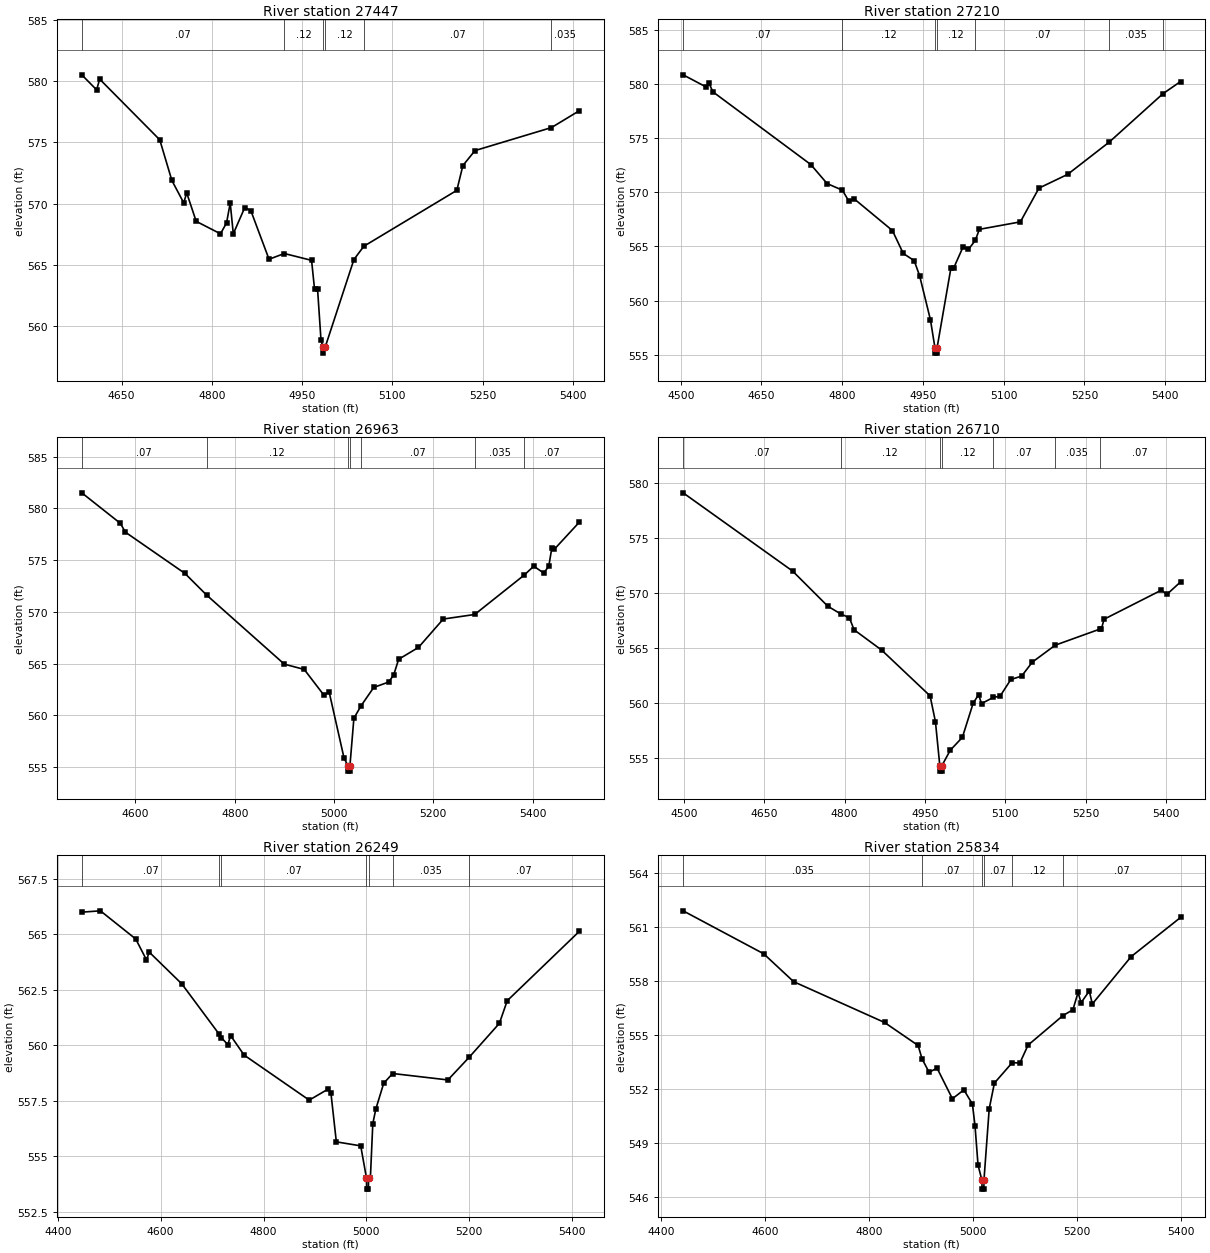
Type RM Length L Ch R = 1 ,27447   ,237,237,237
BEGIN DESCRIPTION:
A19585
END DESCRIPTION:
XS GIS Cut Line= 3
      2307996.64     13721063.49      2308380.01     13721011.21
      2308817.21     13720963.69
#Sta/Elev= 30
  4583.9  580.52  4608.6  579.29  4613.6  580.17  4713.5  575.21  4733.6  571.89
  4753.3  570.06  4758.3  570.87    4774  568.55  4814.4  567.53  4824.5  568.42
  4830.6  570.05  4835.7  567.53  4854.7  569.67  4864.8  569.43  4895.1  565.45
  4920.5  565.92  4965.8  565.36  4970.8  562.98  4975.8  562.98  4981.4  558.89
  4984.5  558.28  4984.7  557.78  4988.5  558.28  5036.2  565.43  5052.6  566.51
  5207.2  571.08  5217.3  573.11  5237.4  574.33  5364.5  576.21  5410.6  577.58
#Mann= 6 ,-1 , 0
  4583.9     .07       0  4920.5     .12       0  4984.5     .05       0
  4988.5     .12       0  5052.6     .07       0  5364.5    .035       0
Bank Sta=4984.5,4988.5
XS Rating Curve= 0 ,0
Exp/Cntr=0.3,0.1

Type RM Length L Ch R = 1 ,27210   ,247,247,247
BEGIN DESCRIPTION:
KRAMS CREEK 56.0
END DESCRIPTION:
XS GIS Cut Line= 3
      2307980.35     13721296.59        2308475.       13721225.
      2308896.15     13721175.06
#Sta/Elev= 30
  4504.5  580.86  4547.5  579.73  4552.6  580.09  4559.7  579.29  4741.6  572.57
  4771.9  570.81  4800.2   570.2  4812.3  569.19  4822.4  569.39  4893.2  566.47
  4913.4  564.35  4933.6  563.69  4943.7   562.3  4963.9  558.21  4972.2  555.64
  4972.5  555.14    4976  555.14  4976.2  555.64  5001.8  562.98  5006.8  562.98
  5024.4  564.95  5034.5  564.73  5047.2  565.56  5054.7  566.58  5130.9  567.27
  5165.4  570.39  5218.7  571.66  5296.1  574.65  5395.6  579.11  5428.4  580.24
#Mann= 7 ,-1 , 0
  4504.5     .07       0  4800.2     .12       0  4972.2     .05       0
  4976.2     .12       0  5047.2     .07       0  5296.1    .035       0
  5395.6     .07       0
Bank Sta=4972.2,4976.2
XS Rating Curve= 0 ,0
Exp/Cntr=0.3,0.1

Type RM Length L Ch R = 1 ,26963   ,253,253,253
BEGIN DESCRIPTION:
A19584
END DESCRIPTION:
XS GIS Cut Line= 3
      2307967.36     13721487.56      2308657.44     13721465.86
      2308965.58     13721422.46
#Sta/Elev= 30
  4492.1   581.5  4569.8  578.55  4579.8   577.7  4699.8  573.71  4743.4  571.62
  4899.9  564.94    4940  564.43    4980  561.92    4990  562.29    5020   555.9
    5028   555.1  5028.3   554.6  5031.8   554.6    5032   555.1    5040  559.71
  5054.5  560.92    5080  562.69    5110  563.21  5120.1  563.89  5130.1  565.41
  5170.1  566.56    5220   569.3  5283.2  569.74    5383  573.55  5402.2  574.41
  5422.4  573.74  5432.5  574.42  5438.6  576.19  5443.7  576.05  5493.7  578.65
#Mann= 7 ,-1 , 0
  4492.1     .07       0  4743.4     .12       0    5028     .05       0
    5032     .12       0  5054.5     .07       0  5283.2    .035       0
    5383     .07       0
Bank Sta=5028,5032
XS Rating Curve= 0 ,0
Exp/Cntr=0.3,0.1

Type RM Length L Ch R = 1 ,26710   ,461,461,461
BEGIN DESCRIPTION:
KRAMS CREEK 55.0
END DESCRIPTION:
XS GIS Cut Line= 3
      2307976.02     13721682.88        2308475.       13721725.
      2308900.27     13721687.24
#Sta/Elev= 30
  4498.9  579.14    4703  572.03  4768.8  568.83  4792.9  568.13    4809  567.78
  4817.7  566.69  4869.2  564.84  4959.5  560.68  4969.5  558.32  4977.6  554.34
  4977.8  553.84  4981.3  553.84  4981.6  554.34  4997.1  555.74  5019.7  556.91
  5039.8  560.01  5049.9  560.79  5055.5  559.98  5077.3  560.54    5090  560.65
  5110.1  562.17  5130.2  562.48  5150.2  563.75  5192.9  565.29  5275.5  566.74
    5279  566.77    5284  567.65  5390.8  570.29  5401.2  569.91  5426.6  571.04
#Mann= 7 ,-1 , 0
  4498.9     .07       0  4792.9     .12       0  4977.6     .05       0
  4981.6     .12       0  5077.3     .07       0  5192.9    .035       0
  5275.5     .07       0
Bank Sta=4977.6,4981.6
XS Rating Curve= 0 ,0
Exp/Cntr=0.3,0.1

Type RM Length L Ch R = 1 ,26249   ,415,415,415
BEGIN DESCRIPTION:
KRAMS CREEK 54.0
END DESCRIPTION:
XS GIS Cut Line= 3
      2308045.44     13722301.37        2308575.       13722125.
      2308921.06     13721907.11
#Sta/Elev= 30
  4446.7  565.99  4482.9  566.05  4551.6  564.78  4572.5  563.84  4577.8  564.19
  4641.1  562.76  4713.2  560.51  4717.8  560.34  4730.7  560.02    4736  560.43
  4762.3  559.55  4888.9  557.52  4925.8  558.02  4931.1  557.84  4941.6  555.64
    4989  555.46  5000.2  554.01  5000.5  553.51    5004  553.51  5004.2  554.01
  5007.8  554.01  5012.5  556.46  5018.4  557.12  5033.7  558.28  5051.1  558.72
  5158.5  558.43  5200.2  559.46  5258.6  560.98  5273.9     562  5413.8  565.12
#Mann= 7 ,-1 , 0
  4446.7     .07       0  4713.2     .12       0  4717.8     .07       0
  5000.2     .05       0  5004.2     .07       0  5051.1    .035       0
  5200.2     .07       0
Bank Sta=5000.2,5004.2
XS Rating Curve= 0 ,0
Exp/Cntr=0.3,0.1

Type RM Length L Ch R = 1 ,25834   ,442,442,442
BEGIN DESCRIPTION:
KRAMS CREEK 53.0
END DESCRIPTION:
XS GIS Cut Line= 3
      2308527.25     13722891.61        2308825.       13722425.
      2309026.35     13722075.69
#Sta/Elev= 30
  4442.1  561.92  4597.1  559.53  4654.6  557.98  4829.5  555.71  4894.1  554.43
  4901.7  553.68  4915.2  552.94  4930.5  553.17    4960  551.47  4982.1  551.96
  4998.5  551.17  5003.5  549.96  5009.3  547.78  5016.7  546.94    5017  546.44
  5020.5  546.44  5020.7  546.94  5030.8  550.91  5040.8  552.34  5075.2  553.48
  5089.7  553.45  5105.5  554.45  5172.5  556.09  5191.8  556.42  5201.7  557.38
  5207.5  556.81  5223.3  557.46  5229.1  556.74  5303.7  559.37  5398.8  561.55
#Mann= 6 ,-1 , 0
  4442.1    .035       0  4901.7     .07       0  5016.7     .05       0
  5020.7     .07       0  5075.2     .12       0  5172.5     .07       0
Bank Sta=5016.7,5020.7
XS Rating Curve= 0 ,0
Exp/Cntr=0.3,0.1

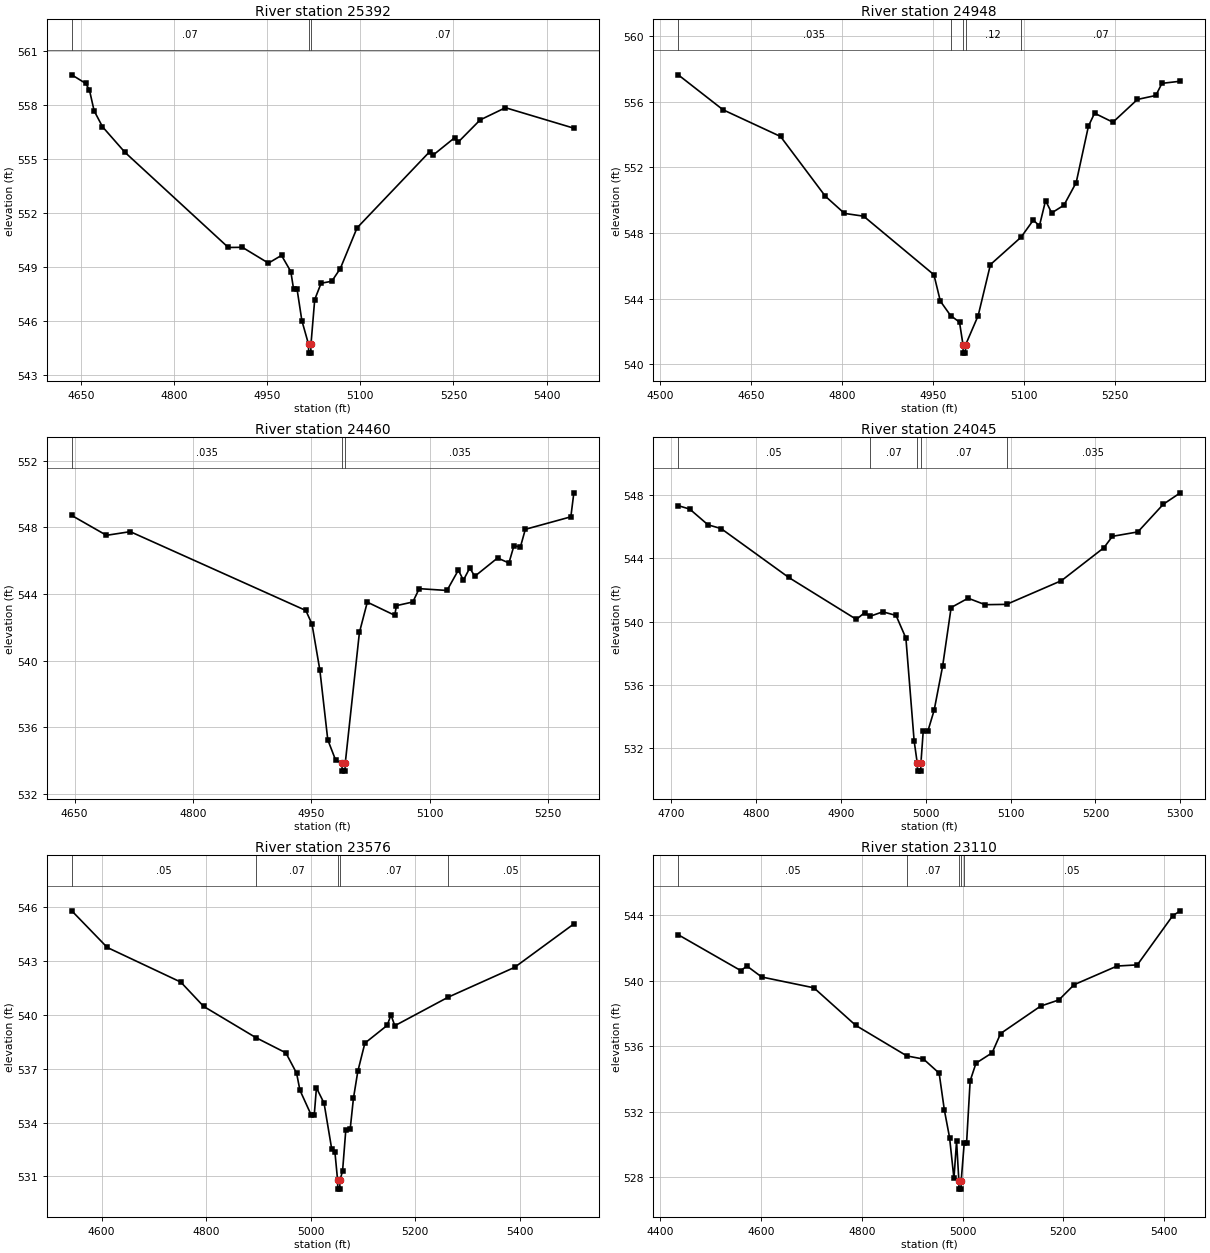
Type RM Length L Ch R = 1 ,25392   ,444,444,444
BEGIN DESCRIPTION:
KRAMS CREEK 52.0
END DESCRIPTION:
XS GIS Cut Line= 3
      2308975.02     13722974.96        2309175.       13722675.
      2309286.79     13722240.56
#Sta/Elev= 30
  4634.9  559.68  4657.4   559.2  4663.4  558.83  4670.9  557.68  4684.4  556.79
  4720.5  555.37  4887.2  550.07  4909.8  550.08  4951.8   549.2  4972.9  549.63
  4987.9  548.73  4992.4  547.74    4998  547.74  5005.7     546  5016.4  544.69
  5016.6  544.19  5020.1  544.19  5020.4  544.69  5026.4  547.17  5036.7  548.08
  5053.9  548.19  5067.7   548.9  5094.6  551.16  5211.6   555.4  5216.8   555.2
  5252.3  556.19  5257.5  555.93    5293  557.17  5333.8  557.85    5444  556.71
#Mann= 3 ,-1 , 0
  4634.9     .07       0  5016.4     .05       0  5020.4     .07       0
Bank Sta=5016.4,5020.4
XS Rating Curve= 0 ,0
Exp/Cntr=0.3,0.1

Type RM Length L Ch R = 1 ,24948   ,488,488,488
BEGIN DESCRIPTION:
KRAMS CREEK 51.0
END DESCRIPTION:
XS GIS Cut Line= 3
      2309074.99       13723075.        2309525.       13722925.
      2309874.99       13722875.
#Sta/Elev= 30
  4529.5  557.65  4603.3  555.52  4698.2  553.89    4772  550.25  4803.6   549.2
  4835.2  549.03  4951.1  545.46  4961.7  543.85  4978.6  542.97  4993.3  542.57
  4999.1  541.18  4999.4  540.68  5003.1  540.68  5003.3  541.18  5024.1  542.97
  5044.3  546.08  5094.8  547.75    5115  548.79  5125.1  548.44  5135.2  549.98
  5145.3  549.23  5165.5   549.7  5185.7  551.08  5205.9  554.52    5216  555.31
  5246.3  554.76  5286.7  556.15    5317  556.39  5327.1  557.13  5357.4  557.26
#Mann= 5 ,-1 , 0
  4529.5    .035       0  4978.6     .12       0  4999.1     .05       0
  5003.3     .12       0  5094.8     .07       0
Bank Sta=4999.1,5003.3
XS Rating Curve= 0 ,0
Exp/Cntr=0.3,0.1

Type RM Length L Ch R = 1 ,24460   ,415,415,415
BEGIN DESCRIPTION:
KRAMS CREEK 50.0
END DESCRIPTION:
XS GIS Cut Line= 3
      2309171.07     13723392.07      2309579.69     13723417.05
      2309720.78      13723594.9
#Sta/Elev= 30
  4646.5  548.72  4690.5  547.53  4720.6  547.75  4943.2  543.02    4951   542.2
    4961  539.43    4971  535.26  4981.1  534.02  4988.9  533.88  4989.2  533.38
  4992.9  533.38  4993.2  533.88  5011.1   541.7  5021.1  543.52  5055.9  542.73
    5058  543.31  5078.8  543.53  5086.9  544.33  5122.1  544.22  5136.5  545.44
  5142.9  544.84    5151  545.57  5157.3  545.07  5186.2  546.17  5200.6  545.87
    5207  546.91  5215.1  546.82  5221.4  547.89  5279.1  548.64  5282.9  550.08
#Mann= 3 ,-1 , 0
  4646.5    .035       0  4988.9    .035       0  4993.2    .035       0
Bank Sta=4988.9,4993.2
XS Rating Curve= 0 ,0
Exp/Cntr=0.3,0.1

Type RM Length L Ch R = 1 ,24045   ,469,469,469
BEGIN DESCRIPTION:
KRAMS CREEK 49.0
END DESCRIPTION:
XS GIS Cut Line= 3
        2309125.       13723625.        2309375.       13723775.
      2309674.96       13723775.
#Sta/Elev= 30
  4708.5  547.34  4722.1  547.12  4743.5  546.13    4759  545.89  4838.7   542.8
  4918.4  540.15  4928.1  540.58  4934.2  540.34  4949.5  540.63  4965.1   540.4
  4976.7  538.97  4986.4  532.48  4990.1  531.06  4990.4  530.56  4994.2  530.56
  4994.4  531.06  4997.1  533.07  5002.5  533.07    5010  534.41    5020   537.2
    5030   540.9    5050  541.49    5070  541.08  5095.3   541.1    5160   542.6
    5210  544.68    5220   545.4    5250  545.68    5280  547.43    5300  548.15
#Mann= 5 ,-1 , 0
  4708.5     .05       0  4934.2     .07       0  4990.1     .05       0
  4994.4     .07       0  5095.3    .035       0
Bank Sta=4990.1,4994.4
XS Rating Curve= 0 ,0
Exp/Cntr=0.3,0.1

Type RM Length L Ch R = 1 ,23576   ,466,466,466
BEGIN DESCRIPTION:
KRAMS CREEK 48.0
END DESCRIPTION:
XS GIS Cut Line= 3
      2309074.99     13723724.98        2309175.       13724175.
        2309575.       13724475.
#Sta/Elev= 30
    4543  545.79  4610.9  543.75  4751.7  541.82  4795.3  540.47  4895.3  538.73
  4952.8  537.88  4973.3  536.75  4979.7   535.8  5001.4  534.41  5007.1  534.41
  5011.3  535.93  5025.9  535.08  5040.5  532.53  5046.7  532.35  5051.8  530.79
  5052.1  530.29  5055.9  530.29  5056.3  530.79  5061.3  531.29  5067.5  533.58
  5075.9  533.63  5082.1  535.34  5090.5  536.85    5104  538.42  5146.7  539.41
    5154  539.99  5161.3  539.39  5263.4  540.98  5390.5  542.64    5504  545.06
#Mann= 5 ,-1 , 0
    4543     .05       0  4895.3     .07       0  5051.8     .05       0
  5056.3     .07       0  5263.4     .05       0
Bank Sta=5051.8,5056.3
XS Rating Curve= 0 ,0
Exp/Cntr=0.3,0.1

Type RM Length L Ch R = 1 ,23110   ,439,439,439
BEGIN DESCRIPTION:
KRAMS CREEK 47.0
END DESCRIPTION:
XS GIS Cut Line= 3
      2308924.99     13723825.05        2308775.       13724375.
      2308924.99     13724774.96
#Sta/Elev= 30
  4435.4   542.8  4559.7  540.61  4571.8  540.89  4601.2  540.22  4704.8  539.56
  4787.8  537.27  4889.6   535.4  4922.5  535.21  4953.6  534.35    4964  532.09
  4974.3  530.42    4983  527.92  4988.2   530.2  4992.8  527.77  4993.1  527.27
    4997  527.27  4997.4  527.77  5003.4  530.09  5008.1  530.09  5015.2  533.88
  5026.8  534.96  5058.8  535.59  5075.7  536.77    5155  538.44  5191.4  538.82
  5221.7  539.75  5307.1  540.89  5347.2  540.96  5417.5  543.96  5432.6  544.26
#Mann= 5 ,-1 , 0
  4435.4     .05       0  4889.6     .07       0  4992.8     .05       0
  4997.4     .07       0  5003.4     .05       0
Bank Sta=4992.8,4997.4
XS Rating Curve= 0 ,0
Exp/Cntr=0.3,0.1

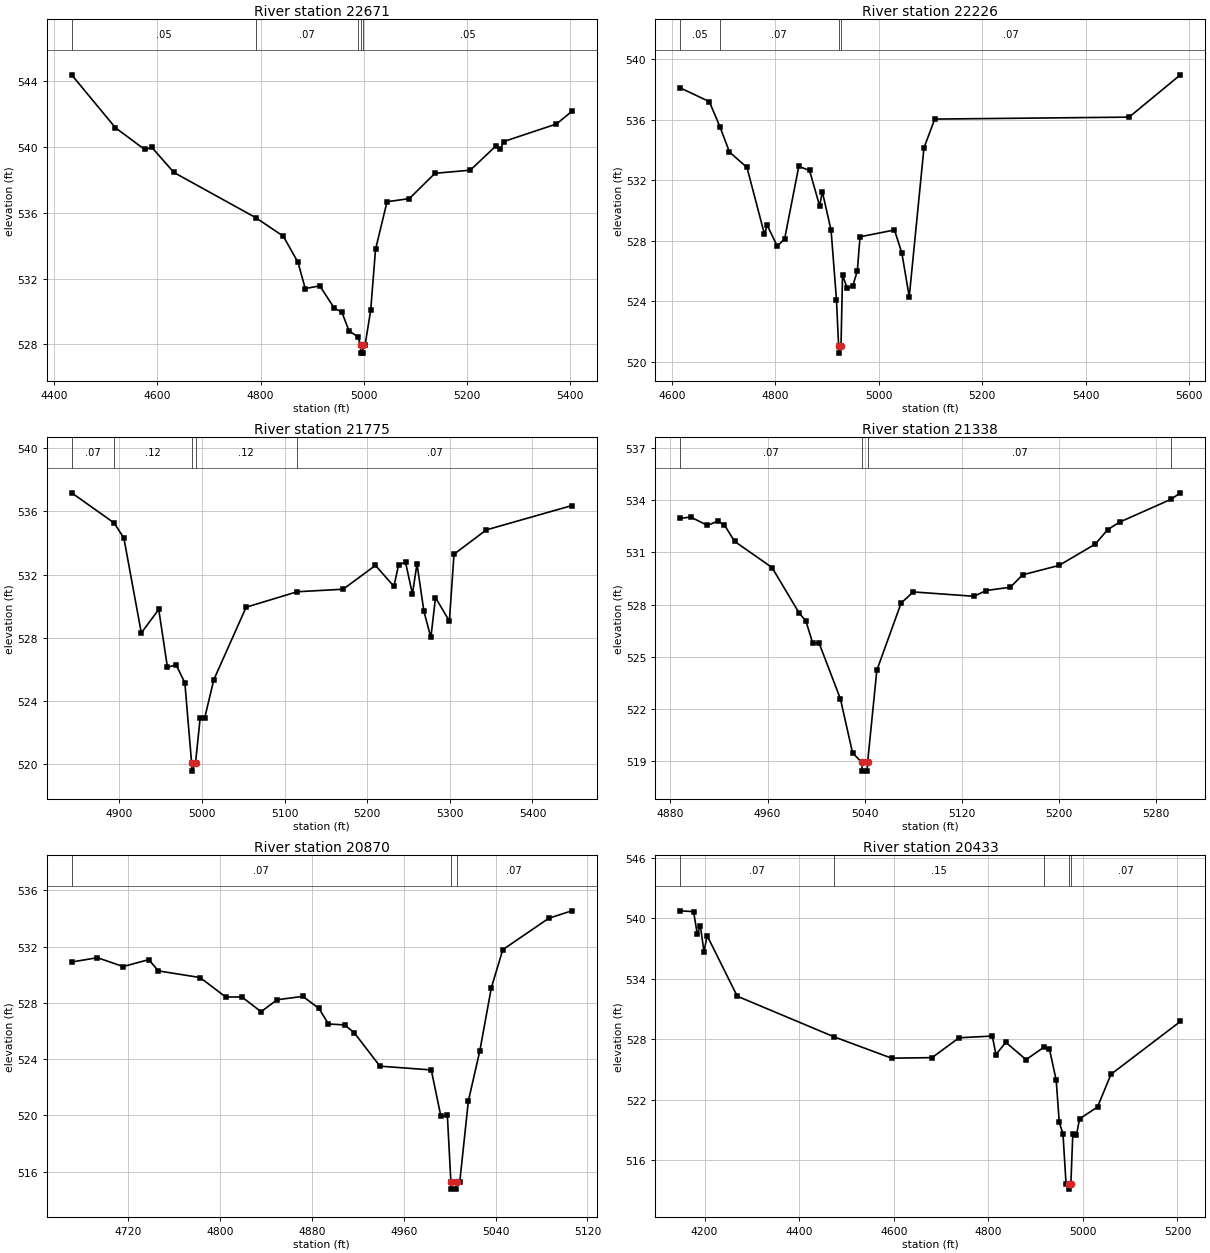
Type RM Length L Ch R = 1 ,22671   ,445,445,445
BEGIN DESCRIPTION:
KRAMS CREEK 46.0
END DESCRIPTION:
XS GIS Cut Line= 3
      2308075.01     13724175.01        2308475.       13724575.
      2308825.02     13724775.01
#Sta/Elev= 30
  4433.9   544.4  4518.7  541.18  4575.3  539.86  4589.4  539.98  4631.9  538.46
  4790.6  535.71    4844  534.58  4872.3     533  4886.4   531.4  4914.7  531.56
    4943  530.19  4957.1  529.98  4971.3  528.82  4988.2  528.47  4993.7  527.97
    4994  527.47    4998  527.47  4998.4  527.97  5002.4  527.97  5013.2  530.07
  5022.6  533.78  5044.9  536.68  5088.1  536.87  5137.8  538.41  5206.2   538.6
  5255.1  540.05  5264.5  539.88  5270.9  540.34  5373.2  541.41  5402.7  542.17
#Mann= 5 ,-1 , 0
  4433.9     .05       0  4790.6     .07       0  4988.2     .05       0
  4993.7     .05       0  4998.4     .05       0
Bank Sta=4993.7,4998.4
XS Rating Curve= 0 ,0
Exp/Cntr=0.3,0.1

Type RM Length L Ch R = 1 ,22226   ,451,451,451
BEGIN DESCRIPTION:
KRAMS CREEK 45.0
END DESCRIPTION:
XS GIS Cut Line= 3
      2308075.01     13724425.02        2308175.       13724775.
      2308575.03     13725225.03
#Sta/Elev= 30
  4616.7  538.11  4672.6  537.21  4693.1  535.55  4711.6  533.87  4745.4  532.85
  4779.2  528.43  4784.4  529.03  4803.9  527.64  4818.2  528.13  4845.5  532.92
  4866.3  532.65  4885.8   530.3    4891  531.24  4907.9  528.69  4918.3   524.1
  4922.4  521.06  4922.8  520.56  4927.1  521.06    4930  525.73  4939.1  524.85
  4949.5  524.98  4958.6     526  4963.8  528.26  5030.4  528.71  5044.7  527.17
  5058.9  524.29  5087.3  534.14  5108.2  536.05  5483.7  536.18  5582.8  538.98
#Mann= 4 ,-1 , 0
  4616.7     .05       0  4693.1     .07       0  4922.4     .05       0
  4927.1     .07       0
Bank Sta=4922.4,4927.1
XS Rating Curve= 0 ,0
Exp/Cntr=0.3,0.1

Type RM Length L Ch R = 1 ,21775   ,437,437,437
BEGIN DESCRIPTION:
KRAMS CREEK 44.0
END DESCRIPTION:
XS GIS Cut Line= 3
      2307725.01       13724725.        2307875.       13724775.
      2308274.99     13724974.99
#Sta/Elev= 30
  4842.2  537.18  4893.6  535.27  4905.4  534.31  4926.5   528.3  4947.6  529.79
  4958.1  526.13  4968.7  526.27  4979.2  525.14  4987.4  520.04  4987.7  519.54
  4992.1  520.04  4997.7  522.89  5003.1  522.89  5014.3  525.34  5053.4  529.93
  5115.2  530.91  5170.8  531.07  5209.9  532.58  5232.3  531.25  5237.9  532.62
  5246.3  532.78  5254.7  530.77  5260.2  532.68  5268.6  529.66    5277  528.01
  5282.6  530.54  5299.4  529.05    5305  533.29  5344.1  534.83  5447.5  536.37
#Mann= 5 ,-1 , 0
  4842.2     .07       0  4893.6     .12       0  4987.4     .05       0
  4992.1     .12       0  5115.2     .07       0
Bank Sta=4987.4,4992.1
XS Rating Curve= 0 ,0
Exp/Cntr=0.3,0.1

Type RM Length L Ch R = 1 ,21338   ,468,468,468
BEGIN DESCRIPTION:
KRAMS CREEK 43.0
END DESCRIPTION:
XS GIS Cut Line= 3
      2307775.01     13725224.99        2307875.       13725175.
      2308175.01       13725175.
#Sta/Elev= 30
  4888.2  532.95  4896.6  533.03  4910.5  532.55  4918.9  532.79  4924.5  532.57
  4932.9  531.63  4963.7  530.13    4986  527.52  4991.6  527.06  4997.2  525.78
  5002.5  525.78    5020  522.59    5030  519.49  5037.6  518.94  5037.9  518.44
    5042  518.44  5042.4  518.94    5050  524.23    5070  528.09    5080  528.73
    5130  528.48    5140  528.81    5160     529    5170  529.71    5200  530.25
    5230  531.48    5240   532.3    5250  532.74  5292.3  534.05    5300  534.42
#Mann= 4 ,-1 , 0
  4888.2     .07       0  5037.6     .05       0  5042.4     .07       0
  5292.3     .05       0
Bank Sta=5037.6,5042.4
XS Rating Curve= 0 ,0
Exp/Cntr=0.3,0.1

Type RM Length L Ch R = 1 ,20870   ,437,437,437
BEGIN DESCRIPTION:
KRAMS CREEK 42.0
END DESCRIPTION:
XS GIS Cut Line= 3
      2307774.97     13725424.98        2308075.       13725575.
      2308174.95       13725575.
#Sta/Elev= 30
  4670.9   530.9  4693.3  531.21  4715.7  530.58    4738  531.07  4746.4  530.27
  4782.7   529.8  4805.1  528.41  4819.1  528.42  4835.8  527.37  4849.8  528.22
  4872.2  528.46  4886.2   527.6  4894.5   526.5  4908.5  526.43  4916.9  525.88
  4939.3   523.5    4984  523.23  4992.4  519.93    4998  520.02  5001.1  515.26
  5001.4  514.76  5005.6  514.76    5006  515.26  5008.8  515.26  5016.3  521.02
  5026.3   524.6  5036.3  529.07  5046.3  531.78  5086.3  534.01  5106.3  534.54
#Mann= 3 ,-1 , 0
  4670.9     .07       0  5001.1     .05       0    5006     .07       0
Bank Sta=5001.1,5006
XS Rating Curve= 0 ,0
Exp/Cntr=0.3,0.1

Type RM Length L Ch R = 1 ,20433   ,450,450,450
BEGIN DESCRIPTION:
KRAMS CREEK 41.0
END DESCRIPTION:
XS GIS Cut Line= 3
        2307375.       13725275.        2307925.       13725925.
      2308124.98       13725875.
#Sta/Elev= 30
  4148.7  540.74  4176.7  540.66  4184.4  538.45    4191  539.27  4198.7  536.68
  4205.3  538.28    4269  532.28  4473.9  528.25  4595.3  526.14    4681  526.19
  4738.2  528.16  4808.4  528.33  4816.2   526.5    4837  527.71  4879.9  525.99
  4917.4  527.22  4929.3  527.04  4943.6  523.95  4950.1  519.77  4957.9  518.65
  4964.4  513.69  4969.7  513.66  4970.1  513.16  4974.6  513.66  4978.7  518.62
  4986.5  518.54    4993  520.12  5031.1  521.31  5059.4  524.54  5206.3  529.78
#Mann= 5 ,-1 , 0
  4148.7     .07       0  4473.9     .15       0  4917.4     .07       0
  4969.7     .05       0  4974.6     .07       0
Bank Sta=4969.7,4974.6
XS Rating Curve= 0 ,0
Exp/Cntr=0.3,0.1

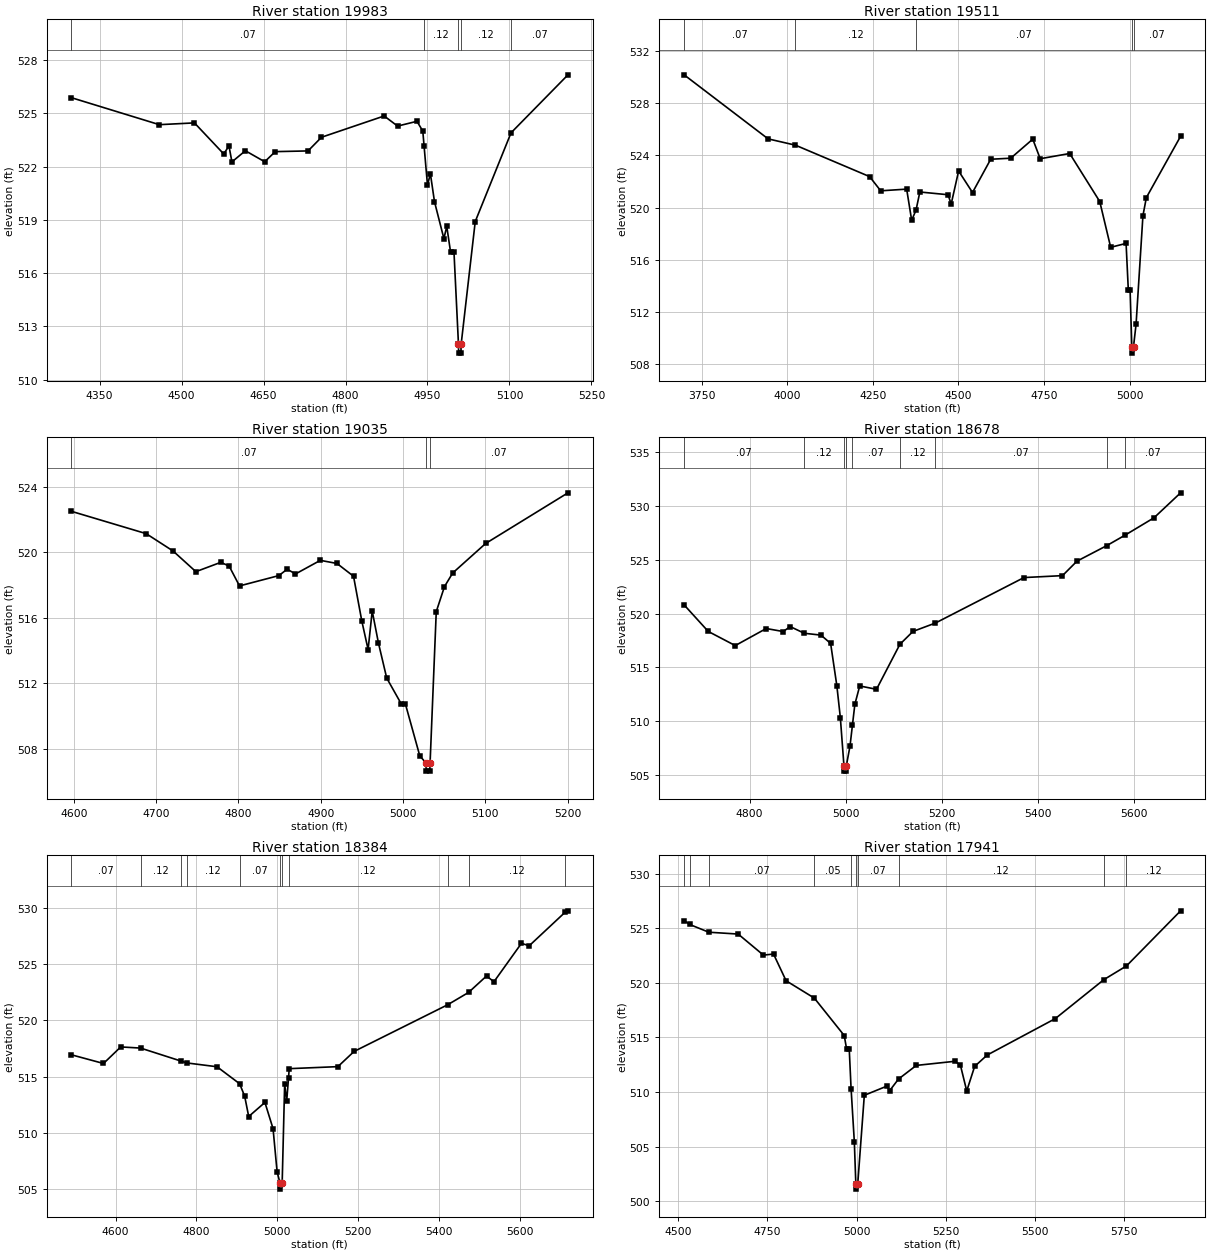
Type RM Length L Ch R = 1 ,19983   ,472,472,472
BEGIN DESCRIPTION:
KRAMS CREEK 40.0
END DESCRIPTION:
XS GIS Cut Line= 3
      2307424.96     13726074.99        2308075.       13726325.
      2308225.01     13726174.99
#Sta/Elev= 30
  4298.5  525.89  4459.3  524.37  4523.5  524.47  4577.1  522.72  4586.7  523.17
  4592.1  522.27  4616.7   522.9  4652.1  522.28  4671.4  522.85  4731.4  522.89
    4756  523.66  4870.7  524.86  4895.3  524.29  4930.7  524.56  4941.4  524.01
  4943.7  523.19    4950  520.96  4955.3  521.61  4962.8  520.03    4980  517.95
  4985.3  518.63  4992.3  517.18  4998.5  517.18  5006.7  511.99    5007  511.49
  5011.2  511.49  5011.6  511.99  5037.4  518.91  5102.9  523.91  5207.1  527.18
#Mann= 5 ,-1 , 0
  4298.5     .07       0  4943.7     .12       0  5006.7     .05       0
  5011.6     .12       0  5102.9     .07       0
Bank Sta=5006.7,5011.6
XS Rating Curve= 0 ,0
Exp/Cntr=0.3,0.1

Type RM Length L Ch R = 1 ,19511   ,476,476,476
BEGIN DESCRIPTION:
KRAMS CREEK 39.0
END DESCRIPTION:
XS GIS Cut Line= 3
      2307074.99     13726224.99        2308275.       13726725.
      2308424.99       13726725.
#Sta/Elev= 30
    3699  530.17  3944.4  525.26    4024  524.78  4240.7  522.37  4273.2  521.28
    4349  521.41  4363.6  519.02  4376.4  519.81  4387.5  521.19  4469.8  520.98
    4479  520.27  4500.7   522.8  4541.3  521.15  4594.4   523.7  4652.9  523.78
  4717.3  525.24    4739  523.74  4825.1  524.14  4912.9  520.46  4944.8  516.95
  4989.8  517.25  4996.3  513.69  5001.5  513.69  5006.5  509.34  5006.9  508.84
  5011.5  509.34    5019  511.06    5039  519.37    5049  520.76    5149  525.46
#Mann= 5 ,-1 , 0
    3699     .07       0    4024     .12       0  4376.4     .07       0
  5006.5     .05       0  5011.5     .07       0
Bank Sta=5006.5,5011.5
XS Rating Curve= 0 ,0
Exp/Cntr=0.3,0.1

Type RM Length L Ch R = 1 ,19035   ,357,357,357
BEGIN DESCRIPTION:
KRAMS CREEK 38.0
END DESCRIPTION:
XS GIS Cut Line= 3
      2307825.02       13727075.        2308225.       13727125.
      2308425.01       13727125.
#Sta/Elev= 30
  4597.3   522.5    4688  521.14  4720.7  520.08  4748.4  518.82  4778.7  519.39
  4788.8  519.16  4801.4  517.95  4849.2  518.58  4859.3  518.97  4869.4  518.68
  4899.6  519.51  4919.8  519.32  4939.9  518.54    4950   515.8  4957.6  514.07
  4962.6  516.42  4970.2  514.46  4980.2  512.33  4997.9  510.75  5002.9  510.75
  5020.4  507.58  5027.9  507.15  5028.2  506.65  5032.5  506.65  5032.9  507.15
  5040.4  516.38  5050.4  517.91  5060.4  518.74  5100.4  520.54  5200.4  523.63
#Mann= 3 ,-1 , 0
  4597.3     .07       0  5027.9     .05       0  5032.9     .07       0
Bank Sta=5027.9,5032.9
XS Rating Curve= 0 ,0
Exp/Cntr=0.3,0.1

Type RM Length L Ch R = 1 ,18678   ,294,294,294
BEGIN DESCRIPTION:
A19583
END DESCRIPTION:
XS GIS Cut Line= 4
      2307893.56     13727166.83      2308097.54     13727323.07
      2308388.34     13727357.79      2308870.08     13727327.41
#Sta/Elev= 30
  4663.9   520.8  4714.1  518.34  4770.3  517.03  4834.7  518.61    4870  518.33
  4884.5  518.79  4913.8  518.17  4948.5     518  4968.6  517.23  4981.5  513.32
  4988.8  510.36  4996.3   505.9  4996.7   505.4    5001   505.4  5001.3   505.9
  5008.9  507.72  5013.9  509.64    5019  511.59  5029.1  513.29    5064  512.98
  5112.7  517.15  5139.8  518.34  5186.6  519.12  5370.7  523.33  5450.8  523.51
  5480.9  524.85  5542.5  526.28  5580.6  527.25  5641.2  528.87  5696.4  531.18
#Mann= 9 ,-1 , 0
  4663.9     .07       0  4913.8     .12       0  4996.3     .05       0
  5001.3     .12       0  5013.9     .07       0  5112.7     .12       0
  5186.6     .07       0  5542.5     .12       0  5580.6     .07       0
Bank Sta=4996.3,5001.3
XS Rating Curve= 0 ,0
Exp/Cntr=0.3,0.1

Type RM Length L Ch R = 1 ,18384   ,443,443,443
BEGIN DESCRIPTION:
A19582
END DESCRIPTION:
XS GIS Cut Line= 4
      2307936.95     13727275.32      2308123.58     13727579.14
      2308470.81     13727600.84      2308965.59     13727431.58
#Sta/Elev= 30
  4491.2  516.93  4570.3  516.16  4612.9  517.63  4661.9  517.53  4762.4  516.37
  4776.1  516.21    4851  515.87  4906.9  514.36  4919.3  513.26  4929.3  511.45
  4969.4   512.7  4989.5  510.37  4999.5  506.54    5007   505.5  5007.3     505
    5012   505.5  5018.2  514.34  5023.2   512.8  5027.7  514.87  5029.5   515.7
  5149.8  515.88  5189.8  517.23  5421.4  521.38  5472.8  522.47  5517.2  523.93
  5535.6  523.42  5603.5  526.83  5622.9  526.62  5711.4  529.59  5718.6  529.72
#Mann= 11 ,-1 , 0
  4491.2     .07       0  4661.9     .12       0  4762.4     .07       0
  4776.1     .12       0  4906.9     .07       0    5007     .05       0
    5012     .07       0  5027.7     .12       0  5421.4     .07       0
  5472.8     .12       0  5711.4     .07       0
Bank Sta=5007,5012
XS Rating Curve= 0 ,0
Exp/Cntr=0.3,0.1

Type RM Length L Ch R = 1 ,17941   ,777,777,777
BEGIN DESCRIPTION:
A19581
END DESCRIPTION:
XS GIS Cut Line= 3
      2307854.48      13728338.7      2308305.88     13727869.94
      2308981.51     13727566.77
#Sta/Elev= 30
  4516.8  525.72  4532.4  525.36    4586  524.65  4668.3  524.48  4739.1  522.55
  4767.4  522.65  4802.6   520.2  4881.7  518.61  4965.5  515.18  4972.4   513.9
  4979.6  513.91  4984.7  510.32  4993.8  505.44    4998   501.6  4998.4   501.1
  5003.4   501.6  5021.8   509.7  5085.6  510.55  5092.5  510.11  5117.6  511.19
  5167.5  512.44  5276.2  512.82  5291.1  512.46  5308.8   510.1    5331  512.35
  5366.1  513.39    5557  516.73    5693   520.3  5756.5  521.56  5908.1  526.61
#Mann= 10 ,-1 , 0
  4516.8     .07       0  4532.4     .12       0    4586     .07       0
  4881.7     .05       0  4984.7     .07       0    4998     .05       0
  5003.4     .07       0  5117.6     .12       0    5693     .07       0
  5756.5     .12       0
Bank Sta=4998,5003.4
XS Rating Curve= 0 ,0
Exp/Cntr=0.3,0.1

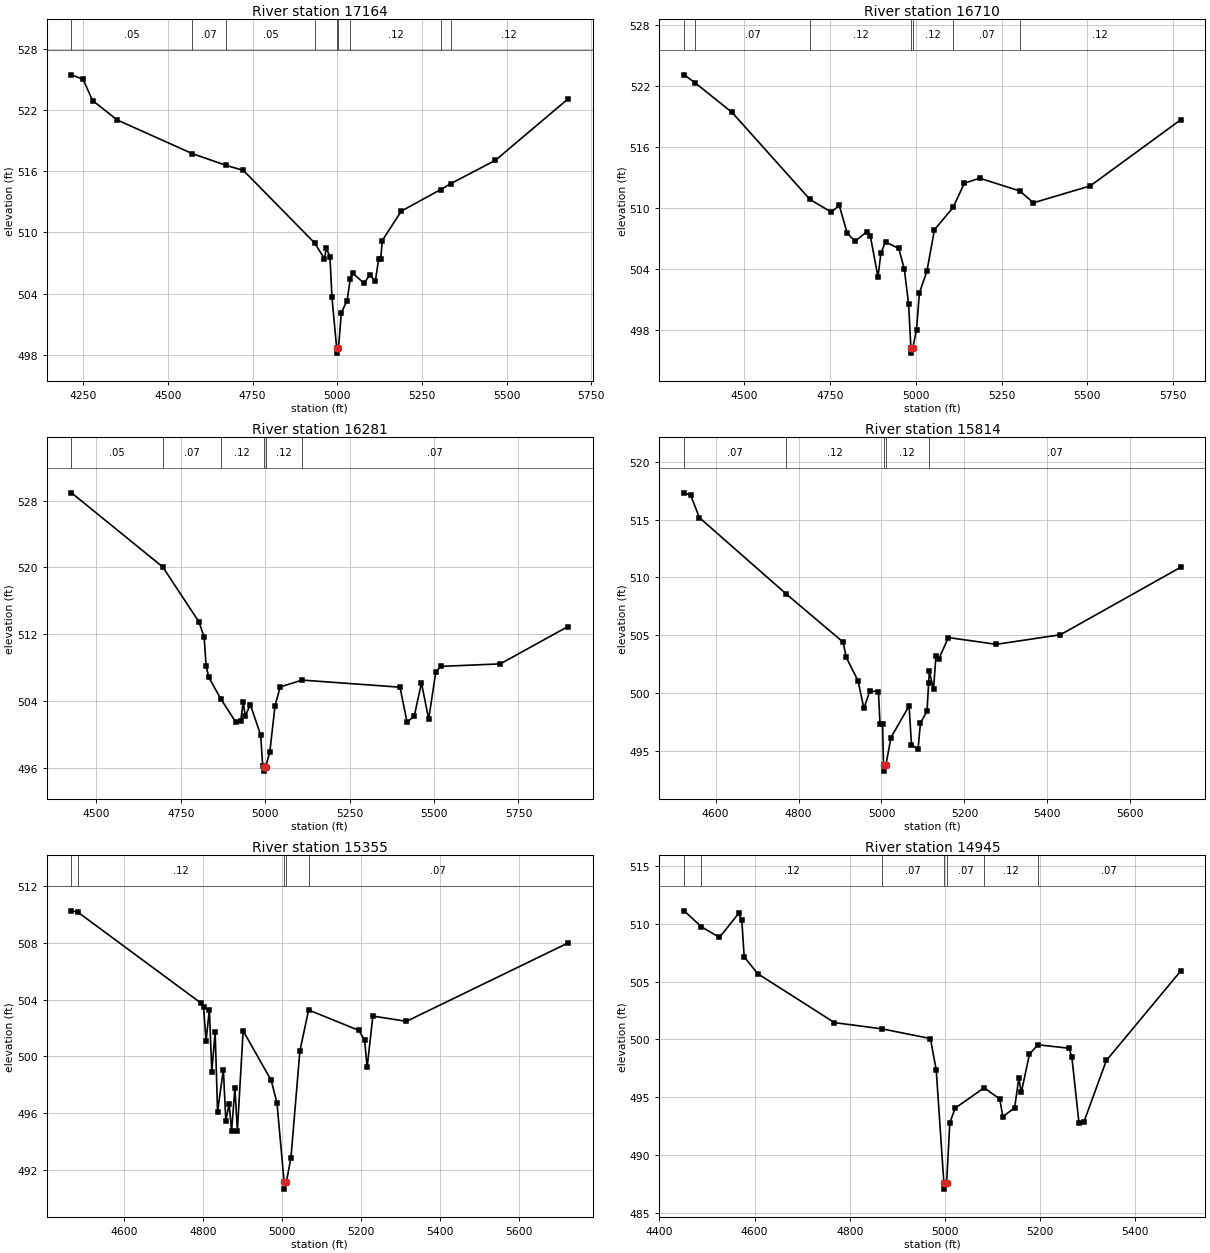
Type RM Length L Ch R = 1 ,17164   ,454,454,454
BEGIN DESCRIPTION:
A19580
END DESCRIPTION:
XS GIS Cut Line= 3
      2307984.71     13728538.34      2308796.33     13728126.02
      2309225.99     13727774.47
#Sta/Elev= 30
  4215.2  525.46  4249.2  525.02  4277.5  522.94  4350.1  521.03  4571.7  517.73
  4672.2  516.57  4722.6  516.08  4933.6  508.94  4961.8  507.41  4967.4  508.43
  4978.2  507.63  4984.1  503.63    4998  498.65  4998.4  498.15  5003.4  498.65
  5011.9  502.13  5028.6  503.28  5038.1  505.39  5045.2  506.01  5079.2  504.99
  5095.3  505.83    5112  505.23    5122  507.35  5127.9  507.35  5132.7   509.2
  5188.7  512.08  5304.8   514.2  5334.6  514.78  5466.5  517.07  5680.7  523.09
#Mann= 9 ,-1 , 0
  4215.2     .05       0  4571.7     .07       0  4672.2     .05       0
  4933.6     .07       0    4998     .05       0  5003.4     .07       0
  5038.1     .12       0  5304.8     .07       0  5334.6     .12       0
Bank Sta=4998,5003.4
XS Rating Curve= 0 ,0
Exp/Cntr=0.3,0.1

Type RM Length L Ch R = 1 ,16710   ,429,429,429
BEGIN DESCRIPTION:
A19579
END DESCRIPTION:
XS GIS Cut Line= 3
      2308210.43     13728816.11      2308982.96      13728468.9
      2309234.71     13727926.33
#Sta/Elev= 30
  4326.2  523.14  4357.1  522.38  4465.7  519.44  4692.5  510.88  4754.6  509.63
  4777.7  510.29  4800.9  507.54    4824  506.77  4858.2  507.71  4868.4  507.24
  4890.4  503.25    4899  505.62  4912.3   506.7  4950.8  506.06  4967.1  504.02
  4979.4  500.62  4986.3  496.26  4986.7  495.76  4991.7  496.26  5002.6  498.07
    5011  501.68  5032.9  503.83  5054.8   507.9  5109.1  510.09  5141.6  512.47
  5186.4  512.97  5303.5  511.71  5342.8  510.55  5508.2  512.21  5771.3  518.71
#Mann= 7 ,-1 , 0
  4326.2     .05       0  4357.1     .07       0  4692.5     .12       0
  4986.3     .05       0  4991.7     .12       0  5109.1     .07       0
  5303.5     .12       0
Bank Sta=4986.3,4991.7
XS Rating Curve= 0 ,0
Exp/Cntr=0.3,0.1

Type RM Length L Ch R = 1 ,16281   ,467,467,467
BEGIN DESCRIPTION:
A19578
END DESCRIPTION:
XS GIS Cut Line= 3
      2308410.04     13729250.15      2309000.32     13728881.23
      2309529.85     13728316.97
#Sta/Elev= 30
  4426.5  528.92  4696.6  520.05    4804  513.46  4819.3  511.63  4825.2  508.15
  4833.3  506.82  4868.3  504.26  4913.6  501.43  4927.6  501.59  4934.9  503.92
  4940.8   502.2  4956.1  503.55  4986.6  499.92  4992.7  496.25  4995.8   496.1
  4996.2   495.6  5001.3   496.1  5013.9  497.94  5029.2  503.43  5044.5  505.68
  5109.2   506.5  5399.2  505.65  5420.2  501.44  5441.6  502.23  5462.7  506.15
  5484.1  501.84  5505.2  507.46  5519.3  508.14  5696.1  508.44  5896.4  512.91
#Mann= 6 ,-1 , 0
  4426.5     .05       0  4696.6     .07       0  4868.3     .12       0
  4995.8     .05       0  5001.3     .12       0  5109.2     .07       0
Bank Sta=4995.8,5001.3
XS Rating Curve= 0 ,0
Exp/Cntr=0.3,0.1

Type RM Length L Ch R = 1 ,15814   ,459,459,459
BEGIN DESCRIPTION:
KRAMS CREEK 33.0
END DESCRIPTION:
XS GIS Cut Line= 3
      2308906.19     13729428.23        2309225.       13729075.
      2309584.99     13728449.41
#Sta/Elev= 30
    4524  517.33  4539.9  517.11  4560.8  515.18  4770.6  508.56  4907.5   504.4
    4915  503.08  4943.4  501.06  4957.6  498.66  4971.8  500.16  4992.7  500.12
  4996.5  497.29  5002.7  497.29  5004.9  493.73  5005.4  493.23  5010.5  493.73
  5022.9  496.14  5066.6  498.88  5072.4  495.51  5088.2  495.11    5094   497.4
  5109.8  498.41  5113.8  500.83  5115.5  501.86  5125.6  500.31  5131.3  503.17
  5138.3  502.94  5161.4   504.8  5276.7  504.21  5431.7  505.04  5721.6  510.88
#Mann= 5 ,-1 , 0
    4524     .07       0  4770.6     .12       0  5004.9     .05       0
  5010.5     .12       0  5113.8     .07       0
Bank Sta=5004.9,5010.5
XS Rating Curve= 0 ,0
Exp/Cntr=0.3,0.1

Type RM Length L Ch R = 1 ,15355   ,410,410,410
BEGIN DESCRIPTION:
KRAMS CREEK 32.0
END DESCRIPTION:
XS GIS Cut Line= 3
      2309102.67     13729489.94        2309525.       13729175.
      2310098.97     13728726.58
#Sta/Elev= 30
  4467.5  510.26  4483.9  510.16  4794.7  503.76  4801.5  503.45  4807.7  501.08
  4816.1   503.3  4822.3  498.93  4830.7  501.71  4836.9   496.1  4851.5  499.07
  4857.7  495.47  4866.1  496.63  4872.3  494.76  4880.7  497.77  4886.9  494.74
  4901.5   501.8  4972.4  498.31    4987  496.73  5005.1  491.14  5005.5  490.64
  5010.8  491.14  5022.4  492.86    5045  500.38    5067  503.27  5194.2  501.83
  5208.7  501.13    5215  499.22  5229.5  502.84  5314.5  502.47  5722.7  507.99
#Mann= 5 ,-1 , 0
  4467.5     .07       0  4483.9     .12       0  5005.1     .05       0
  5010.8     .12       0    5067     .07       0
Bank Sta=5005.1,5010.8
XS Rating Curve= 0 ,0
Exp/Cntr=0.3,0.1

Type RM Length L Ch R = 1 ,14945   ,506,506,506
BEGIN DESCRIPTION:
KRAMS CREEK 31.0
END DESCRIPTION:
XS GIS Cut Line= 3
      2309091.43      13729554.5      2309599.23     13729494.13
      2310110.05     13729346.86
#Sta/Elev= 30
  4452.1  511.15  4488.3  509.77  4526.2  508.84  4566.5  510.92  4573.2  510.35
  4578.2  507.16  4606.7   505.7  4767.9  501.46  4867.9  500.92  4969.5  500.08
  4981.7  497.36  4997.8  487.53  4998.3  487.03  5003.5  487.53  5010.2  492.77
  5021.5  494.05  5082.3  495.81  5115.2  494.84  5121.6  493.31  5146.4  494.07
  5155.2  496.65  5160.4  495.41  5177.6  498.73  5195.3  499.54  5260.9  499.24
  5266.6  498.47  5281.7  492.74  5292.1  492.87  5339.1  498.18  5495.1  505.92
#Mann= 7 ,-1 , 0
  4452.1     .07       0  4488.3     .12       0  4867.9     .07       0
  4997.8     .05       0  5003.5     .07       0  5082.3     .12       0
  5195.3     .07       0
Bank Sta=4997.8,5003.5
XS Rating Curve= 0 ,0
Exp/Cntr=0.3,0.1