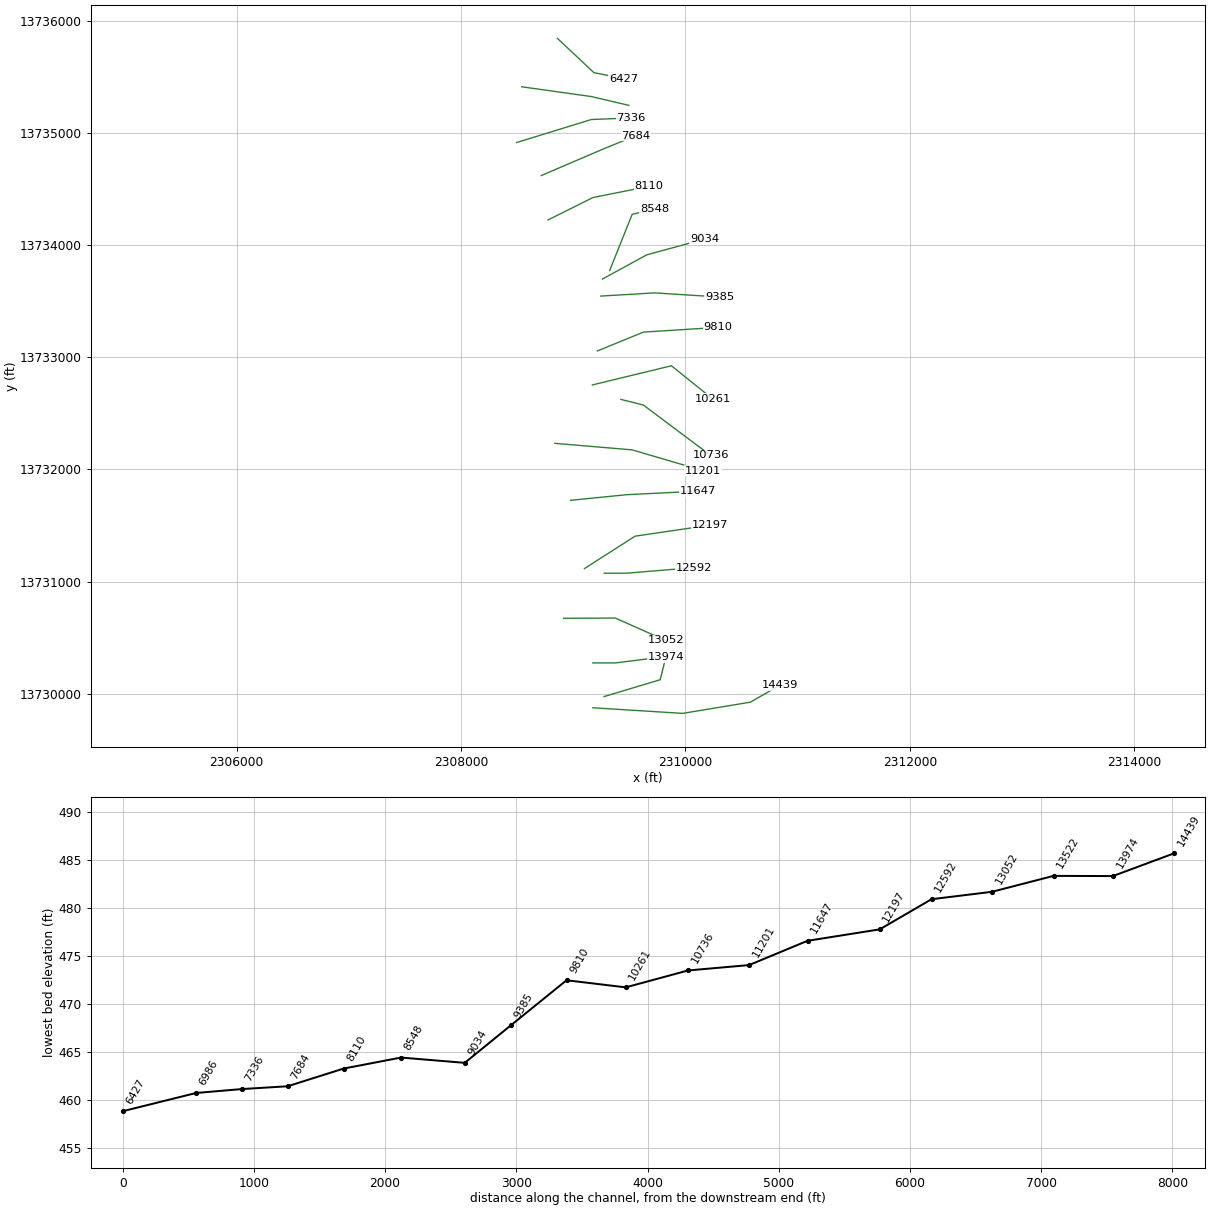
HEC-RAS study KRAMS CREEK.prj: KRAMS CREEK Base Level Engineering

--- KRAMS CREEK.g01 (geometry) --- (continued)

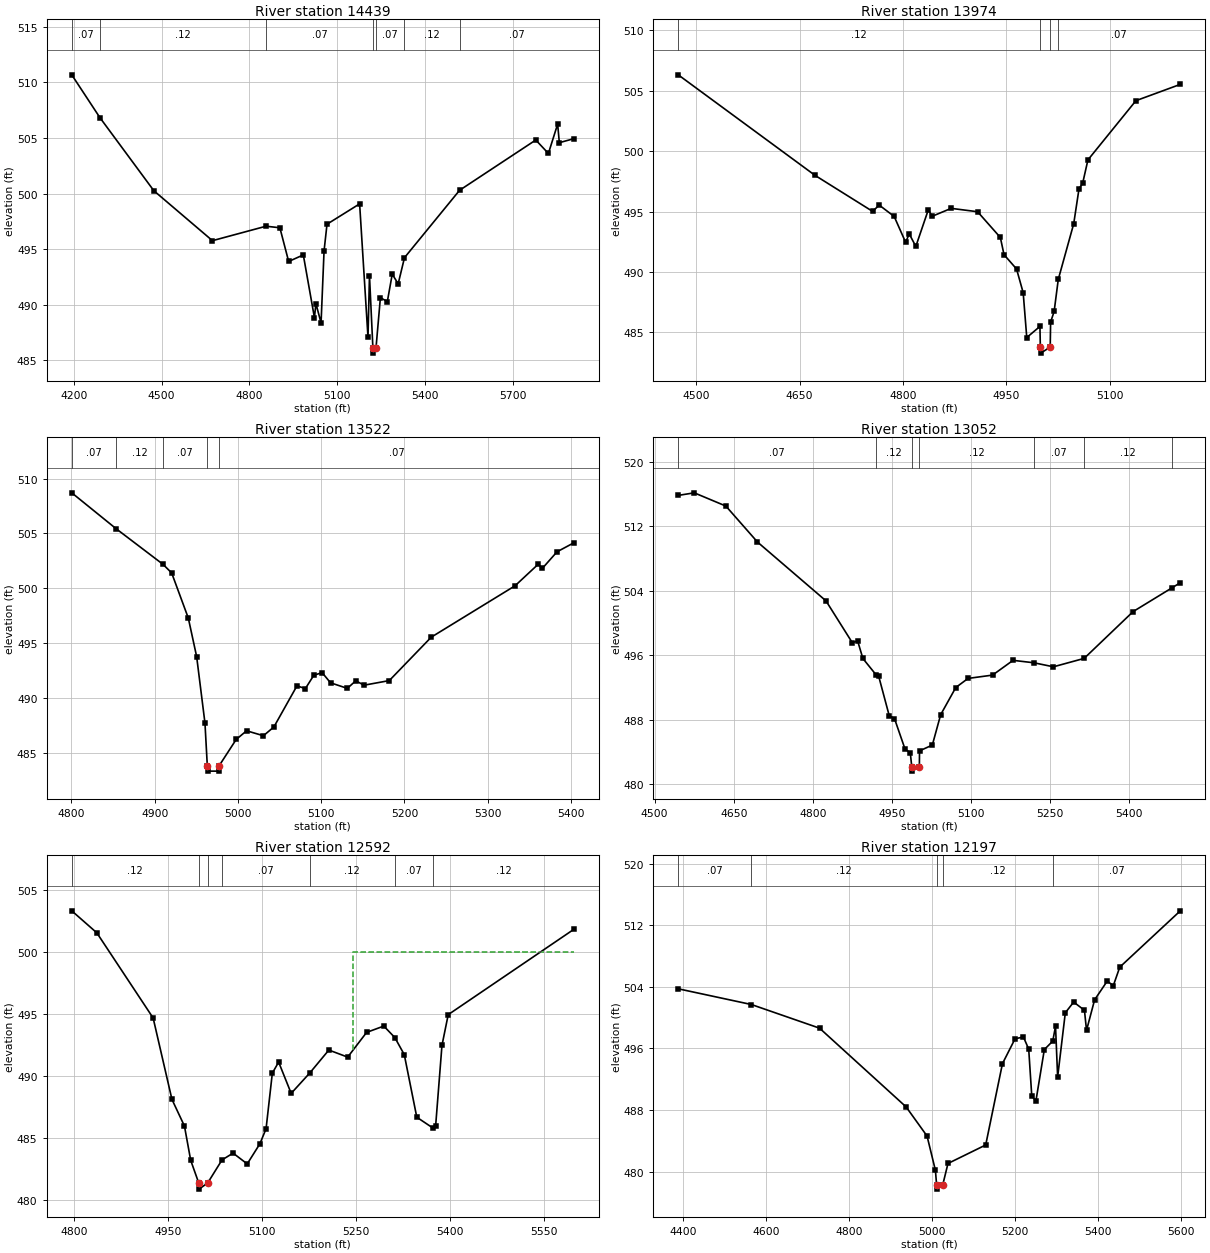
Type RM Length L Ch R = 1 ,14439   ,465,465,465
BEGIN DESCRIPTION:
KRAMS CREEK 30.0
END DESCRIPTION:
XS GIS Cut Line= 4
        2309175.       13729875.        2309975.       13729825.
      2310578.83     13729924.95      2310841.29     13730075.72
#Sta/Elev= 30
  4192.8  510.67  4289.3  506.81  4473.4  500.25  4673.7  495.76    4857  497.06
  4904.2  496.92  4934.2  493.89  4984.3  494.48  5022.3  488.84  5027.4   490.1
    5045  488.37  5055.2  494.83  5065.3  497.24  5176.8  499.07  5205.4  487.08
  5210.5  492.62  5222.1  486.15  5222.6  485.65  5232.9  486.15  5247.8  490.64
  5271.5  490.28  5288.3  492.75  5308.6  491.88  5330.1  494.23  5518.5  500.29
    5779  504.81  5822.1   503.6  5853.7  506.24  5859.5  504.57  5909.1  504.93
#Mann= 7 ,-1 , 0
  4192.8     .07       0  4289.3     .12       0    4857     .07       0
  5222.1     .05       0  5232.9     .07       0  5330.1     .12       0
  5518.5     .07       0
Bank Sta=5222.1,5232.9
XS Rating Curve= 0 ,0
Exp/Cntr=0.3,0.1

Type RM Length L Ch R = 1 ,13974   ,452,452,452
BEGIN DESCRIPTION:
KRAMS CREEK 29.0
END DESCRIPTION:
XS GIS Cut Line= 3
      2309274.97     13729974.99        2309775.       13730125.
        2309825.       13730325.
#Sta/Elev= 30
  4473.9  506.32  4672.3     498  4755.8  495.02  4765.4  495.54  4787.1   494.6
  4803.7  492.46  4808.9  493.16  4818.5  492.12  4836.7  495.17    4842  494.61
  4869.8  495.27  4908.1  494.99  4941.1  492.86  4946.4  491.44  4964.6  490.25
  4974.2  488.29  4979.4  484.58  4998.5   485.5  4999.1  483.79  4999.6  483.29
  5013.4  483.79    5014  485.86  5019.1  486.74  5025.1  489.39  5047.5     494
  5055.2   496.9  5060.4  497.33  5068.1  499.28  5137.7  504.18  5202.1  505.53
#Mann= 4 ,-1 , 0
  4473.9     .12       0  4999.1     .05       0  5013.4     .12       0
  5025.1     .07       0
Bank Sta=4999.1,5013.4
XS Rating Curve= 0 ,0
Exp/Cntr=0.3,0.1

Type RM Length L Ch R = 1 ,13522   ,470,470,470
BEGIN DESCRIPTION:
KRAMS CREEK 28.0
END DESCRIPTION:
XS GIS Cut Line= 3
      2309175.04       13730275.        2309375.       13730275.
      2309775.03       13730325.
#Sta/Elev= 30
  4800.4   508.7  4853.6  505.43  4910.1  502.17  4920.4  501.39  4940.4  497.27
  4950.4  493.76  4960.4  487.69  4963.2  483.81  4963.7  483.31    4977  483.31
  4977.5  483.81  4997.9   486.2  5010.4  486.99  5030.6  486.54  5043.2  487.34
  5070.9  491.09    5081  490.84  5091.1  492.05  5101.1   492.3  5111.2  491.37
  5131.4  490.86  5141.5  491.55  5151.5  491.15  5181.8  491.57  5232.2  495.53
  5332.9  500.22  5360.6  502.18  5365.7  501.81  5383.3  503.32  5403.5  504.14
#Mann= 5 ,-1 , 0
  4800.4     .07       0  4853.6     .12       0  4910.1     .07       0
  4963.2     .05       0  4977.5     .07       0
Bank Sta=4963.2,4977.5
XS Rating Curve= 0 ,0
Exp/Cntr=0.3,0.1

Type RM Length L Ch R = 1 ,13052   ,460,460,460
BEGIN DESCRIPTION:
KRAMS CREEK 27.0
END DESCRIPTION:
XS GIS Cut Line= 3
      2308914.65     13730672.86        2309375.       13730675.
        2309825.       13730475.
#Sta/Elev= 30
  4544.7  515.82  4575.1  516.14  4635.1   514.5  4695.1  510.04  4825.1  502.75
  4875.1  497.56  4885.1   497.8  4895.1  495.61  4920.2  493.58  4925.1  493.41
  4945.1  488.52  4955.1  488.16  4975.1  484.38  4985.1  483.93  4987.9  482.15
  4988.4  481.65  5002.3  482.15  5002.6  484.16  5026.9  484.88  5042.7  488.64
  5071.4  492.01  5094.7  493.14  5141.2  493.55  5180.1  495.38  5219.4  495.08
  5256.7  494.58    5315  495.62  5407.9  501.42  5481.8  504.37  5497.5     505
#Mann= 7 ,-1 , 0
  4544.7     .07       0  4920.2     .12       0  4987.9     .05       0
  5002.3     .12       0  5219.4     .07       0    5315     .12       0
  5481.8     .07       0
Bank Sta=4987.9,5002.3
XS Rating Curve= 0 ,0
Exp/Cntr=0.3,0.1

Type RM Length L Ch R = 1 ,12592   ,395,395,395
BEGIN DESCRIPTION:
KRAMS CREEK 26.0
END DESCRIPTION:
XS GIS Cut Line= 3
      2309274.98       13731075.        2309475.       13731075.
      2310075.01       13731125.
#Sta/Elev= 30
  4795.7  503.29  4835.7  501.52  4925.7  494.66  4955.7  488.11  4975.7  485.96
  4985.7   483.2  4998.5  481.38    4999  480.88  5012.9  481.38  5035.7  483.23
  5053.4  483.78    5076  482.91  5096.1  484.52  5106.1  485.74  5116.1  490.22
  5126.2  491.11  5146.2  488.59  5175.9  490.23  5206.4  492.08  5236.5  491.51
  5266.7   493.5  5294.2  494.01  5311.9  493.08  5326.9  491.71  5346.9  486.67
    5373  485.79    5377  485.97  5387.1  492.45  5397.1  494.93  5597.8   501.8
#Mann= 7 ,-1 , 0
  4795.7     .12       0  4998.5     .05       0  5012.9     .12       0
  5035.7     .07       0  5175.9     .12       0  5311.9     .07       0
    5373     .12       0
#XS Ineff= 2 , 0
       0                    5245       0     500
Permanent Ineff=
       F       F
Bank Sta=4998.5,5012.9
XS Rating Curve= 0 ,0
Exp/Cntr=0.3,0.1

Type RM Length L Ch R = 1 ,12197   ,550,550,550
BEGIN DESCRIPTION:
KRAMS CREEK 25.0
END DESCRIPTION:
XS GIS Cut Line= 3
      2309099.83     13731116.26      2309551.68     13731405.33
      2310219.59     13731503.55
#Sta/Elev= 30
  4387.9  503.74  4564.4   501.7  4728.9  498.63  4937.8  488.41  4988.3  484.63
  5008.5  480.17  5011.4  478.24  5011.9  477.74  5025.9  478.24  5038.8  481.07
  5129.8  483.47  5170.2  494.02  5200.6  497.25  5220.8  497.49  5233.6  495.91
    5241  489.79  5251.1  489.22  5271.3  495.86  5291.6  496.95  5298.3  498.88
  5303.4  492.29  5321.9  500.63  5342.1  502.02  5368.1  500.95  5373.1  498.35
  5392.6  502.31  5422.9  504.73  5437.8  504.16  5453.3  506.55  5599.4  513.86
#Mann= 5 ,-1 , 0
  4387.9     .07       0  4564.4     .12       0  5011.4     .05       0
  5025.9     .12       0  5291.6     .07       0
Bank Sta=5011.4,5025.9
XS Rating Curve= 0 ,0
Exp/Cntr=0.3,0.1

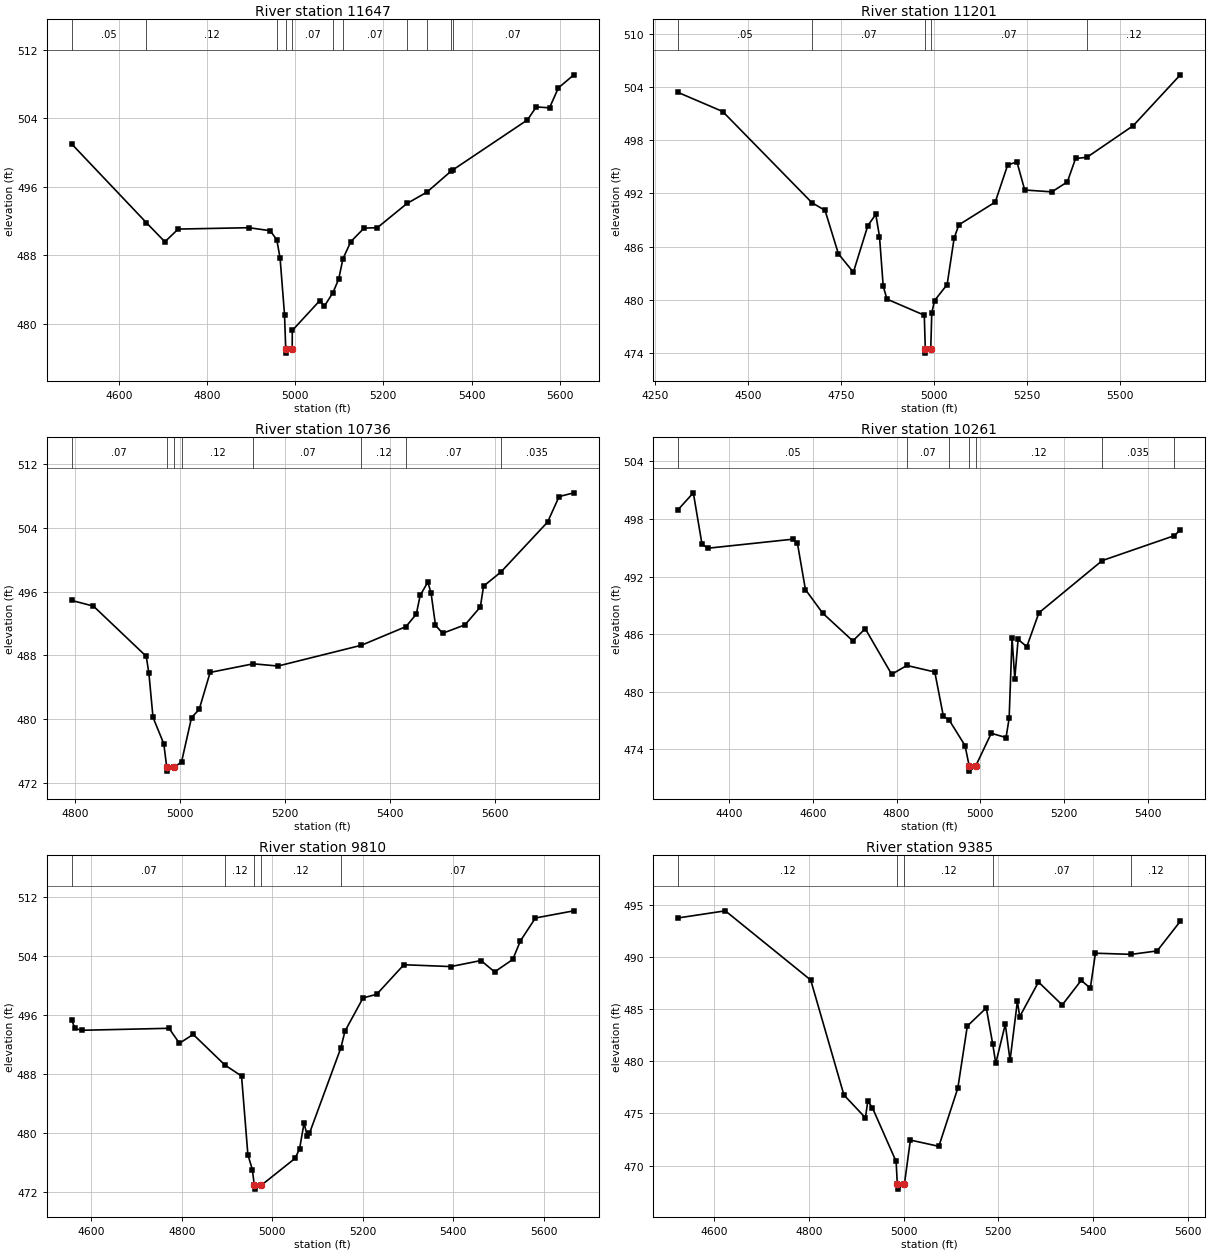
Type RM Length L Ch R = 1 ,11647   ,446,446,446
BEGIN DESCRIPTION:
KRAMS CREEK 24.0
END DESCRIPTION:
XS GIS Cut Line= 3
      2308974.97       13731725.        2309475.       13731775.
      2310110.09     13731806.65
#Sta/Elev= 30
  4493.6  500.99  4662.5  491.81  4704.7  489.56  4734.8  491.05  4895.6  491.21
  4943.4  490.86  4958.5   489.8    4966  487.62    4976  481.05  4978.7  477.05
  4979.2  476.55  4993.4  477.05  4993.6   479.2  5056.2   482.7  5066.2  482.03
  5085.9  483.63  5098.9  485.22  5108.4  487.57  5126.3  489.58  5156.3  491.16
  5186.4  491.21  5253.9  494.05  5298.7  495.36  5352.9  497.79  5357.2  497.95
  5526.8  503.81  5546.8  505.33  5576.8  505.22  5596.9  507.55    5632  509.08
#Mann= 11 ,-1 , 0
  4493.6     .05       0  4662.5     .12       0  4958.5     .07       0
  4978.7     .05       0  4993.4     .07       0  5085.9     .12       0
  5108.4     .07       0  5253.9     .12       0  5298.7     .07       0
  5352.9     .12       0  5357.2     .07       0
Bank Sta=4978.7,4993.4
XS Rating Curve= 0 ,0
Exp/Cntr=0.3,0.1

Type RM Length L Ch R = 1 ,11201   ,465,465,465
BEGIN DESCRIPTION:
KRAMS CREEK 23.0
END DESCRIPTION:
XS GIS Cut Line= 3
      2308836.02     13732233.23        2309525.       13732175.
      2310156.28     13731989.53
#Sta/Elev= 30
  4313.3  503.37  4432.7  501.23  4672.4  490.97  4707.9  490.09  4743.8   485.2
    4784  483.13  4822.8  488.37  4844.2  489.65  4854.2  487.15  4864.2  481.56
  4874.3   480.1  4974.6  478.29  4977.3  474.52  4977.8  474.02    4992  474.52
  4994.7  478.54  5002.2  479.94    5036  481.74  5054.8  486.96  5067.3  488.46
  5165.3  491.03  5198.7  495.21  5223.6  495.55  5244.5  492.39  5317.4  492.18
  5359.1   493.3  5381.2  495.94  5411.7  496.07  5536.3  499.64  5662.7  505.36
#Mann= 5 ,-1 , 0
  4313.3     .05       0  4672.4     .07       0  4977.3     .05       0
    4992     .07       0  5411.7     .12       0
Bank Sta=4977.3,4992
XS Rating Curve= 0 ,0
Exp/Cntr=0.3,0.1

Type RM Length L Ch R = 1 ,10736   ,475,475,475
BEGIN DESCRIPTION:
KRAMS CREEK 22.0
END DESCRIPTION:
XS GIS Cut Line= 3
      2309424.96     13732625.01        2309625.       13732575.
        2310225.       13732125.
#Sta/Elev= 30
  4794.1  494.88  4835.4  494.17  4935.9  487.87    4941  485.74  4948.8  480.21
  4969.4  476.89  4974.9  473.96  4975.4  473.46  4989.7  473.96  5003.2  474.62
  5022.2  480.18  5036.8  481.21  5057.6  485.85  5139.8  486.93  5186.8  486.65
  5345.8  489.26  5430.6   491.6  5450.3  493.17  5457.6  495.51  5472.2  497.19
  5478.4   495.8  5486.8  491.77  5500.3  490.76    5543  491.82  5572.2  494.06
  5578.4  496.68  5611.4  498.45  5700.3  504.72  5722.2  507.92  5750.3  508.39
#Mann= 8 ,-1 , 0
  4794.1     .07       0  4974.9     .05       0  4989.7     .07       0
  5003.2     .12       0  5139.8     .07       0  5345.8     .12       0
  5430.6     .07       0  5611.4    .035       0
Bank Sta=4974.9,4989.7
XS Rating Curve= 0 ,0
Exp/Cntr=0.3,0.1

Type RM Length L Ch R = 1 ,10261   ,451,451,451
BEGIN DESCRIPTION:
KRAMS CREEK 21.0
END DESCRIPTION:
XS GIS Cut Line= 3
      2309170.04     13732753.82        2309875.       13732925.
      2310243.31     13732628.78
#Sta/Elev= 30
  4278.9  498.99  4314.9  500.73  4335.5   495.4  4349.2  494.95  4551.6  495.89
  4563.2   495.5  4582.4  490.64  4623.6  488.18  4695.6  485.28  4725.1  486.56
  4788.2   481.8  4824.5  482.72  4891.1  482.04  4911.7   477.4  4925.1  477.05
  4963.2  474.37  4973.4   472.2  4973.9   471.7  4988.4   472.2  5025.9  475.65
  5061.1   475.2  5068.5  477.19  5075.5  485.59    5082  481.35  5089.9  485.44
  5110.7  484.68  5139.5  488.21  5290.6  493.66  5462.7  496.26    5477  496.86
#Mann= 7 ,-1 , 0
  4278.9     .05       0  4824.5     .07       0  4925.1     .12       0
  4973.4     .05       0  4988.4     .12       0  5290.6    .035       0
  5462.7     .12       0
Bank Sta=4973.4,4988.4
XS Rating Curve= 0 ,0
Exp/Cntr=0.3,0.1

Type RM Length L Ch R = 1 ,9810    ,425,425,425
BEGIN DESCRIPTION:
KRAMS CREEK 20.0
END DESCRIPTION:
XS GIS Cut Line= 3
      2309214.93     13733056.91        2309625.       13733225.
      2310289.77     13733267.39
#Sta/Elev= 30
  4557.1  495.38  4563.9  494.24  4578.8  493.98    4772  494.25  4794.9  492.22
  4825.4  493.42  4895.6  489.26  4932.2  487.78  4946.2  477.12  4956.2  475.06
  4960.4  472.94  4960.9  472.44  4975.4  472.94  5050.4  476.61  5060.4  477.89
  5070.4  481.43  5077.1  479.67  5082.2     480  5151.8  491.62  5160.6  493.85
  5200.7  498.37  5230.8  498.86  5290.9  502.87  5394.6  502.62  5461.2  503.44
  5491.3   501.9  5531.4  503.58  5548.3   506.1  5581.5  509.21  5666.4  510.18
#Mann= 5 ,-1 , 0
  4557.1     .07       0  4895.6     .12       0  4960.4     .05       0
  4975.4     .12       0  5151.8     .07       0
Bank Sta=4960.4,4975.4
XS Rating Curve= 0 ,0
Exp/Cntr=0.3,0.1

Type RM Length L Ch R = 1 ,9385    ,351,351,351
BEGIN DESCRIPTION:
KRAMS CREEK 19.0
END DESCRIPTION:
XS GIS Cut Line= 3
      2309245.81     13733546.63        2309725.       13733575.
       2310303.8     13733538.21
#Sta/Elev= 30
  4524.3  493.72  4623.7   494.4    4804  487.77  4874.1  476.76  4919.5  474.57
  4924.5  476.17  4934.2  475.54  4984.3  470.39  4986.8  468.24  4987.3  467.74
  5001.9  468.24  5014.4  472.44  5074.5  471.84  5114.6  477.42  5134.6  483.36
  5174.7   485.1  5188.3  481.62  5194.7   479.8  5214.8  483.54  5224.8  480.07
  5240.3  485.72  5245.3  484.27  5284.9  487.58    5335  485.38  5375.1  487.74
  5394.3  486.99  5405.1  490.34    5481  490.23  5535.4  490.56  5584.3   493.4
#Mann= 5 ,-1 , 0
  4524.3     .12       0  4986.8     .05       0  5001.9     .12       0
  5188.3     .07       0    5481     .12       0
Bank Sta=4986.8,5001.9
XS Rating Curve= 0 ,0
Exp/Cntr=0.3,0.1

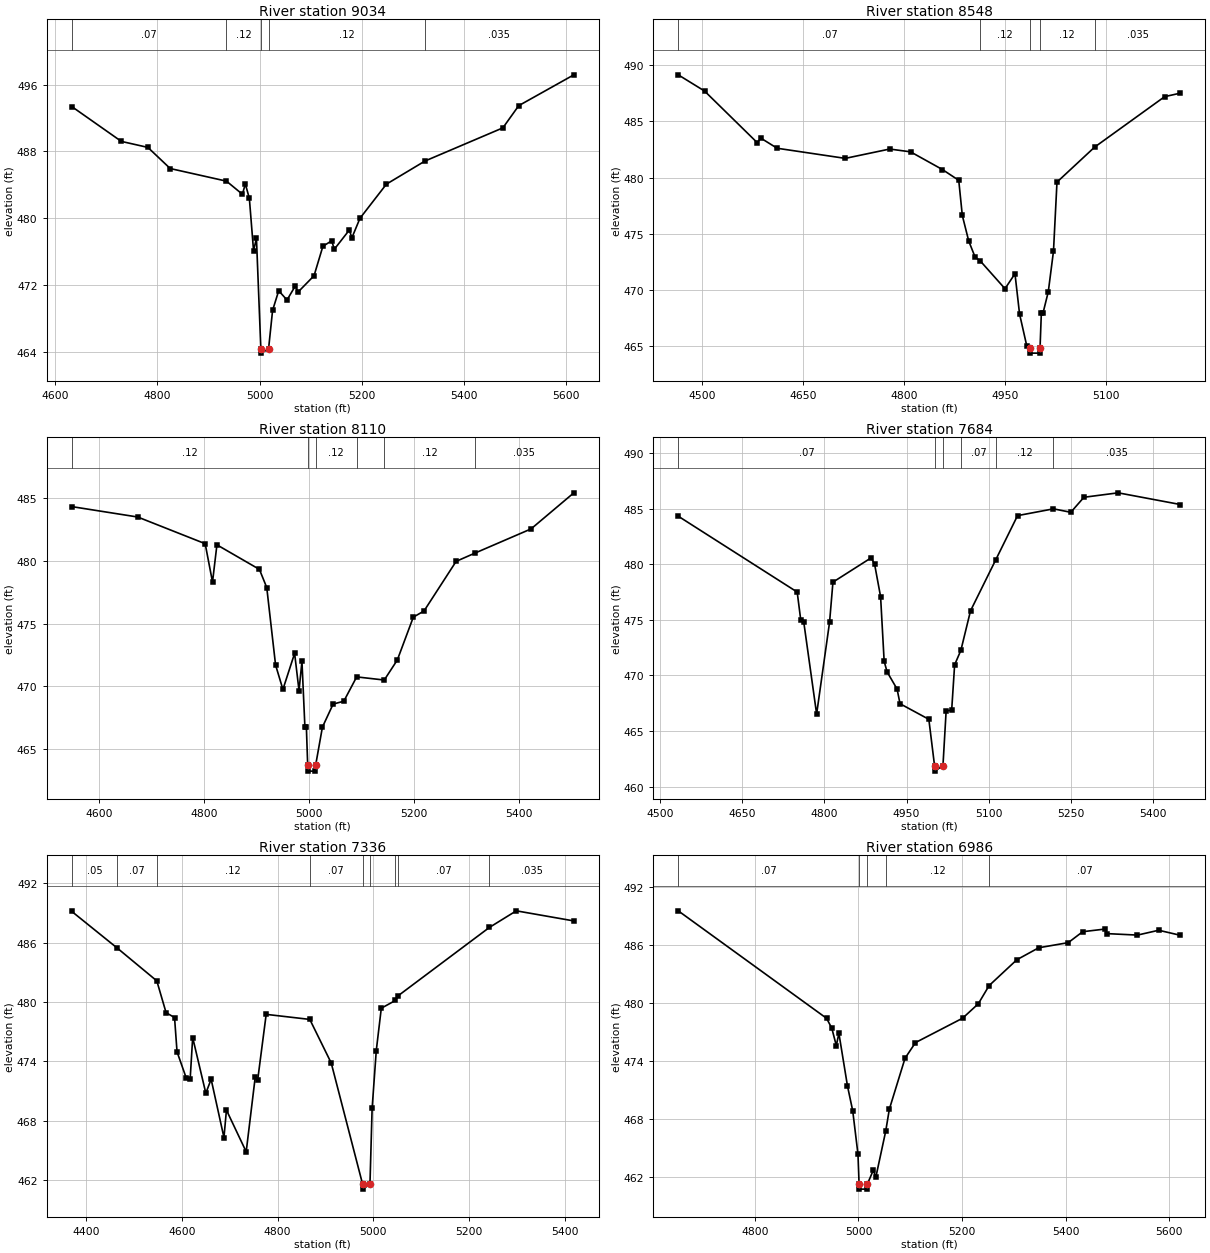
Type RM Length L Ch R = 1 ,9034    ,486,486,486
BEGIN DESCRIPTION:
KRAMS CREEK 18.0
END DESCRIPTION:
XS GIS Cut Line= 3
      2309259.78     13733698.16      2309655.52     13733914.27
       2310169.1     13734054.59
#Sta/Elev= 30
  4632.2  493.36  4729.3  489.19  4781.3  488.47    4825  485.94  4935.2  484.43
  4966.4  482.86  4972.1   484.1    4980  482.37  4988.2  476.11  4993.9  477.58
  5002.5  464.34    5003  463.84  5017.6  464.34  5025.5  468.96  5037.5  471.31
  5053.7   470.2  5069.8  471.86  5075.5  471.16  5106.7  473.11    5124  476.63
  5141.2  477.29  5146.4  476.28  5175.7  478.57  5180.9  477.66  5196.6  479.98
  5248.4  484.07    5324  486.84  5476.5  490.81  5507.6  493.47  5615.5  497.16
#Mann= 5 ,-1 , 0
  4632.2     .07       0  4935.2     .12       0  5002.5     .05       0
  5017.6     .12       0    5324    .035       0
Bank Sta=5002.5,5017.6
XS Rating Curve= 0 ,0
Exp/Cntr=0.3,0.1

Type RM Length L Ch R = 1 ,8548    ,438,438,438
BEGIN DESCRIPTION:
KRAMS CREEK 17.0
END DESCRIPTION:
XS GIS Cut Line= 3
      2309325.02     13733775.04        2309525.       13734275.
      2309724.97     13734324.99
#Sta/Elev= 30
  4465.2  489.14  4504.2   487.7  4582.3  483.11  4587.7  483.51  4611.9  482.61
  4712.9  481.71  4778.8  482.54  4809.8  482.29  4856.9  480.72  4881.2  479.76
  4886.5  476.63    4896  474.36  4905.4  472.94  4913.4  472.57  4949.8  470.12
  4964.6  471.45  4971.4  467.87  4982.1  465.03  4986.7  464.89  4987.2  464.39
  5001.3  464.39  5001.8  464.89  5003.7  467.96  5006.2  467.96    5014  469.85
  5021.7  473.45  5026.9   479.6  5082.7  482.71  5186.6   487.2  5209.8  487.51
#Mann= 5 ,-1 , 0
  4465.2     .07       0  4913.4     .12       0  4986.7     .05       0
  5001.8     .12       0  5082.7    .035       0
Bank Sta=4986.7,5001.8
XS Rating Curve= 0 ,0
Exp/Cntr=0.3,0.1

Type RM Length L Ch R = 1 ,8110    ,426,426,426
BEGIN DESCRIPTION:
KRAMS CREEK 16.0
END DESCRIPTION:
XS GIS Cut Line= 3
      2308775.03     13734225.01        2309175.       13734425.
      2309675.01       13734525.
#Sta/Elev= 30
    4548  484.35  4673.7  483.52  4802.3  481.39  4816.3  478.33  4824.7   481.3
  4905.7  479.34  4919.7  477.89  4936.5  471.71  4950.5  469.76  4972.8  472.64
  4981.2  469.67  4986.8     472  4992.4  466.78  4995.2  466.78  4997.7  463.74
  4998.2  463.24  5012.5  463.24    5013  463.74  5025.8  466.75  5046.2  468.59
  5066.6  468.82  5091.1  470.76  5143.7  470.51  5168.6  472.11  5199.1  475.53
  5219.5  476.02  5280.7  479.98  5316.6  480.64  5423.5  482.57  5505.1  485.45
#Mann= 6 ,-1 , 0
    4548     .12       0  4997.7     .05       0    5013     .12       0
  5091.1     .07       0  5143.7     .12       0  5316.6    .035       0
Bank Sta=4997.7,5013
XS Rating Curve= 0 ,0
Exp/Cntr=0.3,0.1

Type RM Length L Ch R = 1 ,7684    ,348,348,348
BEGIN DESCRIPTION:
KRAMS CREEK 15.0
END DESCRIPTION:
XS GIS Cut Line= 3
      2308715.37     13734621.48      2309265.43     13734857.22
      2309560.04     13734977.87
#Sta/Elev= 30
  4533.1  484.32  4750.3   477.5  4756.8  474.99  4762.2  474.84  4785.8  466.53
  4809.4  474.78  4815.6  478.39  4885.5  480.58  4891.7  479.99  4902.6  477.09
  4909.1  471.28  4914.5  470.32  4932.7  468.78  4938.1  467.46  4990.7  466.06
  5001.1   461.9  5001.6   461.4  5016.5   461.9  5022.3  466.82  5032.4  466.88
  5037.8  470.96  5049.2  472.26  5066.8  475.81    5113  480.41  5152.7  484.37
  5218.3  484.98  5249.9  484.67  5273.9  486.02  5336.4  486.42  5449.9  485.37
#Mann= 6 ,-1 , 0
  4533.1     .07       0  5001.1     .05       0  5016.5     .07       0
  5049.2     .07       0    5113     .12       0  5218.3    .035       0
Bank Sta=5001.1,5016.5
XS Rating Curve= 0 ,0
Exp/Cntr=0.3,0.1

Type RM Length L Ch R = 1 ,7336    ,350,350,350
BEGIN DESCRIPTION:
KRAMS CREEK 14.0
END DESCRIPTION:
XS GIS Cut Line= 3
       2308496.5     13734916.17      2309161.59     13735121.03
      2309515.19     13735135.06
#Sta/Elev= 30
  4369.6  489.14  4465.2  485.42  4547.4  482.13  4566.8  478.92  4584.5  478.43
  4589.7  474.97  4608.7  472.36  4617.2  472.27  4622.4  476.41  4649.9  470.79
    4661   472.2  4687.8  466.32    4693  469.09  4734.3  464.88  4753.1  472.38
  4758.4  472.16  4776.1  478.75  4867.3  478.24  4912.1  473.84  4977.7  461.61
  4978.2  461.11  4993.1  461.61  4997.6  469.25  5006.3   475.1  5016.8  479.37
  5046.2  480.15  5052.1  480.63  5242.7  487.52  5299.1   489.2  5419.4  488.18
#Mann= 9 ,-1 , 0
  4369.6     .05       0  4465.2     .07       0  4547.4     .12       0
  4867.3     .07       0  4977.7     .05       0  4993.1     .07       0
  5046.2     .12       0  5052.1     .07       0  5242.7    .035       0
Bank Sta=4977.7,4993.1
XS Rating Curve= 0 ,0
Exp/Cntr=0.3,0.1

Type RM Length L Ch R = 1 ,6986    ,559,559,559
BEGIN DESCRIPTION:
A19577
END DESCRIPTION:
XS GIS Cut Line= 3
      2308541.35      13735412.9      2309161.59     13735325.89
      2309495.56     13735247.31
#Sta/Elev= 30
    4652  489.49  4938.4  478.37  4948.5  477.35  4957.2  475.55  4962.2  476.82
  4978.8  471.36  4988.9   468.8    4999  464.33  5001.2   461.2  5001.7   460.7
  5016.5   460.7    5017   461.2  5028.5  462.64  5033.6  461.96  5052.6   466.7
  5059.6  468.97  5089.9  474.24  5110.1  475.86    5201  478.38  5231.3  479.87
  5252.3  481.76  5305.8  484.43  5348.1  485.67  5405.1   486.2  5432.9  487.33
  5475.3   487.6  5480.4  487.13  5538.6  486.98  5579.7  487.48  5621.4  486.96
#Mann= 5 ,-1 , 0
    4652     .07       0  5001.2     .05       0    5017     .07       0
  5052.6     .12       0  5252.3     .07       0
Bank Sta=5001.2,5017
XS Rating Curve= 0 ,0
Exp/Cntr=0.3,0.1

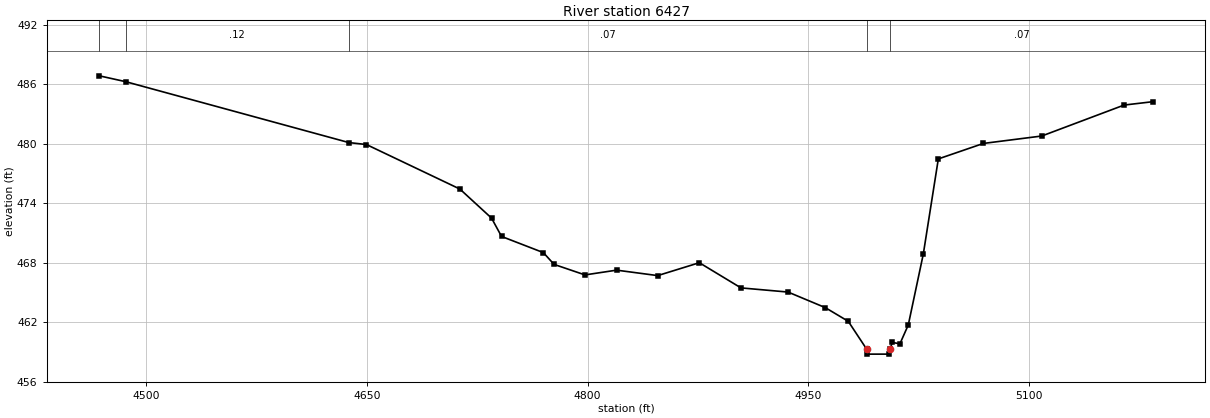
Type RM Length L Ch R = 1 ,6427    ,485,485,485
BEGIN DESCRIPTION:
A19576
END DESCRIPTION:
XS GIS Cut Line= 3
      2308858.53     13735845.05      2309184.04     13735539.18
      2309447.84     13735485.86
#Sta/Elev= 30
  4468.2  486.87  4486.1  486.28  4637.7  480.14  4649.7  479.94  4713.2  475.45
  4734.7  472.52  4741.5  470.67  4769.9  469.04  4777.2  467.85  4798.2  466.79
  4819.7  467.27  4847.6  466.72  4875.9  468.02  4904.2  465.48  4936.2  465.06
  4961.5  463.49  4977.1  462.11  4989.6   459.3  4990.1   458.8  5004.9   458.8
  5005.4   459.3  5007.1  459.98  5012.2  459.84  5017.9  461.75  5028.1   468.9
  5038.3  478.49  5068.9  480.05  5108.6   480.8  5164.5  483.92    5184  484.26
#Mann= 5 ,-1 , 0
  4468.2     .07       0  4486.1     .12       0  4637.7     .07       0
  4989.6     .05       0  5005.4     .07       0
Bank Sta=4989.6,5005.4
XS Rating Curve= 0 ,0
Exp/Cntr=0.3,0.1