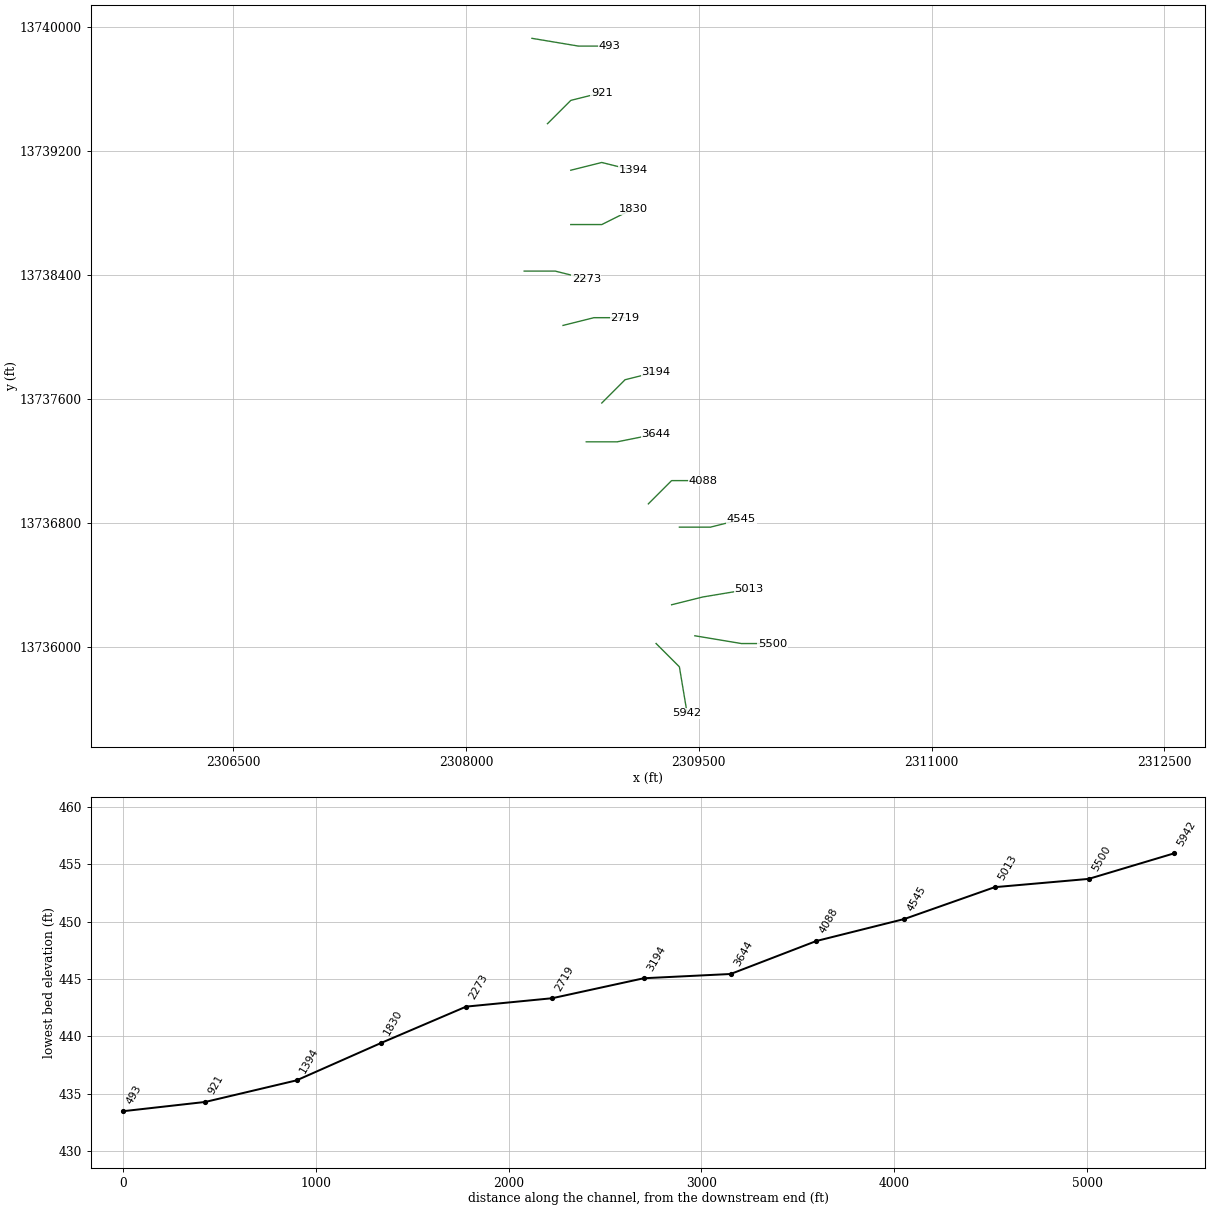
HEC-RAS study KRAMS CREEK.prj: KRAMS CREEK Base Level Engineering

--- KRAMS CREEK.g01 (geometry) --- (continued)

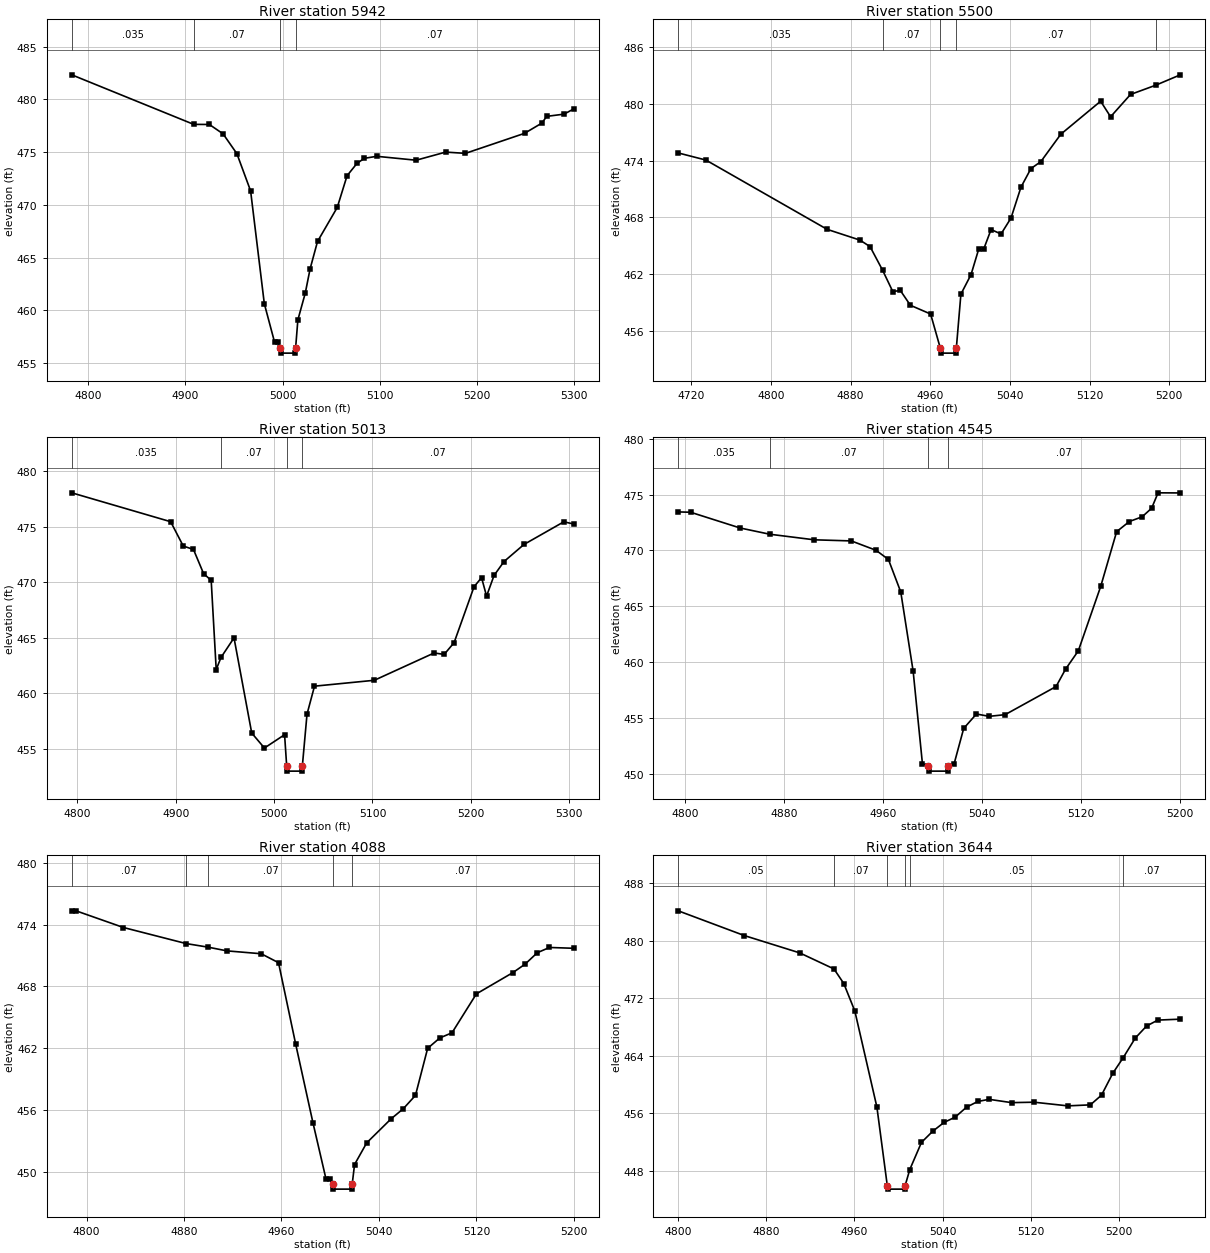
Type RM Length L Ch R = 1 ,5942    ,442,442,442
BEGIN DESCRIPTION:
KRAMS CREEK 13.0
END DESCRIPTION:
XS GIS Cut Line= 3
      2309224.97     13736025.03        2309375.       13735875.
        2309425.     13735575.02
#Sta/Elev= 30
  4783.1  482.33  4908.5  477.63  4924.6  477.62  4938.7  476.73  4952.9  474.85
    4967  471.32  4981.1  460.62  4991.7  456.95  4995.3  456.95  4997.5  456.43
    4998  455.93  5012.8  455.93  5013.3  456.43  5015.6  459.08  5023.2  461.62
  5028.2  463.93  5035.8  466.52  5056.1  469.75  5066.2  472.76  5076.4  473.93
    5084  474.41  5096.7   474.6  5137.2  474.23  5167.6     475  5187.9  474.88
  5248.7  476.78  5266.5  477.75  5271.5  478.39  5289.3   478.6  5299.4   479.1
#Mann= 4 ,-1 , 0
  4783.1    .035       0  4908.5     .07       0  4997.5     .05       0
  5013.3     .07       0
Bank Sta=4997.5,5013.3
XS Rating Curve= 0 ,0
Exp/Cntr=0.3,0.1

Type RM Length L Ch R = 1 ,5500    ,487,487,487
BEGIN DESCRIPTION:
KRAMS CREEK 12.0
END DESCRIPTION:
XS GIS Cut Line= 3
      2309475.04     13736074.99        2309775.       13736025.
        2309975.       13736025.
#Sta/Elev= 30
    4707   474.8  4734.8  474.05  4856.5  466.75  4889.4  465.62  4899.6  464.93
  4912.2  462.44  4922.4   460.2    4930  460.31  4940.1  458.75  4960.4  457.83
  4970.2  454.21  4970.7  453.71  4985.7  453.71  4986.2  454.21  4990.8  459.92
    5001  461.99  5008.6  464.64  5013.6  464.64  5021.1  466.73  5031.1  466.26
  5041.1  467.94  5051.1  471.19  5061.1  473.15  5071.1  473.89  5091.1  476.77
  5131.1  480.25  5141.1  478.61  5161.1  480.96  5186.5  481.94  5211.1  483.03
#Mann= 5 ,-1 , 0
    4707    .035       0  4912.2     .07       0  4970.2     .05       0
  4986.2     .07       0  5186.5     .05       0
Bank Sta=4970.2,4986.2
XS Rating Curve= 0 ,0
Exp/Cntr=0.3,0.1

Type RM Length L Ch R = 1 ,5013    ,468,468,468
BEGIN DESCRIPTION:
KRAMS CREEK 11.0
END DESCRIPTION:
XS GIS Cut Line= 3
      2309325.03     13736275.01        2309525.       13736325.
      2309825.04     13736375.01
#Sta/Elev= 30
  4794.4  478.05  4894.9  475.45  4907.7  473.26  4918.1  472.95  4928.4  470.77
  4936.1  470.17  4941.2  462.14  4946.1  463.23  4959.3  464.99  4977.3  456.42
  4990.2  455.07  5010.7  456.27  5012.8  453.49  5013.3  452.99  5028.3  452.99
  5028.8  453.49  5033.5  458.12  5041.1  460.64  5101.9  461.17  5162.7  463.63
  5172.9   463.5    5183  464.56  5203.3   469.6  5210.9  470.41    5216  468.75
  5223.6  470.61  5233.7  471.86    5254   473.4  5294.5  475.44  5304.7  475.24
#Mann= 4 ,-1 , 0
  4794.4    .035       0  4946.1     .07       0  5012.8     .05       0
  5028.8     .07       0
Bank Sta=5012.8,5028.8
XS Rating Curve= 0 ,0
Exp/Cntr=0.3,0.1

Type RM Length L Ch R = 1 ,4545    ,457,457,457
BEGIN DESCRIPTION:
KRAMS CREEK 10.0
END DESCRIPTION:
XS GIS Cut Line= 3
      2309375.05       13736775.        2309575.       13736775.
      2309774.99       13736825.
#Sta/Elev= 30
  4794.4  473.45  4804.4  473.42  4844.4  472.01  4868.4  471.45  4904.4  470.95
  4934.4  470.85  4954.4  470.01  4964.4  469.19  4974.4  466.27  4984.4  459.18
  4991.9   450.9  4996.7  450.72  4997.2  450.22  5012.2  450.22  5012.7  450.72
  5017.5  450.86  5025.3  454.05  5035.6  455.34  5045.9  455.13  5058.8  455.28
    5100   457.8  5107.7  459.36    5118     461  5136.1  466.77    5149  471.68
  5159.3  472.59  5169.6  473.01  5177.3  473.78  5182.5  475.16  5200.5  475.15
#Mann= 4 ,-1 , 0
  4794.4    .035       0  4868.4     .07       0  4996.7     .05       0
  5012.7     .07       0
Bank Sta=4996.7,5012.7
XS Rating Curve= 0 ,0
Exp/Cntr=0.3,0.1

Type RM Length L Ch R = 1 ,4088    ,444,444,444
BEGIN DESCRIPTION:
KRAMS CREEK 9.0
END DESCRIPTION:
XS GIS Cut Line= 3
      2309175.02     13736925.02        2309325.       13737075.
        2309525.       13737075.
#Sta/Elev= 30
  4787.9  475.34  4791.4  475.34  4830.3  473.72  4881.7  472.16  4899.8  471.81
  4915.2  471.45  4943.4  471.17  4957.6   470.3  4971.7  462.38  4985.9  454.73
  4996.5  449.32    5000  449.32    5002   448.8  5002.5   448.3  5017.6   448.3
  5018.1   448.8    5020  450.69    5030   452.8    5050  455.13    5060  456.11
    5070  457.41    5080  461.98    5090  462.99    5100  463.49    5120  467.27
    5150  469.34    5160  470.16    5170  471.27    5180  471.78    5200   471.7
#Mann= 5 ,-1 , 0
  4787.9     .07       0  4881.7    .035       0  4899.8     .07       0
    5002     .05       0  5018.1     .07       0
Bank Sta=5002,5018.1
XS Rating Curve= 0 ,0
Exp/Cntr=0.3,0.1

Type RM Length L Ch R = 1 ,3644    ,450,450,450
BEGIN DESCRIPTION:
KRAMS CREEK 8.0
END DESCRIPTION:
XS GIS Cut Line= 3
      2308775.02       13737325.        2308975.       13737325.
      2309224.97     13737374.99
#Sta/Elev= 30
  4800.4  484.17  4860.4  480.72  4910.4  478.32  4941.5  476.08  4950.4  474.05
  4960.4  470.22  4980.4  456.85  4989.8  445.93  4990.3  445.43  5005.5  445.43
    5006  445.93  5010.2  448.16  5020.8  451.94    5031  453.49  5041.2  454.71
  5051.4  455.46  5061.6  456.84  5071.8  457.63    5082  457.93  5102.4  457.47
  5122.8  457.53  5153.4  457.02  5173.8  457.16  5183.9  458.51  5194.1  461.55
  5203.6  463.74  5214.5  466.46  5224.7  468.13  5234.9  468.96  5255.3  469.09
#Mann= 6 ,-1 , 0
  4800.4     .05       0  4941.5     .07       0  4989.8     .05       0
    5006     .07       0  5010.2     .05       0  5203.6     .07       0
Bank Sta=4989.8,5006
XS Rating Curve= 0 ,0
Exp/Cntr=0.3,0.1

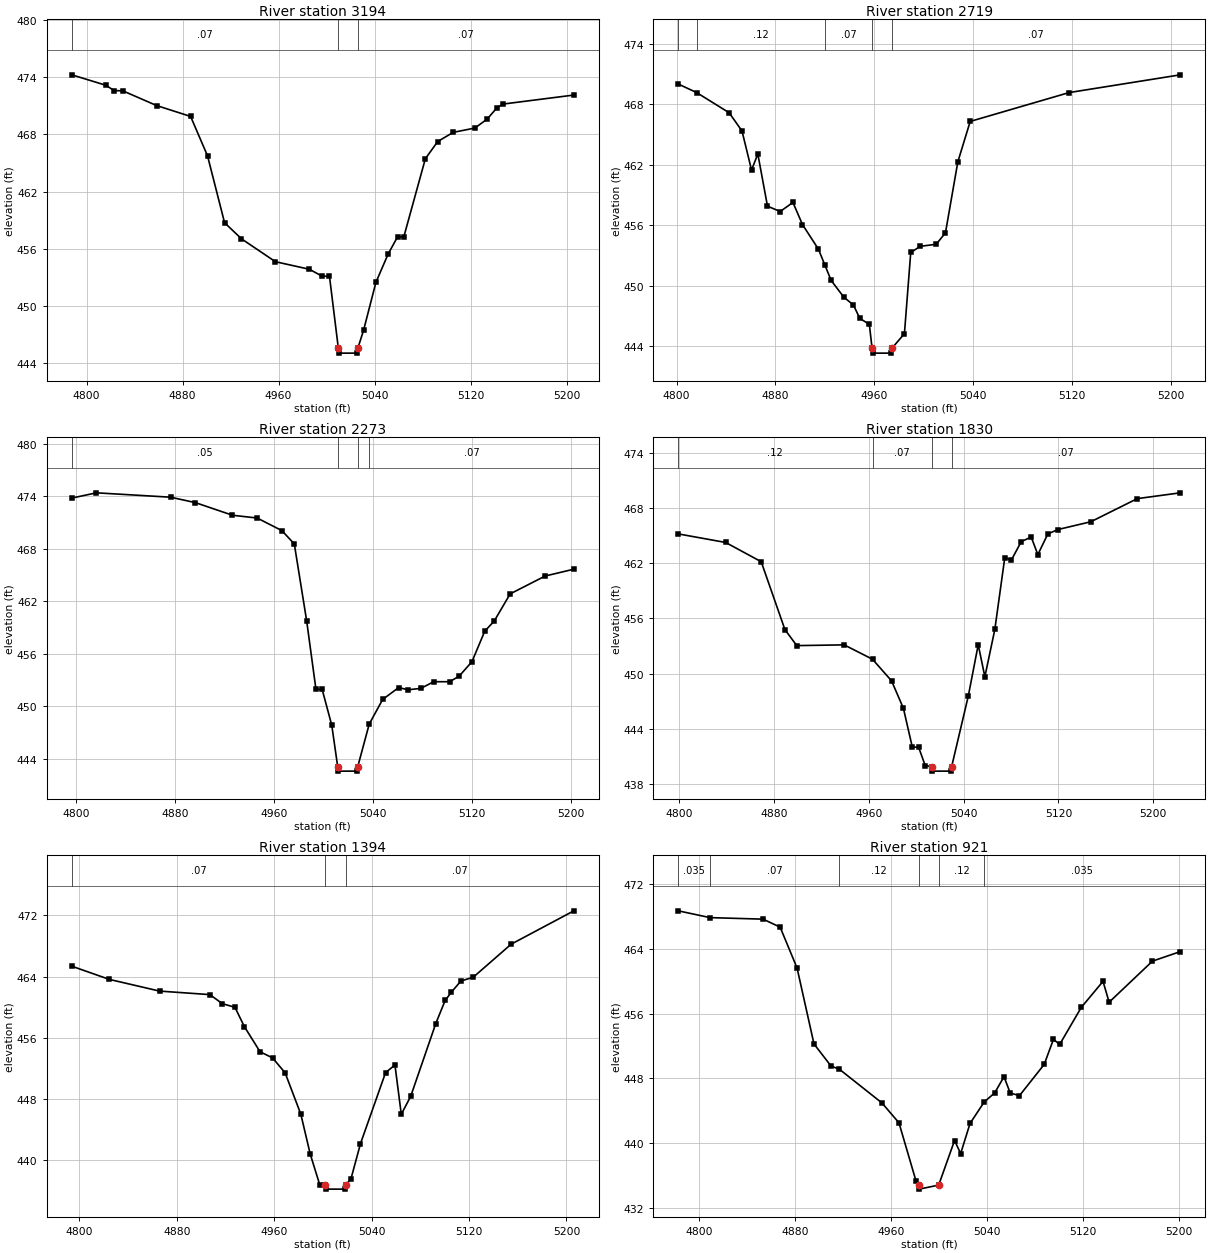
Type RM Length L Ch R = 1 ,3194    ,475,475,475
BEGIN DESCRIPTION:
KRAMS CREEK 7.0
END DESCRIPTION:
XS GIS Cut Line= 3
      2308874.99     13737574.99        2309025.       13737725.
        2309225.       13737775.
#Sta/Elev= 30
  4787.7  474.23    4816  473.14  4823.1  472.57  4830.1  472.56  4858.4  471.01
  4886.7  469.87  4900.8  465.74    4915  458.73  4929.1  457.04  4957.4  454.64
  4985.7  453.85  4996.3  453.12  5002.4  453.12  5009.8  445.56  5010.3  445.06
  5025.5  445.06    5026  445.56  5030.8  447.45  5041.1  452.48  5051.4  455.48
  5059.1  457.24  5064.3  457.23  5082.3  465.44  5092.6  467.24  5105.5   468.2
  5123.5  468.65  5133.8  469.59  5141.6  470.73  5146.7  471.16    5206  472.11
#Mann= 3 ,-1 , 0
  4787.7     .07       0  5009.8     .05       0    5026     .07       0
Bank Sta=5009.8,5026
XS Rating Curve= 0 ,0
Exp/Cntr=0.3,0.1

Type RM Length L Ch R = 1 ,2719    ,446,446,446
BEGIN DESCRIPTION:
KRAMS CREEK 6.0
END DESCRIPTION:
XS GIS Cut Line= 3
      2308624.99       13738075.        2308825.       13738125.
      2309025.03       13738125.
#Sta/Elev= 30
  4801.4     470  4816.3  469.15  4842.6  467.15    4853  465.34  4860.7  461.47
  4865.8  463.06  4873.6  457.89  4883.9  457.36  4894.2  458.26  4901.9  456.07
  4914.8  453.63  4920.1  452.03  4925.1  450.53  4935.4  448.86  4943.1   448.1
  4948.3  446.76    4956  446.18  4958.2  443.82  4958.7  443.32  4973.9  443.32
  4974.4  443.82  4984.4  445.25  4989.5   453.3  4997.3  453.91  5010.1  454.11
  5017.6  455.25  5027.6  462.28  5037.6  466.29  5117.6  469.15  5207.6  470.91
#Mann= 5 ,-1 , 0
  4801.4     .07       0  4816.3     .12       0  4920.1     .07       0
  4958.2     .05       0  4974.4     .07       0
Bank Sta=4958.2,4974.4
XS Rating Curve= 0 ,0
Exp/Cntr=0.3,0.1

Type RM Length L Ch R = 1 ,2273    ,443,443,443
BEGIN DESCRIPTION:
KRAMS CREEK 5.0
END DESCRIPTION:
XS GIS Cut Line= 3
      2308375.04       13738425.        2308575.       13738425.
      2308774.99       13738375.
#Sta/Elev= 30
  4796.2  473.77  4816.2  474.37  4876.2  473.87  4896.2  473.25  4926.2  471.81
  4946.2  471.49  4966.2  470.05  4976.2  468.53  4986.2  459.74  4993.7  451.93
  4998.7  451.93  5006.5  447.83  5011.3  443.09  5011.8  442.59    5027  442.59
  5027.5  443.09  5036.8  447.97  5047.7  450.78  5060.6  452.13  5068.3  451.88
  5078.6  452.04  5088.9   452.8  5101.8   452.8  5109.5  453.43  5119.9  455.09
  5130.2  458.56  5137.9  459.73  5150.8  462.83  5179.1  464.87  5202.3  465.65
#Mann= 4 ,-1 , 0
  4796.2     .05       0  5011.3     .05       0  5027.5     .05       0
  5036.8     .07       0
Bank Sta=5011.3,5027.5
XS Rating Curve= 0 ,0
Exp/Cntr=0.3,0.1

Type RM Length L Ch R = 1 ,1830    ,436,436,436
BEGIN DESCRIPTION:
KRAMS CREEK 4.0
END DESCRIPTION:
XS GIS Cut Line= 3
        2308675.       13738725.        2308875.       13738725.
      2309074.99       13738825.
#Sta/Elev= 30
  4799.2  465.17  4839.2  464.24  4869.2  462.15  4889.2  454.78  4899.2  453.04
  4939.2  453.12  4963.1  451.56  4979.2  449.21  4989.2  446.22  4996.7  442.01
    5002  442.01  5007.6     440  5013.2  439.91  5013.7  439.41  5029.4  439.41
  5029.9  439.91  5043.9  447.55  5052.3  453.14  5057.9  449.66  5066.3  454.79
  5074.7  462.59  5080.3  462.34  5088.6  464.33    5097  464.83  5102.6  462.92
    5111  465.16  5119.4  465.64  5147.3  466.49  5186.5     469  5222.8  469.63
#Mann= 4 ,-1 , 0
  4799.2     .12       0  4963.1     .07       0  5013.2     .05       0
  5029.9     .07       0
Bank Sta=5013.2,5029.9
XS Rating Curve= 0 ,0
Exp/Cntr=0.3,0.1

Type RM Length L Ch R = 1 ,1394    ,473,473,473
BEGIN DESCRIPTION:
KRAMS CREEK 3.0
END DESCRIPTION:
XS GIS Cut Line= 3
      2308675.01       13739075.        2308875.       13739125.
        2309075.       13739075.
#Sta/Elev= 30
  4793.8  465.36  4824.7  463.63  4865.9   462.1  4907.2  461.64  4917.5  460.45
  4927.8  459.98  4935.5  457.46  4948.4  454.16  4958.7  453.35    4969   451.4
  4981.9  445.98  4989.6  440.77  4997.4  436.76  5001.9  436.67  5002.4  436.17
  5018.1  436.17  5018.6  436.67  5023.1  437.53  5030.9  442.13  5051.5  451.43
  5059.2  452.42  5064.4  445.97  5072.1  448.31  5092.7  457.84  5100.4  460.87
  5105.6  461.97  5113.3  463.41  5123.6  463.93  5154.6  468.24  5206.1  472.61
#Mann= 3 ,-1 , 0
  4793.8     .07       0  5001.9     .05       0  5018.6     .07       0
Bank Sta=5001.9,5018.6
XS Rating Curve= 0 ,0
Exp/Cntr=0.3,0.1

Type RM Length L Ch R = 1 ,921     ,428,428,428
BEGIN DESCRIPTION:
KRAMS CREEK 2.0
END DESCRIPTION:
XS GIS Cut Line= 3
      2308524.99     13739374.99        2308675.       13739525.
        2308875.       13739575.
#Sta/Elev= 30
  4782.9   468.7  4809.4  467.86  4853.6  467.67  4867.8  466.68  4881.9  461.63
    4896  452.24  4910.2  449.51  4917.2  449.11  4952.6  444.95  4966.8  442.49
  4980.9  435.34  4983.2  434.79  4983.7  434.29  4999.9  434.79  5013.1   440.3
  5018.2  438.69    5026  442.41  5037.8  445.06  5046.6   446.2  5054.3  448.19
  5059.5  446.17  5067.2  445.85  5087.8  449.71  5095.5  452.81  5100.7  452.18
  5118.7  456.76  5136.8  459.98  5141.9   457.4    5178  462.48  5201.2  463.66
#Mann= 6 ,-1 , 0
  4782.9    .035       0  4809.4     .07       0  4917.2     .12       0
  4983.2     .05       0  4999.9     .12       0  5037.8    .035       0
Bank Sta=4983.2,4999.9
XS Rating Curve= 0 ,0
Exp/Cntr=0.3,0.1

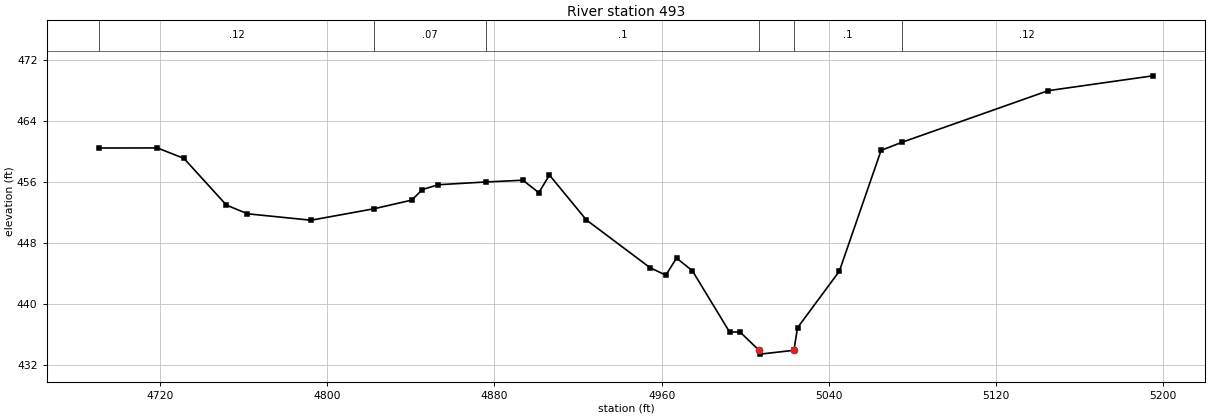
Type RM Length L Ch R = 1 ,493     ,0,0,0
BEGIN DESCRIPTION:
KRAMS CREEK 1.0
END DESCRIPTION:
XS GIS Cut Line= 3
      2308425.04     13739924.99        2308725.       13739875.
      2308925.01       13739875.
#Sta/Elev= 30
  4690.9  460.43  4718.7  460.44  4731.4  459.07  4751.7  452.97  4761.8  451.83
  4792.2  450.99  4822.2  452.48  4840.4  453.62  4845.5     455  4853.1  455.63
  4875.8  455.99  4893.6  456.22  4901.2  454.59  4906.3  456.89    4924  451.02
  4954.4  444.79    4962   443.8  4967.1  446.04  4974.7  444.38  4992.5  436.37
  4997.5  436.37  5006.6  433.98  5007.1  433.48  5023.3  433.98    5025  436.93
    5045  444.31    5065  460.12    5075  461.18    5145  467.93    5195  469.87
#Mann= 6 ,-1 , 0
  4690.9     .12       0  4822.2     .07       0  4875.8      .1       0
  5006.6     .05       0  5023.3      .1       0    5075     .12       0
Bank Sta=5006.6,5023.3
XS Rating Curve= 0 ,0
Exp/Cntr=0.3,0.1

Chan Stop Cuts=-1
Use User Specified Reach Order=0
Composite Channel Slope=5