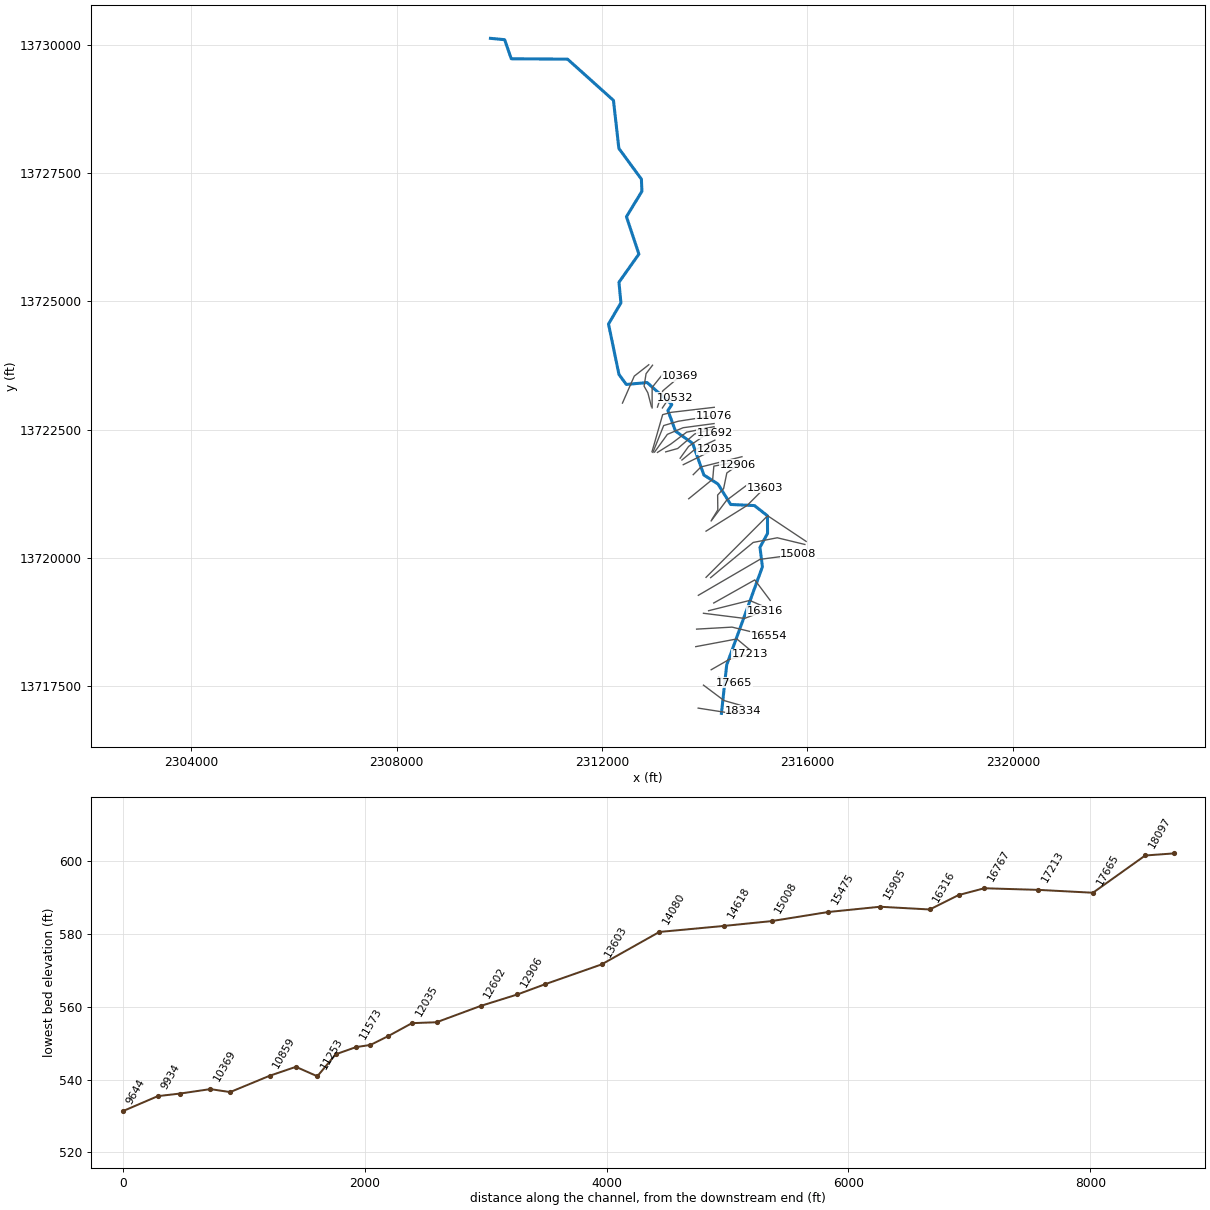
--- KRAMS TRIBUTARY 1.prj (project) ---

Proj Title=KRAMS TRIBUTARY 1 Base Level Engineering
Current Plan=p01
Default Exp/Contr=0.3,0.1
English Units
Geom File=g01
Flow File=f01
Plan File=p01
Y Axis Title=Elevation
X Axis Title(PF)=Main Channel Distance
X Axis Title(XS)=Station
BEGIN DESCRIPTION:
KRAMS TRIBUTARY 1
END DESCRIPTION:
DSS Export Rating Curves= 0
DSS Export Rating Curve Sorted= 0
DSS Export Volume Flow Curves= 0
DXF OffsetX= 0
DXF OffsetY= 0
DXF ScaleX= 1
DXF ScaleY= 10

--- KRAMS TRIBUTARY 1.p01 (plan) ---

Plan Title=Multiple Run
Short Identifier=Multiple
Geom File=g01
Flow File=f01
Subcritical Flow
K Sum by GR= 0
Std Step Tol= 0.01
Critical Tol= 0.01
Num of Std Step Trials= 20
Max Error Tol= 0.3
Flow Tol Ratio= 0.001
Split Flow NTrial= 30
Split Flow Tol= 0.02
Split Flow Ratio= 0.02
Log Output Level= 0
Friction Slope Method= 1
Unsteady Friction Slope Method= 2
Unsteady Bridges Friction Slope Method= 1
Parabolic Critical Depth
Global Vel Dist=  1 , 1 , 1
Global Log Level= 0
CheckData=True
Encroach Param= -1, 0, 0, 0
BEGIN DESCRIPTION:
Multiple Run
END DESCRIPTION:

--- KRAMS TRIBUTARY 1.f01 (steady flow) ---

Flow Title=Multiple
Number of Profiles=7
Profile Names=10-year,25-year,50-year,1pct_min,100-year,1pct_plu,500-year
River Rch & RM= KRAMS TRIBUTARY ,Reach-1,18334
     687    1126    1529    1005    2006    4003    3423
River Rch & RM= KRAMS TRIBUTARY ,Reach-1,17213
    1058    1768    2431    1617    3226    6437    5634
River Rch & RM= KRAMS TRIBUTARY ,Reach-1,9644
    1492    2541    3540    2382    4753    9484    8501
River Rch & RM= KRAMS TRIBUTARY ,Reach-1,8865
    1668    2840    3954    2658    5304   10582    9465
River Rch & RM= KRAMS TRIBUTARY ,Reach-1,833
    1753    2991    4170    2807    5601   11176   10023
Boundary for River Rch & Prof#=KRAMS TRIBUTARY ,Reach-1,1
Up Type=0
Dn Type=3
Dn Slope=0.01
Boundary for River Rch & Prof#=KRAMS TRIBUTARY ,Reach-1,2
Up Type=0
Dn Type=3
Dn Slope=0.01
Boundary for River Rch & Prof#=KRAMS TRIBUTARY ,Reach-1,3
Up Type=0
Dn Type=3
Dn Slope=0.01
Boundary for River Rch & Prof#=KRAMS TRIBUTARY ,Reach-1,4
Up Type=0
Dn Type=3
Dn Slope=0.01
Boundary for River Rch & Prof#=KRAMS TRIBUTARY ,Reach-1,5
Up Type=0
Dn Type=3
Dn Slope=0.01
Boundary for River Rch & Prof#=KRAMS TRIBUTARY ,Reach-1,6
Up Type=0
Dn Type=3
Dn Slope=0.01
Boundary for River Rch & Prof#=KRAMS TRIBUTARY ,Reach-1,7
Up Type=0
Dn Type=3
Dn Slope=0.01

--- KRAMS TRIBUTARY 1.g01 (geometry) ---

Geom Title=Existing Conditions

River Reach=KRAMS TRIBUTARY ,Reach-1
Reach XY= 30
      2314325.00     13716975.00      2314427.26     13717919.06
      2315123.20     13719831.11      2315075.51     13720209.79
      2315223.20     13720481.11      2315221.54     13720823.50
      2314969.07     13721022.76      2314504.84     13721044.58
      2314258.50     13721442.05      2313982.75     13721618.55
      2313764.48     13722234.77      2313430.52     13722472.57
      2313282.34     13722875.10      2313358.80     13722991.67
      2312877.44     13723419.53      2312471.58     13723382.81
      2312328.75     13723576.55      2312125.25     13724559.78
      2312366.96     13724971.68      2312328.55     13725373.53
      2312716.96     13725921.68      2312474.70     13726650.12
      2312775.39     13727145.13      2312765.85     13727381.73
      2312326.62     13727981.03      2312221.47     13728916.51
      2311327.44     13729719.52      2310230.61     13729726.92
      2310101.82     13730098.72      2309825.00     13730125.00

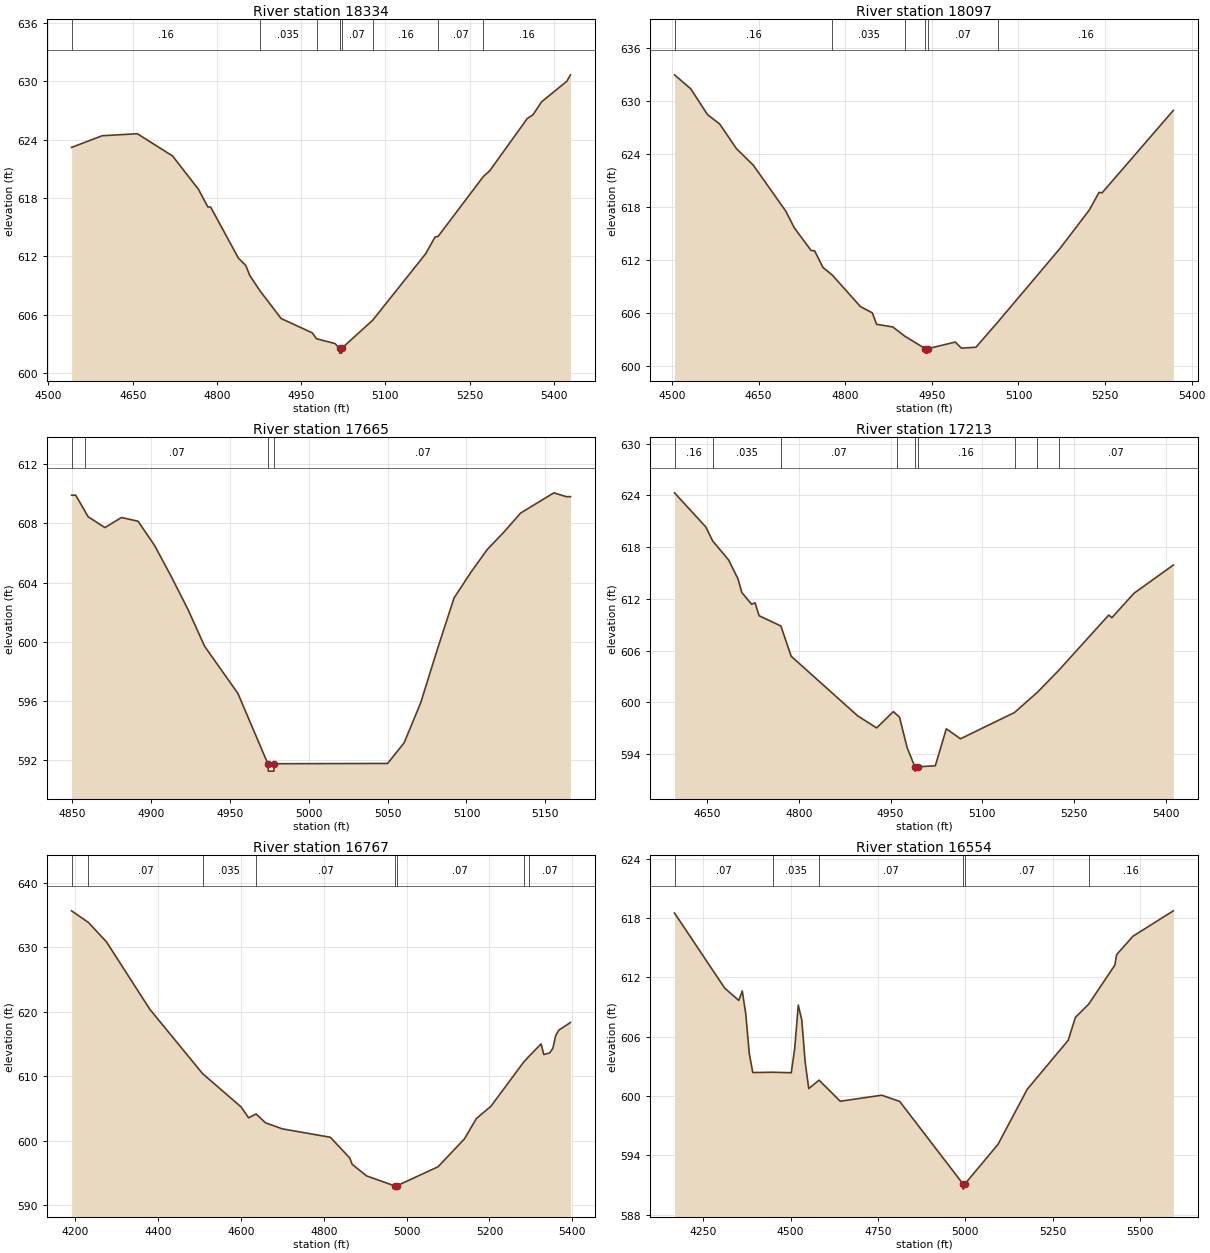
Type RM Length L Ch R = 1,18334,237,237,237
BEGIN DESCRIPTION:
A19607
END DESCRIPTION:
XS GIS Cut Line= 3
      2313871.68     13717077.64      2314427.21     13716990.83
      2314751.40     13717025.41
#Sta/Elev= 30
  4541.2  623.20  4595.5  624.40  4658.2  624.61  4721.0  622.32  4767.2  618.88
  4783.7  617.08  4788.8  617.06  4838.1  611.82  4851.5  611.04  4858.3  610.04
  4877.2  608.40  4914.3  605.59  4969.7  604.12  4977.3  603.51  5010.1  603.02
  5018.3  602.53  5018.5  602.03  5022.0  602.03  5022.3  602.53  5077.4  605.42
  5171.6  612.25  5188.3  613.97  5193.9  614.05  5274.6  620.22  5285.7  620.79
  5352.7  626.18  5362.7  626.55  5378.1  627.89  5423.1  630.01  5429.5  630.67
#Mann=8,-1,0
  4541.2    0.16       0  4877.2   0.035       0  4977.3    0.07       0
  5018.3    0.07       0  5022.3    0.07       0  5077.4    0.16       0
  5193.9    0.07       0  5274.6    0.16       0
Bank Sta=5018.3,5022.3
Exp/Cntr=0.3,0.1

Type RM Length L Ch R = 1,18097,432,432,432
BEGIN DESCRIPTION:
KRAMS TRIBUTARY 1 37.0
END DESCRIPTION:
XS GIS Cut Line= 3
      2313975.01     13717524.99      2314375.00     13717225.00
      2314725.01     13717125.00
#Sta/Elev= 30
  4504.3  632.93  4532.4  631.35  4561.6  628.42  4582.4  627.38  4611.6  624.58
  4640.7  622.72  4697.0  617.52  4711.6  615.65  4740.7  613.08  4747.0  613.02
  4761.6  611.14  4777.7  610.28  4826.2  606.73  4847.0  606.01  4854.3  604.72
  4882.4  604.42  4903.5  603.36  4938.7  601.96  4939.0  601.46  4942.5  601.46
  4942.7  601.96  4990.7  602.71  5001.2  602.02  5026.4  602.13  5064.1  604.96
  5172.0  613.30  5222.7  617.64  5239.6  619.64  5244.8  619.58  5368.3  628.91
#Mann=6,-1,0
  4504.3    0.16       0  4777.7   0.035       0  4903.5    0.07       0
  4938.7    0.07       0  4942.7    0.07       0  5064.1    0.16       0
Bank Sta=4938.7,4942.7
Exp/Cntr=0.3,0.1

Type RM Length L Ch R = 1,17665,452,452,452
BEGIN DESCRIPTION:
KRAMS TRIBUTARY 1 36.0
END DESCRIPTION:
XS GIS Cut Line= 3
      2314275.02     13717674.99      2314425.00     13717625.00
      2314574.99     13717575.00
#Sta/Elev= 28
  4849.7  609.91  4852.3  609.91  4858.1  608.84  4860.2  608.45  4870.8  607.72
  4881.3  608.40  4891.8  608.15  4902.4  606.49  4912.9  604.40  4923.5  602.17
  4934.0  599.69  4955.1  596.50  4974.1  591.74  4974.4  591.24  4977.9  591.24
  4978.2  591.74  5050.0  591.76  5060.5  593.16  5071.0  595.87  5081.6  599.50
  5092.1  602.95  5102.7  604.68  5113.2  606.24  5123.7  607.41  5134.3  608.70
  5155.4  610.07  5163.3  609.81  5165.9  609.81
#Mann=4,-1,0
  4849.7   0.035       0  4858.1    0.07       0  4974.1    0.07       0
  4978.2    0.07       0
Bank Sta=4974.1,4978.2
Exp/Cntr=0.3,0.1

Type RM Length L Ch R = 1,17213,446,446,446
BEGIN DESCRIPTION:
KRAMS TRIBUTARY 1 35.0
END DESCRIPTION:
XS GIS Cut Line= 3
      2314125.01     13717825.01      2314475.00     13718025.00
      2314874.99     13718125.00
#Sta/Elev= 30
  4596.9  624.30  4648.0  620.35  4659.3  618.72  4685.4  616.51  4700.5  614.35
  4707.0  612.74  4722.9  611.38  4728.6  611.55  4735.1  610.05  4770.8  608.86
  4787.6  605.35  4896.3  598.44  4927.3  597.04  4954.6  598.93  4960.0  598.59
  4964.7  598.29  4977.0  594.78  4989.8  592.53  4990.2  592.03  4994.3  592.53
  5023.2  592.65  5041.2  596.94  5064.4  595.78  5152.7  598.83  5190.2  601.18
  5225.0  603.72  5306.7  610.13  5311.8  609.82  5347.9  612.65  5412.3  615.93
#Mann=9,-1,0
  4596.9    0.16       0  4659.3   0.035       0  4770.8    0.07       0
  4960.0    0.16       0  4989.8    0.07       0  4994.3    0.16       0
  5152.7    0.07       0  5190.2    0.16       0  5225.0    0.07       0
Bank Sta=4989.8,4994.3
Exp/Cntr=0.3,0.1

Type RM Length L Ch R = 1,16767,213,213,213
BEGIN DESCRIPTION:
KRAMS TRIBUTARY 1 34.0
END DESCRIPTION:
XS GIS Cut Line= 3
      2313825.04     13718275.01      2314625.00     13718425.00
      2314924.99     13718175.01
#Sta/Elev= 30
  4191.2  635.63  4231.7  633.83  4275.1  630.84  4380.2  620.35  4507.5  610.38
  4600.7  605.20  4618.5  603.53  4636.7  604.13  4659.2  602.76  4699.9  601.82
  4816.0  600.51  4862.7  597.30  4868.6  596.32  4903.4  594.52  4971.5  592.97
  4971.8  592.47  4976.0  592.97  5076.0  595.94  5139.8  600.27  5168.5  603.42
  5203.6  605.32  5282.5  612.16  5296.7  613.15  5324.7  614.99  5331.2  613.34
  5345.5  613.59  5353.3  614.33  5359.8  616.26  5367.6  617.13  5395.6  618.31
#Mann=8,-1,0
  4191.2   0.035       0  4231.7    0.07       0  4507.5   0.035       0
  4636.7    0.07       0  4971.5    0.07       0  4976.0    0.07       0
  5282.5    0.16       0  5296.7    0.07       0
Bank Sta=4971.5,4976
Exp/Cntr=0.3,0.1

Type RM Length L Ch R = 1,16554,238,238,238
BEGIN DESCRIPTION:
A19606
END DESCRIPTION:
XS GIS Cut Line= 3
      2313841.31     13718616.27      2314531.38     13718655.33
      2315247.56     13718481.71
#Sta/Elev= 30
  4167.8  618.50  4311.7  610.90  4351.8  609.67  4361.8  610.62  4371.8  608.31
  4381.8  604.30  4391.9  602.38  4449.3  602.41  4502.0  602.36  4512.0  604.84
  4522.1  609.20  4532.1  607.69  4542.1  603.35  4552.1  600.76  4581.7  601.61
  4642.3  599.48  4761.0  600.09  4812.5  599.46  4994.2  591.10  4994.5  590.60
  4998.7  591.10  5094.0  595.13  5177.6  600.69  5294.9  605.64  5315.4  607.95
  5353.3  609.28  5428.4  613.23  5433.6  614.30  5480.5  616.16  5595.9  618.72
#Mann=6,-1,0
  4167.8    0.07       0  4449.3   0.035       0  4581.7    0.07       0
  4994.2    0.07       0  4998.7    0.07       0  5353.3    0.16       0
Bank Sta=4994.2,4998.7
Exp/Cntr=0.3,0.1

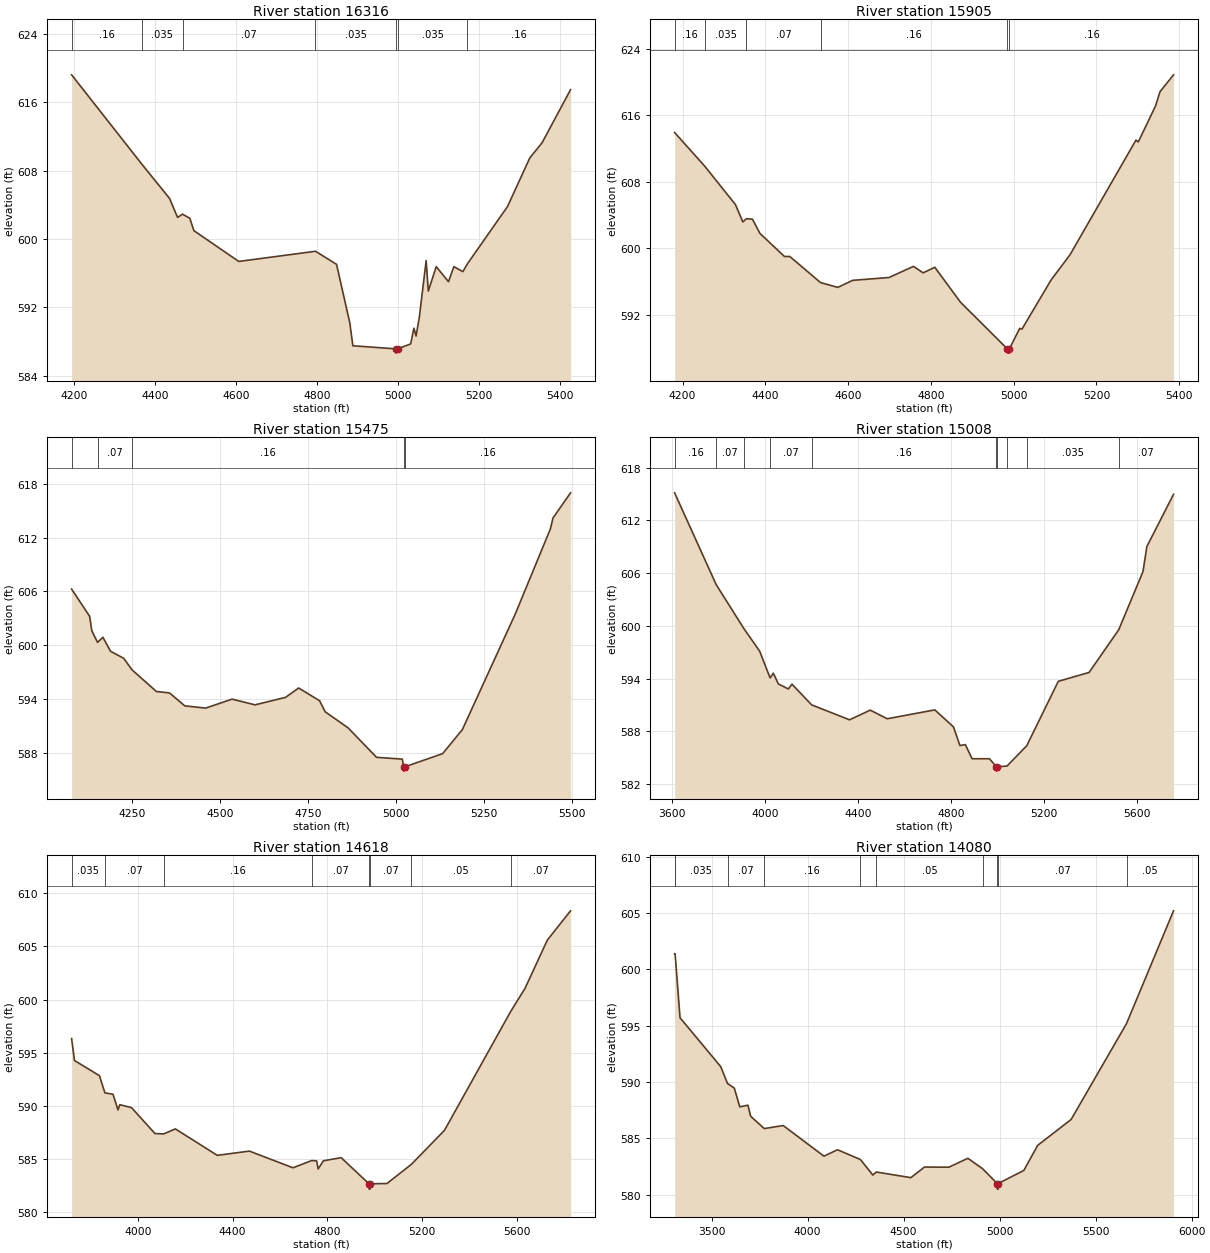
Type RM Length L Ch R = 1,16316,411,411,411
BEGIN DESCRIPTION:
KRAMS TRIBUTARY 1 33.0
END DESCRIPTION:
XS GIS Cut Line= 3
      2313975.03     13718925.00      2314775.00     13718825.00
      2315175.00     13718975.00
#Sta/Elev= 30
  4193.8  619.19  4368.5  608.68  4435.6  604.76  4455.8  602.52  4468.0  602.90
  4486.0  602.42  4496.1  600.97  4607.0  597.37  4796.7  598.56  4848.8  597.03
  4881.6  590.17  4889.1  587.51  4995.2  587.15  4995.5  586.65  4999.8  587.15
  5032.0  587.73  5040.0  589.57  5045.4  588.65  5053.4  590.85  5070.3  597.47
  5075.6  593.91  5095.2  596.76  5125.5  595.00  5138.8  596.76  5161.1  596.18
  5172.4  597.10  5271.4  603.79  5326.6  609.48  5356.9  611.25  5427.2  617.45
#Mann=7,-1,0
  4193.8    0.16       0  4368.5   0.035       0  4468.0    0.07       0
  4796.7   0.035       0  4995.2   0.035       0  4999.8   0.035       0
  5172.4    0.16       0
Bank Sta=4995.2,4999.8
Exp/Cntr=0.3,0.1

Type RM Length L Ch R = 1,15905,430,430,430
BEGIN DESCRIPTION:
KRAMS TRIBUTARY 1 32.0
END DESCRIPTION:
XS GIS Cut Line= 3
      2314075.03     13718975.01      2314875.00     13719175.00
      2315225.02     13719024.99
#Sta/Elev= 30
  4180.9  613.95  4253.8  609.89  4327.8  605.28  4345.8  603.19  4354.5  603.58
  4369.0  603.52  4387.0  601.81  4446.3  599.03  4459.2  599.03  4533.4  595.89
  4575.1  595.31  4611.2  596.16  4698.8  596.50  4758.1  597.84  4781.3  597.06
  4809.6  597.73  4871.5  593.53  4985.1  587.90  4985.5  587.40  4989.4  587.40
  4989.7  587.90  5014.6  590.38  5020.0  590.28  5090.7  596.22  5136.0  599.22
  5295.6  613.04  5301.1  612.81  5342.8  617.14  5353.6  618.86  5386.3  620.89
#Mann=6,-1,0
  4180.9    0.16       0  4253.8   0.035       0  4354.5    0.07       0
  4533.4    0.16       0  4985.1    0.07       0  4989.7    0.16       0
Bank Sta=4985.1,4989.7
Exp/Cntr=0.3,0.1

Type RM Length L Ch R = 1,15475,467,467,467
BEGIN DESCRIPTION:
KRAMS TRIBUTARY 1 31.0
END DESCRIPTION:
XS GIS Cut Line= 3
      2314174.98     13719124.99      2314975.00     13719575.00
      2315275.00     13719175.00
#Sta/Elev= 30
  4077.2  606.26  4128.5  603.21  4134.6  601.61  4150.9  600.31  4166.1  600.88
  4187.8  599.32  4225.4  598.53  4248.6  597.26  4318.2  594.83  4355.5  594.67
  4398.8  593.23  4458.1  592.98  4533.3  593.98  4598.3  593.34  4685.3  594.18
  4722.6  595.22  4781.9  593.80  4797.8  592.57  4862.8  590.78  4943.8  587.49
  5017.0  587.29  5020.9  586.45  5021.3  585.95  5025.5  586.45  5131.6  587.90
  5187.8  590.59  5337.8  603.45  5437.8  612.96  5445.1  614.17  5495.1  616.99
#Mann=5,-1,0
  4077.2   0.035       0  4150.9    0.07       0  4248.6    0.16       0
  5020.9    0.07       0  5025.5    0.16       0
Bank Sta=5020.9,5025.5
Exp/Cntr=0.3,0.1

Type RM Length L Ch R = 1,15008,390,390,390
BEGIN DESCRIPTION:
KRAMS TRIBUTARY 1 30.0
END DESCRIPTION:
XS GIS Cut Line= 3
      2313875.00     13719275.00      2315075.00     13719975.00
      2315825.02     13720075.00
#Sta/Elev= 30
  3611.2  615.13  3789.9  604.69  3909.9  599.65  3977.1  597.11  4021.9  594.07
  4035.8  594.61  4057.3  593.39  4100.3  592.81  4116.0  593.36  4200.5  591.00
  4363.7  589.30  4452.6  590.40  4525.8  589.42  4730.4  590.43  4810.7  588.49
  4838.4  586.37  4861.5  586.48  4890.9  584.87  4965.3  584.87  4995.1  583.96
  4995.5  583.46  4999.9  583.96  5041.0  584.04  5125.8  586.35  5261.5  593.68
  5393.9  594.69  5521.5  599.55  5625.9  606.18  5642.3  609.01  5757.1  614.96
#Mann=10,-1,0
  3611.2    0.16       0  3789.9    0.07       0  3909.9   0.035       0
  4021.9    0.07       0  4200.5    0.16       0  4995.1    0.07       0
  4999.9    0.16       0  5041.0    0.07       0  5125.8   0.035       0
  5521.5    0.07       0
Bank Sta=4995.1,4999.9
Exp/Cntr=0.3,0.1

Type RM Length L Ch R = 1,14618,538,538,538
BEGIN DESCRIPTION:
A19605
END DESCRIPTION:
XS GIS Cut Line= 4
      2314114.73     13719618.89      2314943.70     13720304.64
      2315412.45     13720395.78      2315950.36     13720265.64
#Sta/Elev= 30
  3720.2  596.32  3732.3  594.26  3837.8  592.83  3860.8  591.21  3895.1  591.08
  3916.0  589.61  3923.8  590.10  3973.3  589.82  4072.3  587.38  4109.2  587.35
  4158.3  587.82  4335.4  585.33  4470.9  585.73  4655.0  584.16  4733.9  584.84
  4754.8  584.81  4761.3  584.05  4783.5  584.82  4858.5  585.11  4976.1  582.65
  4976.4  582.15  4980.5  582.15  4980.9  582.65  5052.0  582.68  5155.3  584.49
  5294.9  587.69  5573.9  598.86  5634.8  601.05  5728.9  605.59  5827.0  608.35
#Mann=8,-1,0
  3720.2   0.035       0  3860.8    0.07       0  4109.2    0.16       0
  4733.9    0.07       0  4976.1    0.07       0  4980.9    0.07       0
  5155.3    0.05       0  5573.9    0.07       0
Bank Sta=4976.1,4980.9
Exp/Cntr=0.3,0.1

Type RM Length L Ch R = 1,14080,477,477,477
BEGIN DESCRIPTION:
KRAMS TRIBUTARY 1 29.0
END DESCRIPTION:
XS GIS Cut Line= 3
      2314024.98     13719624.98      2315225.00     13720825.00
      2315975.02     13720324.99
#Sta/Elev= 30
  3307.1  601.40  3309.7  601.40  3335.4  595.71  3547.5  591.36  3582.6  589.87
  3618.3  589.45  3646.5  587.79  3689.0  587.94  3703.1  586.96  3773.7  585.86
  3872.8  586.13  4084.9  583.41  4155.7  583.98  4275.0  583.11  4339.5  581.73
  4357.5  582.00  4537.5  581.50  4608.2  582.44  4735.5  582.43  4834.5  583.22
  4910.7  582.30  4987.6  580.98  4987.9  580.48  4992.1  580.48  4992.5  580.98
  5125.9  582.14  5198.0  584.37  5372.3  586.67  5660.8  595.19  5905.6  605.21
#Mann=10,-1,0
  3307.1    0.05       0  3309.7   0.035       0  3582.6    0.07       0
  3773.7    0.16       0  4275.0    0.07       0  4357.5    0.05       0
  4910.7    0.07       0  4987.6    0.07       0  4992.5    0.07       0
  5660.8    0.05       0
Bank Sta=4987.6,4992.5
Exp/Cntr=0.3,0.1

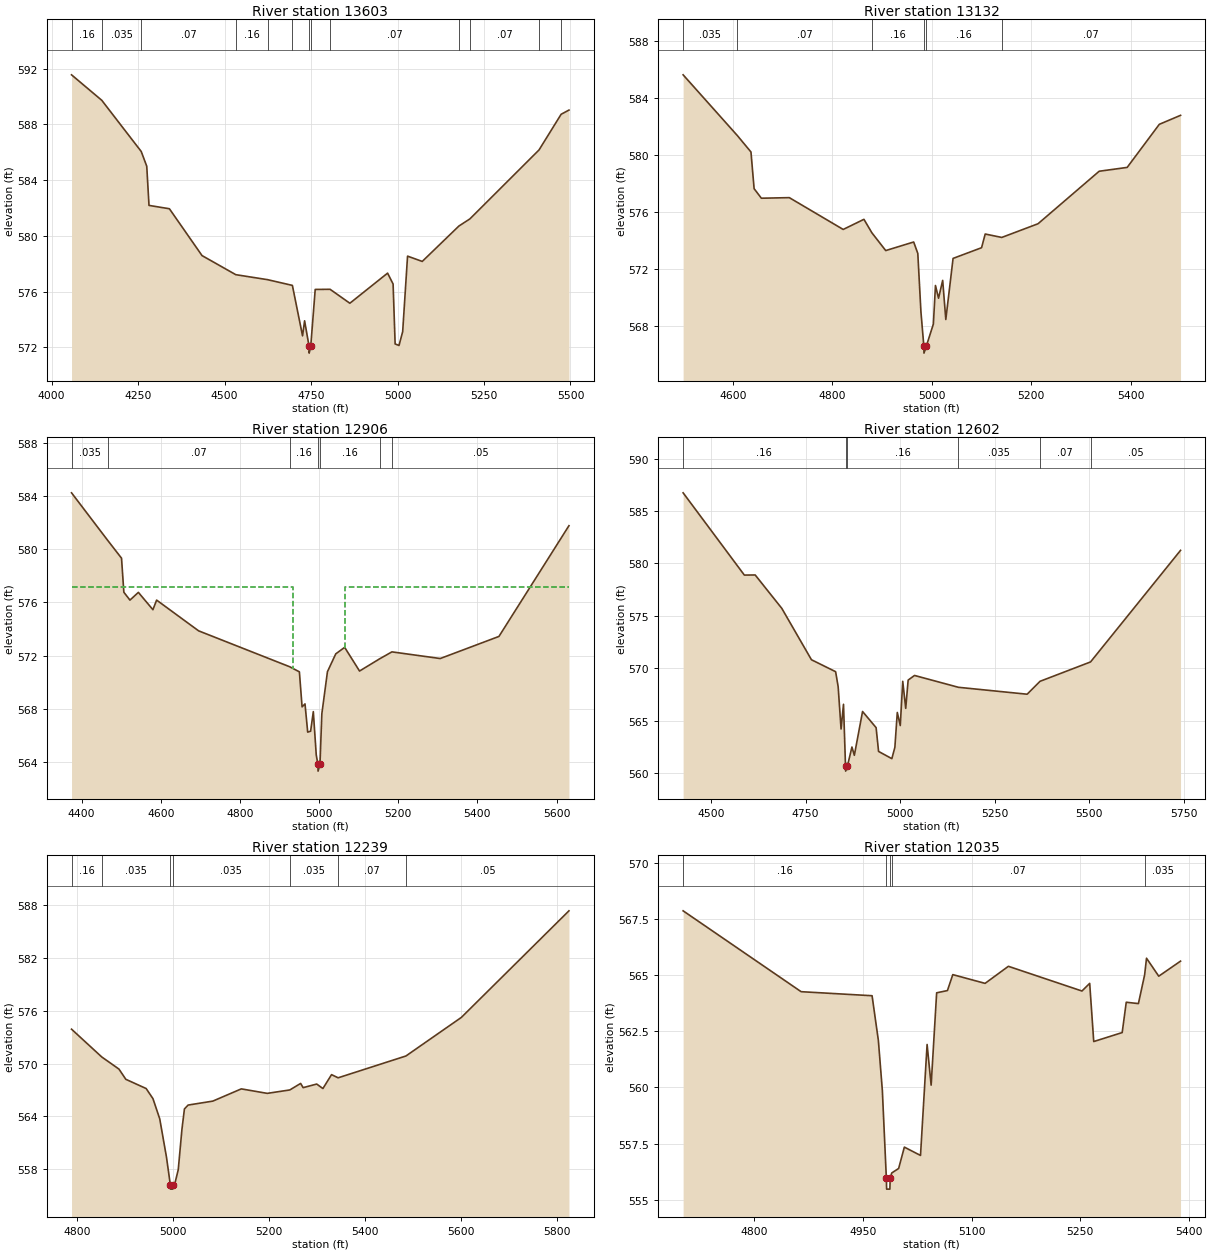
Type RM Length L Ch R = 1,13603,471,471,471
BEGIN DESCRIPTION:
KRAMS TRIBUTARY 1 28.0
END DESCRIPTION:
XS GIS Cut Line= 3
      2314025.04     13720525.02      2314825.00     13721025.00
      2315174.98     13721374.98
#Sta/Elev= 30
  4057.4  591.55  4144.9  589.72  4258.9  586.05  4274.9  584.99  4281.4  582.18
  4340.4  581.94  4434.7  578.58  4532.3  577.21  4624.5  576.85  4696.0  576.44
  4725.4  572.82  4731.3  573.90  4744.2  572.08  4744.5  571.58  4749.1  572.08
  4762.0  576.15  4805.0  576.16  4862.2  575.16  4971.3  577.32  4987.2  576.54
  4993.1  572.24  5004.3  572.13  5014.9  573.12  5029.0  578.54  5071.5  578.16
  5177.5  580.70  5209.2  581.21  5409.2  586.16  5473.1  588.72  5495.7  589.02
#Mann=13,-1,0
  4057.4    0.16       0  4144.9   0.035       0  4258.9    0.07       0
  4532.3    0.16       0  4624.5    0.07       0  4696.0    0.16       0
  4744.2    0.07       0  4749.1    0.16       0  4805.0    0.07       0
  5177.5    0.16       0  5209.2    0.07       0  5409.2    0.05       0
  5473.1    0.07       0
Bank Sta=4744.2,4749.1
Exp/Cntr=0.3,0.1

Type RM Length L Ch R = 1,13132,226,226,226
BEGIN DESCRIPTION:
KRAMS TRIBUTARY 1 27.0
END DESCRIPTION:
XS GIS Cut Line= 3
      2314125.02     13720725.03      2314425.00     13721125.00
      2314825.03     13721425.02
#Sta/Elev= 30
  4500.3  585.61  4609.6  581.34  4636.7  580.20  4643.0  577.63  4657.6  576.96
  4713.8  577.00  4822.1  574.77  4863.8  575.48  4879.7  574.54  4907.6  573.29
  4963.8  573.89  4972.1  573.09  4978.4  568.99  4984.2  566.60  4984.5  566.10
  4989.3  566.60  5003.4  568.14  5007.6  570.84  5013.8  569.95  5022.1  571.20
  5028.4  568.46  5043.0  572.74  5100.3  573.49  5107.6  574.45  5140.9  574.21
  5213.8  575.17  5336.7  578.85  5393.0  579.12  5457.6  582.14  5500.3  582.77
#Mann=6,-1,0
  4500.3   0.035       0  4609.6    0.07       0  4879.7    0.16       0
  4984.2    0.07       0  4989.3    0.16       0  5140.9    0.07       0
Bank Sta=4984.2,4989.3
Exp/Cntr=0.3,0.1

Type RM Length L Ch R = 1,12906,304,304,304
BEGIN DESCRIPTION:
A19604
END DESCRIPTION:
XS GIS Cut Line= 6
      2314141.66     13720755.83      2314254.39     13720938.85
      2314250.85     13721227.89      2314367.69     13721355.20
      2314430.01     13721658.33      2314650.32     13721815.31
#Sta/Elev= 30
  4374.6  584.24  4466.7  580.64  4500.9  579.33  4506.8  576.77  4522.2  576.18
  4543.5  576.76  4580.2  575.46  4589.6  576.18  4695.7  573.87  4926.0  571.17
  4950.3  570.79  4957.1  568.16  4964.5  568.38  4971.3  566.26  4978.7  566.33
  4985.5  567.80  4992.9  564.55  4997.1  563.83  4997.5  563.33  5002.3  563.83
  5007.0  567.63  5021.2  570.80  5042.2  572.14  5064.7  572.63  5102.3  570.85
  5153.2  571.77  5184.1  572.29  5306.2  571.79  5454.5  573.45  5631.4  581.77
#Mann=7,-1,0
  4374.6   0.035       0  4466.7    0.07       0  4926.0    0.16       0
  4997.1    0.07       0  5002.3    0.16       0  5153.2    0.07       0
  5184.1    0.05       0
#XS Ineff=2,0
    0.00 4934.70  577.15 5065.30    0.00  577.15
Permanent Ineff=
       F       F
Bank Sta=4997.1,5002.3
Exp/Cntr=0.3,0.1

Type RM Length L Ch R = 1,12602,363,363,363
BEGIN DESCRIPTION:
KRAMS TRIBUTARY 1 26.0
END DESCRIPTION:
XS GIS Cut Line= 4
      2313687.25     13721155.61      2314154.89     13721536.41
      2314176.99     13721791.46      2314625.00     13721875.00
#Sta/Elev= 30
  4426.4  586.74  4588.2  578.89  4616.9  578.90  4687.3  575.71  4765.6  570.81
  4829.5  569.67  4836.2  568.23  4843.9  564.20  4850.3  566.56  4855.6  560.68
  4856.0  560.18  4860.8  560.68  4872.6  562.48  4879.0  561.69  4900.7  565.87
  4936.5  564.33  4943.0  562.06  4978.1  561.37  4986.1  562.45  4992.5  565.78
  5000.4  564.53  5006.9  568.75  5014.8  566.17  5021.2  568.87  5038.1  569.31
  5154.1  568.18  5335.7  567.52  5369.7  568.75  5503.3  570.60  5741.2  581.25
#Mann=6,-1,0
  4426.4    0.16       0  4855.6    0.07       0  4860.8    0.16       0
  5154.1   0.035       0  5369.7    0.07       0  5503.3    0.05       0
Bank Sta=4855.6,4860.8
Exp/Cntr=0.3,0.1

Type RM Length L Ch R = 1,12239,204,204,204
BEGIN DESCRIPTION:
KRAMS TRIBUTARY 1 25.0
END DESCRIPTION:
XS GIS Cut Line= 3
      2313775.03     13721625.03      2313925.00     13721775.00
      2314724.99     13721975.00
#Sta/Elev= 30
  4787.9  573.91  4850.9  570.75  4886.8  569.37  4901.0  568.21  4943.4  567.16
  4957.6  566.01  4971.7  563.72  4985.8  559.35  4993.8  556.22  4994.2  555.72
  4998.7  555.72  4999.1  556.22  5002.6  556.22  5010.3  557.92  5018.0  562.52
  5023.2  564.84  5030.9  565.28  5082.4  565.73  5141.7  567.12  5195.8  566.61
  5242.8  567.00  5265.4  567.74  5270.6  567.26  5298.9  567.67  5311.8  567.16
  5329.8  568.74  5343.5  568.38  5484.8  570.86  5600.4  575.25  5824.6  587.37
#Mann=7,-1,0
  4787.9    0.16       0  4850.9   0.035       0  4993.8    0.07       0
  4999.1   0.035       0  5242.8   0.035       0  5343.5    0.07       0
  5484.8    0.05       0
Bank Sta=4993.8,4999.1
Exp/Cntr=0.3,0.1

Type RM Length L Ch R = 1,12035,194,194,194
BEGIN DESCRIPTION:
A19603
END DESCRIPTION:
XS GIS Cut Line= 2
      2313580.88     13721819.41      2314197.17     13722123.21
#Sta/Elev= 30
  4701.6  567.86  4864.6  564.26  4962.6  564.08  4971.3  562.09  4976.8  559.86
  4982.3  555.97  4982.7  555.47  4987.2  555.47  4987.6  555.97  4989.8  556.19
  4999.3  556.39  5007.2  557.34  5029.5  556.97  5038.6  561.91  5044.2  560.10
  5051.8  564.21  5066.7  564.31  5074.1  565.02  5118.7  564.63  5150.9  565.39
  5252.5  564.29  5263.2  564.63  5268.8  562.04  5308.1  562.44  5313.7  563.79
  5330.5  563.73  5339.1  565.01  5341.7  565.75  5358.6  564.95  5388.7  565.62
#Mann=5,-1,0
  4701.6    0.16       0  4982.3    0.07       0  4987.6    0.16       0
  4989.8    0.07       0  5339.1   0.035       0
Bank Sta=4982.3,4987.6
Exp/Cntr=0.3,0.1

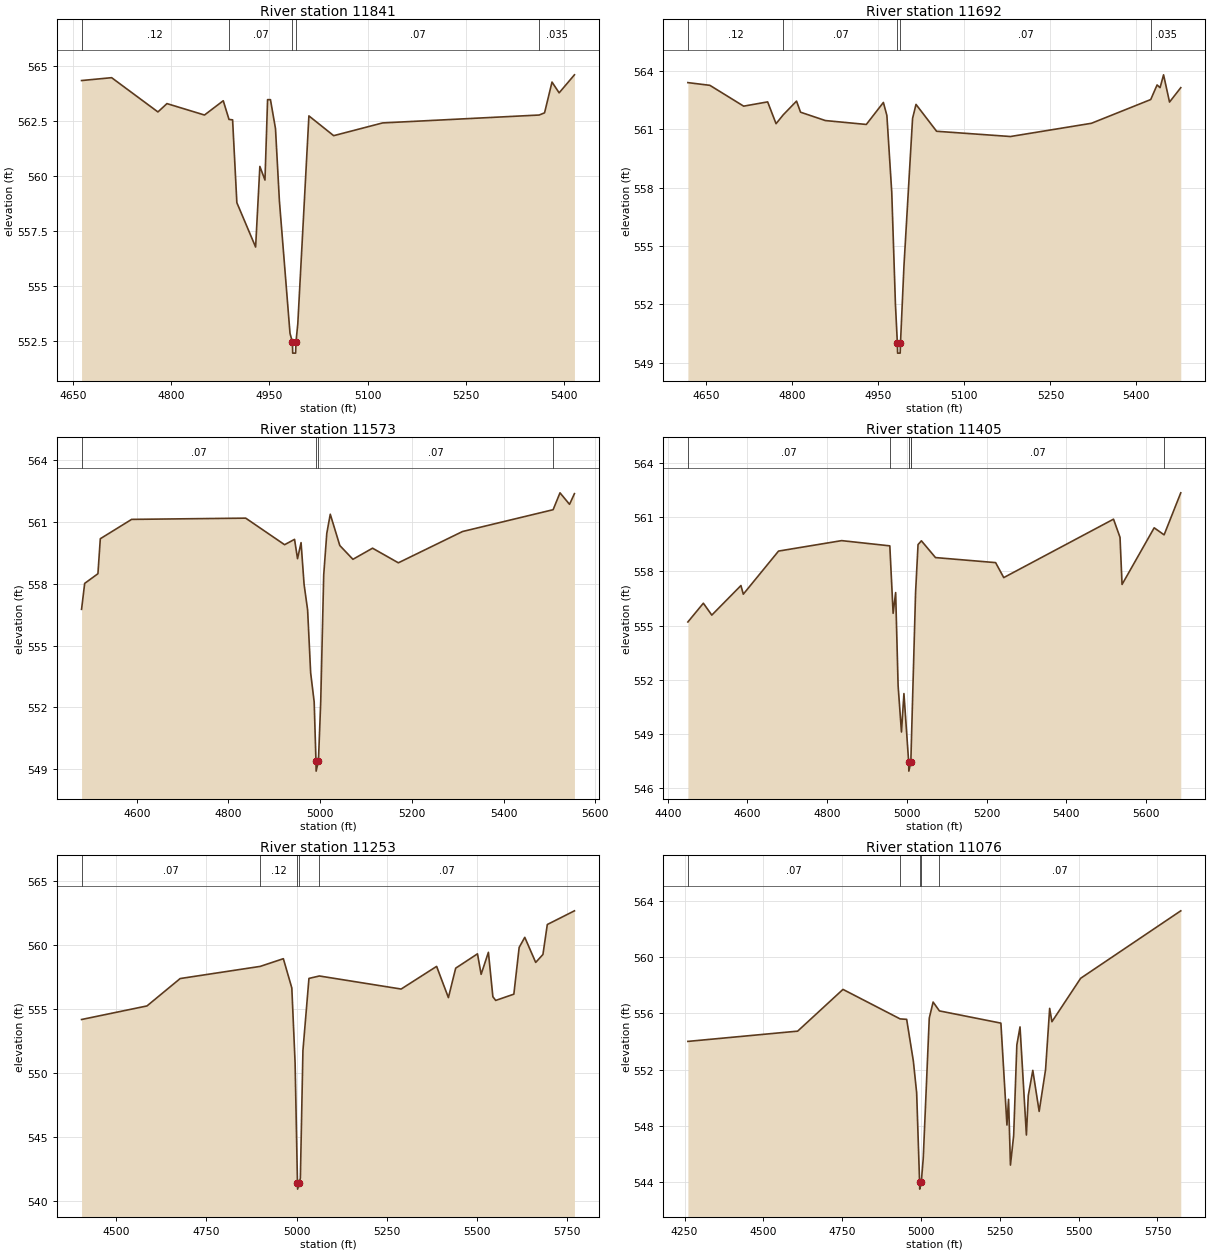
Type RM Length L Ch R = 1,11841,149,149,149
BEGIN DESCRIPTION:
A19602
END DESCRIPTION:
XS GIS Cut Line= 4
      2313554.82     13721910.54      2313776.17     13722092.83
      2314110.50     13722255.82      2314196.10     13722297.26
#Sta/Elev= 30
  4662.6  564.36  4708.6  564.49  4779.4  562.93  4793.2  563.31  4850.6  562.79
  4879.3  563.44  4888.1  562.59  4893.6  562.57  4900.1  558.80  4928.8  556.78
  4935.3  560.45  4943.1  559.83  4947.1  563.49  4951.5  563.49  4959.2  562.17
  4965.2  558.87  4981.4  552.85  4985.1  552.45  4985.5  551.95  4990.0  551.95
  4990.5  552.45  4993.3  553.28  5010.3  562.75  5048.2  561.85  5123.0  562.43
  5362.5  562.79  5370.7  562.89  5382.1  564.29  5393.0  563.80  5416.4  564.62
#Mann=5,-1,0
  4662.6    0.12       0  4888.1    0.07       0  4985.1    0.05       0
  4990.5    0.07       0  5362.5   0.035       0
Bank Sta=4985.1,4990.5
Exp/Cntr=0.3,0.1

Type RM Length L Ch R = 1,11692,119,119,119
BEGIN DESCRIPTION:
A19601
END DESCRIPTION:
XS GIS Cut Line= 4
      2313520.12     13721945.30      2313685.02     13722175.30
      2313969.55     13722369.10      2314193.96     13722429.65
#Sta/Elev= 30
  4617.7  563.39  4656.1  563.25  4715.0  562.18  4756.8  562.40  4771.5  561.28
  4784.2  561.74  4807.2  562.44  4814.2  561.87  4857.5  561.44  4928.9  561.24
  4958.7  562.37  4964.8  561.70  4973.3  557.75  4979.7  552.01  4983.1  549.99
  4983.5  549.49  4988.0  549.49  4988.5  549.99  4994.6  553.98  5009.6  561.55
  5015.6  562.27  5051.5  560.89  5180.3  560.62  5321.6  561.30  5425.0  562.52
  5436.1  563.27  5441.3  563.13  5447.4  563.79  5457.8  562.39  5477.4  563.13
#Mann=5,-1,0
  4617.7    0.12       0  4784.2    0.07       0  4983.1    0.05       0
  4988.5    0.07       0  5425.0   0.035       0
Bank Sta=4983.1,4988.5
Exp/Cntr=0.3,0.1

Type RM Length L Ch R = 1,11573,168,168,168
BEGIN DESCRIPTION:
A19600
END DESCRIPTION:
XS GIS Cut Line= 4
      2313239.10     13722069.40      2313472.88     13722134.78
      2313804.26     13722417.66      2314185.25     13722527.29
#Sta/Elev= 30
  4479.6  556.76  4486.4  558.02  4515.3  558.49  4520.5  560.19  4588.8  561.13
  4837.6  561.19  4922.4  559.90  4944.1  560.16  4950.6  559.22  4958.3  560.00
  4964.9  557.97  4972.6  556.73  4979.2  553.68  4986.9  552.26  4990.8  549.40
  4991.2  548.90  4996.2  549.40  5001.2  552.28  5007.7  558.43  5014.4  560.45
  5022.0  561.38  5042.8  559.86  5071.4  559.19  5114.2  559.73  5170.5  559.02
  5310.4  560.54  5508.0  561.60  5523.0  562.42  5543.8  561.86  5554.5  562.38
#Mann=4,-1,0
  4479.6    0.07       0  4990.8    0.05       0  4996.2    0.07       0
  5508.0   0.035       0
Bank Sta=4990.8,4996.2
Exp/Cntr=0.3,0.1

Type RM Length L Ch R = 1,11405,152,152,152
BEGIN DESCRIPTION:
A19599
END DESCRIPTION:
XS GIS Cut Line= 4
      2313078.47     13722058.54      2313338.01     13722221.03
      2313647.04     13722452.80      2314180.43     13722559.75
#Sta/Elev= 30
  4450.6  555.20  4489.4  556.24  4510.6  555.58  4583.7  557.22  4589.6  556.74
  4678.0  559.13  4836.4  559.71  4957.2  559.42  4958.3  558.92  4965.5  555.68
  4971.8  556.83  4978.0  551.66  4986.4  549.10  4992.6  551.23  5004.5  547.43
  5004.9  546.93  5009.9  547.43  5011.2  548.48  5021.8  556.83  5028.0  559.49
  5036.4  559.70  5071.8  558.77  5222.6  558.49  5243.0  557.66  5518.4  560.90
  5534.7  559.89  5539.8  557.28  5620.4  560.42  5645.3  560.03  5687.1  562.36
#Mann=6,-1,0
  4450.6    0.07       0  4958.3    0.12       0  5004.5    0.05       0
  5009.9    0.12       0  5011.2    0.07       0  5645.3   0.035       0
Bank Sta=5004.5,5009.9
Exp/Cntr=0.3,0.1

Type RM Length L Ch R = 1,11253,177,177,177
BEGIN DESCRIPTION:
A19598
END DESCRIPTION:
XS GIS Cut Line= 4
      2313022.06     13722065.08      2313271.52     13722410.32
      2313578.78     13722539.69      2314181.58     13722620.41
#Sta/Elev= 30
  4403.6  554.15  4585.1  555.21  4677.2  557.35  4899.4  558.30  4963.5  558.90
  4987.0  556.61  4996.1  550.73  5002.6  541.40  5003.0  540.90  5008.0  541.40
  5010.7  541.77  5017.8  551.72  5034.5  557.36  5063.4  557.55  5290.3  556.53
  5388.7  558.30  5421.4  555.86  5441.6  558.16  5502.1  559.28  5512.2  557.68
  5532.4  559.40  5544.8  555.93  5552.6  555.64  5603.0  556.13  5617.7  559.78
  5633.3  560.57  5663.6  558.61  5683.7  559.23  5695.8  561.57  5771.1  562.64
#Mann=5,-1,0
  4403.6    0.07       0  4899.4    0.12       0  5002.6    0.05       0
  5008.0    0.12       0  5063.4    0.07       0
Bank Sta=5002.6,5008
Exp/Cntr=0.3,0.1

Type RM Length L Ch R = 1,11076,217,217,217
BEGIN DESCRIPTION:
A19597
END DESCRIPTION:
XS GIS Cut Line= 4
      2312989.49     13722058.52      2313199.92     13722581.81
      2313484.36     13722665.94      2314178.76     13722774.69
#Sta/Elev= 30
  4260.5  554.00  4608.7  554.73  4752.5  557.70  4933.8  555.60  4954.5  555.57
  4975.8  552.59  4986.2  550.34  4995.5  543.99  4995.9  543.49  5000.9  543.99
  5007.1  545.68  5026.2  555.66  5038.4  556.80  5058.4  556.17  5253.4  555.30
  5272.6  548.05  5277.7  549.88  5283.7  545.20  5293.9  547.30  5304.0  553.75
  5314.1  555.03  5334.3  547.34  5340.3  550.15  5354.6  551.94  5374.8  549.02
  5395.1  551.99  5408.1  556.35  5415.3  555.40  5506.4  558.49  5824.0  563.29
#Mann=5,-1,0
  4260.5    0.07       0  4933.8    0.12       0  4995.5    0.05       0
  5000.9    0.12       0  5058.4    0.07       0
Bank Sta=4995.5,5000.9
Exp/Cntr=0.3,0.1

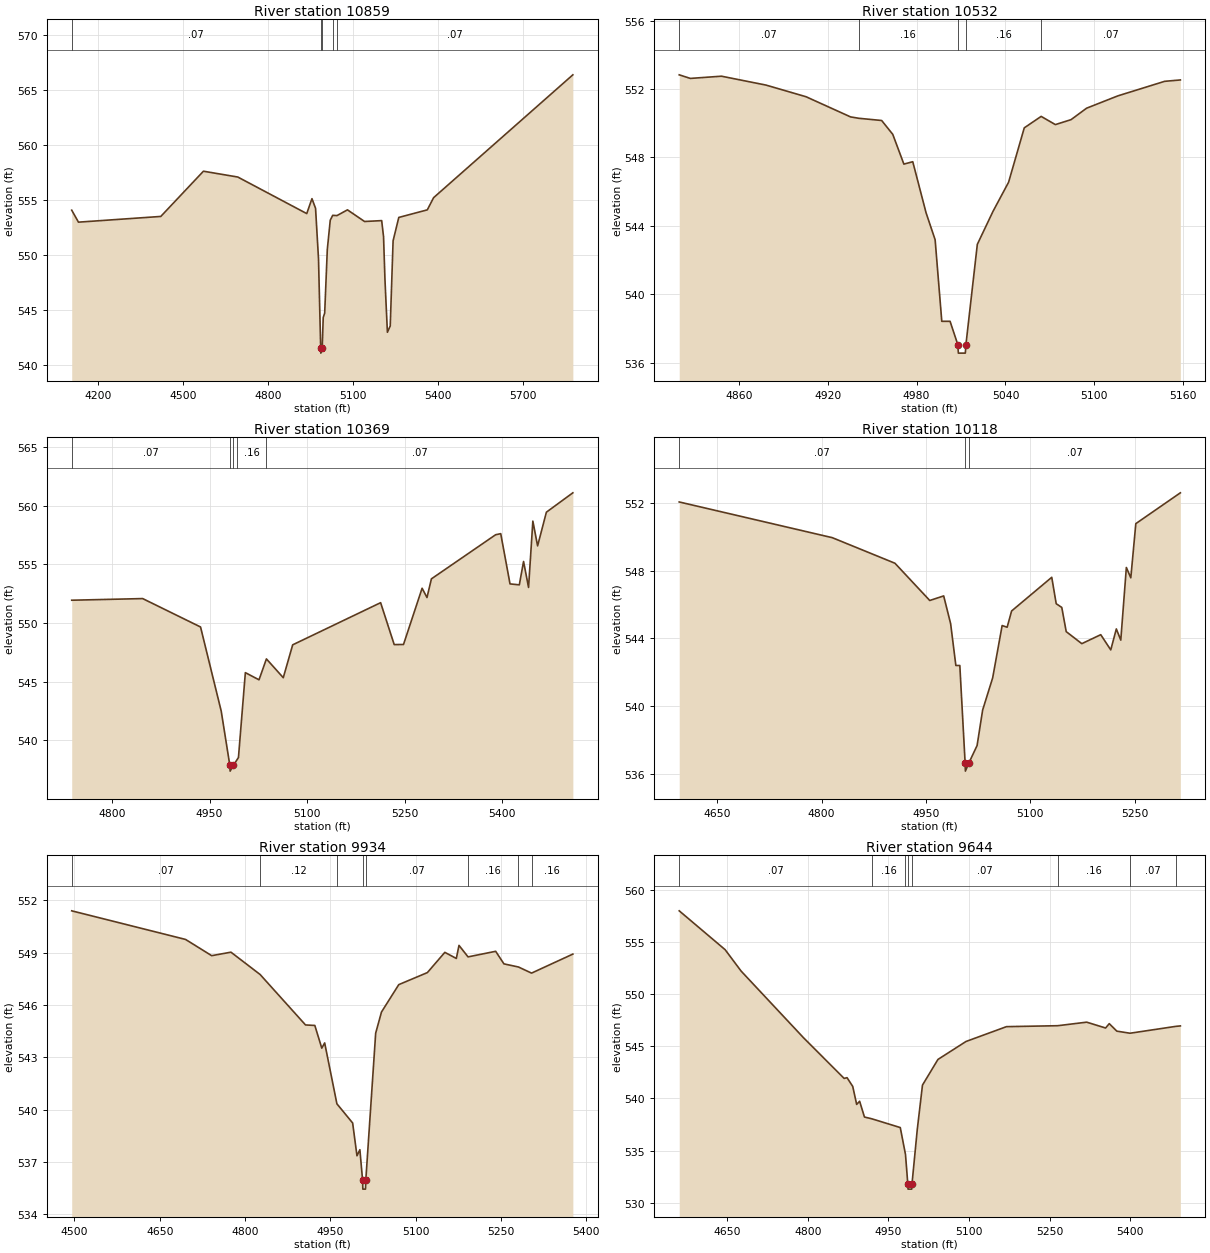
Type RM Length L Ch R = 1,10859,327,327,327
BEGIN DESCRIPTION:
A19596
END DESCRIPTION:
XS GIS Cut Line= 4
      2312972.14     13722071.58      2313179.58     13722793.84
      2313346.48     13722839.36      2314185.21     13722937.45
#Sta/Elev= 30
  4106.6  554.06  4130.4  552.97  4421.0  553.49  4571.5  557.61  4692.8  557.08
  4936.2  553.75  4954.6  555.11  4967.3  554.23  4977.7  549.64  4985.4  541.54
  4985.8  541.04  4990.8  541.54  4994.4  544.29  4999.5  544.68  5008.8  550.49
  5019.2  553.15  5027.8  553.59  5043.1  553.57  5079.9  554.09  5140.3  553.03
  5200.7  553.11  5207.3  551.64  5212.3  547.73  5220.9  542.94  5230.9  543.51
  5241.0  551.27  5261.1  553.40  5361.8  554.09  5384.0  555.20  5875.5  566.39
#Mann=5,-1,0
  4106.6    0.07       0  4985.4    0.05       0  4990.8    0.07       0
  5027.8    0.12       0  5043.1    0.07       0
Bank Sta=4985.4,4990.8
Exp/Cntr=0.3,0.1

Type RM Length L Ch R = 1,10532,163,163,163
BEGIN DESCRIPTION:
KRAMS TRIBUTARY 1 21.0
END DESCRIPTION:
XS GIS Cut Line= 3
      2313175.01     13722925.01      2313275.00     13723075.00
      2313425.02     13723125.01
#Sta/Elev= 30
  4819.7  552.83  4827.2  552.62  4848.2  552.75  4878.3  552.23  4905.3  551.55
  4935.4  550.37  4940.9  550.29  4956.4  550.16  4963.9  549.35  4971.4  547.61
  4977.4  547.75  4986.4  544.76  4992.5  543.19  4997.0  538.42  5002.6  538.42
  5007.8  537.06  5008.2  536.56  5012.9  536.56  5013.3  537.06  5021.0  542.92
  5031.6  544.85  5042.1  546.55  5052.7  549.73  5064.1  550.40  5073.7  549.92
  5084.3  550.21  5094.8  550.88  5115.9  551.60  5147.5  552.45  5158.1  552.53
#Mann=5,-1,0
  4819.7    0.07       0  4940.9    0.16       0  5007.8    0.07       0
  5013.3    0.16       0  5064.1    0.07       0
Bank Sta=5007.8,5013.3
Exp/Cntr=0.3,0.1

Type RM Length L Ch R = 1,10369,251,251,251
BEGIN DESCRIPTION:
A19595
END DESCRIPTION:
XS GIS Cut Line= 3
      2313078.26     13722941.39      2313182.42     13723258.20
      2313516.43     13723540.15
#Sta/Elev= 30
  4738.0  551.94  4847.1  552.08  4936.1  549.66  4967.9  542.49  4981.1  537.88
  4981.6  537.38  4986.7  537.88  4992.2  538.35  4994.4  538.54  5005.0  545.77
  5026.0  545.16  5037.4  546.94  5063.3  545.34  5077.8  548.14  5213.0  551.73
  5233.9  548.16  5248.2  548.17  5276.8  552.96  5284.3  552.17  5291.1  553.76
  5389.9  557.52  5397.7  557.61  5412.0  553.33  5426.3  553.25  5432.8  555.24
  5440.5  553.03  5447.1  558.68  5454.4  556.57  5467.9  559.44  5508.6  561.09
#Mann=5,-1,0
  4738.0    0.07       0  4981.1    0.07       0  4986.7    0.07       0
  4992.2    0.16       0  5037.4    0.07       0
Bank Sta=4981.1,4986.7
Exp/Cntr=0.3,0.1

Type RM Length L Ch R = 1,10118,184,184,184
BEGIN DESCRIPTION:
KRAMS TRIBUTARY 1 20.0
END DESCRIPTION:
XS GIS Cut Line= 3
      2312975.00     13722925.01      2312975.00     13723325.00
      2313174.97     13723574.97
#Sta/Elev= 30
  4595.4  552.06  4815.4  549.95  4905.4  548.44  4955.4  546.24  4975.4  546.51
  4985.4  544.87  4992.9  542.40  4998.6  542.40  5006.2  536.66  5006.6  536.16
  5011.8  536.66  5023.4  537.67  5031.4  539.77  5045.8  541.67  5059.4  544.76
  5066.6  544.66  5073.0  545.62  5130.7  547.61  5137.1  546.05  5145.1  545.83
  5151.5  544.40  5173.9  543.69  5201.1  544.22  5215.5  543.32  5223.5  544.56
  5229.9  543.90  5237.9  548.19  5244.3  547.58  5251.5  550.78  5315.5  552.60
#Mann=3,-1,0
  4595.4    0.07       0  5006.2    0.07       0  5011.8    0.07       0
Bank Sta=5006.2,5011.8
Exp/Cntr=0.3,0.1

Type RM Length L Ch R = 1,9934,290,290,290
BEGIN DESCRIPTION:
A19594
END DESCRIPTION:
XS GIS Cut Line= 5
      2312961.06     13722950.07      2312891.62     13723219.13
      2312817.84     13723349.34      2312856.90     13723592.40
      2312982.78     13723757.34
#Sta/Elev= 30
  4495.3  551.40  4695.5  549.76  4741.4  548.83  4775.3  549.03  4826.6  547.75
  4906.4  544.86  4922.8  544.83  4935.0  543.53  4940.1  543.83  4961.6  540.34
  4989.3  539.24  4996.9  537.36  5002.0  537.71  5006.8  535.95  5007.2  535.45
  5011.9  535.45  5012.4  535.95  5029.8  544.39  5040.0  545.60  5070.4  547.17
  5120.7  547.86  5151.4  549.02  5171.6  548.67  5176.3  549.42  5192.2  548.76
  5240.8  549.08  5255.3  548.36  5280.9  548.18  5303.9  547.83  5376.5  548.92
#Mann=8,-1,0
  4495.3    0.07       0  4826.6    0.12       0  4961.6    0.07       0
  5006.8    0.07       0  5012.4    0.07       0  5192.2    0.16       0
  5280.9    0.07       0  5303.9    0.16       0
Bank Sta=5006.8,5012.4
Exp/Cntr=0.3,0.1

Type RM Length L Ch R = 1,9644,394,394,394
BEGIN DESCRIPTION:
A19593
END DESCRIPTION:
XS GIS Cut Line= 3
      2312396.82     13723019.45      2312626.86     13723544.65
      2312909.01     13723766.03
#Sta/Elev= 30
  4560.9  557.98  4646.2  554.26  4676.1  552.20  4792.0  545.82  4867.6  541.92
  4873.0  541.99  4883.6  541.15  4890.9  539.43  4896.4  539.73  4905.4  538.22
  4919.7  538.04  4972.0  537.21  4981.7  534.63  4986.0  531.81  4986.5  531.31
  4993.3  531.31  4993.8  531.81  5003.6  537.02  5013.3  541.28  5042.1  543.74
  5094.3  545.46  5169.5  546.88  5264.8  546.97  5318.7  547.31  5353.9  546.75
  5360.7  547.17  5374.7  546.45  5399.3  546.25  5484.8  546.91  5492.9  546.95
#Mann=8,-1,0
  4560.9    0.07       0  4919.7    0.16       0  4981.7    0.07       0
  4986.0    0.07       0  4993.8    0.07       0  5264.8    0.16       0
  5399.3    0.07       0  5484.8    0.16       0
Bank Sta=4986,4993.8
Exp/Cntr=0.3,0.1