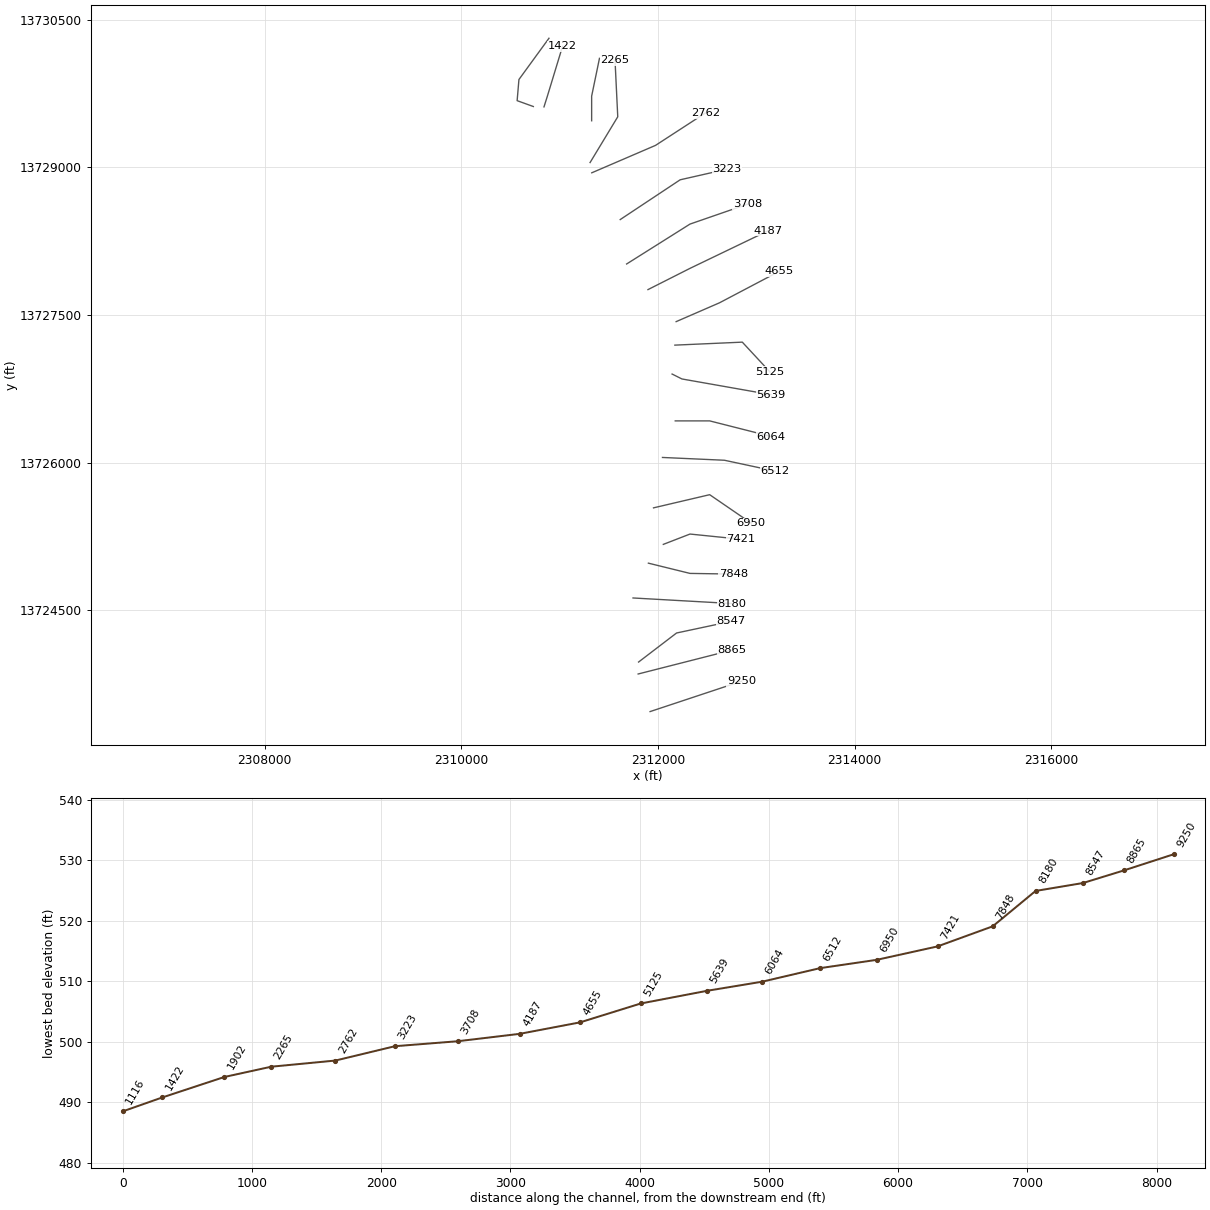
HEC-RAS study KRAMS TRIBUTARY 1.prj: KRAMS TRIBUTARY 1 Base Level Engineering

--- KRAMS TRIBUTARY 1.g01 (geometry) --- (continued)

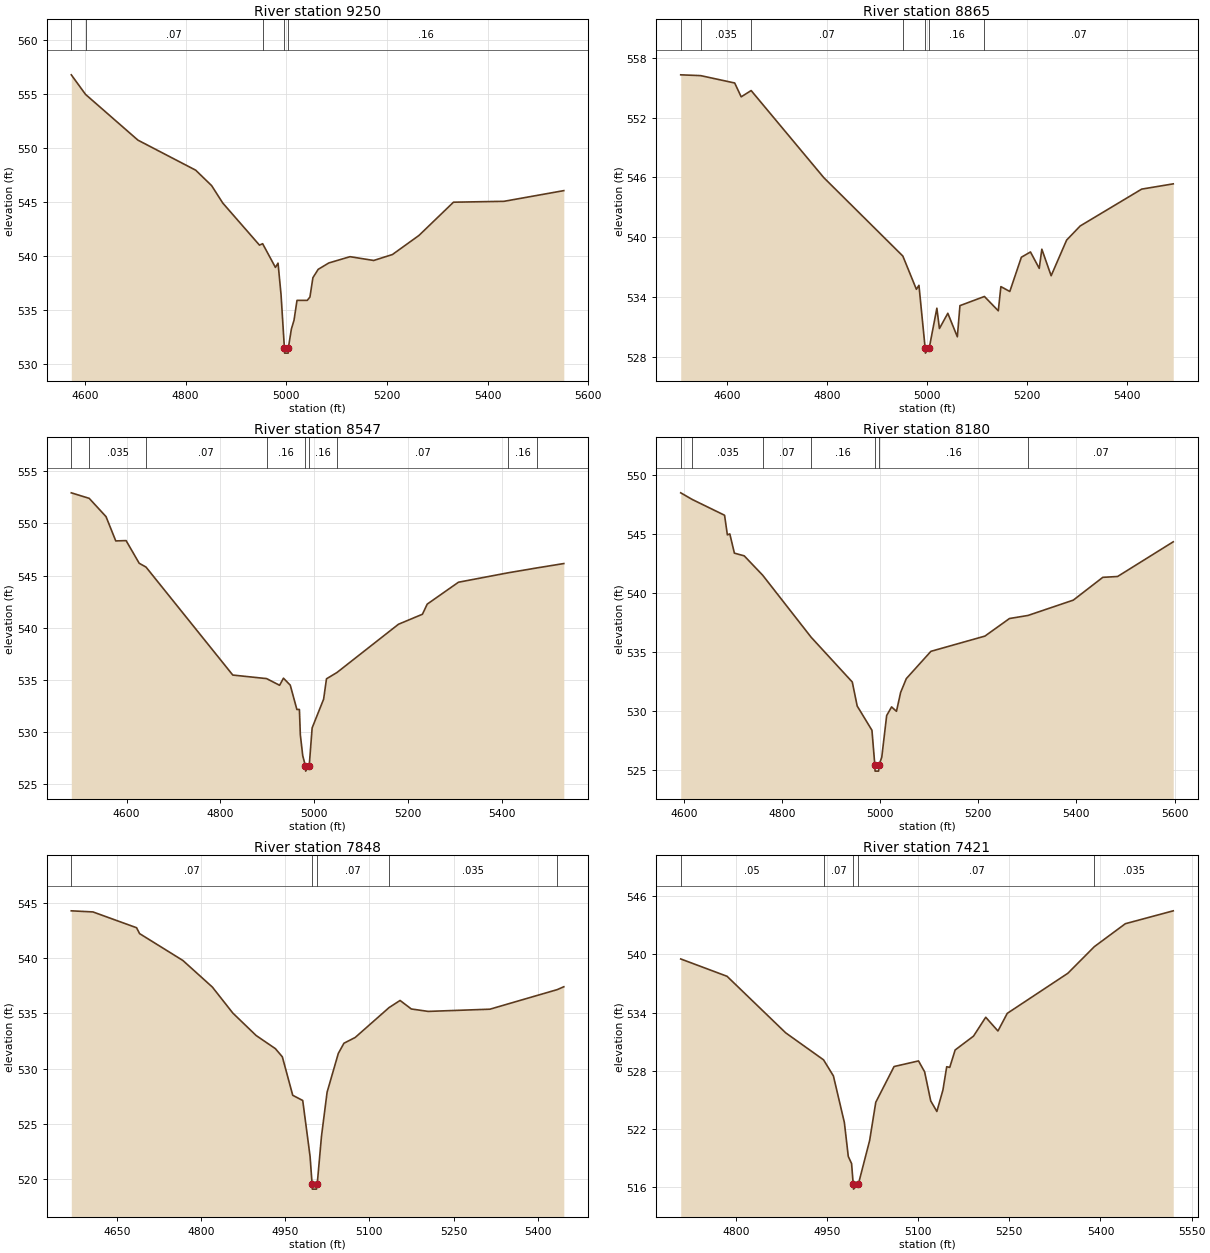
Type RM Length L Ch R = 1,9250,385,385,385
BEGIN DESCRIPTION:
A19592
END DESCRIPTION:
XS GIS Cut Line= 2
      2311919.36     13723470.86      2312848.17     13723779.01
#Sta/Elev= 30
  4573.0  556.75  4601.3  554.94  4705.4  550.71  4820.2  547.93  4851.9  546.50
  4874.0  544.89  4946.9  541.00  4953.2  541.13  4978.6  538.94  4983.8  539.33
  4989.8  536.41  4996.4  531.51  4996.9  531.01  5003.9  531.01  5004.4  531.51
  5010.3  533.24  5015.5  534.04  5021.5  535.89  5041.9  535.89  5047.2  536.20
  5053.1  537.99  5063.6  538.76  5084.7  539.35  5126.8  539.93  5173.9  539.58
  5211.1  540.13  5263.7  541.89  5332.4  544.97  5432.7  545.05  5551.6  546.04
#Mann=5,-1,0
  4573.0   0.035       0  4601.3    0.07       0  4953.2    0.16       0
  4996.4    0.07       0  5004.4    0.16       0
Bank Sta=4996.4,5004.4
Exp/Cntr=0.3,0.1

Type RM Length L Ch R = 1,8865,318,318,318
BEGIN DESCRIPTION:
A19591
END DESCRIPTION:
XS GIS Cut Line= 2
      2311797.89     13723852.82      2312751.39     13724095.53
#Sta/Elev= 30
  4508.1  556.29  4547.9  556.21  4615.9  555.47  4628.9  554.08  4648.8  554.71
  4794.0  545.96  4951.8  538.09  4978.9  534.75  4984.0  535.15  4996.4  528.84
  4996.9  528.34  5004.5  528.84  5019.8  532.85  5024.9  530.81  5041.7  532.34
  5060.7  529.98  5065.9  533.11  5114.8  534.03  5142.5  532.59  5147.7  535.02
  5165.5  534.53  5188.6  537.97  5206.8  538.50  5224.3  536.85  5229.5  538.78
  5248.1  536.11  5279.0  539.69  5306.1  541.11  5428.9  544.81  5492.0  545.34
#Mann=7,-1,0
  4508.1    0.07       0  4547.9   0.035       0  4648.8    0.07       0
  4951.8    0.16       0  4996.4    0.07       0  5004.5    0.16       0
  5114.8    0.07       0
Bank Sta=4996.4,5004.5
Exp/Cntr=0.3,0.1

Type RM Length L Ch R = 1,8547,367,367,367
BEGIN DESCRIPTION:
A19590
END DESCRIPTION:
XS GIS Cut Line= 3
      2311802.18     13723974.32      2312188.50     13724269.48
      2312739.71     13724386.67
#Sta/Elev= 30
  4482.2  552.93  4520.4  552.40  4556.2  550.65  4577.0  548.32  4599.0  548.35
  4626.9  546.18  4641.5  545.81  4826.4  535.46  4898.4  535.12  4926.2  534.48
  4934.4  535.16  4948.9  534.49  4963.0  532.16  4968.4  532.16  4970.4  529.72
  4975.5  527.73  4981.2  526.75  4981.7  526.25  4989.3  526.75  4995.5  530.39
  5020.0  533.15  5026.1  535.10  5048.3  535.70  5179.5  540.33  5230.6  541.29
  5240.8  542.26  5307.4  544.36  5412.8  545.26  5475.8  545.74  5531.9  546.15
#Mann=9,-1,0
  4482.2    0.07       0  4520.4   0.035       0  4641.5    0.07       0
  4898.4    0.16       0  4981.2    0.07       0  4989.3    0.16       0
  5048.3    0.07       0  5412.8    0.16       0  5475.8    0.07       0
Bank Sta=4981.2,4989.3
Exp/Cntr=0.3,0.1

Type RM Length L Ch R = 1,8180,332,332,332
BEGIN DESCRIPTION:
A19589
END DESCRIPTION:
XS GIS Cut Line= 2
      2311745.75     13724625.39      2312748.37     13724568.96
#Sta/Elev= 30
  4593.2  548.52  4617.0  547.95  4682.6  546.62  4688.3  544.96  4693.3  545.04
  4702.6  543.41  4722.7  543.18  4760.5  541.53  4859.2  536.28  4943.0  532.49
  4953.0  530.46  4983.1  528.40  4989.0  525.44  4989.5  524.94  4996.7  524.94
  4997.2  525.44  5003.1  526.11  5013.1  529.65  5023.1  530.38  5033.1  530.01
  5041.6  531.61  5053.2  532.78  5103.3  535.09  5213.4  536.38  5263.5  537.87
  5301.3  538.13  5393.7  539.43  5453.8  541.36  5483.9  541.43  5597.4  544.37
#Mann=7,-1,0
  4593.2    0.07       0  4617.0   0.035       0  4760.5    0.07       0
  4859.2    0.16       0  4989.0    0.07       0  4997.2    0.16       0
  5301.3    0.07       0
Bank Sta=4989,4997.2
Exp/Cntr=0.3,0.1

Type RM Length L Ch R = 1,7848,427,427,427
BEGIN DESCRIPTION:
KRAMS TRIBUTARY 1 15.0
END DESCRIPTION:
XS GIS Cut Line= 3
      2311902.05     13724979.11      2312325.00     13724875.00
      2312766.57     13724868.12
#Sta/Elev= 30
  4569.0  544.27  4607.6  544.17  4685.3  542.74  4690.6  542.21  4767.7  539.78
  4820.3  537.37  4856.7  535.02  4898.2  532.99  4932.5  531.80  4944.9  531.06
  4963.4  527.58  4981.2  527.11  4994.3  522.05  4997.8  519.59  4998.3  519.09
  5005.7  519.09  5006.2  519.59  5007.1  519.59  5014.6  523.87  5024.6  527.86
  5044.6  531.37  5054.6  532.29  5074.6  532.81  5135.1  535.52  5154.6  536.16
  5174.6  535.39  5204.6  535.17  5314.6  535.37  5434.4  537.14  5446.2  537.40
#Mann=5,-1,0
  4569.0    0.07       0  4997.8    0.07       0  5006.2    0.07       0
  5135.1   0.035       0  5434.4    0.07       0
Bank Sta=4997.8,5006.2
Exp/Cntr=0.3,0.1

Type RM Length L Ch R = 1,7421,471,471,471
BEGIN DESCRIPTION:
KRAMS TRIBUTARY 1 14.0
END DESCRIPTION:
XS GIS Cut Line= 3
      2312053.90     13725170.07      2312325.00     13725275.00
      2312841.93     13725222.37
#Sta/Elev= 30
  4709.4  539.54  4785.6  537.75  4882.1  531.91  4944.4  529.12  4960.6  527.46
  4978.6  522.66  4985.1  519.14  4990.5  518.41  4993.2  516.27  4993.7  515.77
  5001.6  516.27  5020.2  520.79  5030.3  524.74  5060.4  528.43  5100.6  529.01
  5110.7  527.88  5120.7  524.88  5130.8  523.79  5140.8  526.01  5147.0  528.41
  5152.0  528.34  5160.9  530.14  5191.1  531.57  5211.2  533.52  5231.3  532.10
  5246.6  533.92  5346.3  538.06  5389.9  540.81  5440.9  543.18  5519.7  544.51
#Mann=5,-1,0
  4709.4    0.05       0  4944.4    0.07       0  4993.2    0.07       0
  5001.6    0.07       0  5389.9   0.035       0
Bank Sta=4993.2,5001.6
Exp/Cntr=0.3,0.1

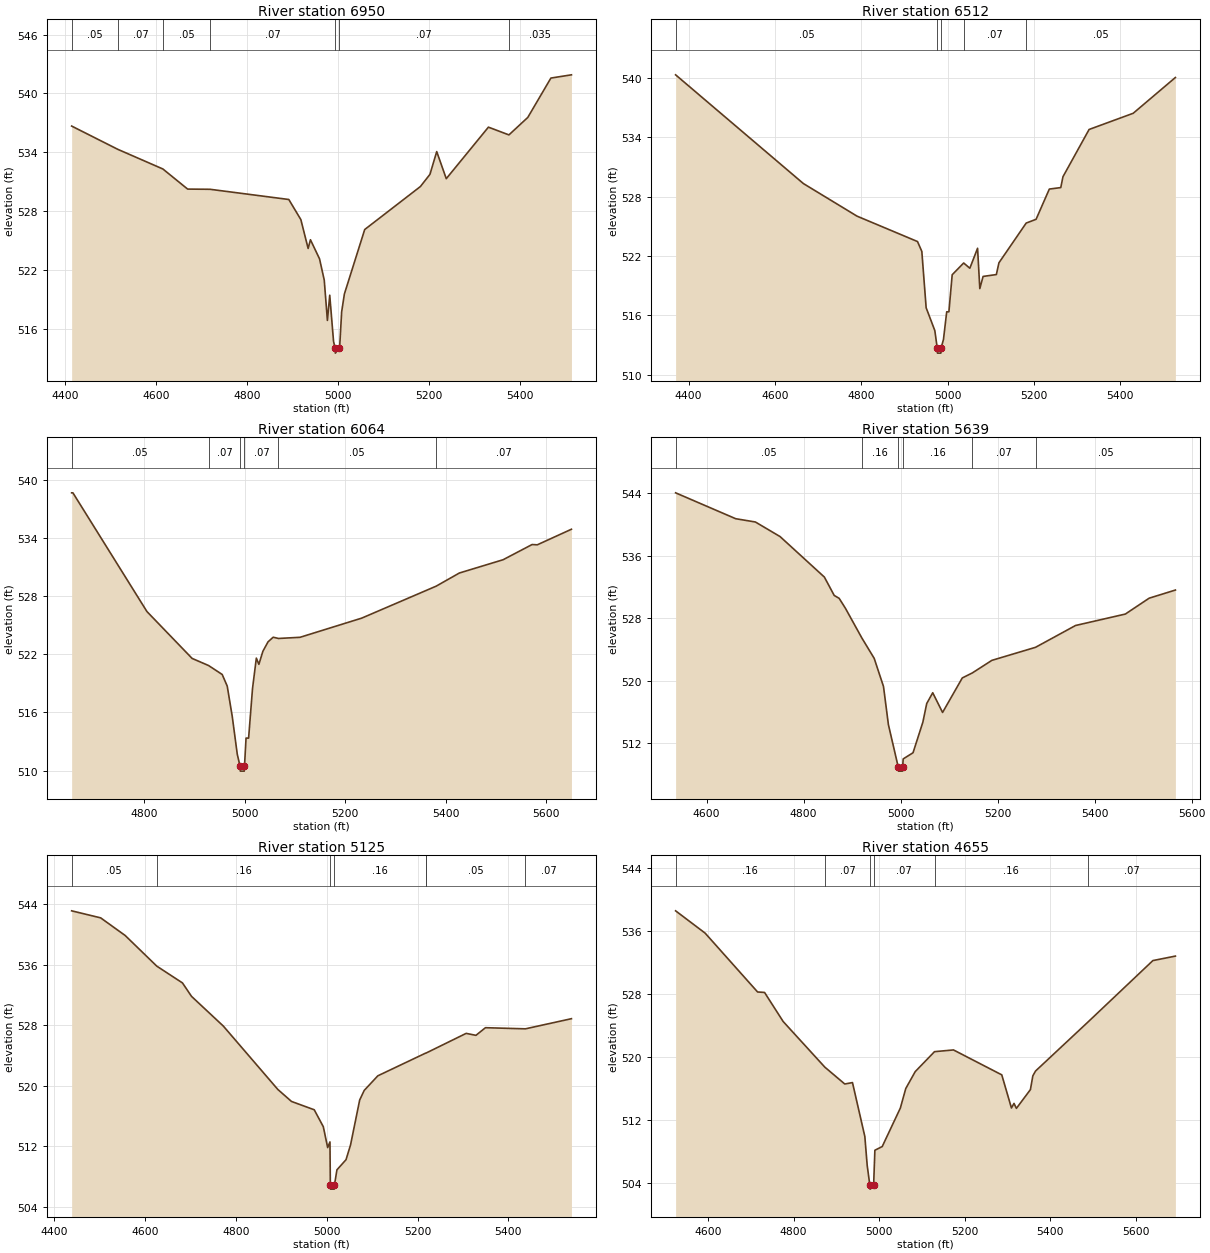
Type RM Length L Ch R = 1,6950,438,438,438
BEGIN DESCRIPTION:
KRAMS TRIBUTARY 1 13.0
END DESCRIPTION:
XS GIS Cut Line= 3
      2311954.17     13725541.19      2312525.00     13725675.00
      2312948.01     13725384.96
#Sta/Elev= 30
  4414.1  536.68  4515.6  534.31  4614.7  532.31  4669.2  530.26  4718.5  530.24
  4891.7  529.20  4918.2  527.15  4934.2  524.21  4939.3  525.10  4959.3  523.15
  4969.6  521.00  4976.6  516.88  4981.7  519.45  4990.1  514.74  4993.6  514.05
  4994.1  513.55  5002.1  514.05  5003.4  514.05  5007.9  517.75  5013.9  519.57
  5058.6  526.14  5181.1  530.52  5202.1  531.76  5217.0  534.08  5238.0  531.32
  5330.7  536.57  5375.8  535.78  5417.3  537.56  5468.1  541.57  5513.3  541.90
#Mann=7,-1,0
  4414.1    0.05       0  4515.6    0.07       0  4614.7    0.05       0
  4718.5    0.07       0  4993.6    0.07       0  5002.1    0.07       0
  5375.8   0.035       0
Bank Sta=4993.6,5002.1
Exp/Cntr=0.3,0.1

Type RM Length L Ch R = 1,6512,448,448,448
BEGIN DESCRIPTION:
KRAMS TRIBUTARY 1 12.0
END DESCRIPTION:
XS GIS Cut Line= 3
      2312045.24     13726053.34      2312675.00     13726025.00
      2313190.51     13725914.57
#Sta/Elev= 30
  4369.9  540.34  4665.8  529.34  4790.1  526.04  4930.2  523.47  4940.2  522.47
  4950.2  516.77  4970.3  514.46  4975.9  512.68  4976.4  512.18  4984.2  512.18
  4984.7  512.68  4990.3  513.56  4997.8  516.36  5002.9  516.36  5010.5  520.11
  5037.1  521.30  5051.4  520.77  5069.3  522.79  5074.5  518.71  5082.1  519.94
  5112.8  520.13  5118.8  521.32  5181.9  525.34  5204.8  525.72  5235.5  528.78
  5262.0  528.93  5267.1  530.03  5327.6  534.81  5429.8  536.45  5527.5  540.07
#Mann=5,-1,0
  4369.9    0.05       0  4975.9    0.05       0  4984.7    0.05       0
  5037.1    0.07       0  5181.9    0.05       0
Bank Sta=4975.9,4984.7
Exp/Cntr=0.3,0.1

Type RM Length L Ch R = 1,6064,425,425,425
BEGIN DESCRIPTION:
KRAMS TRIBUTARY 1 11.0
END DESCRIPTION:
XS GIS Cut Line= 3
      2312174.95     13726425.00      2312525.00     13726425.00
      2313151.04     13726266.26
#Sta/Elev= 30
  4655.0  538.68  4657.5  538.68  4805.0  526.42  4895.0  521.58  4928.0  520.84
  4955.0  519.92  4965.0  518.72  4975.0  515.59  4985.0  511.69  4990.6  510.44
  4991.1  509.94  4998.9  509.94  4999.4  510.44  5002.5  513.35  5007.6  513.35
  5015.4  518.47  5023.0  521.61  5028.1  520.97  5036.0  522.31  5046.3  523.29
  5056.6  523.77  5067.0  523.64  5110.1  523.76  5233.0  525.74  5381.3  529.04
  5427.6  530.40  5514.7  531.77  5572.5  533.34  5582.8  533.31  5650.9  534.92
#Mann=6,-1,0
  4655.0    0.05       0  4928.0    0.07       0  4990.6    0.07       0
  4999.4    0.07       0  5067.0    0.05       0  5381.3    0.07       0
Bank Sta=4990.6,4999.4
Exp/Cntr=0.3,0.1

Type RM Length L Ch R = 1,5639,514,514,514
BEGIN DESCRIPTION:
KRAMS TRIBUTARY 1 10.0
END DESCRIPTION:
XS GIS Cut Line= 3
      2312143.06     13726901.04      2312243.06     13726851.04
      2313147.67     13726691.36
#Sta/Elev= 30
  4536.1  544.02  4660.0  540.71  4700.6  540.29  4751.4  538.43  4842.8  533.25
  4863.1  530.90  4873.3  530.53  4886.2  529.26  4920.1  525.46  4945.5  522.86
  4964.7  519.26  4974.8  514.39  4995.2  508.94  4995.7  508.44  5003.6  508.44
  5004.1  508.94  5005.3  510.00  5025.6  510.79  5045.9  514.71  5053.8  517.08
  5066.2  518.46  5086.5  515.94  5127.1  520.35  5148.0  521.00  5188.1  522.60
  5278.2  524.27  5360.7  527.06  5463.3  528.52  5512.4  530.55  5566.5  531.59
#Mann=6,-1,0
  4536.1    0.05       0  4920.1    0.16       0  4995.2    0.07       0
  5004.1    0.16       0  5148.0    0.07       0  5278.2    0.05       0
Bank Sta=4995.2,5004.1
Exp/Cntr=0.3,0.1

Type RM Length L Ch R = 1,5125,470,470,470
BEGIN DESCRIPTION:
KRAMS TRIBUTARY 1 9.0
END DESCRIPTION:
XS GIS Cut Line= 3
      2312171.17     13727194.83      2312856.90     13727225.21
      2313139.01     13726921.40
#Sta/Elev= 30
  4438.0  543.13  4501.9  542.20  4555.9  539.87  4625.5  535.82  4682.1  533.60
  4702.1  531.82  4772.2  527.89  4892.3  519.51  4922.3  517.93  4972.4  516.83
  4992.4  514.59  5002.0  511.83  5007.0  512.58  5007.9  506.84  5008.4  506.34
  5016.3  506.34  5016.8  506.84  5022.4  508.89  5042.4  510.23  5052.4  512.19
  5072.5  518.12  5082.5  519.39  5112.5  521.32  5217.8  524.32  5218.5  524.32
  5307.1  526.93  5328.6  526.67  5349.6  527.68  5437.6  527.53  5539.0  528.87
#Mann=7,-1,0
  4438.0    0.05       0  4625.5    0.16       0  5007.9    0.07       0
  5016.8    0.16       0  5217.8    0.07       0  5218.5    0.05       0
  5437.6    0.07       0
Bank Sta=5007.9,5016.8
Exp/Cntr=0.3,0.1

Type RM Length L Ch R = 1,4655,468,468,468
BEGIN DESCRIPTION:
KRAMS TRIBUTARY 1 8.0
END DESCRIPTION:
XS GIS Cut Line= 3
      2312184.17     13727433.55      2312625.00     13727625.00
      2313234.47     13727945.68
#Sta/Elev= 30
  4523.9  538.51  4593.0  535.68  4715.7  528.22  4732.0  528.16  4775.6  524.47
  4873.0  518.69  4919.7  516.55  4937.7  516.73  4966.6  509.90  4972.1  506.25
  4978.3  503.72  4978.8  503.22  4987.2  503.72  4990.1  508.15  5007.3  508.62
  5049.7  513.50  5062.4  515.98  5084.5  518.12  5129.6  520.65  5174.0  520.87
  5287.0  517.71  5309.6  513.51  5315.6  514.09  5321.2  513.46  5354.0  515.84
  5359.7  517.59  5366.1  518.20  5488.3  524.39  5640.5  532.20  5693.2  532.77
#Mann=6,-1,0
  4523.9    0.16       0  4873.0    0.07       0  4978.3    0.07       0
  4987.2    0.07       0  5129.6    0.16       0  5488.3    0.07       0
Bank Sta=4978.3,4987.2
Exp/Cntr=0.3,0.1

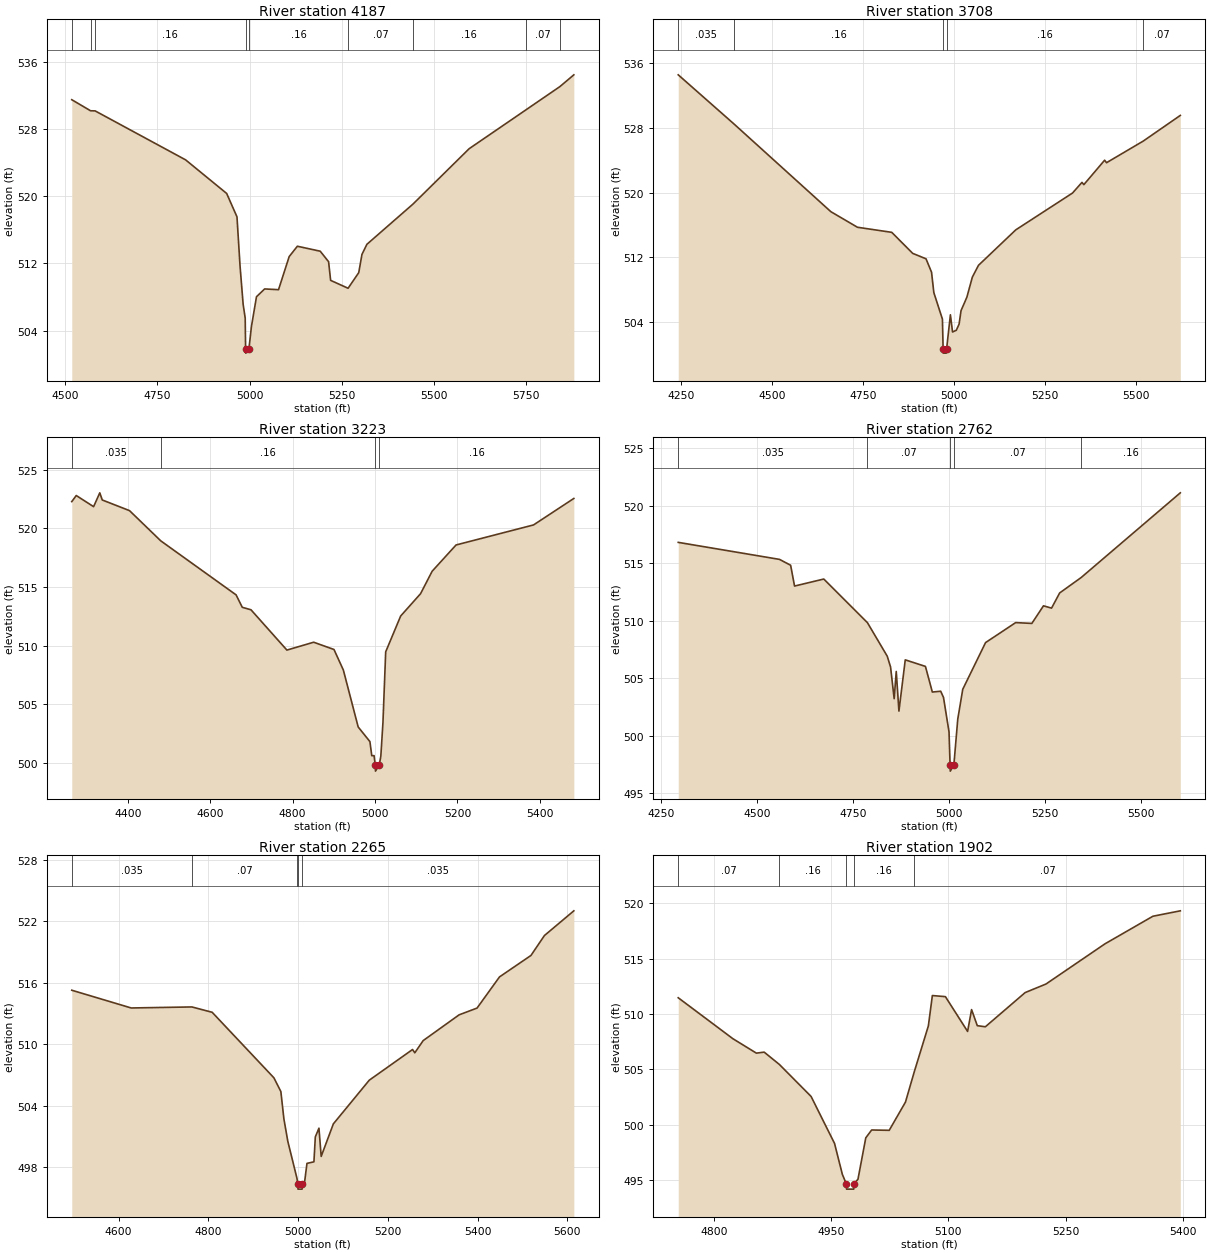
Type RM Length L Ch R = 1,4187,479,479,479
BEGIN DESCRIPTION:
KRAMS TRIBUTARY 1 7.0
END DESCRIPTION:
XS GIS Cut Line= 3
      2311897.69     13727759.06      2312325.00     13727975.00
      2313120.83     13728357.62
#Sta/Elev= 30
  4517.7  531.48  4568.8  530.16  4581.0  530.15  4826.5  524.32  4937.9  520.32
  4965.8  517.54  4974.1  511.71  4982.5  507.14  4988.1  505.49  4989.2  501.82
  4989.7  501.32  4998.2  501.82  5005.0  504.48  5018.7  508.03  5040.9  508.96
  5078.5  508.87  5107.4  512.81  5129.6  514.04  5191.6  513.45  5214.3  512.20
  5219.8  509.98  5267.2  509.04  5296.1  510.90  5304.8  513.07  5318.2  514.27
  5443.0  519.05  5595.6  525.65  5749.2  530.26  5841.7  533.04  5879.5  534.44
#Mann=9,-1,0
  4517.7    0.16       0  4568.8    0.07       0  4581.0    0.16       0
  4989.2    0.07       0  4998.2    0.16       0  5267.2    0.07       0
  5443.0    0.16       0  5749.2    0.07       0  5841.7    0.05       0
Bank Sta=4989.2,4998.2
Exp/Cntr=0.3,0.1

Type RM Length L Ch R = 1,3708,485,485,485
BEGIN DESCRIPTION:
KRAMS TRIBUTARY 1 6.0
END DESCRIPTION:
XS GIS Cut Line= 3
      2311680.70     13728019.49      2312325.00     13728425.00
      2312909.02     13728627.13
#Sta/Elev= 30
  4242.9  534.59  4395.8  528.51  4662.2  517.63  4735.2  515.70  4829.4  515.07
  4887.1  512.46  4923.6  511.79  4938.8  510.13  4945.1  507.60  4968.7  504.31
  4970.6  500.60  4971.1  500.10  4979.6  500.10  4980.1  500.60  4990.6  504.85
  4996.5  502.72  5006.8  502.93  5014.5  503.70  5019.8  505.36  5035.9  507.04
  5050.9  509.52  5067.7  510.98  5170.3  515.38  5326.1  519.94  5352.0  521.26
  5357.2  520.98  5414.3  524.01  5419.6  523.70  5520.4  526.38  5622.2  529.56
#Mann=5,-1,0
  4242.9   0.035       0  4395.8    0.16       0  4970.6    0.07       0
  4980.1    0.16       0  5520.4    0.07       0
Bank Sta=4970.6,4980.1
Exp/Cntr=0.3,0.1

Type RM Length L Ch R = 1,3223,461,461,461
BEGIN DESCRIPTION:
KRAMS TRIBUTARY 1 5.0
END DESCRIPTION:
XS GIS Cut Line= 3
      2311615.60     13728470.88      2312225.00     13728875.00
      2312700.37     13728982.96
#Sta/Elev= 30
  4263.8  522.28  4274.7  522.80  4316.8  521.85  4331.8  523.03  4337.8  522.42
  4404.0  521.51  4479.9  518.93  4662.7  514.32  4677.7  513.26  4698.8  513.05
  4786.0  509.61  4851.0  510.28  4900.3  509.66  4923.0  507.91  4959.0  503.05
  4987.5  501.80  4992.0  500.60  4997.6  500.60  5000.5  499.78  5001.0  499.28
  5010.1  499.78  5014.0  500.56  5019.1  503.40  5025.8  509.46  5062.2  512.52
  5110.4  514.42  5138.6  516.34  5196.6  518.58  5384.7  520.29  5482.5  522.55
#Mann=4,-1,0
  4263.8   0.035       0  4479.9    0.16       0  5000.5    0.07       0
  5010.1    0.16       0
Bank Sta=5000.5,5010.1
Exp/Cntr=0.3,0.1

Type RM Length L Ch R = 1,2762,497,497,497
BEGIN DESCRIPTION:
KRAMS TRIBUTARY 1 4.0
END DESCRIPTION:
XS GIS Cut Line= 3
      2311326.48     13728946.11      2311975.00     13729225.00
      2312480.53     13729553.44
#Sta/Elev= 30
  4293.8  516.81  4557.8  515.33  4586.8  514.82  4597.0  513.01  4673.2  513.62
  4786.9  509.83  4838.6  506.91  4847.3  505.97  4856.7  503.21  4862.1  505.58
  4869.1  502.13  4885.6  506.59  4938.2  506.02  4956.2  503.79  4978.0  503.86
  4985.3  503.32  4999.7  500.32  5002.5  497.41  5003.0  496.91  5012.2  497.41
  5022.5  501.44  5035.5  504.03  5094.9  508.09  5173.4  509.83  5215.6  509.76
  5245.9  511.29  5267.0  511.09  5288.1  512.41  5344.1  513.75  5602.6  521.12
#Mann=5,-1,0
  4293.8   0.035       0  4786.9    0.07       0  5002.5    0.07       0
  5012.2    0.07       0  5344.1    0.16       0
Bank Sta=5002.5,5012.2
Exp/Cntr=0.3,0.1

Type RM Length L Ch R = 1,2265,363,363,363
BEGIN DESCRIPTION:
KRAMS TRIBUTARY 1 3.0
END DESCRIPTION:
XS GIS Cut Line= 3
      2311309.15     13729050.29      2311590.51     13729515.30
      2311562.71     13730090.53
#Sta/Elev= 30
  4495.4  515.28  4627.9  513.55  4763.2  513.65  4808.4  513.13  4946.1  506.74
  4961.6  505.40  4968.4  502.72  4977.1  500.55  4997.5  496.94  4999.3  496.39
  4999.8  495.89  5008.9  495.89  5009.4  496.39  5014.0  496.41  5019.8  498.40
  5035.3  498.55  5038.4  500.98  5046.5  501.83  5051.5  499.08  5078.6  502.25
  5158.7  506.51  5255.2  509.50  5260.2  509.18  5278.9  510.37  5359.0  512.88
  5399.0  513.54  5449.1  516.58  5519.2  518.67  5549.2  520.61  5614.8  523.02
#Mann=5,-1,0
  4495.4   0.035       0  4763.2    0.07       0  4997.5    0.16       0
  4999.3    0.07       0  5009.4   0.035       0
Bank Sta=4999.3,5009.4
Exp/Cntr=0.3,0.1

Type RM Length L Ch R = 1,1902,480,480,480
BEGIN DESCRIPTION:
KRAMS TRIBUTARY 1 2.0
END DESCRIPTION:
XS GIS Cut Line= 3
      2311325.00     13729475.02      2311325.00     13729725.00
      2311404.65     13730109.36
#Sta/Elev= 30
  4754.3  511.47  4824.3  507.77  4854.3  506.47  4864.3  506.56  4883.7  505.45
  4924.3  502.56  4954.3  498.32  4964.3  495.53  4969.2  494.69  4969.7  494.19
  4978.9  494.19  4979.4  494.69  4984.3  495.08  4994.3  498.82  5001.8  499.53
  5024.3  499.50  5045.1  502.05  5056.5  504.82  5074.4  508.93  5079.5  511.67
  5096.2  511.57  5124.6  508.43  5129.7  510.40  5137.0  508.95  5147.3  508.85
  5198.3  511.94  5224.9  512.71  5300.4  516.34  5361.7  518.83  5396.8  519.32
#Mann=5,-1,0
  4754.3    0.07       0  4883.7    0.16       0  4969.2    0.07       0
  4979.4    0.16       0  5056.5    0.07       0
Bank Sta=4969.2,4979.4
Exp/Cntr=0.3,0.1

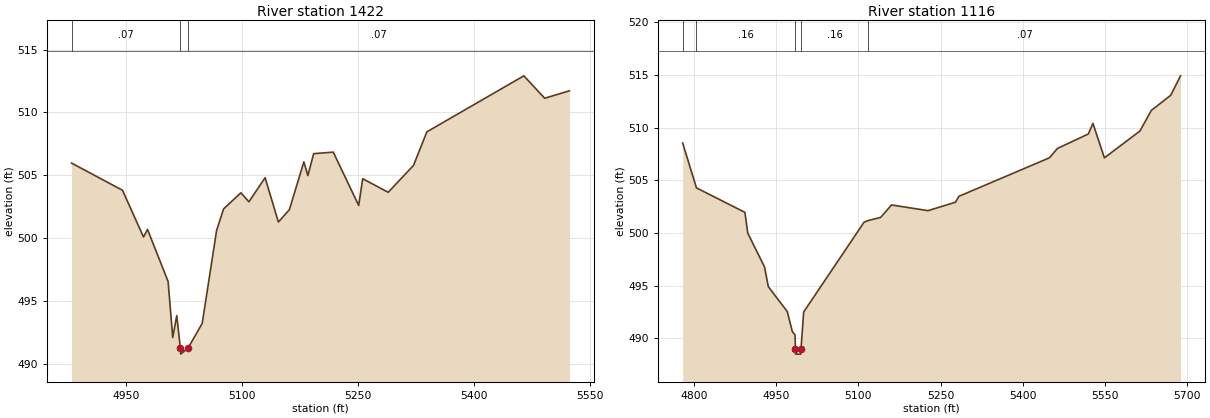
Type RM Length L Ch R = 1,1422,306,306,306
BEGIN DESCRIPTION:
KRAMS TRIBUTARY 1 1.0
END DESCRIPTION:
XS GIS Cut Line= 3
      2310840.54     13729615.96      2310875.00     13729725.00
      2311029.10     13730231.31
#Sta/Elev= 30
  4880.0  505.98  4945.9  503.82  4973.0  500.11  4978.2  500.71  5004.8  496.58
  5010.8  492.13  5016.0  493.87  5020.6  491.31  5021.1  490.81  5030.8  491.31
  5048.9  493.25  5067.5  500.63  5076.5  502.34  5098.9  503.62  5109.3  502.91
  5130.2  504.82  5147.4  501.30  5161.6  502.28  5180.3  506.08  5185.5  504.99
  5193.0  506.73  5218.3  506.85  5251.2  502.62  5256.4  504.74  5289.3  503.66
  5322.1  505.80  5339.3  508.46  5464.7  512.91  5491.6  511.13  5523.6  511.72
#Mann=3,-1,0
  4880.0    0.07       0  5020.6    0.07       0  5030.8    0.07       0
Bank Sta=5020.6,5030.8
Exp/Cntr=0.3,0.1

Type RM Length L Ch R = 1,1116,283,283,283
BEGIN DESCRIPTION:
A19588
END DESCRIPTION:
XS GIS Cut Line= 4
      2310732.20     13729619.70      2310567.49     13729679.18
      2310585.79     13729894.18      2310891.15     13730313.47
#Sta/Elev= 30
  4778.9  508.53  4804.1  504.28  4892.6  501.96  4897.9  499.98  4928.5  496.78
  4935.4  494.91  4969.9  492.56  4979.3  490.65  4984.3  490.32  4984.9  489.01
  4985.4  488.51  4994.6  488.51  4995.1  489.01  5000.0  492.51  5110.4  501.03
  5118.4  501.19  5140.5  501.48  5160.6  502.66  5227.2  502.12  5277.4  502.92
  5283.6  503.48  5448.9  507.13  5463.6  508.02  5520.0  509.39  5528.5  510.40
  5549.4  507.13  5614.3  509.67  5635.2  511.63  5670.7  513.07  5688.5  514.91
#Mann=5,-1,0
  4778.9    0.07       0  4804.1    0.16       0  4984.9    0.07       0
  4995.1    0.16       0  5118.4    0.07       0
Bank Sta=4984.9,4995.1
Exp/Cntr=0.3,0.1