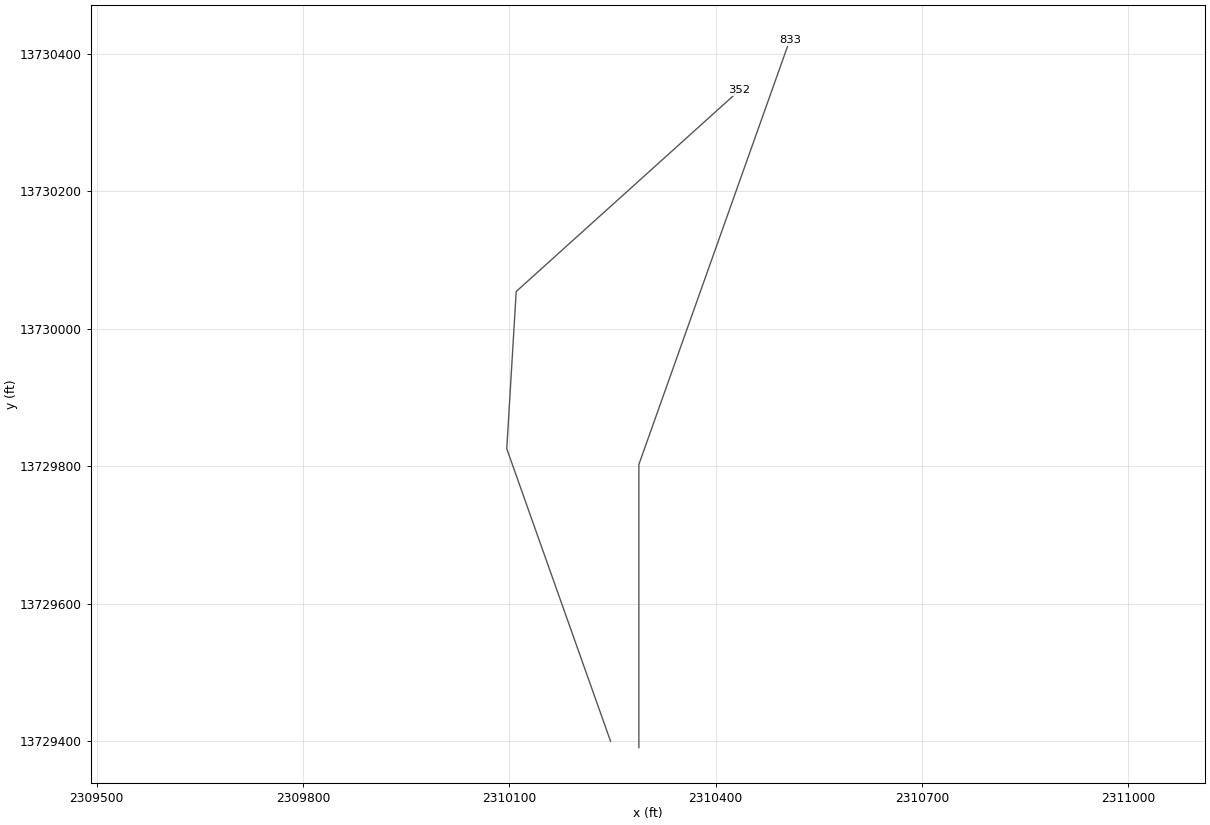
HEC-RAS study KRAMS TRIBUTARY 1.prj: KRAMS TRIBUTARY 1 Base Level Engineering

--- KRAMS TRIBUTARY 1.g01 (geometry) --- (continued)

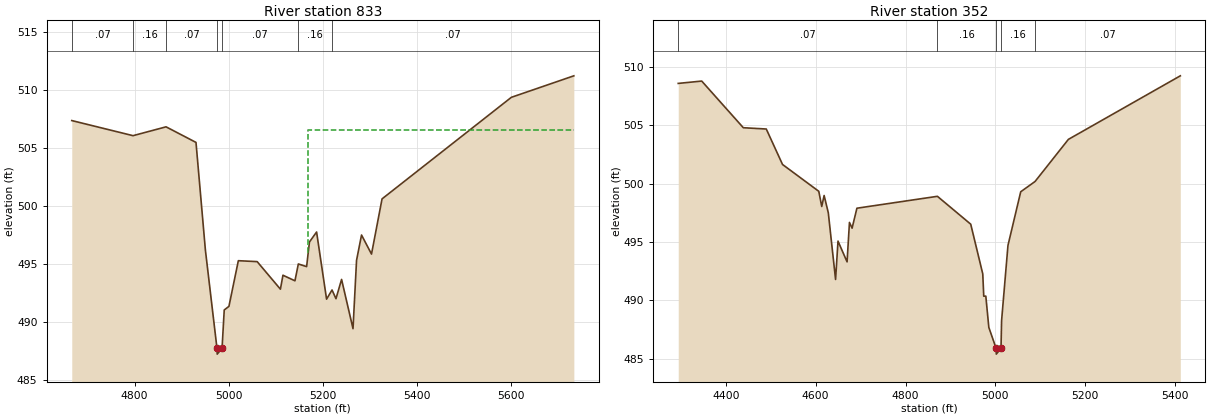
Type RM Length L Ch R = 1,833,481,481,481
BEGIN DESCRIPTION:
A19587
END DESCRIPTION:
XS GIS Cut Line= 3
      2310288.45     13729390.98      2310288.45     13729802.69
      2310507.98     13730420.11
#Sta/Elev= 30
  4666.4  507.36  4796.6  506.06  4866.8  506.82  4930.4  505.48  4950.4  496.21
  4975.0  487.76  4975.5  487.26  4985.8  487.76  4990.4  491.06  5000.4  491.37
  5020.4  495.30  5060.4  495.22  5109.8  492.85  5115.2  494.05  5140.7  493.57
  5147.9  495.02  5165.5  494.79  5171.5  496.91  5186.7  497.77  5207.9  491.99
  5219.5  492.78  5227.9  492.03  5239.8  493.69  5264.1  489.45  5271.6  495.33
  5282.2  497.51  5303.4  495.87  5325.8  500.62  5600.6  509.36  5733.4  511.21
#Mann=7,-1,0
  4666.4    0.07       0  4796.6    0.16       0  4866.8    0.07       0
  4975.0    0.07       0  4985.8    0.07       0  5147.9    0.16       0
  5219.5    0.07       0
#XS Ineff=2,0
       0                 5168.90    0.00  506.58
Permanent Ineff=
       F       F
Bank Sta=4975,4985.8
Exp/Cntr=0.3,0.1

Type RM Length L Ch R = 1,352,0,0,0
BEGIN DESCRIPTION:
A19586
END DESCRIPTION:
XS GIS Cut Line= 4
      2310247.27     13729400.14      2310096.32     13729825.56
      2310110.04     13730054.29      2310434.82     13730347.05
#Sta/Elev= 30
  4294.0  508.60  4346.3  508.80  4438.9  504.80  4490.0  504.69  4526.2  501.65
  4606.9  499.35  4613.5  498.05  4618.8  498.99  4628.1  497.51  4644.3  491.79
  4649.7  495.08  4669.9  493.30  4675.2  496.68  4681.1  496.19  4691.8  497.90
  4871.0  498.92  4945.2  496.53  4972.0  492.27  4974.2  490.36  4978.8  490.36
  4985.5  487.68  5001.7  485.89  5002.2  485.39  5012.6  485.89  5013.9  488.26
  5028.1  494.71  5056.5  499.31  5088.4  500.19  5162.6  503.80  5411.8  509.25
#Mann=5,-1,0
  4294.0    0.07       0  4871.0    0.16       0  5001.7    0.07       0
  5012.6    0.16       0  5088.4    0.07       0
Bank Sta=5001.7,5012.6
Exp/Cntr=0.3,0.1

Chan Stop Cuts=-1