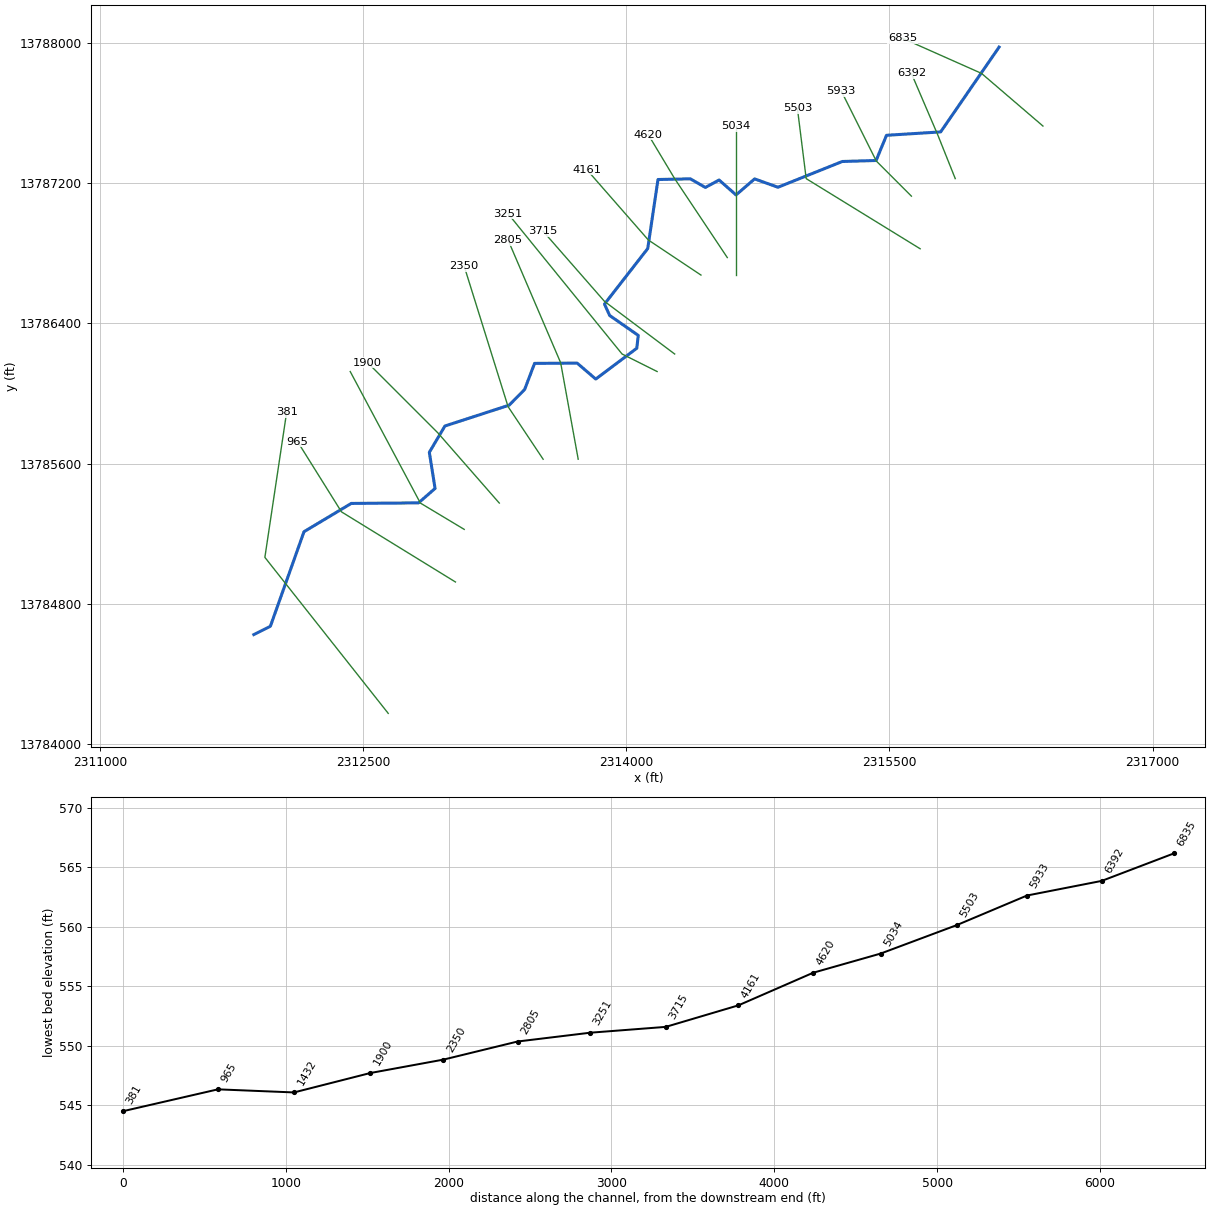
--- LITTLE CREEK TRIBUTARY 1.prj (project) ---

Proj Title=LITTLE CREEK TRIBUTARY 1 Base Level Engineering
Current Plan=p01
Default Exp/Contr=0.3,0.1
English Units
Geom File=g01
Flow File=f01
Plan File=p01
BEGIN DESCRIPTION:
LITTLE CREEK TRIBUTARY 1
END DESCRIPTION:

--- LITTLE CREEK TRIBUTARY 1.p01 (plan) ---

Plan Title=Multiple Run
Short Identifier=Multiple
Geom File=g01
Flow File=f01
Subcritical Flow
K Sum by GR= 0
Std Step Tol= 0.01
Critical Tol= 0.01
Num of Std Step Trials= 20
Max Error Tol= 0.3
Flow Tol Ratio= 0.001
Split Flow NTrial= 30
Split Flow Tol= 0.02
Split Flow Ratio= 0.02
Log Output Level= 0
Friction Slope Method= 1
Unsteady Friction Slope Method= 2
Unsteady Bridges Friction Slope Method= 1
Parabolic Critical Depth
Global Vel Dist=  1 , 1 , 1
Global Log Level= 0
CheckData=True
Encroach Param= -1, 0, 0, 0
BEGIN DESCRIPTION:
Multiple Run
END DESCRIPTION:

--- LITTLE CREEK TRIBUTARY 1.f01 (steady flow) ---

Flow Title=Multiple
Number of Profiles=7
Profile Names=10-year,25-year,50-year,1pct_min,100-year,1pct_plu,500-year
River Rch & RM= LITTLE CREEK TRI,Reach-1,6835
     771    1269    1730    1142    2278    4545    3915
River Rch & RM= LITTLE CREEK TRI,Reach-1,5034
     891    1472    2009    1326    2646    5279    4550
Boundary for River Rch & Prof#=LITTLE CREEK TRI,Reach-1,1
Up Type=0
Dn Type=3
Dn Slope=0.005
Boundary for River Rch & Prof#=LITTLE CREEK TRI,Reach-1,2
Up Type=0
Dn Type=3
Dn Slope=0.005
Boundary for River Rch & Prof#=LITTLE CREEK TRI,Reach-1,3
Up Type=0
Dn Type=3
Dn Slope=0.005
Boundary for River Rch & Prof#=LITTLE CREEK TRI,Reach-1,4
Up Type=0
Dn Type=3
Dn Slope=0.005
Boundary for River Rch & Prof#=LITTLE CREEK TRI,Reach-1,5
Up Type=0
Dn Type=3
Dn Slope=0.005
Boundary for River Rch & Prof#=LITTLE CREEK TRI,Reach-1,6
Up Type=0
Dn Type=3
Dn Slope=0.005
Boundary for River Rch & Prof#=LITTLE CREEK TRI,Reach-1,7
Up Type=0
Dn Type=3
Dn Slope=0.005

--- LITTLE CREEK TRIBUTARY 1.g01 (geometry) ---

Geom Title=Existing Conditions

River Reach=LITTLE CREEK TRI,Reach-1
Reach XY= 30
      2316125.00     13787975.00      2315791.80     13787491.42
      2315482.97     13787472.06      2315423.78     13787328.44
      2315230.94     13787322.74      2314864.31     13787175.77
      2314731.03     13787223.36      2314625.00     13787132.11
      2314528.41     13787217.15      2314450.04     13787174.69
      2314364.50     13787223.76      2314180.00     13787220.00
      2314121.46     13786826.47      2313874.87     13786509.58
      2313904.31     13786444.63      2314067.55     13786331.05
      2314058.95     13786257.95      2313825.00     13786082.08
      2313719.15     13786172.92      2313476.22     13786171.56
      2313419.48     13786022.56      2313331.08     13785933.13
      2312965.00     13785814.37      2312876.08     13785664.46
      2312908.80     13785458.29      2312814.57     13785376.04
      2312430.86     13785372.94      2312161.36     13785211.56
      2311969.67     13784672.34      2311875.00     13784625.00

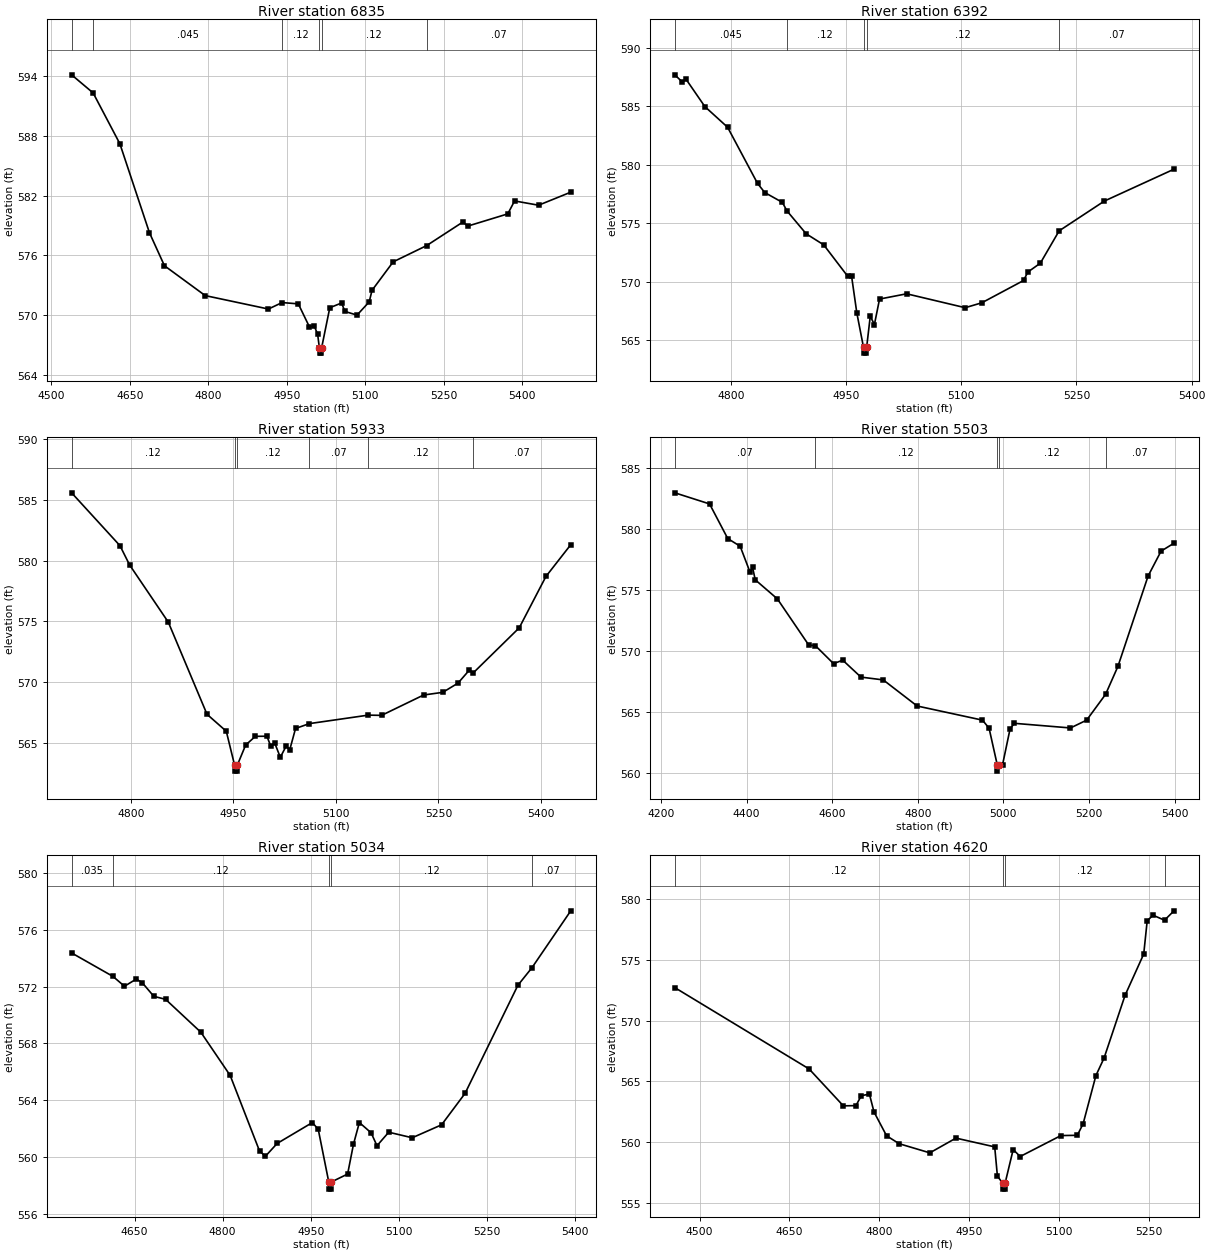
Type RM Length L Ch R = 1,6835,443,443,443
BEGIN DESCRIPTION:
LITTLE CREEK TRIBUTARY 1 14.0
END DESCRIPTION:
XS GIS Cut Line= 3
      2316375.01     13787524.99      2316025.00     13787825.00
      2315575.03     13788024.99
#Sta/Elev= 30
  4539.0  594.14  4580.1  592.32  4631.2  587.21  4687.7  578.27  4716.3  574.96
  4794.2  571.96  4914.9  570.61  4941.0  571.26  4972.0  571.13  4992.9  568.85
  5002.7  568.87  5008.9  568.08  5012.3  566.68  5012.6  566.18  5016.2  566.18
  5016.4  566.68  5032.1  570.74  5054.7  571.22  5060.9  570.37  5084.1  570.00
  5107.4  571.33  5112.8  572.49  5153.2  575.35  5217.0  576.98  5286.6  579.36
  5295.5  578.94  5372.1  580.17  5385.1  581.47  5430.9  581.04  5492.4  582.35
#Mann=6,-1,0
  4539.0   0.035       0  4580.1   0.045       0  4941.0    0.12       0
  5012.3    0.05       0  5016.4    0.12       0  5217.0    0.07       0
Bank Sta=5012.3,5016.4
Exp/Cntr=0.3,0.1

Type RM Length L Ch R = 1,6392,459,459,459
BEGIN DESCRIPTION:
LITTLE CREEK TRIBUTARY 1 13.0
END DESCRIPTION:
XS GIS Cut Line= 3
      2315875.01     13787224.98      2315775.00     13787475.00
      2315624.99     13787825.03
#Sta/Elev= 30
  4726.9  587.70  4736.3  587.10  4741.7  587.30  4766.0  584.98  4795.6  583.21
  4834.6  578.40  4844.0  577.62  4866.9  576.78  4872.9  576.05  4897.9  574.09
  4920.8  573.14  4951.8  570.47  4957.1  570.45  4963.9  567.31  4972.6  564.37
  4972.8  563.87  4976.4  563.87  4976.7  564.37  4981.4  567.03  4986.8  566.32
  4993.5  568.50  5028.8  568.95  5105.0  567.76  5126.7  568.18  5181.1  570.09
  5186.6  570.81  5202.9  571.57  5227.4  574.34  5286.3  576.89  5377.0  579.62
#Mann=5,-1,0
  4726.9   0.045       0  4872.9    0.12       0  4972.6    0.05       0
  4976.7    0.12       0  5227.4    0.07       0
Bank Sta=4972.6,4976.7
Exp/Cntr=0.3,0.1

Type RM Length L Ch R = 1,5933,430,430,430
BEGIN DESCRIPTION:
LITTLE CREEK TRIBUTARY 1 12.0
END DESCRIPTION:
XS GIS Cut Line= 3
      2315624.98     13787125.02      2315425.00     13787325.00
      2315225.01     13787724.98
#Sta/Elev= 30
  4713.5  585.60  4784.2  581.24  4798.3  579.65  4854.9  574.93  4911.5  567.33
  4939.7  565.93  4951.8  563.14  4952.1  562.64  4955.7  562.64  4955.9  563.14
  4968.0  564.79  4982.2  565.51  4999.1  565.52  5004.7  564.71  5010.3  564.99
  5018.7  563.78  5027.1  564.69  5032.6  564.42  5041.0  566.16  5061.2  566.56
  5147.4  567.26  5166.8  567.24  5228.3  568.92  5256.3  569.14  5278.6  569.90
  5295.4  570.99  5300.8  570.74  5368.1  574.46  5407.2  578.70  5443.5  581.32
#Mann=6,-1,0
  4713.5    0.12       0  4951.8    0.05       0  4955.9    0.12       0
  5061.2    0.07       0  5147.4    0.12       0  5300.8    0.07       0
Bank Sta=4951.8,4955.9
Exp/Cntr=0.3,0.1

Type RM Length L Ch R = 1,5503,469,469,469
BEGIN DESCRIPTION:
LITTLE CREEK TRIBUTARY 1 11.0
END DESCRIPTION:
XS GIS Cut Line= 3
      2315674.98     13786825.02      2315025.00     13787225.00
      2314975.00     13787625.00
#Sta/Elev= 30
  4232.4  582.98  4313.5  582.07  4356.0  579.23  4385.0  578.60  4408.1  576.47
  4414.0  576.86  4420.2  575.85  4472.0  574.28  4545.4  570.49  4560.7  570.45
  4603.3  568.97  4624.6  569.26  4667.2  567.87  4719.3  567.64  4798.5  565.50
  4951.2  564.34  4966.6  563.68  4985.8  560.66  4986.1  560.16  4990.0  560.66
  4998.1  560.68  5015.7  563.63  5025.8  564.08  5156.8  563.70  5194.6  564.34
  5238.9  566.46  5267.7  568.75  5338.2  576.16  5368.5  578.20  5398.7  578.85
#Mann=5,-1,0
  4232.4    0.07       0  4560.7    0.12       0  4985.8    0.05       0
  4990.0    0.12       0  5238.9    0.07       0
Bank Sta=4985.8,4990
Exp/Cntr=0.3,0.1

Type RM Length L Ch R = 1,5034,414,414,414
BEGIN DESCRIPTION:
LITTLE CREEK TRIBUTARY 1 10.0
END DESCRIPTION:
XS GIS Cut Line= 3
      2314625.00     13786675.01      2314625.00     13787125.00
      2314625.00     13787525.01
#Sta/Elev= 30
  4542.9  574.36  4613.3  572.71  4632.9  572.02  4652.9  572.52  4662.9  572.28
  4682.9  571.31  4702.9  571.10  4762.9  568.79  4812.9  565.75  4862.9  560.44
  4872.9  560.07  4892.9  560.97  4952.9  562.44  4962.9  561.96  4980.8  558.26
  4981.0  557.76  4984.7  557.76  4985.0  558.26  5012.9  558.82  5022.9  560.92
  5032.9  562.44  5052.9  561.72  5062.9  560.81  5082.9  561.76  5122.9  561.37
  5172.9  562.28  5212.9  564.49  5302.9  572.09  5326.8  573.32  5392.9  577.32
#Mann=5,-1,0
  4542.9   0.035       0  4613.3    0.12       0  4980.8    0.05       0
  4985.0    0.12       0  5326.8    0.07       0
Bank Sta=4980.8,4985
Exp/Cntr=0.3,0.1

Type RM Length L Ch R = 1,4620,459,459,459
BEGIN DESCRIPTION:
LITTLE CREEK TRIBUTARY 1 9.0
END DESCRIPTION:
XS GIS Cut Line= 3
      2314575.03     13786774.96      2314275.00     13787225.00
      2314125.01     13787474.98
#Sta/Elev= 30
  4458.9  572.70  4682.8  566.02  4739.9  562.99  4760.9  563.01  4769.9  563.83
  4783.4  563.95  4791.0  562.49  4812.0  560.53  4833.0  559.88  4884.1  559.13
  4927.7  560.34  4992.3  559.62  4996.8  557.22  5005.4  556.65  5005.7  556.15
  5009.5  556.15  5009.7  556.65  5023.1  559.40  5034.8  558.83  5102.8  560.55
  5130.0  560.57  5139.7  561.51  5161.1  565.48  5174.7  566.92  5209.7  572.07
  5240.8  575.46  5246.6  578.19  5256.3  578.65  5275.5  578.24  5291.3  579.01
#Mann=4,-1,0
  4458.9    0.12       0  5005.4    0.05       0  5009.7    0.12       0
  5275.5    0.07       0
Bank Sta=5005.4,5009.7
Exp/Cntr=0.3,0.1

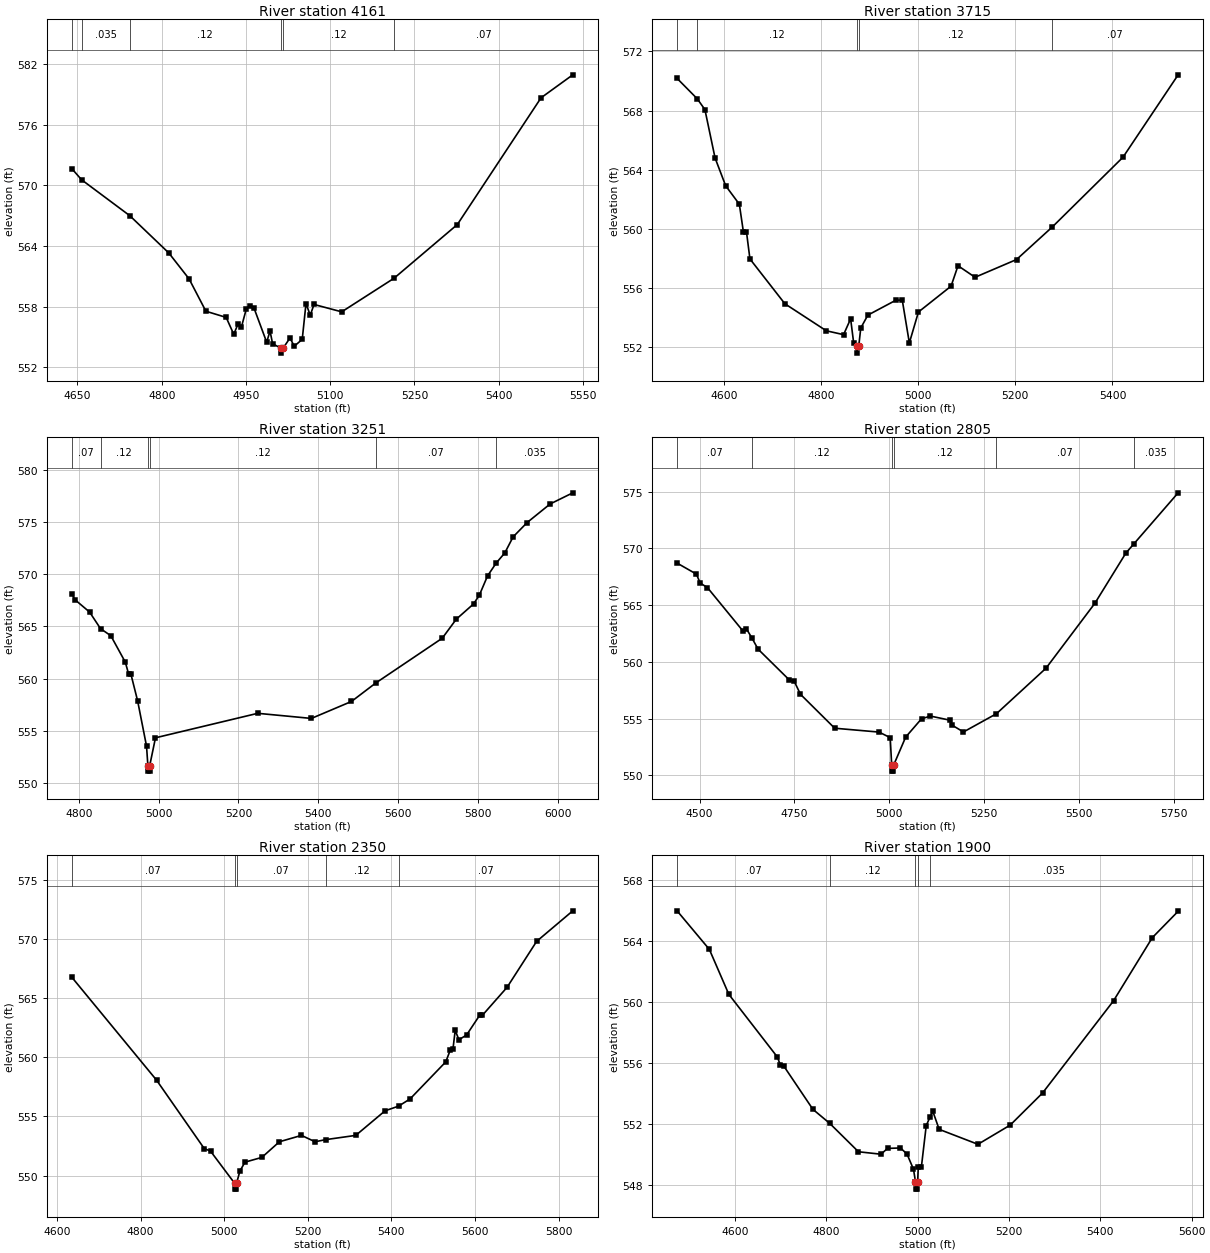
Type RM Length L Ch R = 1,4161,446,446,446
BEGIN DESCRIPTION:
LITTLE CREEK TRIBUTARY 1 8.0
END DESCRIPTION:
XS GIS Cut Line= 3
      2314425.03     13786674.98      2314125.00     13786875.00
      2313775.00     13787275.00
#Sta/Elev= 30
  4639.8  571.65  4657.4  570.54  4743.2  566.99  4812.6  563.31  4848.7  560.75
  4878.7  557.55  4914.8  556.94  4928.3  555.27  4935.8  556.28  4941.8  555.96
  4950.8  557.81  4956.8  558.09  4964.3  557.87  4986.9  554.49  4992.9  555.60
  4997.4  554.34  5011.9  553.91  5012.2  553.41  5016.3  553.91  5028.4  554.91
  5036.0  554.09  5050.2  554.77  5056.9  558.31  5064.5  557.15  5071.1  558.22
  5120.5  557.49  5213.7  560.81  5326.4  566.12  5475.4  578.64  5531.9  580.91
#Mann=6,-1,0
  4639.8    0.12       0  4657.4   0.035       0  4743.2    0.12       0
  5011.9    0.05       0  5016.3    0.12       0  5213.7    0.07       0
Bank Sta=5011.9,5016.3
Exp/Cntr=0.3,0.1

Type RM Length L Ch R = 1,3715,464,464,464
BEGIN DESCRIPTION:
LITTLE CREEK TRIBUTARY 1 7.0
END DESCRIPTION:
XS GIS Cut Line= 3
      2314275.04     13786224.97      2313875.00     13786525.00
      2313524.97     13786925.03
#Sta/Elev= 30
  4503.6  570.18  4545.1  568.80  4560.9  568.07  4581.8  564.80  4603.6  562.92
  4631.8  561.67  4640.1  559.81  4646.4  559.82  4653.6  557.97  4725.5  554.94
  4810.9  553.11  4846.4  552.85  4860.9  553.92  4867.2  552.28  4873.3  552.10
  4873.6  551.60  4877.7  552.10  4881.8  553.30  4896.4  554.17  4953.6  555.17
  4967.2  555.19  4981.8  552.29  5000.5  554.38  5067.7  556.13  5082.0  557.51
  5117.1  556.73  5202.5  557.93  5276.4  560.14  5421.7  564.85  5535.2  570.42
#Mann=5,-1,0
  4503.6    0.07       0  4545.1    0.12       0  4873.3    0.05       0
  4877.7    0.12       0  5276.4    0.07       0
Bank Sta=4873.3,4877.7
Exp/Cntr=0.3,0.1

Type RM Length L Ch R = 1,3251,446,446,446
BEGIN DESCRIPTION:
LITTLE CREEK TRIBUTARY 1 6.0
END DESCRIPTION:
XS GIS Cut Line= 3
      2314175.03     13786124.98      2313975.00     13786225.00
      2313325.01     13787024.99
#Sta/Elev= 30
  4782.5  568.15  4790.9  567.56  4827.3  566.38  4854.6  564.79  4880.4  564.11
  4916.7  561.57  4925.1  560.41  4930.7  560.42  4947.4  557.87  4969.8  553.51
  4973.2  551.61  4973.5  551.11  4977.3  551.11  4977.6  551.61  4992.2  554.31
  5248.2  556.66  5382.5  556.17  5482.9  557.80  5543.6  559.57  5710.1  563.87
  5745.3  565.70  5788.4  567.16  5802.8  567.99  5823.6  569.86  5845.4  571.10
  5866.7  572.06  5887.5  573.60  5922.7  574.98  5980.2  576.76  6036.9  577.83
#Mann=6,-1,0
  4782.5    0.07       0  4854.6    0.12       0  4973.2    0.05       0
  4977.6    0.12       0  5543.6    0.07       0  5845.4   0.035       0
Bank Sta=4973.2,4977.6
Exp/Cntr=0.3,0.1

Type RM Length L Ch R = 1,2805,455,455,455
BEGIN DESCRIPTION:
LITTLE CREEK TRIBUTARY 1 5.0
END DESCRIPTION:
XS GIS Cut Line= 3
      2313724.99     13785625.03      2313625.00     13786175.00
      2313324.98     13786875.04
#Sta/Elev= 30
  4440.9  568.70  4491.7  567.73  4501.9  566.94  4520.9  566.54  4613.7  562.75
  4623.8  562.90  4638.5  562.08  4654.3  561.12  4735.6  558.44  4749.6  558.29
  4766.1  557.14  4856.3  554.15  4973.2  553.81  5002.6  553.32  5006.6  550.87
  5007.0  550.37  5011.0  550.37  5011.3  550.87  5043.4  553.37  5085.1  554.98
  5108.7  555.22  5161.3  554.85  5166.7  554.40  5195.7  553.82  5282.7  555.43
  5413.3  559.44  5542.1  565.16  5623.7  569.58  5645.5  570.42  5761.5  574.89
#Mann=6,-1,0
  4440.9    0.07       0  4638.5    0.12       0  5006.6    0.05       0
  5011.3    0.12       0  5282.7    0.07       0  5645.5   0.035       0
Bank Sta=5006.6,5011.3
Exp/Cntr=0.3,0.1

Type RM Length L Ch R = 1,2350,450,450,450
BEGIN DESCRIPTION:
LITTLE CREEK TRIBUTARY 1 4.0
END DESCRIPTION:
XS GIS Cut Line= 3
      2313525.03     13785624.96      2313325.00     13785925.00
      2313074.99     13786725.04
#Sta/Elev= 30
  4635.1  566.76  4838.0  558.06  4952.1  552.28  4967.2  552.06  5024.7  549.35
  5025.1  548.85  5029.2  548.85  5029.5  549.35  5037.6  550.39  5049.7  551.13
  5090.0  551.53  5131.9  552.85  5184.8  553.39  5217.3  552.85  5242.4  553.03
  5314.7  553.39  5384.9  555.47  5417.1  555.86  5444.6  556.47  5530.0  559.60
  5540.5  560.57  5547.3  560.71  5552.6  562.26  5561.5  561.47  5579.8  561.87
  5612.3  563.60  5617.5  563.53  5676.7  565.90  5747.4  569.78  5833.9  572.36
#Mann=5,-1,0
  4635.1    0.07       0  5024.7    0.05       0  5029.5    0.07       0
  5242.4    0.12       0  5417.1    0.07       0
Bank Sta=5024.7,5029.5
Exp/Cntr=0.3,0.1

Type RM Length L Ch R = 1,1900,468,468,468
BEGIN DESCRIPTION:
LITTLE CREEK TRIBUTARY 1 3.0
END DESCRIPTION:
XS GIS Cut Line= 3
      2313274.98     13785375.02      2312925.00     13785775.00
      2312524.98     13786175.02
#Sta/Elev= 30
  4473.3  565.97  4544.0  563.44  4586.7  560.49  4693.0  556.38  4699.6  555.84
  4707.2  555.78  4770.8  552.95  4807.3  552.04  4870.5  550.17  4919.8  550.01
  4934.1  550.39  4962.5  550.42  4976.8  550.02  4991.0  549.02  4995.3  548.22
  4995.6  547.72  4999.7  547.72  5000.1  548.22  5001.5  549.18  5008.3  549.18
  5018.9  551.89  5027.1  552.44  5033.1  552.84  5047.2  551.64  5132.1  550.66
  5202.8  551.92  5273.5  554.02  5429.0  560.07  5513.9  564.21  5570.5  565.94
#Mann=5,-1,0
  4473.3    0.07       0  4807.3    0.12       0  4995.3    0.05       0
  5000.1    0.12       0  5027.1   0.035       0
Bank Sta=4995.3,5000.1
Exp/Cntr=0.3,0.1

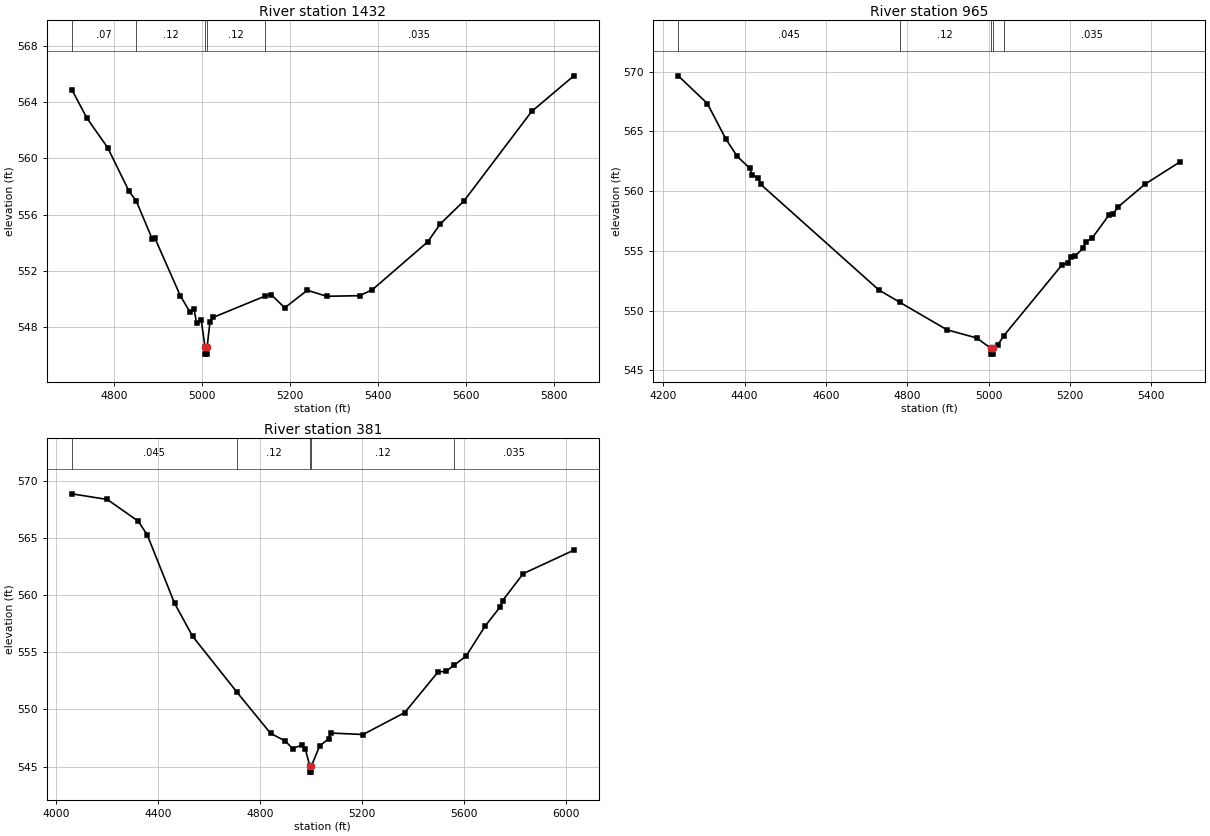
Type RM Length L Ch R = 1,1432,467,467,467
BEGIN DESCRIPTION:
LITTLE CREEK TRIBUTARY 1 2.0
END DESCRIPTION:
XS GIS Cut Line= 3
      2313074.99     13785225.00      2312825.00     13785375.00
      2312425.02     13786124.97
#Sta/Elev= 30
  4704.6  564.88  4739.6  562.83  4786.2  560.76  4834.8  557.66  4851.2  556.97
  4887.3  554.29  4893.1  554.36  4951.4  550.24  4972.8  549.10  4982.5  549.32
  4988.4  548.27  4999.0  548.50  5007.5  546.59  5007.9  546.09  5012.0  546.09
  5012.4  546.59  5018.8  548.40  5026.2  548.70  5143.0  550.20  5158.0  550.32
  5188.8  549.38  5240.2  550.63  5284.1  550.20  5358.8  550.24  5388.2  550.67
  5514.3  554.08  5541.9  555.32  5596.5  556.98  5750.2  563.33  5846.1  565.86
#Mann=5,-1,0
  4704.6    0.07       0  4851.2    0.12       0  5007.5    0.05       0
  5012.4    0.12       0  5143.0   0.035       0
Bank Sta=5007.5,5012.4
Exp/Cntr=0.3,0.1

Type RM Length L Ch R = 1,965,584,584,584
BEGIN DESCRIPTION:
LITTLE CREEK TRIBUTARY 1 1.0
END DESCRIPTION:
XS GIS Cut Line= 3
      2313025.03     13784924.98      2312375.00     13785325.00
      2312125.02     13785724.96
#Sta/Elev= 30
  4236.7  569.66  4308.3  567.34  4354.1  564.35  4381.7  562.92  4412.5  561.92
  4418.4  561.39  4433.8  561.08  4439.6  560.57  4729.9  551.73  4781.3  550.70
  4897.6  548.39  4971.0  547.70  5005.2  546.85  5005.5  546.35  5009.7  546.35
  5010.1  546.85  5022.9  547.13  5036.9  547.87  5181.0  553.84  5196.3  554.02
  5202.2  554.52  5211.6  554.54  5232.8  555.23  5238.7  555.75  5254.1  556.04
  5296.5  558.02  5306.0  558.08  5318.3  558.67  5385.0  560.59  5471.6  562.47
#Mann=5,-1,0
  4236.7   0.045       0  4781.3    0.12       0  5005.2    0.05       0
  5010.1    0.12       0  5036.9   0.035       0
Bank Sta=5005.2,5010.1
Exp/Cntr=0.3,0.1

Type RM Length L Ch R = 1,381,0,0,0
BEGIN DESCRIPTION:
A19680
END DESCRIPTION:
XS GIS Cut Line= 3
      2312641.69     13784175.77      2311938.32     13785065.33
      2312062.24     13785891.45
#Sta/Elev= 30
  4062.6  568.85  4201.8  568.36  4323.1  566.46  4358.4  565.27  4465.8  559.28
  4536.3  556.40  4709.9  551.52  4842.4  547.90  4900.2  547.23  4928.5  546.57
  4964.3  546.87  4978.7  546.51  4997.0  545.01  4997.4  544.51  5001.7  544.51
  5002.0  545.01  5034.8  546.80  5070.0  547.42  5078.1  547.93  5204.7  547.80
  5368.2  549.71  5499.7  553.28  5530.0  553.32  5563.0  553.88  5609.1  554.65
  5683.3  557.26  5742.3  558.94  5752.5  559.51  5833.4  561.87  6032.0  563.92
#Mann=5,-1,0
  4062.6   0.045       0  4709.9    0.12       0  4997.0    0.05       0
  5002.0    0.12       0  5563.0   0.035       0
Bank Sta=4997,5002
Exp/Cntr=0.3,0.1

Chan Stop Cuts=-1