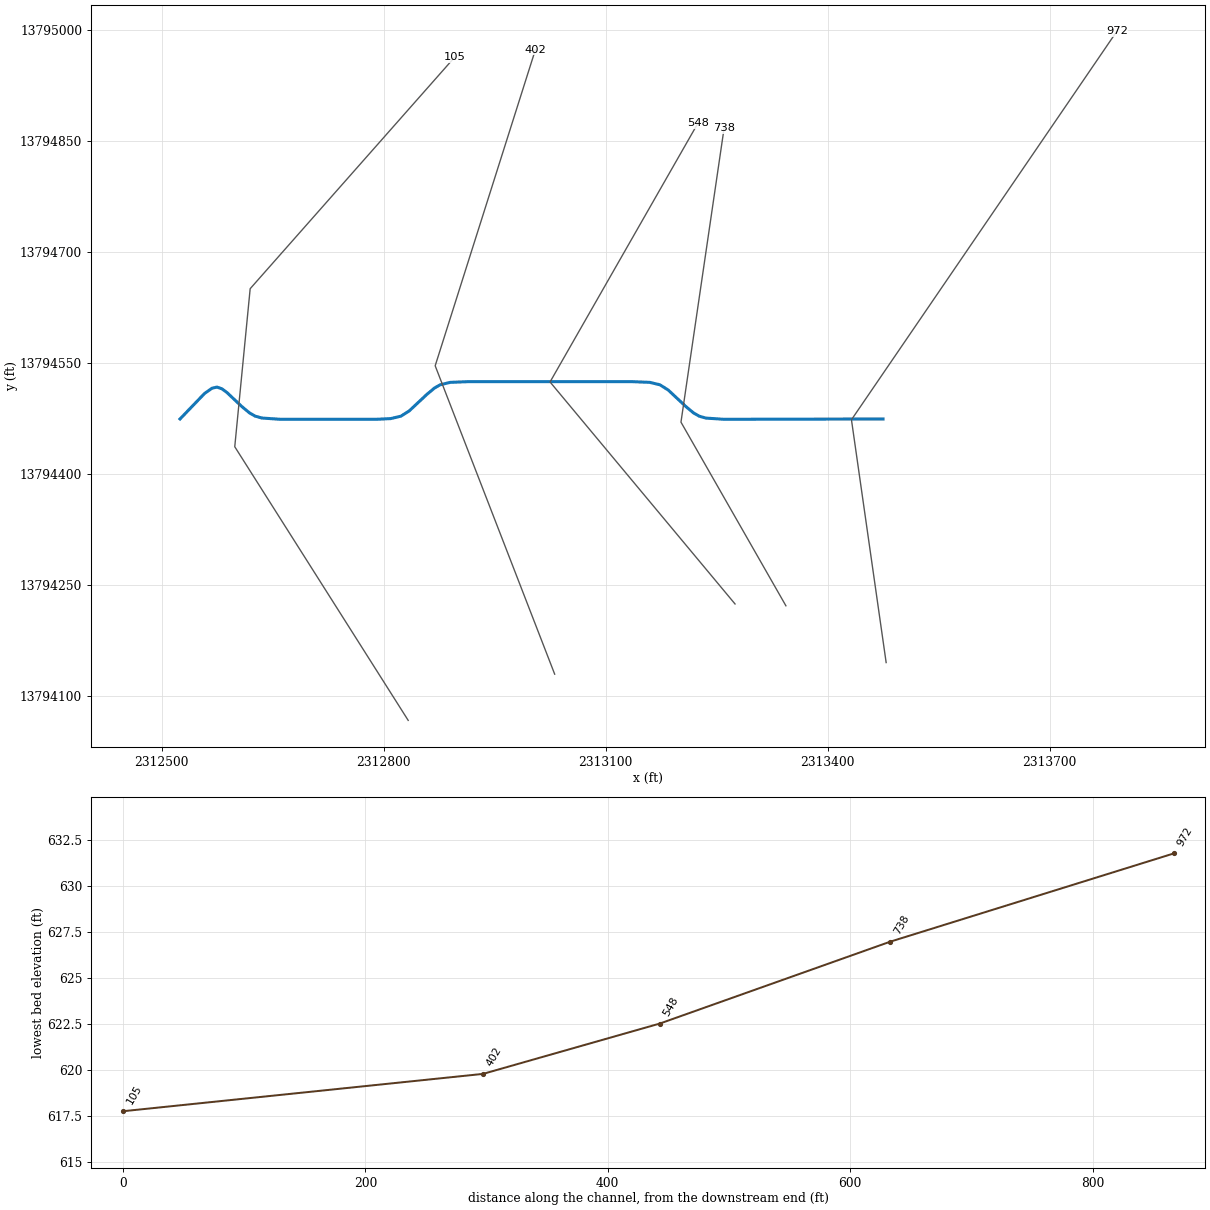
--- LITTLE CREEK TRIBUTARY 4.prj (project) ---

Proj Title=LITTLE CREEK TRIBUTARY 4 Base Level Engineering
Current Plan=p01
Default Exp/Contr=0.3,0.1
English Units
Geom File=g01
Flow File=f01
Plan File=p01
BEGIN DESCRIPTION:
LITTLE CREEK TRIBUTARY 4
END DESCRIPTION:

--- LITTLE CREEK TRIBUTARY 4.p01 (plan) ---

Plan Title=Multiple Run
Short Identifier=Multiple
Geom File=g01
Flow File=f01
Subcritical Flow
K Sum by GR= 0
Std Step Tol= 0.01
Critical Tol= 0.01
Num of Std Step Trials= 20
Max Error Tol= 0.3
Flow Tol Ratio= 0.001
Split Flow NTrial= 30
Split Flow Tol= 0.02
Split Flow Ratio= 0.02
Log Output Level= 0
Friction Slope Method= 1
Unsteady Friction Slope Method= 2
Unsteady Bridges Friction Slope Method= 1
Parabolic Critical Depth
Global Vel Dist=  1 , 1 , 1
Global Log Level= 0
CheckData=True
Encroach Param= -1, 0, 0, 0
BEGIN DESCRIPTION:
Multiple Run
END DESCRIPTION:

--- LITTLE CREEK TRIBUTARY 4.f01 (steady flow) ---

Flow Title=Multiple
Number of Profiles=7
Profile Names=10-year,25-year,50-year,1pct_min,100-year,1pct_plu,500-year
River Rch & RM= LITTLE CREEK TRI,Reach-1,972
     238     366     477     304     606    1209     961
Boundary for River Rch & Prof#=LITTLE CREEK TRI,Reach-1,1
Up Type=0
Dn Type=3
Dn Slope=0.005
Boundary for River Rch & Prof#=LITTLE CREEK TRI,Reach-1,2
Up Type=0
Dn Type=3
Dn Slope=0.005
Boundary for River Rch & Prof#=LITTLE CREEK TRI,Reach-1,3
Up Type=0
Dn Type=3
Dn Slope=0.005
Boundary for River Rch & Prof#=LITTLE CREEK TRI,Reach-1,4
Up Type=0
Dn Type=3
Dn Slope=0.005
Boundary for River Rch & Prof#=LITTLE CREEK TRI,Reach-1,5
Up Type=0
Dn Type=3
Dn Slope=0.005
Boundary for River Rch & Prof#=LITTLE CREEK TRI,Reach-1,6
Up Type=0
Dn Type=3
Dn Slope=0.005
Boundary for River Rch & Prof#=LITTLE CREEK TRI,Reach-1,7
Up Type=0
Dn Type=3
Dn Slope=0.005

--- LITTLE CREEK TRIBUTARY 4.g01 (geometry) ---

Geom Title=Existing Conditions

River Reach=LITTLE CREEK TRI,Reach-1
Reach XY= 30
      2313475.00     13794475.00      2313259.82     13794474.57
      2313235.50     13794476.22      2313226.57     13794478.78
      2313218.94     13794483.14      2313208.43     13794491.89
      2313184.65     13794514.15      2313173.43     13794521.22
      2313159.78     13794524.48      2313135.19     13794525.45
      2312914.81     13794525.45      2312890.22     13794524.48
      2312876.57     13794521.22      2312868.94     13794516.86
      2312858.43     13794508.11      2312834.65     13794485.85
      2312823.43     13794478.78      2312809.78     13794475.52
      2312790.18     13794474.57      2312659.80     13794474.61
      2312635.42     13794476.31      2312626.44     13794478.89
      2312618.78     13794483.29      2312608.19     13794492.10
      2312588.11     13794511.03      2312581.49     13794515.80
      2312574.86     13794518.09      2312568.23     13794516.56
      2312558.16     13794509.46      2312525.00     13794475.00

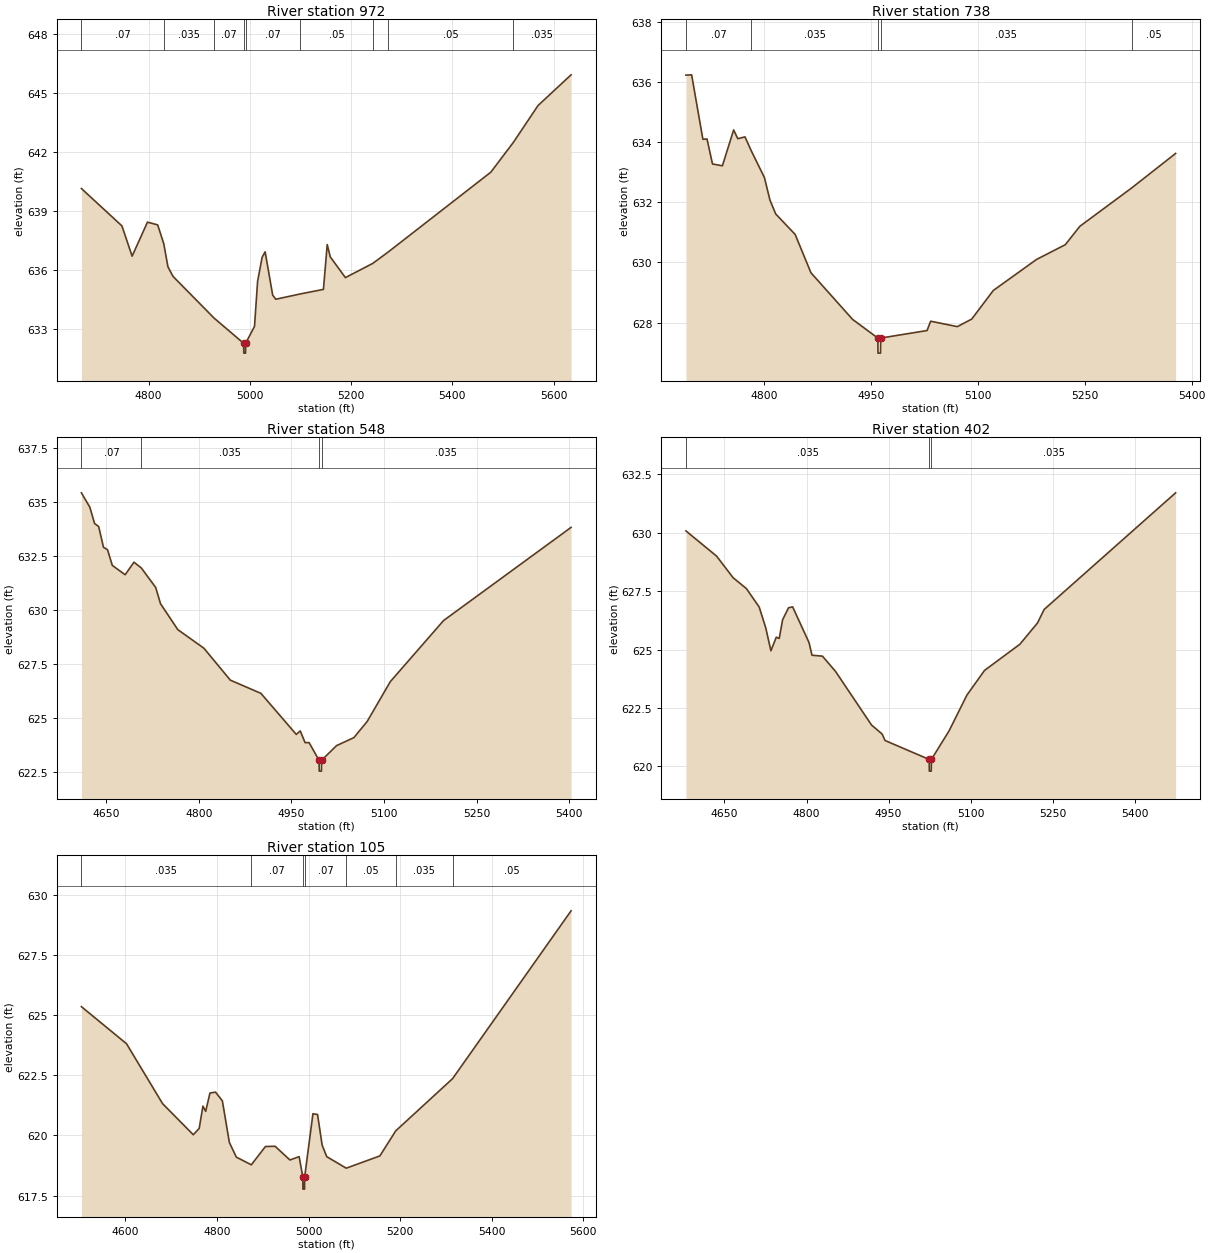
Type RM Length L Ch R = 1,972,234,234,234
BEGIN DESCRIPTION:
LITTLE CREEK TRIBUTARY 4 4.0
END DESCRIPTION:
XS GIS Cut Line= 3
      2313479.17     13794145.83      2313432.29     13794473.96
      2313790.85     13794998.81
#Sta/Elev= 30
  4667.3  640.16  4747.3  638.26  4767.5  636.72  4797.8  638.45  4818.0  638.31
  4830.0  637.35  4838.2  636.18  4848.3  635.69  4929.0  633.58  4987.7  632.29
  4988.0  631.79  4991.5  631.79  4991.7  632.29  5009.2  633.15  5015.3  635.44
  5024.2  636.66  5030.2  636.94  5045.1  634.74  5051.2  634.53  5099.8  634.80
  5145.3  635.03  5152.8  637.31  5158.9  636.68  5188.7  635.63  5242.6  636.35
  5273.2  636.93  5475.9  640.99  5520.3  642.50  5569.2  644.38  5634.4  645.94
#Mann=9,-1,0
  4667.3    0.07       0  4830.0   0.035       0  4929.0    0.07       0
  4987.7    0.05       0  4991.7    0.07       0  5099.8    0.05       0
  5242.6   0.035       0  5273.2    0.05       0  5520.3   0.035       0
Bank Sta=4987.7,4991.7
Exp/Cntr=0.3,0.1

Type RM Length L Ch R = 1,738,190,190,190
BEGIN DESCRIPTION:
A19681
END DESCRIPTION:
XS GIS Cut Line= 3
      2313343.70     13794222.58      2313201.91     13794470.72
      2313260.24     13794868.27
#Sta/Elev= 30
  4689.9  636.22  4697.9  636.23  4713.7  634.09  4719.5  634.10  4727.2  633.27
  4741.1  633.21  4756.9  634.40  4762.7  634.11  4772.8  634.17  4781.6  633.71
  4800.1  632.82  4807.9  632.07  4816.0  631.61  4843.3  630.93  4865.4  629.66
  4923.9  628.11  4959.4  627.49  4959.6  626.99  4963.1  626.99  4963.4  627.49
  5028.5  627.74  5033.5  628.05  5071.0  627.87  5091.2  628.12  5121.5  629.07
  5182.2  630.10  5222.6  630.59  5243.0  631.20  5315.6  632.47  5377.5  633.62
#Mann=5,-1,0
  4689.9    0.07       0  4781.6   0.035       0  4959.4   0.035       0
  4963.4   0.035       0  5315.6    0.05       0
Bank Sta=4959.4,4963.4
Exp/Cntr=0.3,0.1

Type RM Length L Ch R = 1,548,146,146,146
BEGIN DESCRIPTION:
LITTLE CREEK TRIBUTARY 4 3.0
END DESCRIPTION:
XS GIS Cut Line= 3
      2313274.98     13794225.02      2313025.00     13794525.00
      2313225.00     13794875.00
#Sta/Elev= 30
  4609.5  635.42  4623.1  634.76  4630.9  634.00  4637.5  633.86  4645.3  632.90
  4651.8  632.79  4659.6  632.06  4680.4  631.63  4694.7  632.21  4706.7  631.94
  4729.9  631.04  4737.7  630.29  4765.7  629.09  4808.0  628.23  4850.9  626.75
  4900.4  626.14  4957.7  624.24  4964.2  624.40  4972.0  623.86  4978.5  623.86
  4994.7  623.04  4995.0  622.54  4998.5  622.54  4998.7  623.04  5023.0  623.72
  5051.1  624.09  5072.7  624.84  5110.1  626.68  5196.5  629.51  5403.1  633.82
#Mann=4,-1,0
  4609.5    0.07       0  4706.7   0.035       0  4994.7   0.035       0
  4998.7   0.035       0
Bank Sta=4994.7,4998.7
Exp/Cntr=0.3,0.1

Type RM Length L Ch R = 1,402,297,297,297
BEGIN DESCRIPTION:
LITTLE CREEK TRIBUTARY 4 2.0
END DESCRIPTION:
XS GIS Cut Line= 3
      2313031.26     13794130.19      2312869.79     13794546.88
      2313005.20     13794973.95
#Sta/Elev= 30
  4579.6  630.08  4635.7  629.00  4665.7  628.08  4690.2  627.61  4713.5  626.82
  4725.5  625.93  4734.9  624.95  4744.7  625.53  4750.1  625.48  4756.3  626.28
  4767.1  626.79  4774.6  626.83  4804.6  625.30  4810.0  624.76  4829.1  624.72
  4852.9  624.07  4918.9  621.77  4938.1  621.39  4943.5  621.11  5024.2  620.30
  5024.4  619.80  5027.9  619.80  5028.2  620.30  5060.7  621.53  5093.0  623.05
  5125.3  624.11  5189.9  625.23  5222.1  626.14  5234.3  626.72  5474.5  631.71
#Mann=3,-1,0
  4579.6   0.035       0  5024.2   0.035       0  5028.2   0.035       0
Bank Sta=5024.2,5028.2
Exp/Cntr=0.3,0.1

Type RM Length L Ch R = 1,105,0,0,0
BEGIN DESCRIPTION:
LITTLE CREEK TRIBUTARY 4 1.0
END DESCRIPTION:
XS GIS Cut Line= 4
      2312833.32     13794067.73      2312598.96     13794437.50
      2312619.79     13794651.04      2312895.83     13794963.54
#Sta/Elev= 30
  4503.9  625.35  4602.4  623.81  4681.2  621.32  4748.2  620.03  4761.1  620.29
  4769.3  621.22  4775.3  621.00  4784.6  621.76  4796.7  621.80  4811.7  621.44
  4827.0  619.71  4842.2  619.10  4874.9  618.78  4905.8  619.54  4926.9  619.55
  4959.3  618.98  4979.4  619.12  4987.4  618.27  4987.7  617.77  4991.2  617.77
  4991.4  618.27  5009.5  620.90  5019.6  620.87  5029.6  619.60  5039.6  619.12
  5082.2  618.64  5155.7  619.15  5190.3  620.19  5314.5  622.36  5573.2  629.33
#Mann=7,-1,0
  4503.9   0.035       0  4874.9    0.07       0  4987.4    0.05       0
  4991.4    0.07       0  5082.2    0.05       0  5190.3   0.035       0
  5314.5    0.05       0
Bank Sta=4987.4,4991.4
Exp/Cntr=0.3,0.1

Chan Stop Cuts=-1