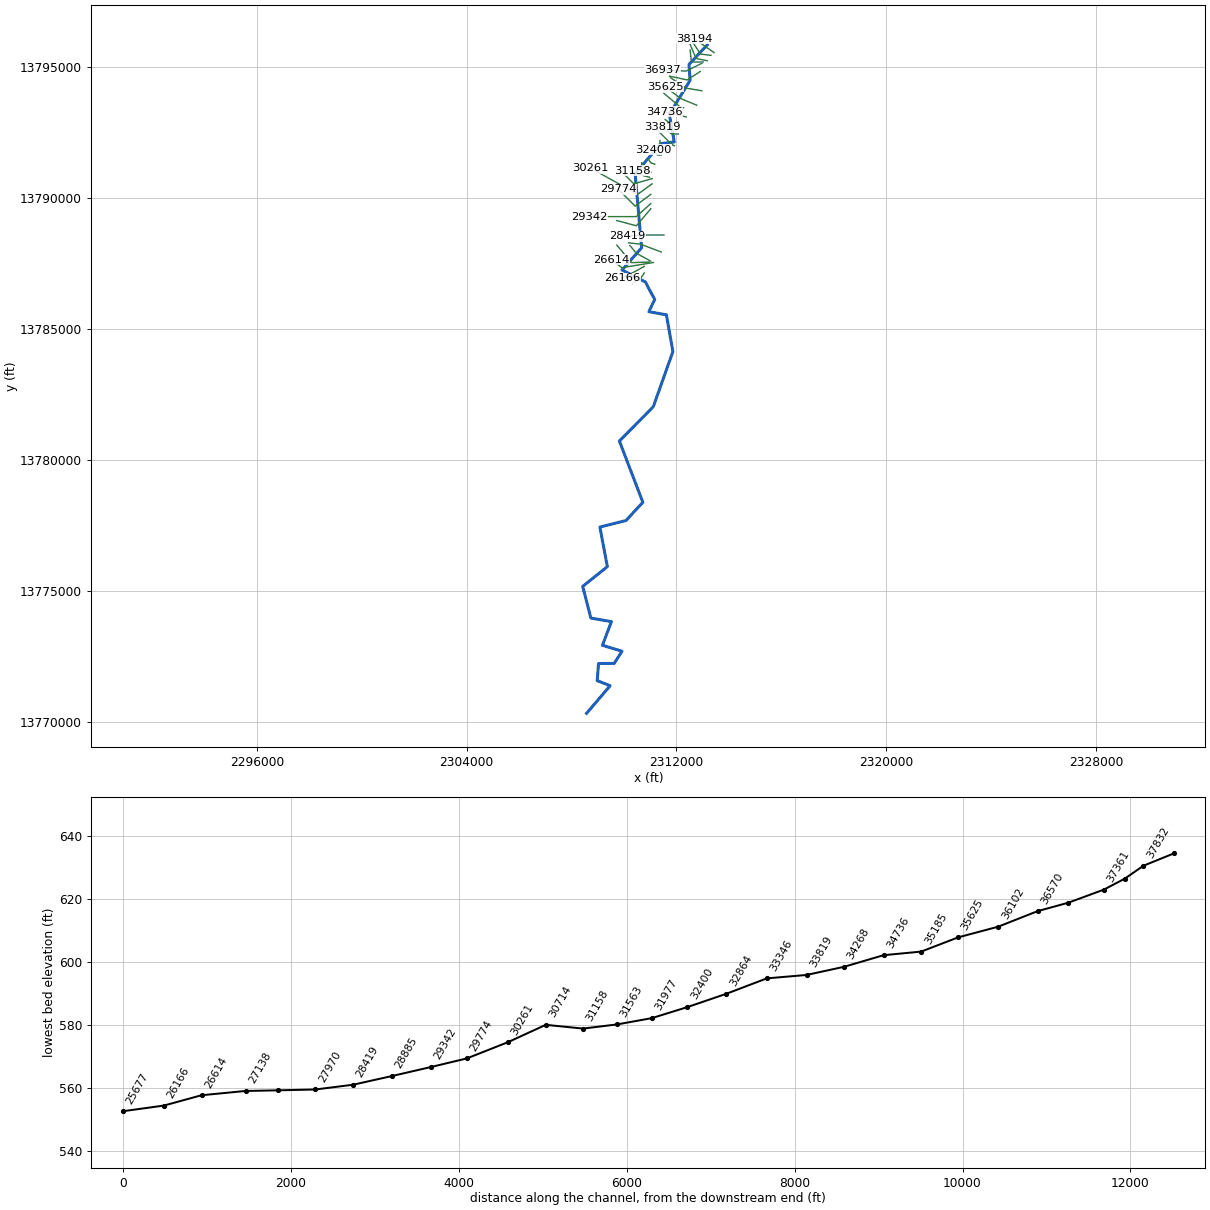
--- LITTLE CREEK.prj (project) ---

Proj Title=LITTLE CREEK Base Level Engineering
Current Plan=p01
Default Exp/Contr=0.3,0.1
English Units
Geom File=g01
Flow File=f01
Plan File=p01
Y Axis Title=Elevation
X Axis Title(PF)=Main Channel Distance
X Axis Title(XS)=Station
BEGIN DESCRIPTION:
LITTLE CREEK
END DESCRIPTION:
DSS Export Rating Curves= 0
DSS Export Rating Curve Sorted= 0
DSS Export Volume Flow Curves= 0
DXF OffsetX= 0
DXF OffsetY= 0
DXF ScaleX= 1
DXF ScaleY= 10

--- LITTLE CREEK.p01 (plan) ---

Plan Title=Multiple Run
Short Identifier=Multiple
Geom File=g01
Flow File=f01
Subcritical Flow
K Sum by GR= 0
Std Step Tol= 0.01
Critical Tol= 0.01
Num of Std Step Trials= 20
Max Error Tol= 0.3
Flow Tol Ratio= 0.001
Split Flow NTrial= 30
Split Flow Tol= 0.02
Split Flow Ratio= 0.02
Log Output Level= 0
Friction Slope Method= 1
Unsteady Friction Slope Method= 2
Unsteady Bridges Friction Slope Method= 1
Parabolic Critical Depth
Global Vel Dist=  1 , 1 , 1
Global Log Level= 0
CheckData=True
Encroach Param= -1, 0, 0, 0
BEGIN DESCRIPTION:
Multiple Run
END DESCRIPTION:

--- LITTLE CREEK.f01 (steady flow) ---

Flow Title=Multiple
Number of Profiles=7
Profile Names=10-year,25-year,50-year,1pct_min,100-year,1pct_plu,500-year
River Rch & RM= LITTLE CREEK,Reach-1,38194
     512     824    1107     722    1441    2875    2416
River Rch & RM= LITTLE CREEK,Reach-1,36102
    1137    1914    2645    1768    3528    7039    6225
River Rch & RM= LITTLE CREEK,Reach-1,28419
    1255    2115    2925    1956    3903    7787    6890
River Rch & RM= LITTLE CREEK,Reach-1,23393
    1650    2818    3933    2651    5290   10555    9492
River Rch & RM= LITTLE CREEK,Reach-1,21984
    2204    3786    5303    3582    7147   14261   12880
River Rch & RM= LITTLE CREEK,Reach-1,16027
    2188    3751    5247    3539    7060   14087   12685
River Rch & RM= LITTLE CREEK,Reach-1,14654
    2277    3898    5445    3666    7314   14594   13095
River Rch & RM= LITTLE CREEK,Reach-1,9787
    2231    3796    5280    3538    7060   14086   12526
Boundary for River Rch & Prof#=LITTLE CREEK,Reach-1,1
Up Type=0
Dn Type=3
Dn Slope=0.005
Boundary for River Rch & Prof#=LITTLE CREEK,Reach-1,2
Up Type=0
Dn Type=3
Dn Slope=0.005
Boundary for River Rch & Prof#=LITTLE CREEK,Reach-1,3
Up Type=0
Dn Type=3
Dn Slope=0.005
Boundary for River Rch & Prof#=LITTLE CREEK,Reach-1,4
Up Type=0
Dn Type=3
Dn Slope=0.005
Boundary for River Rch & Prof#=LITTLE CREEK,Reach-1,5
Up Type=0
Dn Type=3
Dn Slope=0.005
Boundary for River Rch & Prof#=LITTLE CREEK,Reach-1,6
Up Type=0
Dn Type=3
Dn Slope=0.005
Boundary for River Rch & Prof#=LITTLE CREEK,Reach-1,7
Up Type=0
Dn Type=3
Dn Slope=0.005

--- LITTLE CREEK.g01 (geometry) ---

Geom Title=Existing Conditions

River Reach=LITTLE CREEK,Reach-1
Reach XY= 30
      2313175.00     13795825.00      2312480.83     13795077.30
      2312525.00     13794475.00      2311732.60     13793178.34
      2311919.92     13792122.69      2311411.20     13792061.81
      2310425.87     13790914.67      2310674.41     13788085.62
      2309925.98     13787235.26      2310817.17     13786781.18
      2311174.81     13786109.65      2310951.12     13785648.06
      2311619.54     13785527.47      2311867.21     13784125.10
      2311119.16     13782022.71      2309826.19     13780714.50
      2310721.54     13778376.49      2310077.31     13777680.82
      2309083.13     13777431.08      2309367.16     13775921.77
      2308427.14     13775169.03      2308738.52     13773961.59
      2309521.56     13773823.78      2309180.52     13772922.02
      2309925.69     13772695.07      2309627.74     13772230.34
      2309030.52     13772227.44      2308979.97     13771572.42
      2309472.74     13771380.94      2308575.00     13770325.00

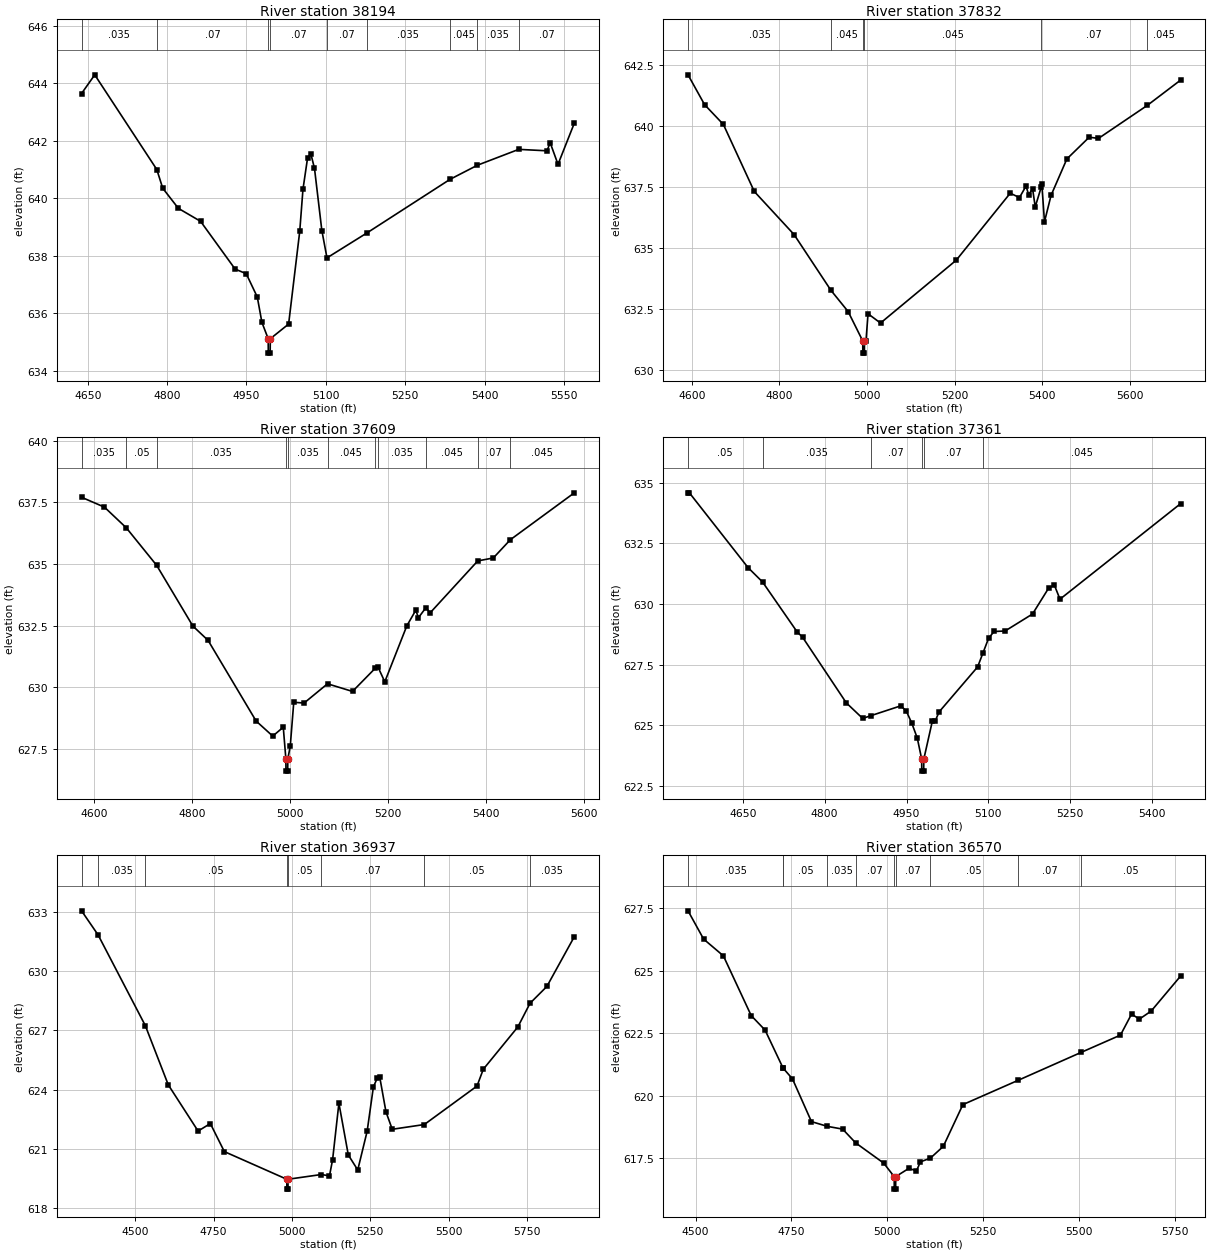
Type RM Length L Ch R = 1,38194,362,362,362
BEGIN DESCRIPTION:
A19679
END DESCRIPTION:
XS GIS Cut Line= 2
      2313435.39     13795531.77      2312672.99     13796066.45
#Sta/Elev= 30
  4638.4  643.64  4663.3  644.29  4780.6  641.00  4791.8  640.35  4821.4  639.65
  4863.3  639.20  4928.6  637.54  4949.6  637.38  4970.5  636.57  4979.2  635.69
  4991.1  635.12  4991.3  634.62  4994.8  634.62  4995.1  635.12  5029.7  635.63
  5050.7  638.85  5056.8  640.31  5065.5  641.40  5071.6  641.55  5078.6  641.04
  5092.5  638.88  5102.2  637.93  5177.2  638.79  5334.9  640.66  5386.6  641.15
  5464.6  641.70  5517.9  641.65  5524.0  641.93  5538.8  641.18  5569.6  642.61
#Mann=9,-1,0
  4638.4   0.035       0  4780.6    0.07       0  4991.1   0.035       0
  4995.1    0.07       0  5102.2    0.07       0  5177.2   0.035       0
  5334.9   0.045       0  5386.6   0.035       0  5464.6    0.07       0
Bank Sta=4991.1,4995.1
Exp/Cntr=0.3,0.1

Type RM Length L Ch R = 1,37832,223,223,223
BEGIN DESCRIPTION:
LITTLE CREEK 68.0
END DESCRIPTION:
XS GIS Cut Line= 3
      2313325.03     13795425.00      2312925.00     13795475.00
      2312524.97     13796075.04
#Sta/Elev= 30
  4591.4  642.09  4629.2  640.87  4672.1  640.06  4742.6  637.32  4833.3  635.56
  4917.4  633.28  4956.7  632.41  4990.0  631.21  4990.3  630.71  4993.8  630.71
  4994.0  631.21  4997.5  631.21  5002.1  632.32  5030.6  631.94  5203.4  634.51
  5326.6  637.25  5347.6  637.07  5362.6  637.54  5368.6  637.19  5377.6  637.43
  5383.6  636.69  5397.3  637.50  5398.7  637.62  5404.7  636.08  5419.7  637.16
  5455.8  638.65  5506.8  639.54  5527.9  639.49  5639.3  640.84  5715.7  641.88
#Mann=6,-1,0
  4591.4   0.035       0  4917.4   0.045       0  4990.0   0.045       0
  4994.0   0.045       0  5397.3    0.07       0  5639.3   0.045       0
Bank Sta=4990,4994
Exp/Cntr=0.3,0.1

Type RM Length L Ch R = 1,37609,248,248,248
BEGIN DESCRIPTION:
A19678
END DESCRIPTION:
XS GIS Cut Line= 4
      2313178.03     13795221.49      2312788.52     13795297.41
      2312729.11     13795360.12      2312524.89     13795841.03
#Sta/Elev= 30
  4574.1  637.70  4620.8  637.30  4665.5  636.46  4727.4  634.94  4801.3  632.48
  4832.3  631.90  4930.4  628.63  4964.3  628.02  4985.8  628.38  4991.1  627.10
  4991.3  626.60  4994.8  626.60  4995.1  627.10  5000.0  627.60  5007.2  629.39
  5028.3  629.36  5076.1  630.14  5127.1  629.83  5173.0  630.76  5178.6  630.84
  5193.0  630.22  5238.0  632.49  5256.2  633.12  5261.7  632.82  5277.1  633.23
  5285.3  633.01  5382.7  635.12  5414.5  635.24  5449.3  635.98  5579.8  637.88
#Mann=11,-1,0
  4574.1   0.035       0  4665.5    0.05       0  4727.4   0.035       0
  4991.1   0.035       0  4995.1   0.035       0  5076.1   0.045       0
  5173.0    0.07       0  5178.6   0.035       0  5277.1   0.045       0
  5382.7    0.07       0  5449.3   0.045       0
Bank Sta=4991.1,4995.1
Exp/Cntr=0.3,0.1

Type RM Length L Ch R = 1,37361,424,424,424
BEGIN DESCRIPTION:
LITTLE CREEK 67.0
END DESCRIPTION:
XS GIS Cut Line= 3
      2313024.97     13795175.00      2312575.00     13795175.00
      2312525.00     13795624.96
#Sta/Elev= 30
  4549.7  634.58  4552.2  634.58  4659.7  631.50  4686.2  630.91  4749.7  628.85
  4759.7  628.63  4839.7  625.93  4869.7  625.29  4884.2  625.40  4939.7  625.81
  4949.7  625.59  4959.7  625.09  4969.7  624.48  4977.7  623.62  4977.9  623.12
  4981.4  623.12  4981.7  623.62  4997.2  625.17  5002.2  625.17  5009.7  625.56
  5080.2  627.41  5090.1  627.99  5100.3  628.59  5110.3  628.87  5130.5  628.89
  5180.8  629.59  5211.0  630.68  5221.0  630.77  5231.1  630.20  5452.4  634.14
#Mann=6,-1,0
  4549.7    0.05       0  4686.2   0.035       0  4884.2    0.07       0
  4977.7    0.07       0  4981.7    0.07       0  5090.1   0.045       0
Bank Sta=4977.7,4981.7
Exp/Cntr=0.3,0.1

Type RM Length L Ch R = 1,36937,367,367,367
BEGIN DESCRIPTION:
LITTLE CREEK 66.0
END DESCRIPTION:
XS GIS Cut Line= 3
      2312975.02     13795125.01      2312375.00     13794825.00
      2311475.03     13794875.00
#Sta/Elev= 30
  4329.0  633.05  4381.8  631.83  4532.4  627.24  4605.7  624.24  4700.8  621.90
  4739.9  622.28  4784.6  620.86  4983.9  619.46  4984.1  618.96  4987.6  618.96
  4987.9  619.46  5094.3  619.70  5120.0  619.63  5130.0  620.45  5150.1  623.31
  5180.1  620.69  5210.2  619.93  5240.2  621.89  5260.2  624.14  5272.8  624.59
  5280.3  624.64  5300.3  622.87  5320.3  621.99  5422.6  622.23  5590.8  624.18
  5610.8  625.03  5721.0  627.17  5759.9  628.37  5813.6  629.22  5901.2  631.74
#Mann=8,-1,0
  4329.0    0.05       0  4381.8   0.035       0  4532.4    0.05       0
  4983.9    0.05       0  4987.9    0.05       0  5094.3    0.07       0
  5422.6    0.05       0  5759.9   0.035       0
Bank Sta=4983.9,4987.9
Exp/Cntr=0.3,0.1

Type RM Length L Ch R = 1,36570,468,468,468
BEGIN DESCRIPTION:
A19677
END DESCRIPTION:
XS GIS Cut Line= 3
      2312913.97     13794812.25      2312412.25     13794488.77
      2311739.48     13794633.88
#Sta/Elev= 30
  4480.2  627.40  4520.9  626.27  4572.4  625.60  4645.0  623.21  4681.2  622.63
  4727.8  621.12  4728.7  621.10  4752.6  620.68  4802.1  618.97  4843.7  618.78
  4883.5  618.67  4917.4  618.12  4990.6  617.31  5017.9  616.77  5018.2  616.27
  5021.7  616.27  5021.9  616.77  5056.2  617.10  5076.0  617.00  5086.3  617.36
  5112.4  617.51  5146.0  617.98  5197.1  619.65  5340.9  620.62  5505.7  621.74
  5608.1  622.43  5637.0  623.27  5657.5  623.07  5688.1  623.39  5765.4  624.80
#Mann=10,-1,0
  4480.2   0.035       0  4727.8    0.07       0  4728.7    0.05       0
  4843.7   0.035       0  4917.4    0.07       0  5017.9    0.07       0
  5021.9    0.07       0  5112.4    0.05       0  5340.9    0.07       0
  5505.7    0.05       0
Bank Sta=5017.9,5021.9
Exp/Cntr=0.3,0.1

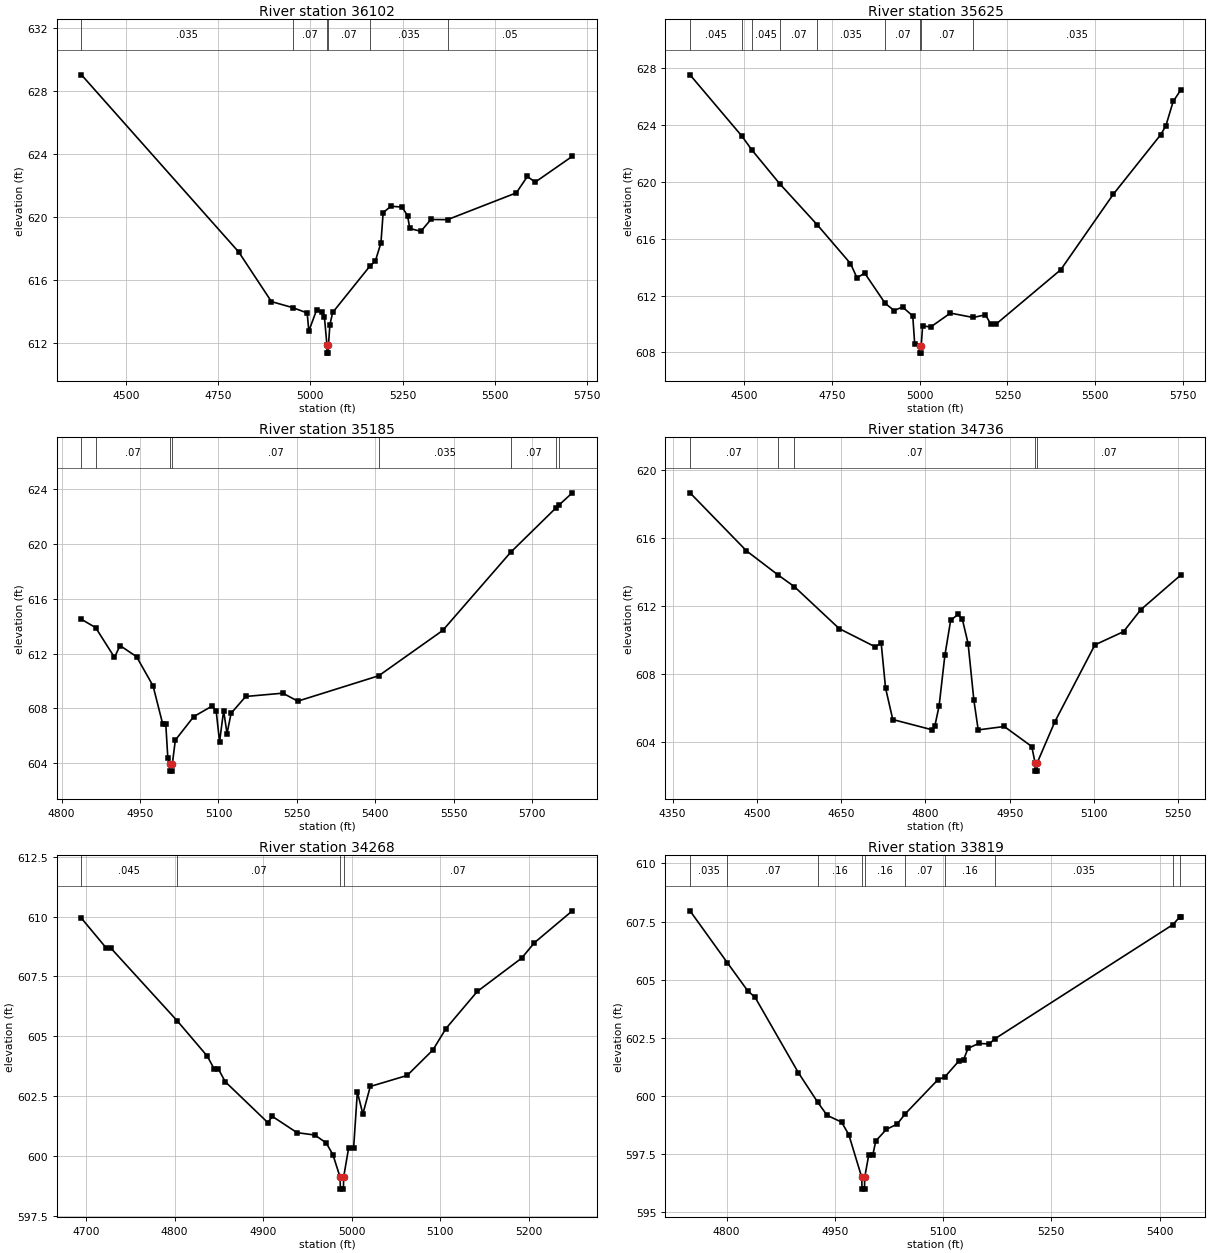
Type RM Length L Ch R = 1,36102,477,477,477
BEGIN DESCRIPTION:
LITTLE CREEK 65.0
END DESCRIPTION:
XS GIS Cut Line= 3
      2312975.03     13794074.99      2312375.00     13794175.00
      2311775.02     13794574.99
#Sta/Elev= 30
  4380.1  629.00  4805.9  617.76  4894.6  614.61  4951.8  614.23  4991.4  613.89
  4995.9  612.74  5017.0  614.08  5032.0  613.92  5038.0  613.66  5045.0  611.84
  5045.2  611.34  5048.7  611.34  5049.0  611.84  5053.0  613.15  5060.5  613.92
  5161.2  616.86  5176.2  617.19  5191.2  618.34  5197.2  620.26  5218.3  620.66
  5248.3  620.61  5263.3  620.06  5269.3  619.25  5299.4  619.07  5326.4  619.82
  5371.5  619.81  5557.8  621.51  5587.8  622.55  5608.9  622.19  5709.5  623.83
#Mann=6,-1,0
  4380.1   0.035       0  4951.8    0.07       0  5045.0    0.07       0
  5049.0    0.07       0  5161.2   0.035       0  5371.5    0.05       0
Bank Sta=5045,5049
Exp/Cntr=0.3,0.1

Type RM Length L Ch R = 1,35625,440,440,440
BEGIN DESCRIPTION:
LITTLE CREEK 64.0
END DESCRIPTION:
XS GIS Cut Line= 3
      2312774.97     13793525.01      2312175.00     13793775.00
      2311574.98     13794225.02
#Sta/Elev= 30
  4344.8  627.55  4492.2  623.25  4521.8  622.24  4600.2  619.89  4708.3  616.97
  4802.5  614.26  4820.9  613.26  4843.1  613.58  4901.6  611.45  4927.1  610.95
  4950.9  611.20  4980.1  610.57  4985.6  608.61  5000.1  608.45  5000.3  607.95
  5003.8  607.95  5004.1  608.45  5008.3  609.87  5031.2  609.79  5087.5  610.77
  5152.4  610.46  5187.5  610.65  5202.1  610.01  5216.6  609.97  5402.1  613.82
  5552.1  619.14  5687.5  623.34  5702.1  623.97  5722.9  625.68  5744.8  626.49
#Mann=9,-1,0
  4344.8   0.045       0  4492.2    0.07       0  4521.8   0.045       0
  4600.2    0.07       0  4708.3   0.035       0  4901.6    0.07       0
  5000.1    0.07       0  5004.1    0.07       0  5152.4   0.035       0
Bank Sta=5000.1,5004.1
Exp/Cntr=0.3,0.1

Type RM Length L Ch R = 1,35185,449,449,449
BEGIN DESCRIPTION:
LITTLE CREEK 63.0
END DESCRIPTION:
XS GIS Cut Line= 3
      2312274.97     13793425.01      2312125.00     13793475.00
      2311525.01     13793974.99
#Sta/Elev= 30
  4837.9  614.49  4865.0  613.89  4901.1  611.72  4911.7  612.58  4943.3  611.77
  4974.9  609.64  4993.3  606.87  4999.2  606.87  5003.1  604.42  5007.7  603.93
  5007.9  603.43  5011.4  603.43  5011.7  603.93  5017.5  605.69  5052.6  607.40
  5087.8  608.17  5095.6  607.83  5102.1  605.57  5109.9  607.83  5116.4  606.17
  5124.2  607.65  5152.2  608.87  5223.1  609.11  5251.8  608.53  5406.7  610.38
  5529.0  613.68  5658.9  619.37  5746.5  622.64  5751.8  622.83  5777.0  623.71
#Mann=8,-1,0
  4837.9   0.035       0  4865.0    0.07       0  5007.7    0.07       0
  5011.7    0.07       0  5406.7   0.035       0  5658.9    0.07       0
  5746.5   0.035       0  5751.8    0.07       0
Bank Sta=5007.7,5011.7
Exp/Cntr=0.3,0.1

Type RM Length L Ch R = 1,34736,468,468,468
BEGIN DESCRIPTION:
LITTLE CREEK 62.0
END DESCRIPTION:
XS GIS Cut Line= 3
      2312374.99     13793075.00      2311775.00     13793225.00
      2311525.00     13793275.00
#Sta/Elev= 30
  4381.1  618.68  4481.6  615.26  4537.4  613.85  4566.8  613.15  4646.5  610.68
  4710.9  609.60  4721.2  609.84  4729.0  607.18  4741.9  605.32  4811.4  604.72
  4816.6  604.92  4824.3  606.12  4834.6  609.11  4844.9  611.17  4857.8  611.51
  4865.6  611.24  4875.9  609.80  4886.2  606.45  4893.9  604.71  4940.3  604.91
  4989.2  603.73  4995.0  602.78  4995.2  602.28  4998.7  602.28  4999.0  602.78
  5030.1  605.18  5101.5  609.72  5152.5  610.50  5183.1  611.79  5254.5  613.84
#Mann=5,-1,0
  4381.1    0.07       0  4537.4   0.035       0  4566.8    0.07       0
  4995.0    0.07       0  4999.0    0.07       0
Bank Sta=4995,4999
Exp/Cntr=0.3,0.1

Type RM Length L Ch R = 1,34268,449,449,449
BEGIN DESCRIPTION:
LITTLE CREEK 61.0
END DESCRIPTION:
XS GIS Cut Line= 3
      2312075.05     13792875.01      2311775.00     13792825.00
      2311574.99     13792975.01
#Sta/Elev= 30
  4694.8  609.93  4722.7  608.69  4727.8  608.69  4803.0  605.64  4836.8  604.17
  4844.4  603.65  4849.4  603.63  4857.1  603.10  4905.2  601.39  4910.3  601.65
  4938.2  600.97  4958.4  600.87  4971.1  600.54  4978.7  600.05  4986.8  599.11
  4987.1  598.61  4990.6  598.61  4990.8  599.11  4996.5  600.34  5002.1  600.34
  5006.3  602.67  5012.5  601.75  5020.9  602.90  5062.5  603.36  5091.7  604.43
  5106.3  605.32  5141.7  606.87  5191.7  608.26  5206.3  608.91  5249.0  610.24
#Mann=4,-1,0
  4694.8   0.045       0  4803.0    0.07       0  4986.8    0.07       0
  4990.8    0.07       0
Bank Sta=4986.8,4990.8
Exp/Cntr=0.3,0.1

Type RM Length L Ch R = 1,33819,473,473,473
BEGIN DESCRIPTION:
LITTLE CREEK 60.0
END DESCRIPTION:
XS GIS Cut Line= 3
      2312075.02     13792425.00      2311825.00     13792425.00
      2311475.03     13792674.98
#Sta/Elev= 30
  4749.4  607.96  4801.1  605.73  4829.4  604.52  4839.4  604.25  4899.4  601.01
  4926.4  599.73  4939.4  599.17  4959.4  598.88  4969.4  598.34  4987.4  596.50
  4987.7  596.00  4991.2  596.00  4991.4  596.50  4996.9  597.45  5002.5  597.45
  5006.8  598.07  5021.5  598.57  5036.3  598.79  5047.7  599.24  5092.8  600.70
  5102.4  600.82  5122.3  601.52  5128.5  601.57  5134.6  602.05  5149.3  602.26
  5164.1  602.24  5171.3  602.45  5418.6  607.37  5427.7  607.69  5429.5  607.69
#Mann=10,-1,0
  4749.4   0.035       0  4801.1    0.07       0  4926.4    0.16       0
  4987.4    0.07       0  4991.4    0.16       0  5047.7    0.07       0
  5102.4    0.16       0  5171.3   0.035       0  5418.6   0.045       0
  5427.7    0.07       0
Bank Sta=4987.4,4991.4
Exp/Cntr=0.3,0.1

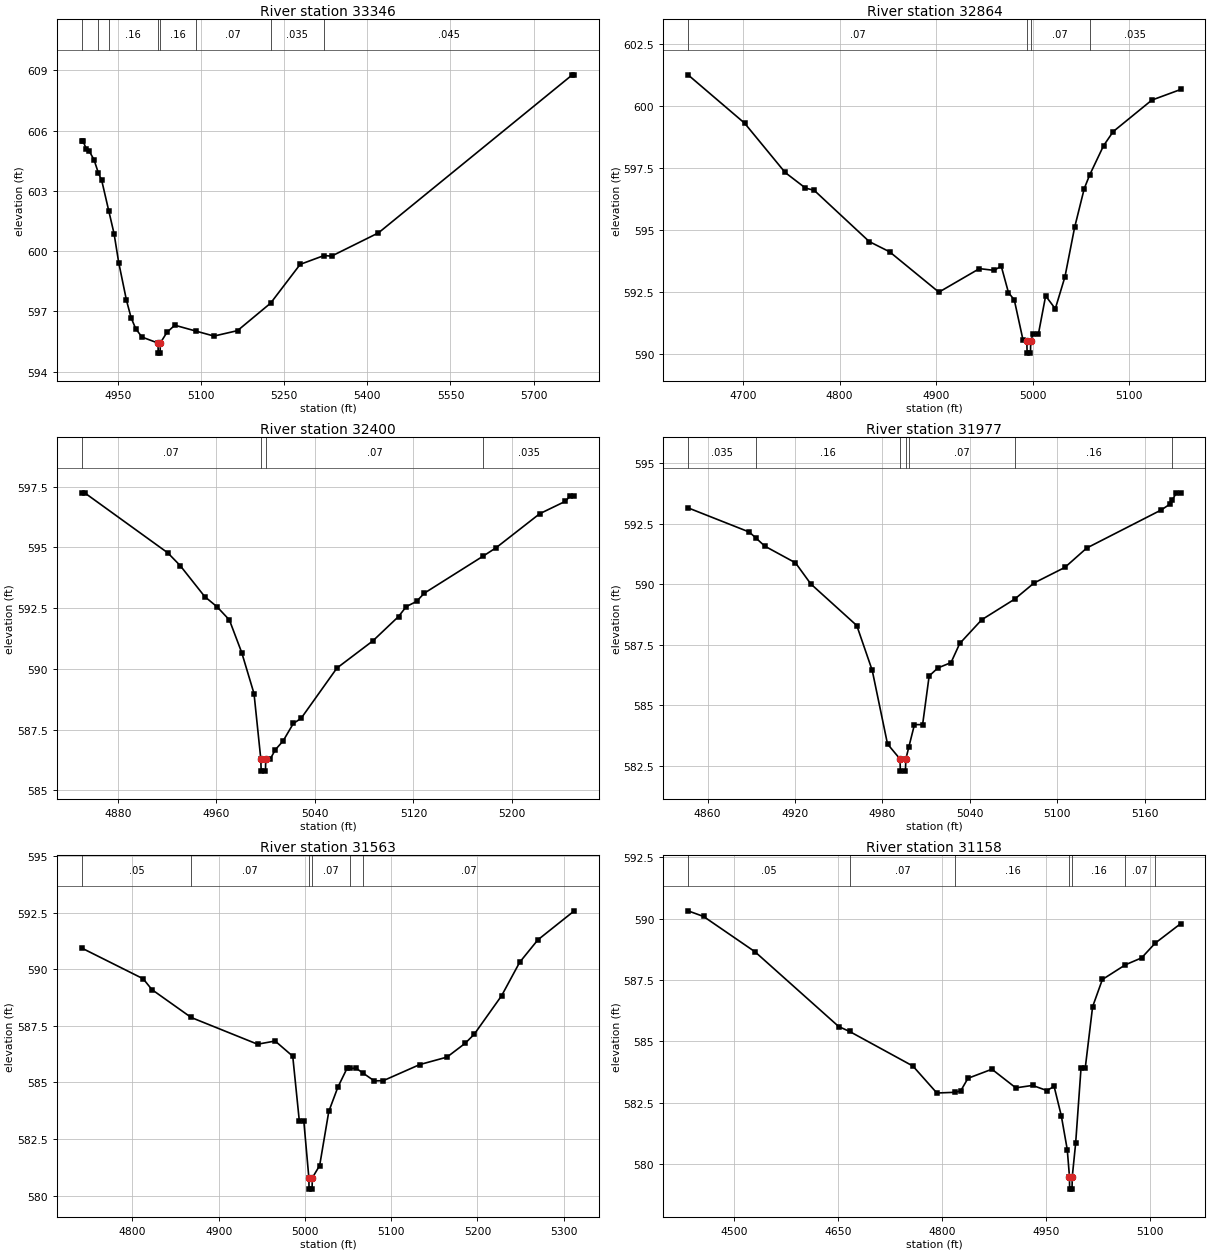
Type RM Length L Ch R = 1,33346,482,482,482
BEGIN DESCRIPTION:
LITTLE CREEK 59.0
END DESCRIPTION:
XS GIS Cut Line= 3
      2311925.04     13791974.98      2311825.00     13792025.00
      2311274.98     13792575.02
#Sta/Elev= 30
  4883.9  605.46  4886.7  605.46  4892.3  605.11  4897.9  604.97  4906.3  604.56
  4914.3  603.89  4920.3  603.52  4932.9  602.02  4942.6  600.87  4951.0  599.43
  4965.0  597.55  4973.4  596.68  4981.8  596.13  4993.0  595.72  5022.0  595.42
  5022.3  594.92  5025.8  594.92  5026.0  595.42  5038.2  595.96  5052.3  596.31
  5090.1  596.02  5123.0  595.77  5165.5  596.04  5225.3  597.41  5278.6  599.34
  5321.7  599.78  5335.2  599.75  5420.0  600.91  5770.0  608.78  5773.6  608.78
#Mann=8,-1,0
  4883.9   0.045       0  4914.3    0.07       0  4932.9    0.16       0
  5022.0    0.07       0  5026.0    0.16       0  5090.1    0.07       0
  5225.3   0.035       0  5321.7   0.045       0
Bank Sta=5022,5026
Exp/Cntr=0.3,0.1

Type RM Length L Ch R = 1,32864,464,464,464
BEGIN DESCRIPTION:
LITTLE CREEK 58.0
END DESCRIPTION:
XS GIS Cut Line= 3
      2311674.98     13791825.01      2311375.00     13792025.00
      2311375.00     13792174.97
#Sta/Elev= 30
  4642.9  601.25  4701.5  599.30  4743.5  597.31  4764.6  596.68  4773.6  596.59
  4830.7  594.52  4851.7  594.11  4902.8  592.48  4944.8  593.43  4959.9  593.36
  4967.4  593.53  4974.9  592.46  4980.9  592.17  4989.9  590.56  4993.9  590.52
  4994.2  590.02  4997.7  590.02  4997.9  590.52  5000.4  590.79  5005.9  590.79
  5013.4  592.33  5023.4  591.81  5033.4  593.10  5043.4  595.09  5053.4  596.66
  5058.9  597.20  5073.4  598.39  5083.4  598.96  5123.4  600.23  5153.4  600.66
#Mann=4,-1,0
  4642.9    0.07       0  4993.9    0.07       0  4997.9    0.07       0
  5058.9   0.035       0
Bank Sta=4993.9,4997.9
Exp/Cntr=0.3,0.1

Type RM Length L Ch R = 1,32400,423,423,423
BEGIN DESCRIPTION:
LITTLE CREEK 57.0
END DESCRIPTION:
XS GIS Cut Line= 3
      2311425.04     13791625.00      2311275.00     13791625.00
      2311125.02     13791824.97
#Sta/Elev= 30
  4850.6  597.24  4853.1  597.24  4920.6  594.77  4930.6  594.25  4950.6  592.97
  4960.6  592.55  4970.6  592.01  4980.6  590.67  4990.6  588.98  4996.1  586.29
  4996.4  585.79  4999.9  585.79  5000.1  586.29  5003.8  586.29  5007.9  586.67
  5014.2  587.03  5022.5  587.75  5028.8  587.96  5057.9  590.03  5087.1  591.15
  5107.9  592.15  5114.2  592.56  5122.5  592.77  5128.8  593.11  5176.4  594.63
  5187.1  594.98  5222.5  596.38  5243.3  596.89  5247.5  597.13  5250.6  597.13
#Mann=4,-1,0
  4850.6    0.07       0  4996.1    0.07       0  5000.1    0.07       0
  5176.4   0.035       0
Bank Sta=4996.1,5000.1
Exp/Cntr=0.3,0.1

Type RM Length L Ch R = 1,31977,414,414,414
BEGIN DESCRIPTION:
LITTLE CREEK 56.0
END DESCRIPTION:
XS GIS Cut Line= 3
      2311174.98     13791275.01      2311025.00     13791325.00
      2310924.99     13791475.02
#Sta/Elev= 30
  4846.5  593.16  4888.6  592.16  4893.4  591.90  4899.2  591.58  4920.3  590.89
  4930.8  590.02  4962.4  588.30  4973.0  586.45  4983.5  583.41  4992.1  582.79
  4992.3  582.29  4995.8  582.29  4996.1  582.79  4998.2  583.30  5002.0  584.21
  5007.6  584.21  5012.1  586.22  5018.1  586.55  5027.1  586.77  5033.1  587.56
  5048.2  588.54  5070.8  589.39  5084.2  590.06  5105.3  590.70  5120.3  591.50
  5171.4  593.07  5177.4  593.31  5179.0  593.48  5181.9  593.78  5184.9  593.78
#Mann=7,-1,0
  4846.5   0.035       0  4893.4    0.16       0  4992.1    0.07       0
  4996.1    0.16       0  4998.2    0.07       0  5070.8    0.16       0
  5179.0    0.07       0
Bank Sta=4992.1,4996.1
Exp/Cntr=0.3,0.1

Type RM Length L Ch R = 1,31563,405,405,405
BEGIN DESCRIPTION:
LITTLE CREEK 55.0
END DESCRIPTION:
XS GIS Cut Line= 3
      2311025.00     13790975.00      2310775.00     13791025.00
      2310674.99     13791325.02
#Sta/Elev= 30
  4741.1  590.94  4812.5  589.58  4822.7  589.10  4868.2  587.87  4945.1  586.69
  4965.5  586.83  4985.9  586.16  4993.5  583.31  4998.7  583.31  5004.6  580.79
  5004.8  580.29  5008.3  580.29  5008.6  580.79  5017.1  581.33  5027.7  583.72
  5038.2  584.79  5048.8  585.62  5052.0  585.62  5059.3  585.63  5066.8  585.43
  5080.4  585.07  5090.9  585.08  5133.1  585.79  5164.7  586.12  5185.8  586.73
  5196.3  587.13  5228.0  588.83  5249.0  590.31  5270.1  591.30  5312.3  592.58
#Mann=6,-1,0
  4741.1    0.05       0  4868.2    0.07       0  5004.6    0.07       0
  5008.6    0.07       0  5052.0    0.16       0  5066.8    0.07       0
Bank Sta=5004.6,5008.6
Exp/Cntr=0.3,0.1

Type RM Length L Ch R = 1,31158,444,444,444
BEGIN DESCRIPTION:
LITTLE CREEK 54.0
END DESCRIPTION:
XS GIS Cut Line= 3
      2310974.97     13790775.01      2310425.00     13790925.00
      2310324.98     13791025.02
#Sta/Elev= 30
  4433.6  590.32  4456.0  590.09  4530.3  588.65  4651.2  585.60  4666.9  585.40
  4758.3  583.99  4792.9  582.89  4819.8  582.92  4827.4  582.98  4837.8  583.49
  4872.4  583.86  4906.9  583.10  4931.1  583.20  4951.8  582.99  4962.2  583.16
  4972.6  581.96  4981.2  580.58  4984.4  579.47  4984.6  578.97  4988.1  578.97
  4988.4  579.47  4993.3  580.84  5001.1  583.92  5007.2  583.92  5017.8  586.41
  5031.9  587.52  5065.2  588.12  5088.5  588.40  5108.1  589.00  5145.1  589.80
#Mann=7,-1,0
  4433.6    0.05       0  4666.9    0.07       0  4819.8    0.16       0
  4984.4    0.07       0  4988.4    0.16       0  5065.2    0.07       0
  5108.1   0.035       0
Bank Sta=4984.4,4988.4
Exp/Cntr=0.3,0.1

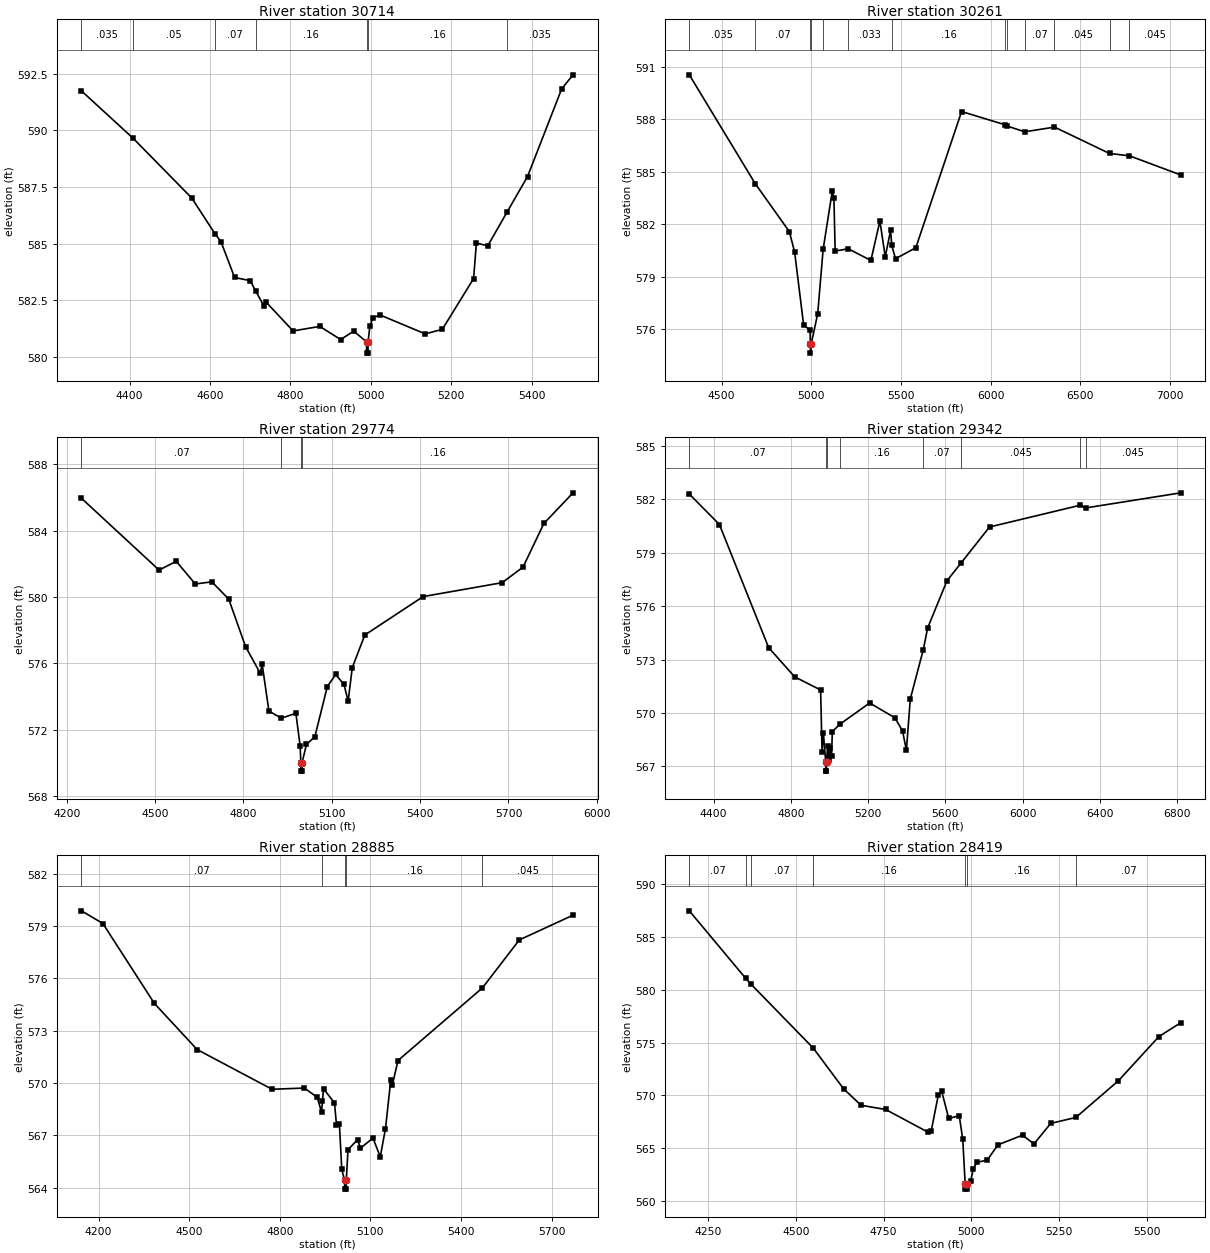
Type RM Length L Ch R = 1,30714,453,453,453
BEGIN DESCRIPTION:
LITTLE CREEK 53.0
END DESCRIPTION:
XS GIS Cut Line= 3
      2311074.96     13790724.99      2310375.00     13790525.00
      2310025.03     13790874.97
#Sta/Elev= 30
  4280.2  591.74  4409.1  589.64  4554.5  587.01  4612.0  585.44  4627.3  585.08
  4661.1  583.50  4700.1  583.36  4713.6  582.90  4733.9  582.25  4739.1  582.42
  4806.7  581.14  4873.0  581.34  4925.0  580.76  4957.5  581.13  4989.3  580.66
  4989.5  580.16  4993.0  580.16  4993.3  580.66  4997.8  581.38  5005.6  581.72
  5022.3  581.85  5135.4  581.01  5177.9  581.21  5255.7  583.45  5262.7  585.02
  5291.0  584.90  5339.7  586.41  5390.0  587.96  5474.9  591.83  5503.1  592.45
#Mann=7,-1,0
  4280.2   0.035       0  4409.1    0.05       0  4612.0    0.07       0
  4713.6    0.16       0  4989.3    0.07       0  4993.3    0.16       0
  5339.7   0.035       0
Bank Sta=4989.3,4993.3
Exp/Cntr=0.3,0.1

Type RM Length L Ch R = 1,30261,487,487,487
BEGIN DESCRIPTION:
LITTLE CREEK 52.0
END DESCRIPTION:
XS GIS Cut Line= 3
      2311074.97     13790524.98      2310525.00     13790125.00
      2308724.97     13791125.02
#Sta/Elev= 30
  4320.0  590.54  4687.0  584.32  4877.5  581.57  4906.9  580.40  4957.1  576.23
  4992.7  575.93  4994.9  575.12  4995.2  574.62  4998.9  575.12  5035.5  576.88
  5065.7  580.55  5116.7  583.89  5125.9  583.48  5132.7  580.46  5205.9  580.59
  5331.8  579.92  5382.1  582.18  5411.9  580.13  5441.6  581.64  5448.3  580.78
  5469.1  580.02  5582.3  580.65  5837.4  588.44  6080.5  587.68  6088.6  587.62
  6189.0  587.28  6355.1  587.55  6662.0  586.04  6772.2  585.91  7059.2  584.81
#Mann=13,-1,0
  4320.0   0.035       0  4687.0    0.07       0  4994.9    0.07       0
  4998.9    0.07       0  5065.7    0.16       0  5205.9   0.033       0
  5448.3    0.16       0  6080.5    0.07       0  6088.6    0.16       0
  6189.0    0.07       0  6355.1   0.045       0  6662.0    0.07       0
  6772.2   0.045       0
Bank Sta=4994.9,4998.9
Exp/Cntr=0.3,0.1

Type RM Length L Ch R = 1,29774,432,432,432
BEGIN DESCRIPTION:
LITTLE CREEK 51.0
END DESCRIPTION:
XS GIS Cut Line= 3
      2311024.96     13790124.97      2310425.00     13789675.00
      2309774.99     13790325.01
#Sta/Elev= 30
  4250.0  585.95  4513.5  581.62  4571.8  582.15  4636.4  580.78  4692.7  580.91
  4750.0  579.87  4807.2  577.00  4857.2  575.39  4863.5  575.95  4886.4  573.12
  4928.5  572.68  4978.1  572.98  4992.7  570.98  4994.8  569.99  4995.0  569.49
  4998.6  569.49  4998.9  569.99  5014.1  571.11  5042.4  571.56  5084.8  574.59
  5113.1  575.32  5141.4  574.72  5155.5  573.72  5169.7  575.74  5212.1  577.70
  5410.1  580.02  5678.8  580.86  5749.5  581.80  5820.2  584.43  5919.2  586.28
#Mann=4,-1,0
  4250.0    0.07       0  4928.5    0.16       0  4994.8    0.07       0
  4998.9    0.16       0
Bank Sta=4994.8,4998.9
Exp/Cntr=0.3,0.1

Type RM Length L Ch R = 1,29342,457,457,457
BEGIN DESCRIPTION:
LITTLE CREEK 50.0
END DESCRIPTION:
XS GIS Cut Line= 3
      2311024.98     13789774.99      2310475.00     13789275.00
      2308674.98     13789275.00
#Sta/Elev= 30
  4274.8  582.30  4430.5  580.59  4685.3  573.67  4819.8  572.03  4954.2  571.29
  4961.7  567.81  4968.4  568.89  4980.6  567.23  4980.8  566.73  4984.4  566.73
  4984.7  567.23  4990.0  568.15  4996.8  567.38  5004.2  568.04  5011.0  567.60
  5014.7  568.95  5053.2  569.36  5208.1  570.56  5338.1  569.73  5378.1  568.99
  5398.1  567.90  5418.1  570.78  5485.1  573.54  5508.1  574.78  5608.1  577.43
  5682.0  578.44  5828.1  580.45  6296.2  581.67  6324.9  581.52  6818.1  582.37
#Mann=8,-1,0
  4274.8    0.07       0  4980.6    0.07       0  4984.7    0.07       0
  5053.2    0.16       0  5485.1    0.07       0  5682.0   0.045       0
  6296.2   0.035       0  6324.9   0.045       0
Bank Sta=4980.6,4984.7
Exp/Cntr=0.3,0.1

Type RM Length L Ch R = 1,28885,466,466,466
BEGIN DESCRIPTION:
LITTLE CREEK 49.0
END DESCRIPTION:
XS GIS Cut Line= 3
      2311025.02     13789575.02      2310475.00     13788925.00
      2309725.01     13789125.00
#Sta/Elev= 30
  4143.3  579.88  4214.2  579.15  4384.5  574.57  4526.2  571.92  4774.5  569.64
  4881.1  569.71  4923.9  569.18  4938.2  568.33  4941.3  568.96  4944.8  569.67
  4981.1  568.86  4987.7  567.61  4997.4  567.65  5005.2  565.05  5014.6  564.41
  5015.1  563.91  5019.8  563.91  5020.2  564.41  5025.8  566.17  5057.5  566.75
  5067.2  566.26  5108.6  566.84  5132.6  565.76  5150.0  567.38  5167.5  570.17
  5172.7  569.88  5191.4  571.29  5471.2  575.46  5593.1  578.21  5771.0  579.63
#Mann=5,-1,0
  4143.3    0.07       0  4941.3    0.16       0  5014.6    0.07       0
  5020.2    0.16       0  5471.2   0.045       0
Bank Sta=5014.6,5020.2
Exp/Cntr=0.3,0.1

Type RM Length L Ch R = 1,28419,449,449,449
BEGIN DESCRIPTION:
LITTLE CREEK 48.0
END DESCRIPTION:
XS GIS Cut Line= 3
      2311525.02     13788575.00      2310725.00     13788575.00
      2310125.00     13788525.00
#Sta/Elev= 30
  4195.7  587.48  4356.7  581.08  4370.6  580.57  4549.6  574.47  4635.7  570.63
  4685.7  569.07  4755.7  568.67  4875.7  566.54  4885.7  566.63  4905.7  570.00
  4915.7  570.39  4935.7  567.82  4965.7  568.08  4975.7  565.83  4982.6  561.63
  4983.1  561.13  4988.3  561.13  4988.8  561.63  4998.2  561.88  5005.8  563.07
  5015.8  563.66  5045.9  563.89  5076.0  565.32  5146.2  566.24  5178.9  565.41
  5226.5  567.35  5298.4  567.92  5419.7  571.39  5535.1  575.57  5597.8  576.89
#Mann=7,-1,0
  4195.7    0.07       0  4356.7    0.16       0  4370.6    0.07       0
  4549.6    0.16       0  4982.6    0.07       0  4988.8    0.16       0
  5298.4    0.07       0
Bank Sta=4982.6,4988.8
Exp/Cntr=0.3,0.1

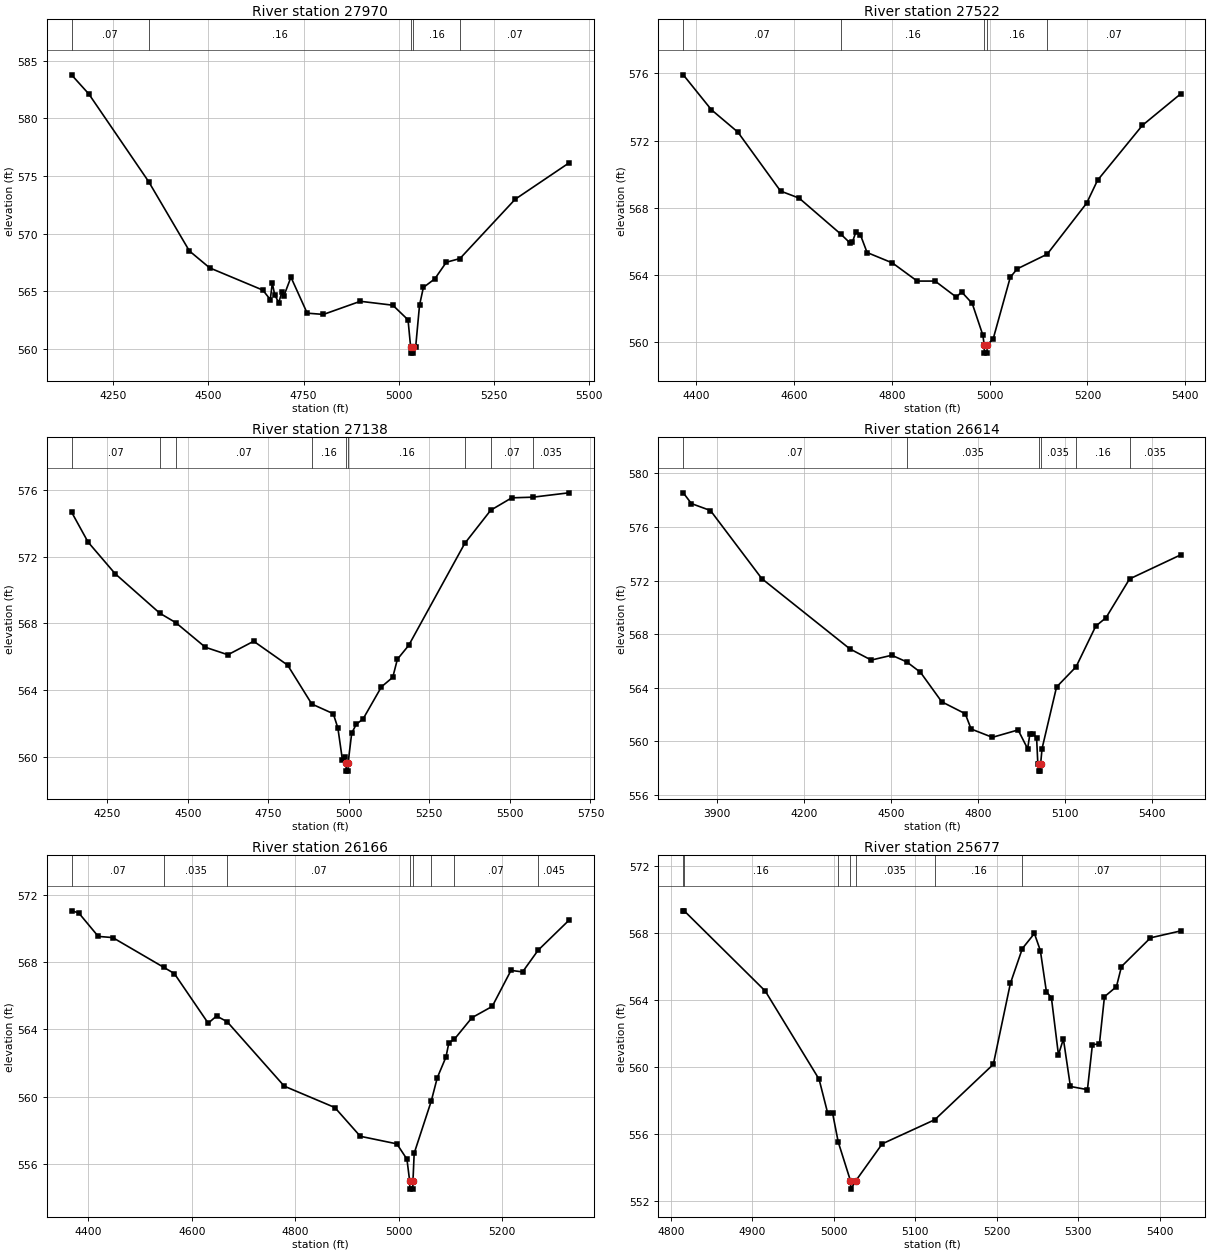
Type RM Length L Ch R = 1,27970,448,448,448
BEGIN DESCRIPTION:
LITTLE CREEK 47.0
END DESCRIPTION:
XS GIS Cut Line= 3
      2311425.03     13787924.99      2310625.00     13788225.00
      2310175.00     13788275.00
#Sta/Elev= 30
  4140.2  583.78  4185.6  582.12  4342.9  574.51  4450.0  568.49  4503.4  567.02
  4643.1  565.09  4662.7  564.27  4668.0  565.71  4674.2  564.69  4684.9  564.00
  4692.9  564.89  4698.3  564.58  4717.0  566.21  4759.7  563.09  4802.4  562.98
  4899.4  564.12  4984.8  563.78  5024.8  562.51  5031.7  560.12  5032.2  559.62
  5037.5  559.62  5038.0  560.12  5044.9  560.17  5055.0  563.78  5065.1  565.32
  5095.2  566.07  5125.4  567.51  5161.3  567.83  5306.5  572.98  5447.4  576.12
#Mann=5,-1,0
  4140.2    0.07       0  4342.9    0.16       0  5031.7    0.07       0
  5038.0    0.16       0  5161.3    0.07       0
Bank Sta=5031.7,5038
Exp/Cntr=0.3,0.1

Type RM Length L Ch R = 1,27522,384,384,384
BEGIN DESCRIPTION:
LITTLE CREEK 46.0
END DESCRIPTION:
XS GIS Cut Line= 3
      2311025.02     13787574.99      2310475.00     13787875.00
      2310225.02     13788174.98
#Sta/Elev= 30
  4373.5  575.92  4431.0  573.84  4485.1  572.51  4572.4  569.00  4610.4  568.58
  4695.5  566.44  4713.8  565.93  4719.5  565.97  4726.6  566.57  4735.7  566.40
  4749.4  565.34  4801.2  564.72  4851.9  563.64  4888.5  563.64  4932.1  562.68
  4942.6  563.00  4964.4  562.31  4986.3  560.41  4988.8  559.85  4989.3  559.35
  4994.7  559.35  4995.2  559.85  5007.2  560.19  5042.3  563.87  5056.6  564.37
  5117.7  565.24  5198.5  568.28  5220.7  569.64  5312.4  572.91  5390.5  574.78
#Mann=5,-1,0
  4373.5    0.07       0  4695.5    0.16       0  4988.8    0.07       0
  4995.2    0.16       0  5117.7    0.07       0
Bank Sta=4988.8,4995.2
Exp/Cntr=0.3,0.1

Type RM Length L Ch R = 1,27138,524,524,524
BEGIN DESCRIPTION:
A19676
END DESCRIPTION:
XS GIS Cut Line= 3
      2310960.01     13787541.79      2310292.12     13787518.96
      2309726.97     13788186.86
#Sta/Elev= 30
  4139.5  574.67  4190.8  572.87  4274.6  570.98  4413.4  568.61  4463.3  568.04
  4554.8  566.57  4624.8  566.12  4704.8  566.93  4810.1  565.50  4885.1  563.17
  4951.8  562.59  4966.1  561.73  4980.4  559.79  4986.9  560.02  4991.5  559.65
  4992.0  559.15  4997.4  559.15  4997.9  559.65  5009.0  561.43  5023.3  561.96
  5044.1  562.27  5101.3  564.20  5136.4  564.77  5150.7  565.85  5185.8  566.68
  5359.8  572.79  5440.5  574.78  5505.6  575.52  5571.7  575.56  5682.7  575.82
#Mann=9,-1,0
  4139.5    0.07       0  4413.4    0.16       0  4463.3    0.07       0
  4885.1    0.16       0  4991.5    0.07       0  4997.9    0.16       0
  5359.8   0.035       0  5440.5    0.07       0  5571.7   0.035       0
Bank Sta=4991.5,4997.9
Exp/Cntr=0.3,0.1

Type RM Length L Ch R = 1,26614,448,448,448
BEGIN DESCRIPTION:
LITTLE CREEK 45.0
END DESCRIPTION:
XS GIS Cut Line= 3
      2311125.05     13787525.01      2309925.00     13787325.00
      2309525.00     13787625.00
#Sta/Elev= 30
  3783.3  578.54  3811.2  577.74  3877.1  577.22  4054.5  572.14  4358.7  566.90
  4432.2  566.07  4503.1  566.43  4555.0  565.93  4602.0  565.16  4675.5  562.96
  4756.6  562.07  4776.9  560.93  4850.4  560.31  4939.1  560.86  4972.0  559.46
  4979.6  560.53  4989.8  560.59  5003.0  560.27  5007.2  558.34  5010.2  558.29
  5010.7  557.79  5016.2  557.79  5016.7  558.29  5021.8  559.47  5071.8  564.06
  5139.3  565.57  5207.2  568.60  5242.6  569.23  5323.9  572.12  5499.9  573.91
#Mann=6,-1,0
  3783.3    0.07       0  4555.0   0.035       0  5010.2   0.035       0
  5016.7   0.035       0  5139.3    0.16       0  5323.9   0.035       0
Bank Sta=5010.2,5016.7
Exp/Cntr=0.3,0.1

Type RM Length L Ch R = 1,26166,489,489,489
BEGIN DESCRIPTION:
LITTLE CREEK 44.0
END DESCRIPTION:
XS GIS Cut Line= 3
      2310774.99     13787374.99      2310225.00     13787075.00
      2309925.00     13786925.00
#Sta/Elev= 30
  4367.4  571.05  4381.2  570.93  4419.1  569.53  4447.1  569.46  4545.9  567.69
  4566.3  567.32  4631.8  564.37  4647.9  564.80  4668.4  564.46  4778.9  560.63
  4876.7  559.36  4926.0  557.65  4996.7  557.20  5016.2  556.29  5021.4  555.01
  5021.9  554.51  5027.4  554.51  5027.9  555.01  5030.2  556.64  5063.3  559.75
  5074.9  561.13  5091.7  562.36  5097.3  563.21  5107.7  563.41  5142.0  564.70
  5181.2  565.37  5217.5  567.51  5239.9  567.42  5270.0  568.71  5329.3  570.48
#Mann=8,-1,0
  4367.4    0.07       0  4545.9   0.035       0  4668.4    0.07       0
  5021.4    0.07       0  5027.9    0.07       0  5063.3    0.16       0
  5107.7    0.07       0  5270.0   0.045       0
Bank Sta=5021.4,5027.9
Exp/Cntr=0.3,0.1

Type RM Length L Ch R = 1,25677,476,476,476
BEGIN DESCRIPTION:
LITTLE CREEK 43.0
END DESCRIPTION:
XS GIS Cut Line= 3
      2310774.99     13787124.99      2310675.00     13786975.00
      2310324.98     13786724.99
#Sta/Elev= 30
  4815.2  569.30  4816.3  569.30  4915.8  564.52  4981.9  559.26  4992.5  557.23
  4998.5  557.23  5005.4  555.52  5020.4  553.21  5020.9  552.71  5027.0  553.21
  5059.4  555.41  5124.0  556.85  5195.8  560.15  5216.7  564.97  5231.4  567.05
  5246.2  567.95  5253.5  566.93  5260.9  564.49  5267.1  564.11  5275.7  560.72
  5281.8  561.66  5290.4  558.83  5311.3  558.64  5317.4  561.32  5326.0  561.37
  5332.2  564.18  5346.9  564.78  5353.1  565.98  5388.7  567.69  5425.6  568.10
#Mann=7,-1,0
  4815.2    0.07       0  4816.3    0.16       0  5005.4   0.035       0
  5020.4    0.07       0  5027.0   0.035       0  5124.0    0.16       0
  5231.4    0.07       0
Bank Sta=5020.4,5027
Exp/Cntr=0.3,0.1