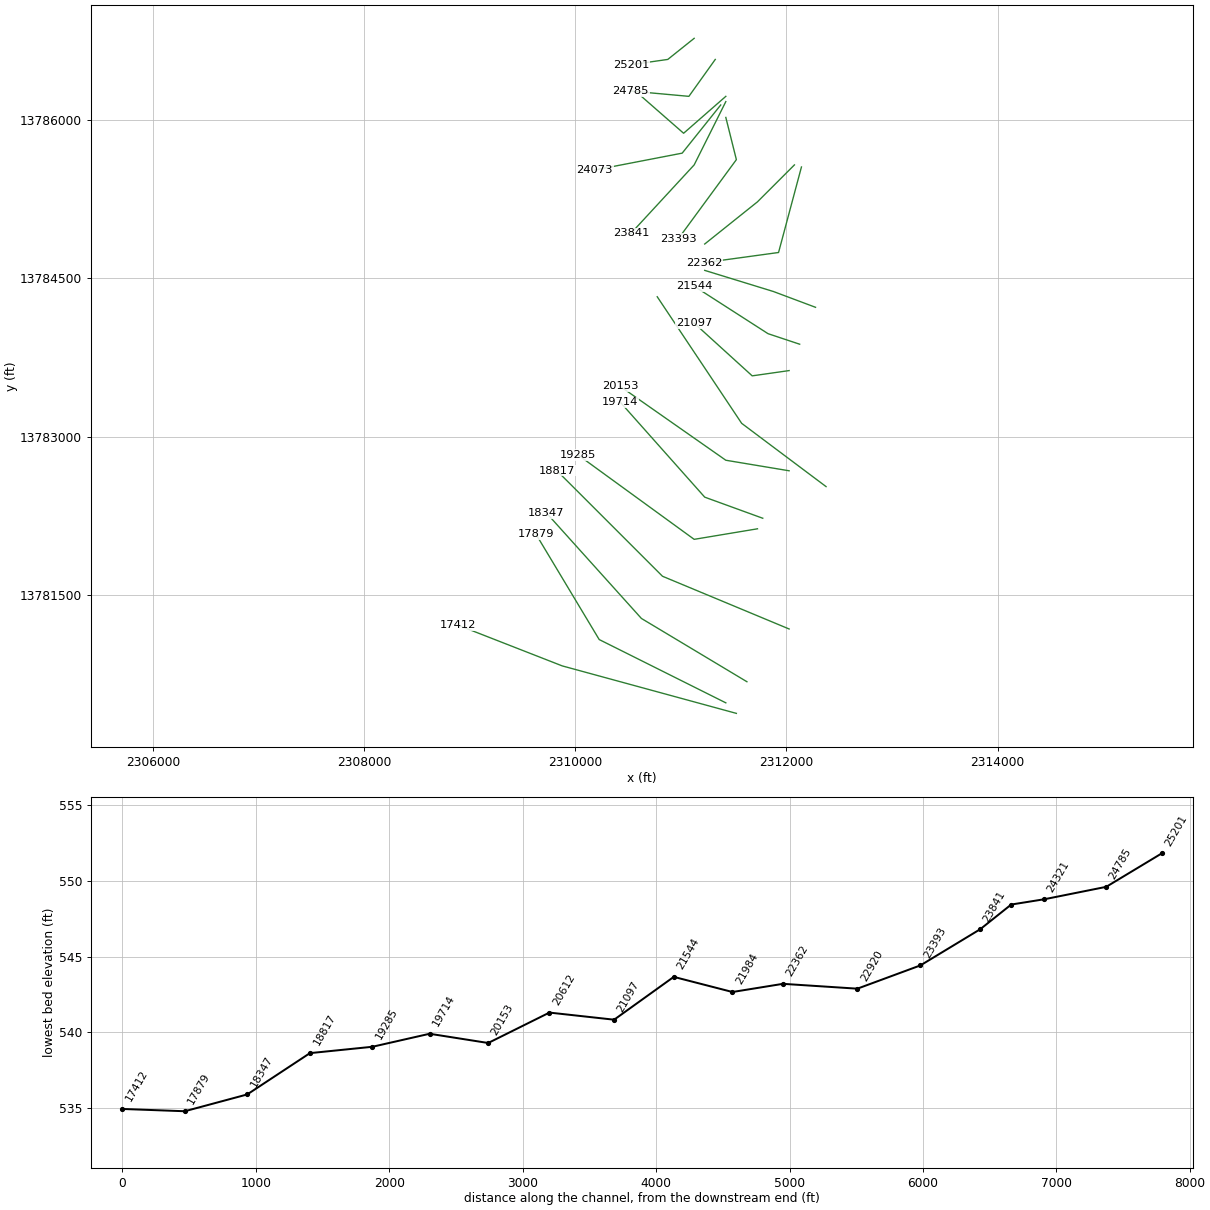
HEC-RAS study LITTLE CREEK.prj: LITTLE CREEK Base Level Engineering

--- LITTLE CREEK.g01 (geometry) --- (continued)

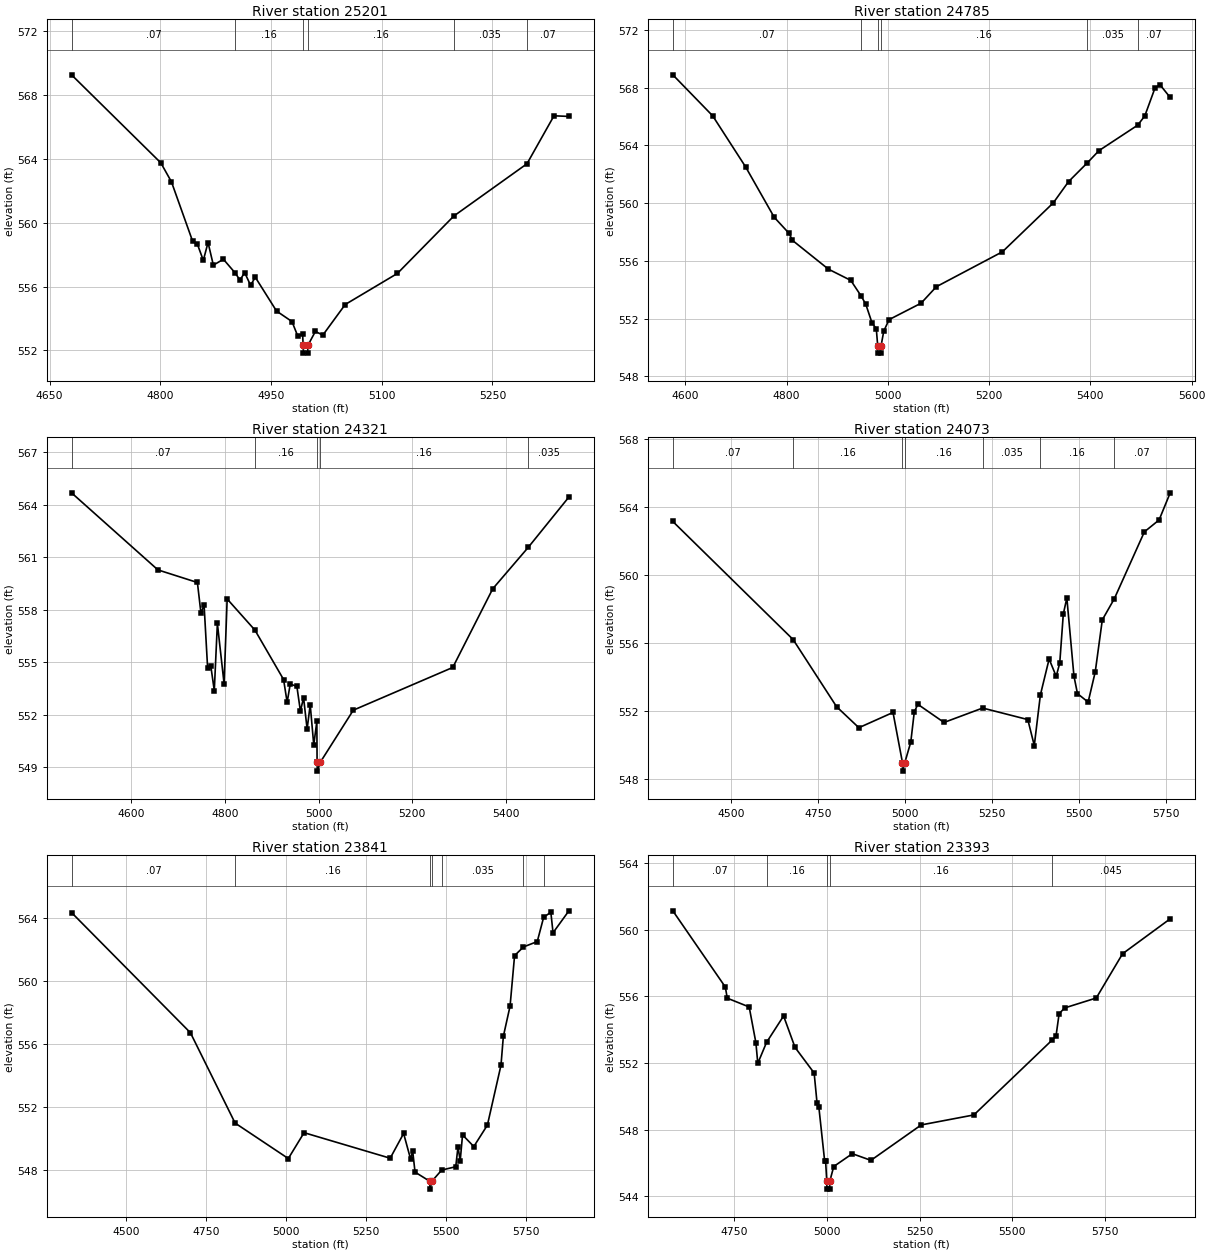
Type RM Length L Ch R = 1,25201,416,416,416
BEGIN DESCRIPTION:
LITTLE CREEK 42.0
END DESCRIPTION:
XS GIS Cut Line= 3
      2311125.01     13786775.01      2310875.00     13786575.00
      2310525.02     13786525.00
#Sta/Elev= 30
  4679.8  569.28  4800.7  563.76  4815.1  562.57  4843.9  558.83  4850.3  558.65
  4858.3  557.64  4864.7  558.76  4871.9  557.34  4885.5  557.71  4901.8  556.83
  4907.9  556.40  4914.3  556.87  4922.3  556.08  4928.7  556.58  4957.5  554.46
  4978.4  553.80  4986.4  552.87  4992.8  553.04  4993.5  552.32  4994.0  551.82
  4999.6  551.82  5000.1  552.32  5010.1  553.18  5020.2  552.95  5050.5  554.87
  5121.2  556.82  5197.6  560.42  5296.7  563.70  5333.3  566.71  5353.5  566.67
#Mann=6,-1,0
  4679.8    0.07       0  4901.8    0.16       0  4993.5    0.07       0
  5000.1    0.16       0  5197.6   0.035       0  5296.7    0.07       0
Bank Sta=4993.5,5000.1
Exp/Cntr=0.3,0.1

Type RM Length L Ch R = 1,24785,464,464,464
BEGIN DESCRIPTION:
LITTLE CREEK 41.0
END DESCRIPTION:
XS GIS Cut Line= 3
      2311325.01     13786575.02      2311075.00     13786225.00
      2310525.01     13786275.00
#Sta/Elev= 30
  4575.2  568.89  4653.9  566.05  4719.0  562.51  4775.5  559.02  4805.0  557.90
  4811.2  557.43  4882.4  555.43  4926.7  554.65  4946.9  553.58  4956.2  553.01
  4968.5  551.72  4977.1  551.29  4979.9  550.11  4980.4  549.61  4986.0  549.61
  4986.5  550.11  4991.8  551.13  5002.3  551.93  5065.6  553.07  5095.7  554.21
  5226.2  556.63  5326.7  560.02  5356.8  561.49  5394.1  562.80  5417.0  563.64
  5493.3  565.40  5507.4  566.04  5527.5  567.97  5537.5  568.20  5557.6  567.32
#Mann=6,-1,0
  4575.2    0.07       0  4946.9    0.16       0  4979.9    0.07       0
  4986.5    0.16       0  5394.1   0.035       0  5493.3    0.07       0
Bank Sta=4979.9,4986.5
Exp/Cntr=0.3,0.1

Type RM Length L Ch R = 1,24321,248,248,248
BEGIN DESCRIPTION:
LITTLE CREEK 40.0
END DESCRIPTION:
XS GIS Cut Line= 3
      2311424.97     13786224.97      2311025.00     13785875.00
      2310624.98     13786225.02
#Sta/Elev= 30
  4472.0  564.68  4656.6  560.28  4741.0  559.56  4748.6  557.81  4755.3  558.27
  4762.9  554.65  4769.5  554.82  4777.1  553.39  4783.7  557.22  4798.0  553.79
  4804.6  558.62  4864.0  556.84  4925.2  554.02  4932.8  552.72  4939.4  553.76
  4953.6  553.63  4961.2  552.21  4967.9  552.99  4975.5  551.19  4982.1  552.58
  4989.7  550.28  4996.3  551.64  4996.8  549.29  4997.3  548.79  5003.5  549.29
  5074.2  552.27  5286.8  554.71  5372.2  559.20  5447.9  561.56  5535.0  564.44
#Mann=5,-1,0
  4472.0    0.07       0  4864.0    0.16       0  4996.8    0.07       0
  5003.5    0.16       0  5447.9   0.035       0
Bank Sta=4996.8,5003.5
Exp/Cntr=0.3,0.1

Type RM Length L Ch R = 1,24073,232,232,232
BEGIN DESCRIPTION:
A19675
END DESCRIPTION:
XS GIS Cut Line= 3
      2311376.77     13786143.20      2311011.40     13785686.49
      2310183.66     13785526.65
#Sta/Elev= 30
  4333.6  563.16  4678.9  556.20  4803.7  552.24  4867.7  551.00  4965.7  551.90
  4992.9  548.94  4993.4  548.44  4999.6  548.94  5016.7  550.15  5026.8  551.93
  5037.0  552.38  5112.2  551.31  5223.1  552.16  5352.7  551.48  5371.3  549.95
  5388.8  552.93  5413.9  555.05  5434.2  554.03  5444.4  554.81  5454.6  557.70
  5464.8  558.65  5485.2  554.04  5495.3  553.01  5525.9  552.51  5546.3  554.29
  5566.6  557.36  5601.2  558.61  5687.4  562.55  5729.6  563.25  5761.5  564.85
#Mann=7,-1,0
  4333.6    0.07       0  4678.9    0.16       0  4992.9    0.07       0
  4999.6    0.16       0  5223.1   0.035       0  5388.8    0.16       0
  5601.2    0.07       0
Bank Sta=4992.9,4999.6
Exp/Cntr=0.3,0.1

Type RM Length L Ch R = 1,23841,448,448,448
BEGIN DESCRIPTION:
LITTLE CREEK 39.0
END DESCRIPTION:
XS GIS Cut Line= 3
      2311424.98     13786174.96      2311125.00     13785575.00
      2310524.98     13784924.98
#Sta/Elev= 30
  4329.1  564.35  4700.8  556.73  4840.6  551.00  5007.0  548.75  5056.3  550.39
  5325.6  548.77  5367.6  550.34  5389.2  548.73  5396.0  549.21  5403.3  547.89
  5449.3  547.31  5449.8  546.81  5456.0  547.31  5486.7  548.02  5530.6  548.23
  5537.7  549.50  5544.5  548.60  5551.9  550.25  5587.1  549.51  5629.6  550.87
  5672.1  554.67  5679.5  556.50  5700.5  558.42  5714.6  561.62  5742.4  562.17
  5785.5  562.51  5805.5  564.05  5828.0  564.37  5834.9  563.07  5884.5  564.46
#Mann=7,-1,0
  4329.1    0.07       0  4840.6    0.16       0  5449.3    0.07       0
  5456.0    0.16       0  5486.7   0.035       0  5742.4    0.16       0
  5805.5    0.07       0
Bank Sta=5449.3,5456
Exp/Cntr=0.3,0.1

Type RM Length L Ch R = 1,23393,473,473,473
BEGIN DESCRIPTION:
LITTLE CREEK 38.0
END DESCRIPTION:
XS GIS Cut Line= 3
      2311425.01     13786024.97      2311525.00     13785625.00
      2310975.02     13784875.03
#Sta/Elev= 30
  4584.1  561.15  4725.8  556.57  4731.0  555.90  4790.2  555.37  4808.3  553.22
  4813.4  551.98  4837.0  553.24  4883.0  554.83  4913.9  552.94  4965.5  551.40
  4973.2  549.62  4978.3  549.33  4993.8  546.12  4996.4  546.12  4999.5  544.92
  5000.0  544.42  5007.5  544.42  5008.0  544.92  5018.4  545.78  5068.5  546.55
  5118.7  546.15  5254.5  548.28  5396.6  548.88  5607.7  553.38  5618.1  553.60
  5626.6  554.96  5641.2  555.31  5726.9  555.91  5797.9  558.57  5926.4  560.67
#Mann=5,-1,0
  4584.1    0.07       0  4837.0    0.16       0  4999.5    0.07       0
  5008.0    0.16       0  5607.7   0.045       0
Bank Sta=4999.5,5008
Exp/Cntr=0.3,0.1

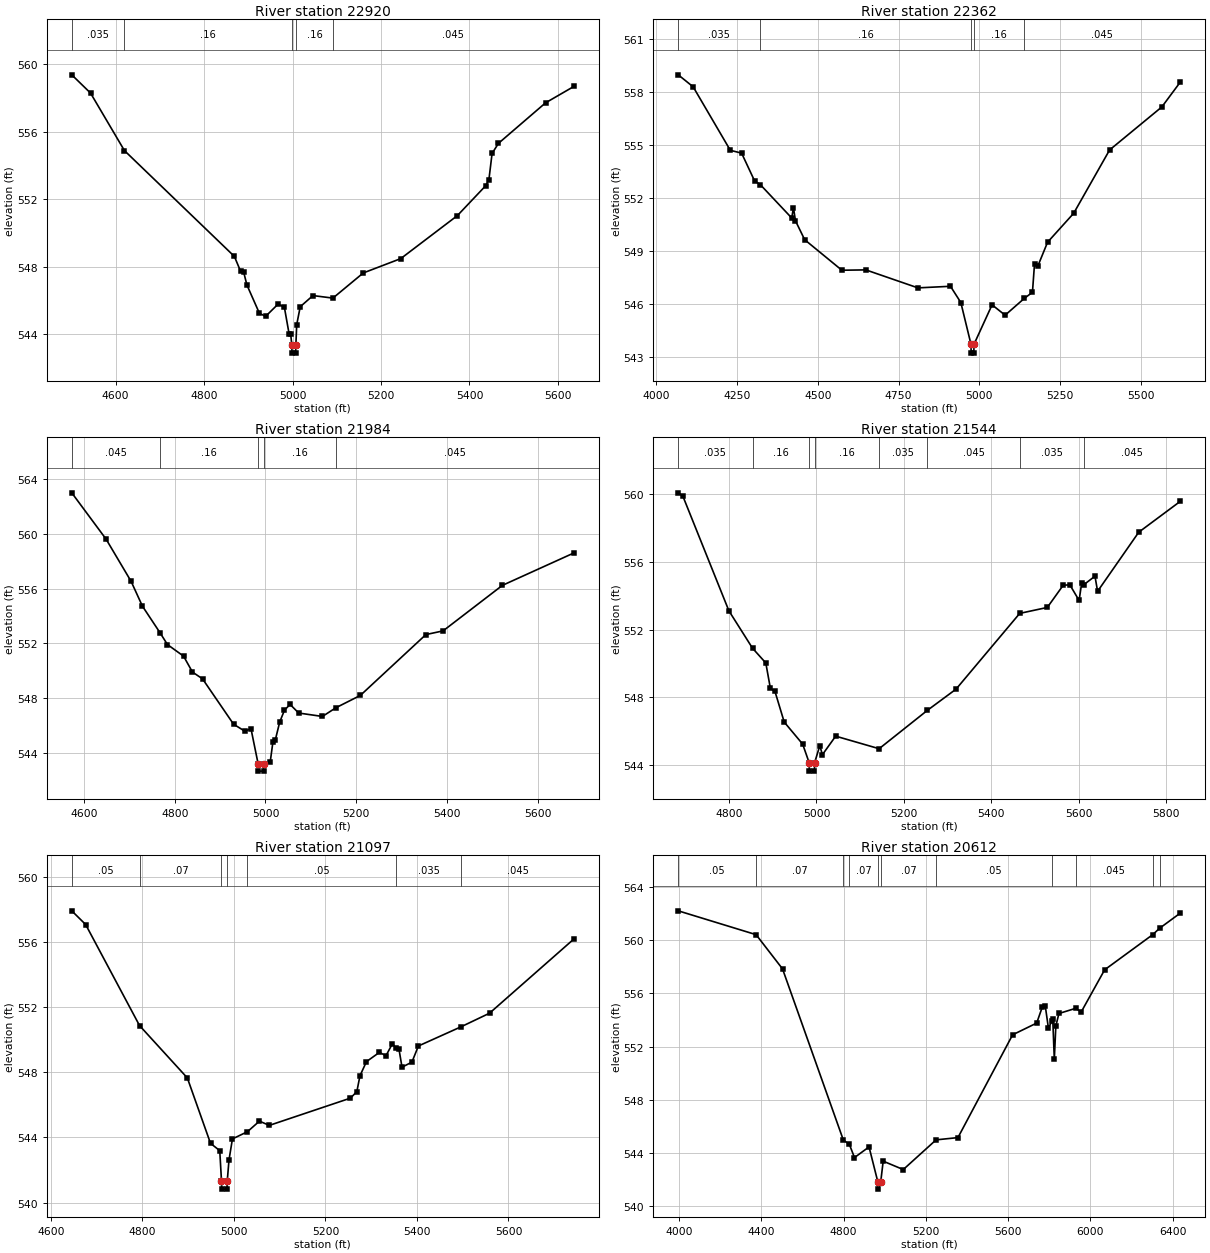
Type RM Length L Ch R = 1,22920,558,558,558
BEGIN DESCRIPTION:
LITTLE CREEK 37.0
END DESCRIPTION:
XS GIS Cut Line= 3
      2312075.01     13785575.01      2311725.00     13785225.00
      2311225.00     13784825.00
#Sta/Elev= 30
  4500.7  559.37  4543.1  558.29  4619.8  554.88  4868.4  548.61  4882.6  547.72
  4889.6  547.66  4896.7  546.92  4925.0  545.24  4939.1  545.06  4967.4  545.79
  4981.5  545.59  4992.2  544.01  4995.7  544.01  4998.2  543.38  4998.7  542.88
  5007.0  542.88  5007.5  543.38  5009.3  544.56  5017.3  545.63  5046.1  546.29
  5091.2  546.14  5159.8  547.63  5244.6  548.48  5372.7  551.03  5436.7  552.80
  5443.9  553.15  5451.1  554.71  5465.5  555.31  5572.0  557.71  5636.0  558.68
#Mann=5,-1,0
  4500.7   0.035       0  4619.8    0.16       0  4998.2    0.07       0
  5007.5    0.16       0  5091.2   0.045       0
Bank Sta=4998.2,5007.5
Exp/Cntr=0.3,0.1

Type RM Length L Ch R = 1,22362,378,378,378
BEGIN DESCRIPTION:
A19674
END DESCRIPTION:
XS GIS Cut Line= 3
      2312141.72     13785555.22      2311924.78     13784744.57
      2311218.46     13784647.74
#Sta/Elev= 30
  4068.9  558.98  4115.0  558.30  4229.9  554.70  4264.8  554.54  4304.8  552.97
  4322.8  552.75  4419.8  550.86  4425.0  551.45  4431.4  550.70  4459.8  549.63
  4574.8  547.90  4648.8  547.92  4809.9  546.90  4910.5  546.99  4942.5  546.07
  4973.9  543.70  4974.4  543.20  4982.7  543.20  4983.2  543.70  5039.1  545.94
  5079.4  545.35  5138.5  546.30  5163.9  546.65  5170.3  548.26  5180.4  548.13
  5210.7  549.49  5291.4  551.13  5402.4  554.72  5563.9  557.16  5621.0  558.57
#Mann=5,-1,0
  4068.9   0.035       0  4322.8    0.16       0  4973.9    0.07       0
  4983.2    0.16       0  5138.5   0.045       0
Bank Sta=4973.9,4983.2
Exp/Cntr=0.3,0.1

Type RM Length L Ch R = 1,21984,440,440,440
BEGIN DESCRIPTION:
LITTLE CREEK 36.0
END DESCRIPTION:
XS GIS Cut Line= 3
      2312275.02     13784224.99      2311875.00     13784375.00
      2311225.00     13784575.00
#Sta/Elev= 30
  4572.8  563.02  4648.5  559.63  4703.7  556.54  4728.6  554.73  4767.9  552.76
  4783.8  551.92  4819.4  551.07  4838.9  549.91  4861.2  549.41  4929.7  546.09
  4954.6  545.58  4968.0  545.77  4984.0  543.16  4984.5  542.66  4996.0  542.66
  4996.5  543.16  5010.5  543.34  5016.4  544.79  5021.6  544.93  5031.4  546.25
  5041.9  547.12  5054.3  547.54  5073.3  546.91  5125.6  546.66  5155.5  547.30
  5209.3  548.20  5353.8  552.65  5391.7  552.92  5522.5  556.25  5680.1  558.62
#Mann=5,-1,0
  4572.8   0.045       0  4767.9    0.16       0  4984.0    0.07       0
  4996.5    0.16       0  5155.5   0.045       0
Bank Sta=4984,4996.5
Exp/Cntr=0.3,0.1

Type RM Length L Ch R = 1,21544,447,447,447
BEGIN DESCRIPTION:
LITTLE CREEK 35.0
END DESCRIPTION:
XS GIS Cut Line= 3
      2312124.99     13783875.00      2311825.00     13783975.00
      2311124.98     13784425.01
#Sta/Elev= 30
  4683.8  560.05  4694.3  559.86  4799.7  553.10  4853.7  550.90  4884.1  550.03
  4894.6  548.53  4905.1  548.35  4926.2  546.55  4968.4  545.25  4983.2  544.16
  4983.7  543.66  4995.3  543.66  4995.8  544.16  5007.6  545.16  5013.6  544.63
  5043.9  545.72  5143.3  544.98  5253.7  547.24  5319.3  548.49  5464.9  552.95
  5528.0  553.30  5564.4  554.61  5579.6  554.63  5600.7  553.71  5606.6  554.74
  5611.5  554.64  5637.0  555.14  5643.0  554.25  5737.1  557.73  5832.2  559.55
#Mann=8,-1,0
  4683.8   0.035       0  4853.7    0.16       0  4983.2    0.07       0
  4995.8    0.16       0  5143.3   0.035       0  5253.7   0.045       0
  5464.9   0.035       0  5611.5   0.045       0
Bank Sta=4983.2,4995.8
Exp/Cntr=0.3,0.1

Type RM Length L Ch R = 1,21097,485,485,485
BEGIN DESCRIPTION:
LITTLE CREEK 34.0
END DESCRIPTION:
XS GIS Cut Line= 3
      2312025.01     13783625.00      2311675.00     13783575.00
      2311124.97     13784075.02
#Sta/Elev= 30
  4645.9  557.90  4676.2  557.06  4794.0  550.86  4898.4  547.65  4949.0  543.64
  4969.2  543.19  4973.0  541.33  4973.5  540.83  4985.1  540.83  4985.6  541.33
  4989.4  542.62  4996.9  543.91  5029.6  544.35  5055.9  545.00  5077.5  544.74
  5254.6  546.41  5268.7  546.81  5275.5  547.78  5289.7  548.65  5318.1  549.22
  5332.3  549.01  5346.4  549.75  5354.8  549.46  5360.6  549.44  5367.4  548.31
  5389.0  548.62  5403.2  549.61  5496.6  550.79  5558.6  551.62  5742.8  556.17
#Mann=7,-1,0
  4645.9    0.05       0  4794.0    0.07       0  4973.0    0.07       0
  4985.6    0.07       0  5029.6    0.05       0  5354.8   0.035       0
  5496.6   0.045       0
Bank Sta=4973,4985.6
Exp/Cntr=0.3,0.1

Type RM Length L Ch R = 1,20612,459,459,459
BEGIN DESCRIPTION:
LITTLE CREEK 33.0
END DESCRIPTION:
XS GIS Cut Line= 3
      2312375.00     13782525.00      2311575.00     13783125.00
      2310775.01     13784324.99
#Sta/Elev= 30
  3995.7  562.20  4374.4  560.41  4503.0  557.84  4798.9  544.98  4827.6  544.68
  4853.0  543.67  4923.8  544.47  4967.3  541.80  4967.8  541.30  4980.3  541.80
  4992.6  543.40  5090.3  542.77  5249.9  545.00  5356.3  545.17  5622.2  552.89
  5739.3  553.77  5766.4  554.97  5781.4  555.02  5796.4  553.38  5813.6  553.95
  5817.5  554.04  5825.0  551.05  5832.5  553.56  5847.5  554.49  5929.6  554.88
  5955.7  554.60  6069.8  557.77  6303.6  560.41  6337.1  560.89  6437.9  562.03
#Mann=11,-1,0
  3995.7    0.05       0  4374.4    0.07       0  4798.9   0.035       0
  4827.6    0.07       0  4967.3    0.07       0  4980.3    0.07       0
  5249.9    0.05       0  5813.6   0.035       0  5929.6   0.045       0
  6303.6   0.035       0  6337.1   0.045       0
Bank Sta=4967.3,4980.3
Exp/Cntr=0.3,0.1

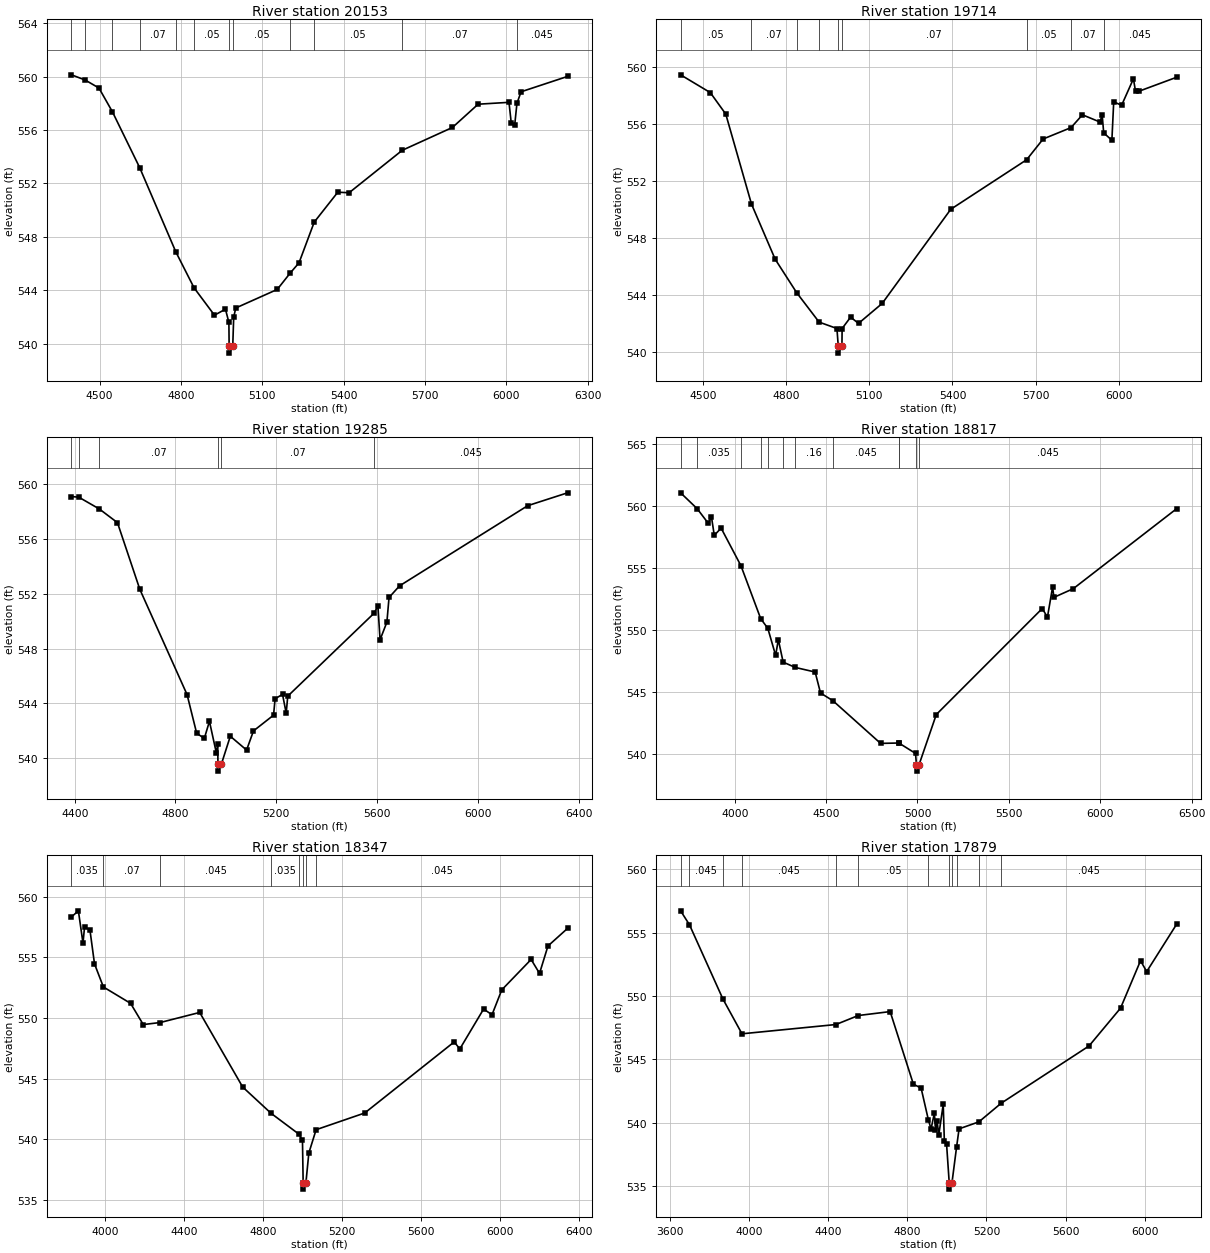
Type RM Length L Ch R = 1,20153,439,439,439
BEGIN DESCRIPTION:
LITTLE CREEK 32.0
END DESCRIPTION:
XS GIS Cut Line= 3
      2312024.98     13782675.00      2311425.00     13782775.00
      2310425.01     13783474.99
#Sta/Elev= 30
  4396.1  560.13  4446.8  559.74  4497.5  559.14  4547.1  557.36  4647.4  553.19
  4780.9  546.87  4848.1  544.18  4923.3  542.13  4963.8  542.58  4976.5  541.59
  4977.4  539.79  4977.9  539.29  4990.7  539.79  4994.2  541.98  5001.8  542.67
  5154.8  544.06  5203.1  545.30  5235.0  546.05  5291.1  549.10  5378.0  551.34
  5419.8  551.30  5615.7  554.48  5800.8  556.19  5895.4  557.93  6009.2  558.07
  6017.5  556.52  6030.1  556.35  6038.5  557.99  6053.7  558.86  6225.0  560.01
#Mann=12,-1,0
  4396.1    0.07       0  4446.8    0.05       0  4547.1   0.035       0
  4647.4    0.07       0  4780.9    0.16       0  4848.1    0.05       0
  4977.4    0.05       0  4990.7    0.05       0  5203.1    0.07       0
  5291.1    0.05       0  5615.7    0.07       0  6038.5   0.045       0
Bank Sta=4977.4,4990.7
Exp/Cntr=0.3,0.1

Type RM Length L Ch R = 1,19714,429,429,429
BEGIN DESCRIPTION:
LITTLE CREEK 31.0
END DESCRIPTION:
XS GIS Cut Line= 3
      2311774.98     13782225.01      2311225.00     13782425.00
      2310424.98     13783325.02
#Sta/Elev= 30
  4419.3  559.46  4526.4  558.21  4582.2  556.70  4674.9  550.38  4760.4  546.50
  4837.9  544.15  4918.9  542.08  4983.2  541.63  4987.9  540.40  4988.4  539.90
  5001.2  540.40  5001.9  541.63  5032.5  542.43  5061.0  541.99  5146.3  543.39
  5393.8  550.01  5667.4  553.49  5727.0  554.95  5827.6  555.75  5868.8  556.65
  5932.3  556.14  5939.8  556.67  5945.5  555.38  5975.0  554.86  5981.6  557.56
  6010.1  557.32  6052.7  559.18  6060.2  558.31  6074.5  558.32  6208.7  559.29
#Mann=9,-1,0
  4419.3    0.05       0  4674.9    0.07       0  4837.9    0.16       0
  4918.9    0.07       0  4987.9    0.07       0  5001.2    0.07       0
  5667.4    0.05       0  5827.6    0.07       0  5945.5   0.045       0
Bank Sta=4987.9,5001.2
Exp/Cntr=0.3,0.1

Type RM Length L Ch R = 1,19285,468,468,468
BEGIN DESCRIPTION:
LITTLE CREEK 30.0
END DESCRIPTION:
XS GIS Cut Line= 3
      2311725.04     13782125.01      2311125.00     13782025.00
      2310024.97     13782825.02
#Sta/Elev= 30
  4387.2  559.11  4416.5  559.06  4497.7  558.20  4569.7  557.20  4658.4  552.33
  4846.0  544.63  4884.0  541.81  4914.4  541.43  4934.7  542.68  4962.6  540.33
  4967.6  541.03  4968.5  539.54  4969.0  539.04  4981.9  539.54  5017.5  541.59
  5082.1  540.58  5109.5  541.98  5189.1  543.13  5195.3  544.33  5224.7  544.65
  5239.3  543.28  5245.5  544.52  5587.4  550.57  5603.3  551.10  5611.8  548.64
  5638.9  549.93  5647.4  551.73  5689.1  552.58  6197.6  558.44  6355.7  559.38
#Mann=6,-1,0
  4387.2    0.07       0  4416.5   0.045       0  4497.7    0.07       0
  4968.5    0.07       0  4981.9    0.07       0  5587.4   0.045       0
Bank Sta=4968.5,4981.9
Exp/Cntr=0.3,0.1

Type RM Length L Ch R = 1,18817,470,470,470
BEGIN DESCRIPTION:
LITTLE CREEK 29.0
END DESCRIPTION:
XS GIS Cut Line= 3
      2312025.01     13781175.00      2310825.00     13781675.00
      2309825.02     13782674.98
#Sta/Elev= 30
  3703.9  561.09  3794.4  559.81  3855.6  558.62  3872.4  559.17  3888.1  557.66
  3925.5  558.24  4034.1  555.20  4142.1  550.93  4181.0  550.15  4223.9  547.96
  4238.5  549.24  4264.9  547.42  4331.6  546.99  4440.0  546.62  4469.3  544.93
  4537.5  544.30  4798.1  540.86  4898.1  540.89  4898.2  540.89  4989.3  540.05
  4994.3  539.12  4994.8  538.62  5008.1  539.12  5102.9  543.19  5682.7  551.75
  5711.0  551.05  5739.3  553.49  5746.4  552.65  5852.4  553.35  6418.1  559.81
#Mann=12,-1,0
  3703.9   0.045       0  3794.4   0.035       0  4034.1    0.16       0
  4142.1    0.07       0  4181.0    0.16       0  4264.9    0.07       0
  4331.6    0.16       0  4537.5   0.045       0  4898.1   0.035       0
  4898.2    0.07       0  4994.3    0.07       0  5008.1   0.045       0
Bank Sta=4994.3,5008.1
Exp/Cntr=0.3,0.1

Type RM Length L Ch R = 1,18347,468,468,468
BEGIN DESCRIPTION:
LITTLE CREEK 28.0
END DESCRIPTION:
XS GIS Cut Line= 3
      2311625.01     13780675.00      2310625.00     13781275.00
      2309724.97     13782275.03
#Sta/Elev= 30
  3829.7  558.34  3864.7  558.84  3888.0  556.18  3895.8  557.48  3923.0  557.29
  3946.3  554.47  3991.3  552.56  4129.0  551.21  4193.2  549.46  4279.3  549.63
  4478.9  550.46  4696.6  544.31  4840.5  542.14  4980.8  540.43  4999.3  539.91
  5002.8  536.39  5003.3  535.89  5016.6  536.39  5031.4  538.86  5068.3  540.79
  5314.7  542.17  5767.6  548.03  5796.0  547.45  5916.4  550.74  5959.0  550.27
  6008.3  552.32  6157.0  554.83  6199.6  553.68  6242.2  555.94  6341.3  557.39
#Mann=8,-1,0
  3829.7   0.035       0  3991.3    0.07       0  4279.3   0.045       0
  4840.5   0.035       0  4980.8    0.05       0  5002.8    0.05       0
  5016.6    0.05       0  5068.3   0.045       0
Bank Sta=5002.8,5016.6
Exp/Cntr=0.3,0.1

Type RM Length L Ch R = 1,17879,467,467,467
BEGIN DESCRIPTION:
LITTLE CREEK 27.0
END DESCRIPTION:
XS GIS Cut Line= 3
      2311425.03     13780474.99      2310225.00     13781075.00
      2309624.98     13782075.03
#Sta/Elev= 30
  3654.1  556.71  3698.9  555.61  3868.0  549.76  3964.3  547.02  4439.3  547.75
  4552.2  548.46  4713.5  548.77  4830.9  543.05  4870.0  542.74  4907.0  540.22
  4920.3  539.52  4937.1  540.78  4942.7  539.40  4951.0  540.11  4959.4  539.06
  4981.8  541.46  4987.4  538.59  4998.7  538.33  5012.1  535.28  5012.6  534.78
  5026.0  535.28  5049.2  538.09  5061.9  539.53  5162.0  540.08  5274.8  541.55
  5718.8  546.06  5878.2  549.04  5979.3  552.78  6010.4  551.92  6162.0  555.66
#Mann=12,-1,0
  3654.1   0.035       0  3698.9   0.045       0  3868.0    0.07       0
  3964.3   0.045       0  4439.3   0.035       0  4552.2    0.05       0
  4907.0    0.07       0  5012.1    0.07       0  5026.0    0.07       0
  5049.2    0.05       0  5162.0   0.035       0  5274.8   0.045       0
Bank Sta=5012.1,5026
Exp/Cntr=0.3,0.1

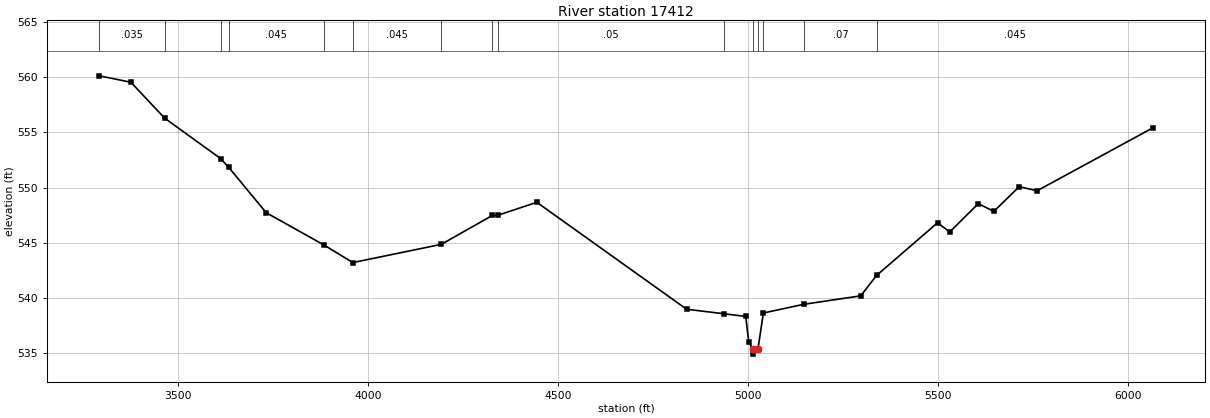
Type RM Length L Ch R = 1,17412,450,450,450
BEGIN DESCRIPTION:
LITTLE CREEK 26.0
END DESCRIPTION:
XS GIS Cut Line= 3
      2311525.01     13780375.00      2309875.00     13780825.00
      2308887.83     13781210.93
#Sta/Elev= 30
  3294.3  560.10  3377.2  559.52  3466.1  556.27  3613.1  552.62  3634.9  551.81
  3733.1  547.72  3885.0  544.80  3961.0  543.21  4193.8  544.86  4328.1  547.48
  4341.4  547.48  4444.8  548.66  4838.7  538.99  4937.2  538.58  4994.2  538.34
  5002.0  536.06  5012.4  535.43  5012.9  534.93  5026.5  535.43  5040.5  538.65
  5147.4  539.44  5296.4  540.20  5338.4  542.05  5498.5  546.81  5530.7  545.98
  5605.8  548.54  5646.7  547.84  5713.2  550.07  5760.7  549.71  6064.5  555.39
#Mann=15,-1,0
  3294.3   0.035       0  3466.1   0.045       0  3613.1    0.07       0
  3634.9   0.045       0  3885.0   0.035       0  3961.0   0.045       0
  4193.8    0.05       0  4328.1   0.035       0  4341.4    0.05       0
  4937.2    0.07       0  5012.4    0.07       0  5026.5    0.07       0
  5040.5    0.05       0  5147.4    0.07       0  5338.4   0.045       0
Bank Sta=5012.4,5026.5
Exp/Cntr=0.3,0.1