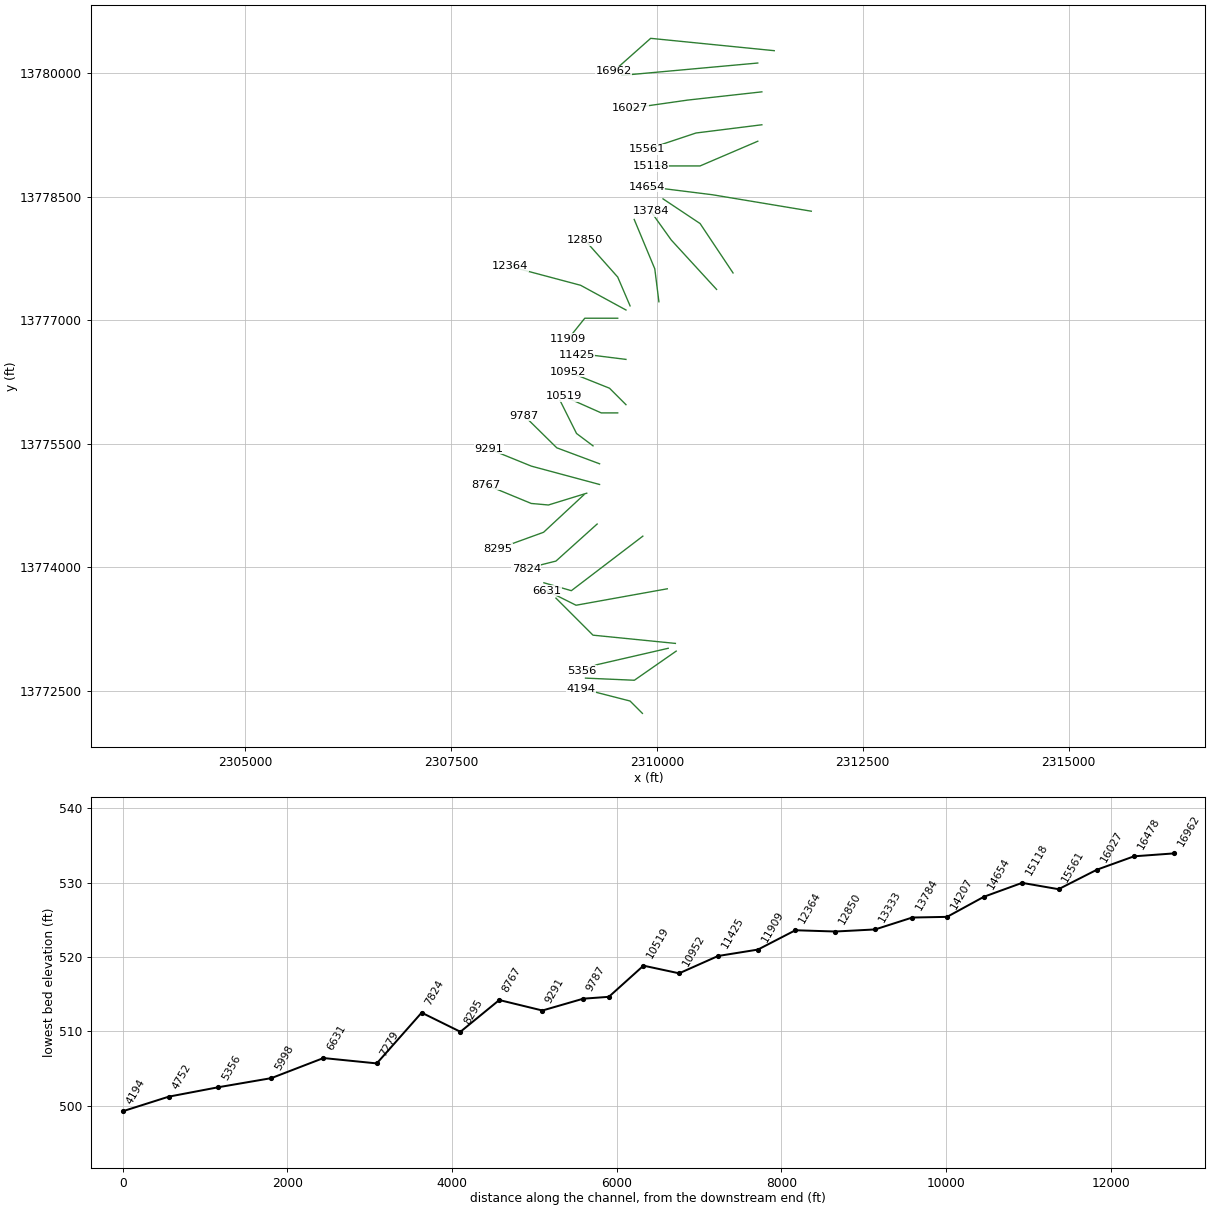
HEC-RAS study LITTLE CREEK.prj: LITTLE CREEK Base Level Engineering

--- LITTLE CREEK.g01 (geometry) --- (continued)

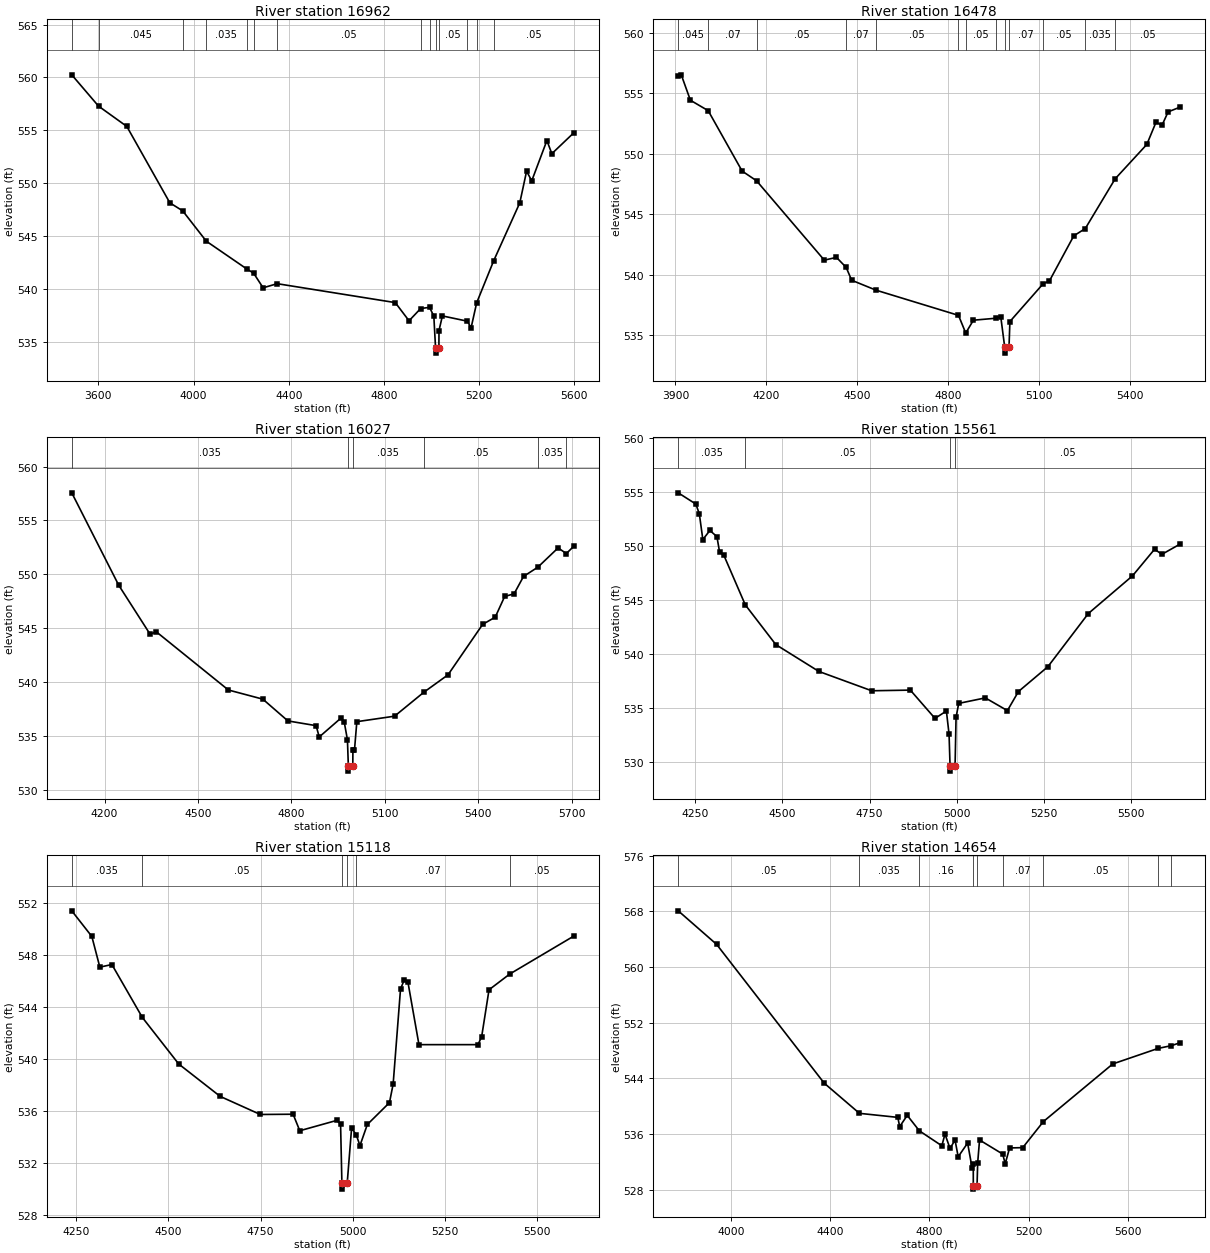
Type RM Length L Ch R = 1,16962,484,484,484
BEGIN DESCRIPTION:
LITTLE CREEK 25.0
END DESCRIPTION:
XS GIS Cut Line= 3
      2311425.02     13780275.00      2309925.00     13780425.00
      2309474.99     13780024.99
#Sta/Elev= 30
  3488.1  560.25  3600.5  557.29  3719.3  555.37  3900.2  548.14  3954.2  547.38
  4053.4  544.51  4222.3  541.90  4252.0  541.49  4292.1  540.10  4351.3  540.49
  4847.4  538.70  4905.2  536.98  4954.1  538.14  4991.4  538.25  5009.4  537.42
  5016.6  534.42  5017.1  533.92  5030.7  534.42  5031.1  536.06  5045.4  537.44
  5150.7  536.94  5165.8  536.30  5189.4  538.68  5261.1  542.67  5370.6  548.14
  5399.1  551.13  5420.8  550.22  5484.4  554.03  5505.3  552.79  5597.7  554.77
#Mann=14,-1,0
  3488.1   0.035       0  3600.5   0.045       0  3954.2    0.07       0
  4053.4   0.035       0  4222.3   0.045       0  4252.0   0.035       0
  4351.3    0.05       0  4954.1    0.07       0  4991.4    0.05       0
  5016.6    0.05       0  5030.7    0.05       0  5150.7   0.035       0
  5189.4    0.07       0  5261.1    0.05       0
Bank Sta=5016.6,5030.7
Exp/Cntr=0.3,0.1

Type RM Length L Ch R = 1,16478,451,451,451
BEGIN DESCRIPTION:
LITTLE CREEK 24.0
END DESCRIPTION:
XS GIS Cut Line= 3
      2311224.98     13780125.00      2310125.00     13780025.00
      2309574.98     13779975.00
#Sta/Elev= 30
  3909.2  556.45  3919.2  556.52  3949.3  554.42  4008.0  553.56  4120.0  548.57
  4167.5  547.77  4391.2  541.21  4431.3  541.44  4463.4  540.61  4481.5  539.55
  4562.0  538.73  4834.0  536.65  4857.9  535.19  4883.2  536.25  4956.5  536.41
  4973.5  536.54  4986.5  534.03  4987.0  533.53  5000.7  534.03  5003.7  536.14
  5113.3  539.26  5134.2  539.50  5214.5  543.22  5252.4  543.82  5351.0  547.93
  5455.5  550.77  5485.7  552.60  5505.7  552.36  5525.8  553.46  5566.0  553.86
#Mann=13,-1,0
  3909.2   0.045       0  4008.0    0.07       0  4167.5    0.05       0
  4463.4    0.07       0  4562.0    0.05       0  4834.0    0.07       0
  4857.9    0.05       0  4956.5    0.07       0  4986.5    0.07       0
  5000.7    0.07       0  5113.3    0.05       0  5252.4   0.035       0
  5351.0    0.05       0
Bank Sta=4986.5,5000.7
Exp/Cntr=0.3,0.1

Type RM Length L Ch R = 1,16027,466,466,466
BEGIN DESCRIPTION:
LITTLE CREEK 23.0
END DESCRIPTION:
XS GIS Cut Line= 3
      2311274.97     13779775.00      2310375.00     13779675.00
      2309675.01     13779575.00
#Sta/Elev= 30
  4094.5  557.56  4245.4  548.98  4346.0  544.44  4366.1  544.66  4597.5  539.26
  4708.2  538.41  4788.7  536.39  4879.3  535.95  4889.3  534.90  4959.8  536.67
  4969.8  536.26  4979.9  534.64  4982.8  532.23  4983.3  531.73  4997.1  532.23
  4997.5  533.67  5002.5  533.67  5010.1  536.32  5131.3  536.83  5225.7  539.06
  5303.0  540.67  5414.2  545.35  5454.6  546.02  5484.9  547.94  5515.2  548.19
  5545.5  549.80  5591.5  550.66  5656.6  552.45  5683.0  551.92  5707.1  552.61
#Mann=6,-1,0
  4094.5   0.035       0  4982.8   0.035       0  4997.1   0.035       0
  5225.7    0.05       0  5591.5   0.035       0  5683.0    0.05       0
Bank Sta=4982.8,4997.1
Exp/Cntr=0.3,0.1

Type RM Length L Ch R = 1,15561,443,443,443
BEGIN DESCRIPTION:
LITTLE CREEK 22.0
END DESCRIPTION:
XS GIS Cut Line= 3
      2311274.98     13779375.00      2310475.00     13779275.00
      2309874.96     13779074.99
#Sta/Elev= 30
  4201.6  554.91  4252.0  553.87  4262.0  552.97  4272.1  550.58  4292.3  551.42
  4312.4  550.85  4320.0  549.44  4332.6  549.10  4393.8  544.52  4481.2  540.84
  4604.7  538.35  4755.9  536.56  4866.7  536.62  4937.3  534.00  4970.0  534.68
  4977.6  532.55  4980.5  529.61  4981.0  529.11  4994.9  529.61  4997.7  534.11
  5005.3  535.39  5081.6  535.90  5144.8  534.72  5176.5  536.49  5260.8  538.79
  5376.7  543.72  5503.2  547.21  5566.5  549.68  5587.6  549.21  5640.3  550.17
#Mann=4,-1,0
  4201.6   0.035       0  4393.8    0.05       0  4980.5    0.05       0
  4994.9    0.05       0
Bank Sta=4980.5,4994.9
Exp/Cntr=0.3,0.1

Type RM Length L Ch R = 1,15118,464,464,464
BEGIN DESCRIPTION:
LITTLE CREEK 21.0
END DESCRIPTION:
XS GIS Cut Line= 3
      2311224.97     13779174.99      2310525.00     13778875.00
      2309925.04     13778875.00
#Sta/Elev= 30
  4237.8  551.36  4292.2  549.39  4313.9  547.03  4346.6  547.23  4429.2  543.16
  4527.9  539.58  4640.3  537.09  4749.1  535.70  4838.0  535.72  4856.1  534.45
  4955.8  535.24  4966.7  534.98  4970.3  530.46  4970.8  529.96  4984.8  530.46
  4996.6  534.65  5009.0  534.15  5019.3  533.31  5039.3  534.93  5099.3  536.61
  5109.3  538.04  5129.3  545.35  5139.3  546.04  5149.3  545.89  5179.3  541.07
  5339.3  541.07  5349.3  541.68  5369.3  545.29  5425.5  546.50  5599.3  549.42
#Mann=6,-1,0
  4237.8   0.035       0  4429.2    0.05       0  4970.3    0.05       0
  4984.8    0.05       0  5009.0    0.07       0  5425.5    0.05       0
Bank Sta=4970.3,4984.8
Exp/Cntr=0.3,0.1

Type RM Length L Ch R = 1,14654,447,447,447
BEGIN DESCRIPTION:
LITTLE CREEK 20.0
END DESCRIPTION:
XS GIS Cut Line= 3
      2311875.03     13778324.99      2310675.00     13778525.00
      2309875.01     13778625.00
#Sta/Elev= 30
  3788.4  568.08  3943.0  563.26  4376.4  543.32  4518.5  538.98  4673.0  538.40
  4680.6  537.07  4711.0  538.69  4759.8  536.47  4850.4  534.32  4863.1  536.00
  4883.3  533.94  4903.6  535.14  4916.3  532.74  4954.3  534.71  4972.0  531.19
  4977.1  531.77  4977.2  528.59  4977.7  528.09  4992.3  528.59  4994.8  531.87
  5002.4  535.15  5095.5  533.13  5105.8  531.74  5123.4  534.01  5176.3  534.05
  5259.6  537.80  5539.1  546.08  5721.7  548.31  5775.6  548.71  5811.2  549.14
#Mann=9,-1,0
  3788.4    0.05       0  4518.5   0.035       0  4759.8    0.16       0
  4977.2    0.07       0  4992.3    0.16       0  5095.5    0.07       0
  5259.6    0.05       0  5721.7   0.045       0  5775.6    0.05       0
Bank Sta=4977.2,4992.3
Exp/Cntr=0.3,0.1

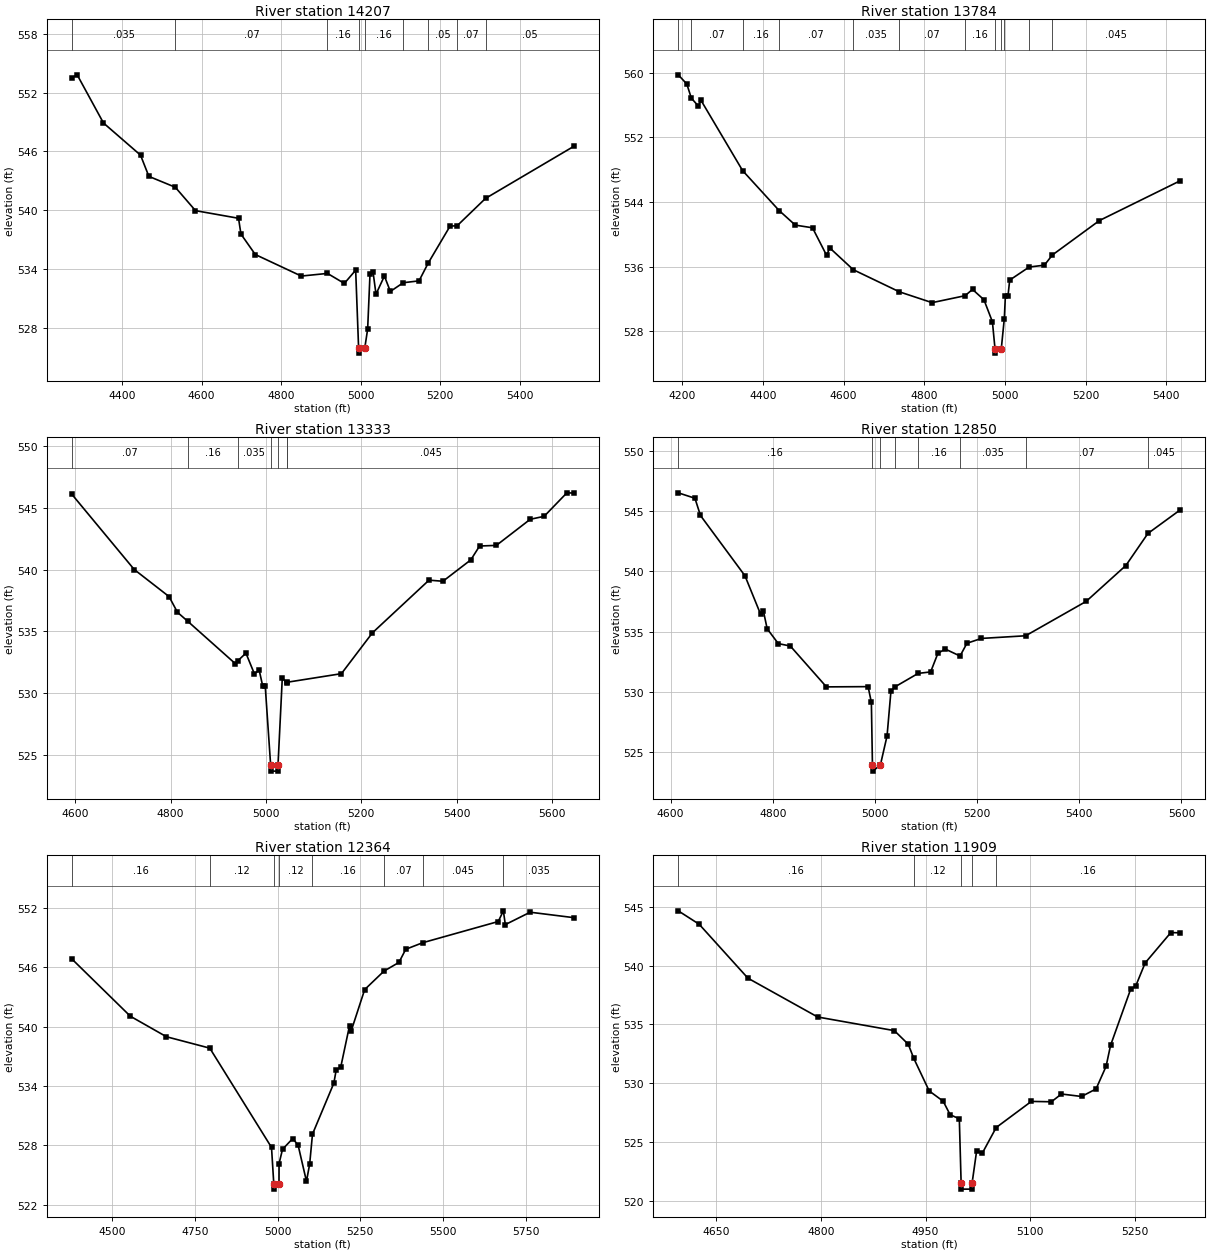
Type RM Length L Ch R = 1,14207,423,423,423
BEGIN DESCRIPTION:
LITTLE CREEK 19.0
END DESCRIPTION:
XS GIS Cut Line= 3
      2310925.02     13777574.96      2310525.00     13778175.00
      2310074.99     13778475.01
#Sta/Elev= 30
  4273.9  553.50  4287.5  553.81  4353.6  548.89  4446.7  545.61  4467.7  543.44
  4534.1  542.33  4584.9  539.94  4693.1  539.16  4699.1  537.55  4735.2  535.46
  4850.8  533.26  4916.6  533.53  4959.0  532.51  4987.5  533.86  4994.9  525.89
  4995.4  525.39  5010.3  525.89  5017.6  527.84  5023.6  533.51  5031.1  533.70
  5038.6  531.41  5059.7  533.26  5074.7  531.69  5107.1  532.58  5146.8  532.77
  5169.6  534.57  5224.9  538.37  5242.4  538.39  5313.9  541.19  5535.9  546.51
#Mann=9,-1,0
  4273.9   0.035       0  4534.1    0.07       0  4916.6    0.16       0
  4994.9    0.07       0  5010.3    0.16       0  5107.1    0.07       0
  5169.6    0.05       0  5242.4    0.07       0  5313.9    0.05       0
Bank Sta=4994.9,5010.3
Exp/Cntr=0.3,0.1

Type RM Length L Ch R = 1,13784,451,451,451
BEGIN DESCRIPTION:
LITTLE CREEK 18.0
END DESCRIPTION:
XS GIS Cut Line= 3
      2310725.01     13777374.99      2310175.00     13777975.00
      2309924.98     13778325.03
#Sta/Elev= 30
  4190.4  559.76  4211.7  558.62  4222.8  556.88  4240.0  555.90  4246.8  556.60
  4349.9  547.90  4440.3  542.96  4480.5  541.15  4523.1  540.82  4558.2  537.39
  4565.6  538.34  4624.1  535.63  4738.4  532.89  4819.4  531.55  4901.1  532.41
  4919.6  533.19  4947.9  531.91  4968.9  529.18  4975.4  525.80  4975.9  525.30
  4990.8  525.80  4998.4  529.58  5001.0  532.33  5007.4  532.33  5011.7  534.34
  5059.9  535.96  5097.7  536.19  5117.4  537.45  5234.2  541.72  5434.5  546.65
#Mann=12,-1,0
  4190.4   0.035       0  4222.8    0.07       0  4349.9    0.16       0
  4440.3    0.07       0  4624.1   0.035       0  4738.4    0.07       0
  4901.1    0.16       0  4975.4    0.07       0  4990.8    0.16       0
  4998.4    0.07       0  5059.9    0.05       0  5117.4   0.045       0
Bank Sta=4975.4,4990.8
Exp/Cntr=0.3,0.1

Type RM Length L Ch R = 1,13333,483,483,483
BEGIN DESCRIPTION:
LITTLE CREEK 17.0
END DESCRIPTION:
XS GIS Cut Line= 3
      2310025.00     13777224.97      2309975.00     13777625.00
      2309725.02     13778224.96
#Sta/Elev= 30
  4592.8  546.09  4723.8  540.00  4796.9  537.81  4814.5  536.54  4836.2  535.81
  4935.5  532.40  4941.6  532.64  4958.1  533.24  4975.8  531.57  4985.9  531.86
  4993.4  530.56  4998.6  530.56  5009.9  524.20  5010.4  523.70  5024.9  523.70
  5025.4  524.20  5034.4  531.26  5043.4  530.80  5045.2  530.89  5158.4  531.58
  5223.4  534.88  5342.1  539.14  5371.3  539.05  5429.8  540.78  5448.2  541.90
  5483.4  541.95  5554.4  544.06  5583.6  544.30  5631.3  546.20  5645.9  546.18
#Mann=7,-1,0
  4592.8    0.07       0  4836.2    0.16       0  4941.6   0.035       0
  5009.9   0.035       0  5025.4   0.035       0  5043.4    0.07       0
  5045.2   0.045       0
Bank Sta=5009.9,5025.4
Exp/Cntr=0.3,0.1

Type RM Length L Ch R = 1,12850,486,486,486
BEGIN DESCRIPTION:
LITTLE CREEK 16.0
END DESCRIPTION:
XS GIS Cut Line= 3
      2309675.01     13777174.98      2309525.00     13777525.00
      2309124.99     13777975.01
#Sta/Elev= 30
  4614.8  546.51  4647.5  546.06  4658.3  544.63  4745.4  539.63  4776.2  536.42
  4781.6  536.69  4788.9  535.23  4810.7  534.00  4834.2  533.80  4904.9  530.41
  4986.5  530.43  4992.9  529.12  4995.0  523.92  4995.5  523.42  5010.5  523.92
  5023.6  526.34  5031.2  530.05  5038.2  530.39  5084.5  531.53  5108.9  531.65
  5123.1  533.19  5137.4  533.55  5166.5  532.97  5180.0  534.03  5208.4  534.43
  5294.9  534.65  5413.3  537.50  5491.1  540.48  5534.3  543.14  5597.7  545.10
#Mann=8,-1,0
  4614.8    0.16       0  4995.0    0.07       0  5010.5    0.16       0
  5038.2   0.035       0  5084.5    0.16       0  5166.5   0.035       0
  5294.9    0.07       0  5534.3   0.045       0
Bank Sta=4995,5010.5
Exp/Cntr=0.3,0.1

Type RM Length L Ch R = 1,12364,455,455,455
BEGIN DESCRIPTION:
LITTLE CREEK 15.0
END DESCRIPTION:
XS GIS Cut Line= 3
      2309625.02     13777124.99      2309075.00     13777425.00
      2308214.18     13777654.48
#Sta/Elev= 30
  4377.8  546.83  4554.9  541.04  4664.0  538.97  4794.9  537.82  4981.5  527.80
  4988.4  524.09  4988.9  523.59  5004.1  524.09  5004.3  526.17  5014.7  527.61
  5045.7  528.70  5061.9  528.02  5087.1  524.38  5096.8  526.12  5105.3  529.14
  5169.9  534.29  5177.1  535.65  5190.6  535.89  5217.2  540.08  5222.3  539.56
  5263.0  543.73  5321.5  545.60  5366.5  546.47  5387.2  547.80  5438.3  548.46
  5666.7  550.60  5682.2  551.68  5688.1  550.29  5763.2  551.54  5895.2  550.99
#Mann=8,-1,0
  4377.8    0.16       0  4794.9    0.12       0  4988.4    0.07       0
  5004.1    0.12       0  5105.3    0.16       0  5321.5    0.07       0
  5438.3   0.045       0  5682.2   0.035       0
Bank Sta=4988.4,5004.1
Exp/Cntr=0.3,0.1

Type RM Length L Ch R = 1,11909,484,484,484
BEGIN DESCRIPTION:
LITTLE CREEK 14.0
END DESCRIPTION:
XS GIS Cut Line= 3
      2309525.04     13777025.00      2309125.00     13777025.00
      2308925.00     13776774.99
#Sta/Elev= 30
  4595.3  544.66  4625.3  543.52  4695.3  538.93  4795.3  535.63  4905.3  534.47
  4925.3  533.31  4933.1  532.12  4955.3  529.34  4975.3  528.47  4985.3  527.32
  4998.5  526.97  5001.1  521.49  5001.6  520.99  5016.3  520.99  5016.8  521.49
  5023.3  524.23  5031.4  524.04  5051.4  526.23  5101.8  528.45  5130.6  528.42
  5145.0  529.08  5173.8  528.87  5194.6  529.51  5209.0  531.43  5215.4  533.21
  5244.3  538.00  5251.5  538.26  5265.1  540.23  5301.9  542.81  5315.5  542.79
#Mann=5,-1,0
  4595.3    0.16       0  4933.1    0.12       0  5001.1    0.07       0
  5016.8    0.12       0  5051.4    0.16       0
Bank Sta=5001.1,5016.8
Exp/Cntr=0.3,0.1

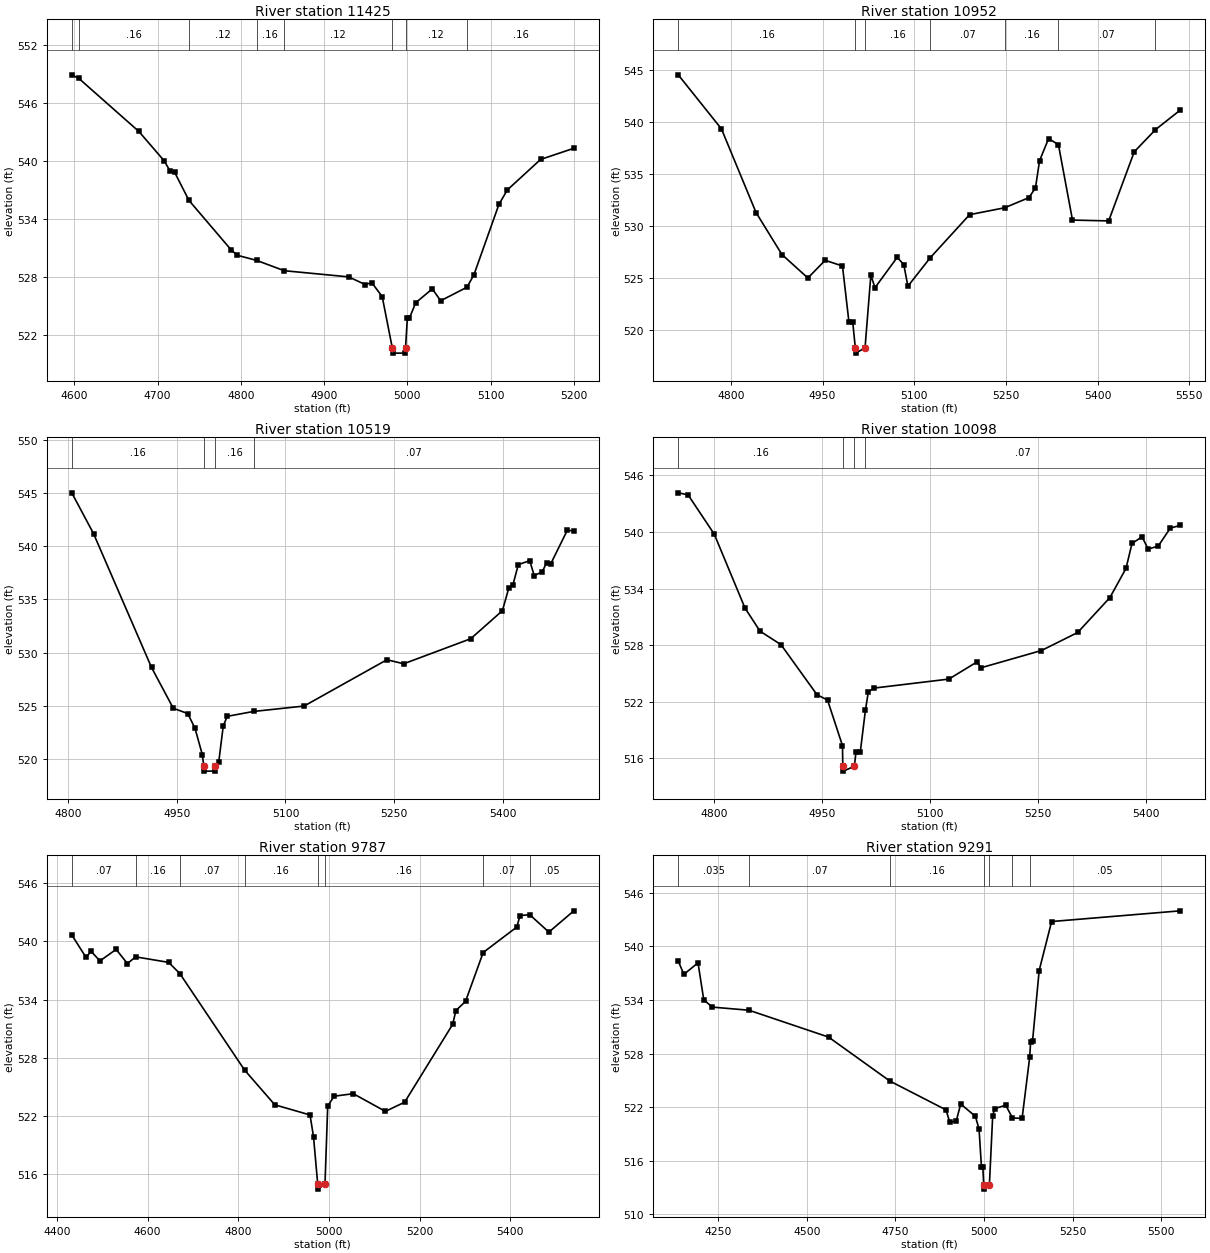
Type RM Length L Ch R = 1,11425,473,473,473
BEGIN DESCRIPTION:
LITTLE CREEK 13.0
END DESCRIPTION:
XS GIS Cut Line= 3
      2309624.99     13776525.00      2309225.00     13776575.00
      2309025.01     13776575.00
#Sta/Elev= 30
  4596.8  548.93  4605.4  548.55  4677.4  543.07  4707.7  540.04  4715.2  538.93
  4720.2  538.87  4737.6  535.93  4788.3  530.81  4795.8  530.25  4818.7  529.73
  4852.0  528.66  4929.4  528.02  4949.5  527.22  4957.1  527.43  4969.7  525.98
  4981.9  520.63  4982.4  520.13  4997.2  520.13  4997.7  520.63  4999.9  523.75
  5002.4  523.75  5009.9  525.34  5029.9  526.78  5039.9  525.55  5071.5  526.95
  5079.9  528.24  5109.9  535.52  5119.9  537.01  5159.9  540.17  5199.9  541.33
#Mann=8,-1,0
  4596.8    0.07       0  4605.4    0.16       0  4737.6    0.12       0
  4818.7    0.16       0  4852.0    0.12       0  4981.9    0.07       0
  4997.7    0.12       0  5071.5    0.16       0
Bank Sta=4981.9,4997.7
Exp/Cntr=0.3,0.1

Type RM Length L Ch R = 1,10952,433,433,433
BEGIN DESCRIPTION:
LITTLE CREEK 12.0
END DESCRIPTION:
XS GIS Cut Line= 3
      2309625.00     13775975.00      2309425.00     13776175.00
      2308924.96     13776375.02
#Sta/Elev= 30
  4713.8  544.51  4784.5  539.32  4841.1  531.29  4883.5  527.26  4925.9  525.01
  4954.2  526.71  4982.5  526.16  4993.1  520.77  4999.3  520.77  5003.5  518.30
  5004.0  517.80  5019.4  518.30  5028.9  525.28  5035.7  524.08  5072.0  526.99
  5082.8  526.30  5089.5  524.22  5126.0  526.95  5190.5  531.09  5247.8  531.75
  5287.4  532.72  5298.2  533.65  5304.9  536.26  5319.7  538.39  5335.8  537.81
  5358.8  530.57  5418.0  530.49  5459.8  537.12  5494.6  539.25  5535.2  541.13
#Mann=7,-1,0
  4713.8    0.16       0  5003.5    0.07       0  5019.4    0.16       0
  5126.0    0.07       0  5247.8    0.16       0  5335.8    0.07       0
  5494.6    0.16       0
Bank Sta=5003.5,5019.4
Exp/Cntr=0.3,0.1

Type RM Length L Ch R = 1,10519,421,421,421
BEGIN DESCRIPTION:
LITTLE CREEK 11.0
END DESCRIPTION:
XS GIS Cut Line= 3
      2309524.99     13775875.00      2309325.00     13775875.00
      2308875.03     13776074.99
#Sta/Elev= 30
  4805.3  545.04  4835.3  541.20  4915.3  528.59  4945.3  524.75  4965.3  524.25
  4975.3  522.85  4985.3  520.39  4987.3  519.33  4987.8  518.83  5002.8  518.83
  5003.3  519.33  5008.0  519.70  5014.2  523.08  5019.7  523.99  5056.0  524.45
  5125.7  524.96  5239.9  529.32  5263.1  528.94  5355.5  531.30  5399.2  533.94
  5408.1  536.11  5413.6  536.35  5421.1  538.28  5436.9  538.65  5443.0  537.25
  5454.0  537.60  5460.1  538.44  5465.6  538.32  5488.8  541.53  5497.7  541.43
#Mann=4,-1,0
  4805.3    0.16       0  4987.3    0.07       0  5003.3    0.16       0
  5056.0    0.07       0
Bank Sta=4987.3,5003.3
Exp/Cntr=0.3,0.1

Type RM Length L Ch R = 1,10098,311,311,311
BEGIN DESCRIPTION:
LITTLE CREEK 10.0
END DESCRIPTION:
XS GIS Cut Line= 3
      2309225.01     13775474.99      2309025.00     13775625.00
      2308825.01     13776024.98
#Sta/Elev= 30
  4750.0  544.15  4763.6  543.94  4800.0  539.77  4842.7  531.93  4863.6  529.48
  4892.7  528.05  4942.7  522.74  4957.3  522.18  4978.1  517.34  4978.5  515.14
  4979.0  514.64  4994.5  515.14  4996.9  516.68  5002.8  516.68  5010.0  521.14
  5014.0  523.05  5022.4  523.45  5125.8  524.40  5164.9  526.22  5170.5  525.60
  5254.4  527.43  5304.7  529.34  5349.4  533.04  5371.8  536.14  5380.1  538.78
  5394.1  539.49  5402.5  538.19  5416.5  538.50  5433.3  540.41  5447.2  540.70
#Mann=4,-1,0
  4750.0    0.16       0  4978.5    0.07       0  4994.5    0.16       0
  5010.0    0.07       0
Bank Sta=4978.5,4994.5
Exp/Cntr=0.3,0.1

Type RM Length L Ch R = 1,9787,496,496,496
BEGIN DESCRIPTION:
A19673
END DESCRIPTION:
XS GIS Cut Line= 3
      2309304.55     13775256.85      2308785.04     13775450.95
      2308391.16     13775839.13
#Sta/Elev= 30
  4432.7  540.68  4464.2  538.35  4475.3  538.98  4494.9  537.99  4530.5  539.18
  4555.5  537.72  4573.6  538.41  4646.4  537.84  4671.1  536.68  4813.8  526.71
  4880.6  523.11  4958.3  522.06  4966.0  519.81  4975.3  514.89  4975.8  514.39
  4991.3  514.89  4997.3  522.97  5011.4  524.00  5053.8  524.26  5124.6  522.43
  5167.0  523.38  5273.0  531.43  5280.1  532.86  5301.3  533.80  5340.3  538.86
  5414.4  541.49  5421.6  542.68  5442.9  542.77  5485.2  540.97  5540.3  543.17
#Mann=8,-1,0
  4432.7    0.07       0  4573.6    0.16       0  4671.1    0.07       0
  4813.8    0.16       0  4975.3    0.07       0  4991.3    0.16       0
  5340.3    0.07       0  5442.9    0.05       0
Bank Sta=4975.3,4991.3
Exp/Cntr=0.3,0.1

Type RM Length L Ch R = 1,9291,524,524,524
BEGIN DESCRIPTION:
A19672
END DESCRIPTION:
XS GIS Cut Line= 3
      2309304.54     13775005.68      2308476.78     13775228.31
      2307958.65     13775438.98
#Sta/Elev= 30
  4137.6  538.36  4153.5  536.87  4193.4  538.16  4209.6  534.02  4233.4  533.20
  4337.2  532.85  4561.7  529.84  4734.8  524.91  4893.1  521.68  4903.4  520.33
  4921.6  520.38  4934.5  522.34  4975.9  520.96  4986.3  519.53  4993.1  515.24
  4997.0  515.24  4999.5  513.30  5000.0  512.80  5015.5  513.30  5024.7  520.98
  5030.1  521.81  5061.5  522.21  5080.5  520.78  5107.7  520.72  5129.1  527.56
  5131.8  529.32  5137.2  529.39  5155.9  537.30  5191.0  542.79  5554.1  543.99
#Mann=7,-1,0
  4137.6   0.035       0  4337.2    0.07       0  4734.8    0.16       0
  4999.5    0.07       0  5015.5    0.16       0  5080.5    0.07       0
  5129.1    0.05       0
Bank Sta=4999.5,5015.5
Exp/Cntr=0.3,0.1

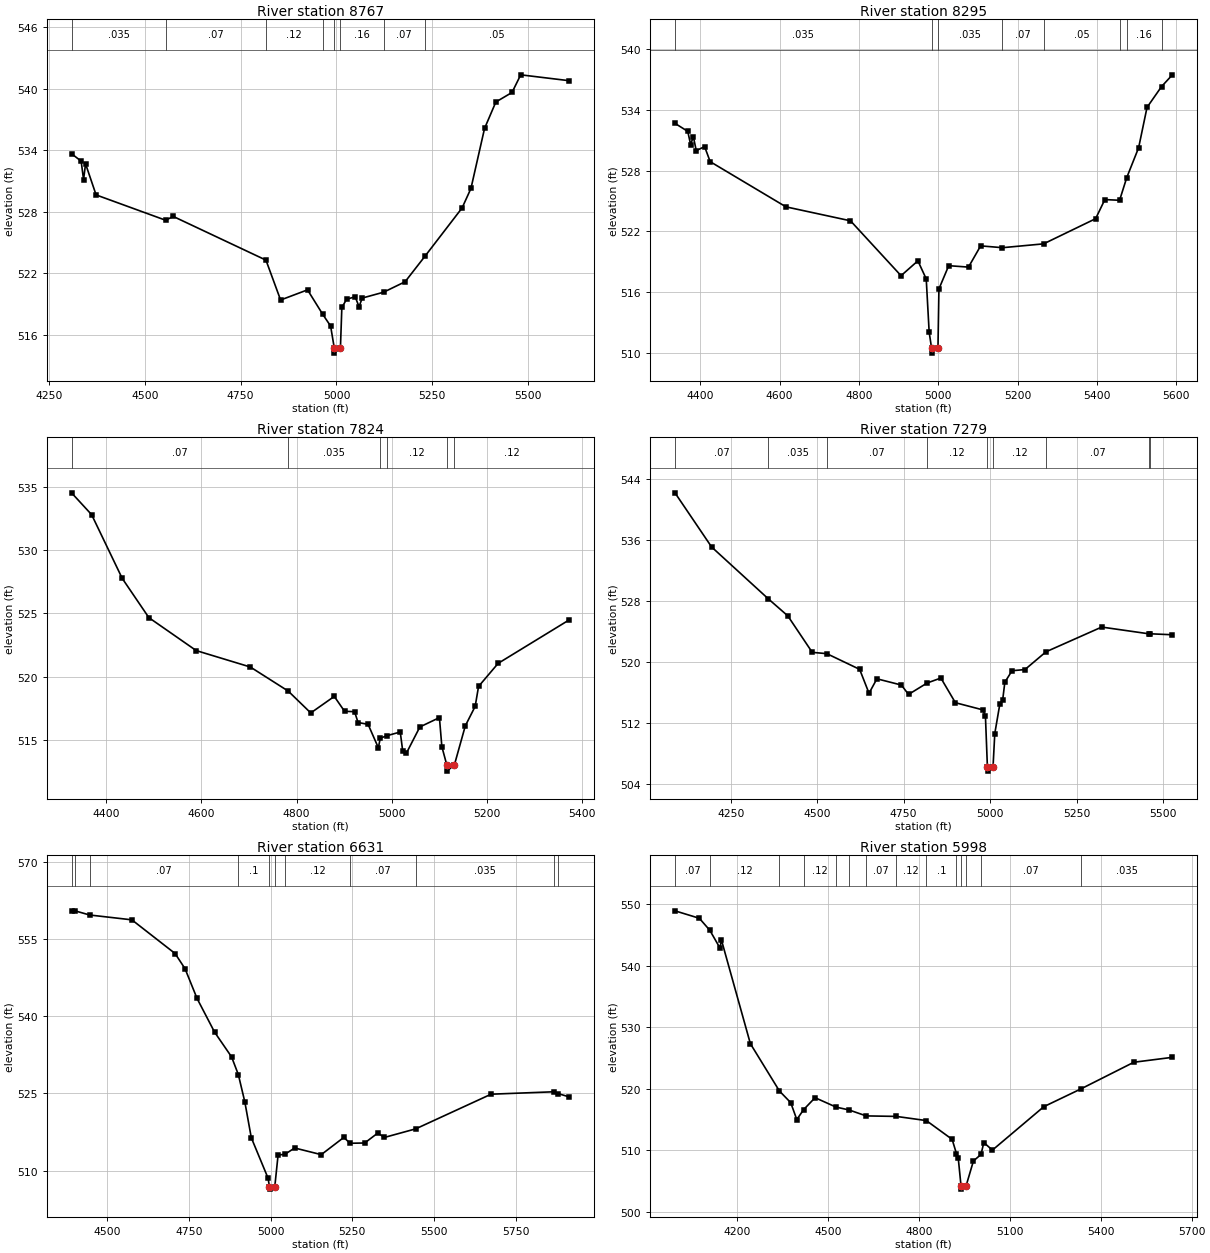
Type RM Length L Ch R = 1,8767,472,472,472
BEGIN DESCRIPTION:
LITTLE CREEK 9.0
END DESCRIPTION:
XS GIS Cut Line= 4
      2309148.97     13774899.57      2308683.52     13774756.31
      2308475.00     13774775.00      2307918.67     13775005.13
#Sta/Elev= 30
  4308.5  533.66  4333.6  532.93  4339.9  531.13  4345.1  532.67  4372.6  529.64
  4554.1  527.17  4574.0  527.54  4816.0  523.28  4854.2  519.39  4924.5  520.38
  4964.1  518.00  4984.8  516.85  4994.3  514.71  4994.8  514.21  5010.4  514.71
  5014.1  518.66  5026.5  519.46  5048.8  519.71  5059.0  518.74  5067.3  519.58
  5123.0  520.15  5179.2  521.17  5230.9  523.65  5328.0  528.37  5351.1  530.27
  5386.6  536.12  5416.1  538.70  5458.3  539.63  5481.0  541.35  5606.9  540.78
#Mann=8,-1,0
  4308.5   0.035       0  4554.1    0.07       0  4816.0    0.12       0
  4964.1    0.16       0  4994.3    0.07       0  5010.4    0.16       0
  5123.0    0.07       0  5230.9    0.05       0
Bank Sta=4994.3,5010.4
Exp/Cntr=0.3,0.1

Type RM Length L Ch R = 1,8295,471,471,471
BEGIN DESCRIPTION:
LITTLE CREEK 8.0
END DESCRIPTION:
XS GIS Cut Line= 3
      2309114.91     13774880.65      2308625.00     13774425.00
      2308074.98     13774224.99
#Sta/Elev= 30
  4336.1  532.67  4368.3  531.88  4375.6  530.57  4382.4  531.36  4389.8  529.97
  4410.8  530.37  4424.9  528.88  4616.0  524.41  4778.7  523.03  4906.2  517.60
  4948.7  519.07  4969.7  517.28  4977.1  512.01  4983.2  510.44  4983.7  509.94
  4999.3  510.44  5001.7  516.29  5026.4  518.59  5076.3  518.45  5106.9  520.55
  5162.0  520.37  5265.7  520.75  5396.9  523.24  5420.1  525.13  5457.3  525.06
  5475.4  527.31  5505.3  530.26  5526.5  534.25  5563.1  536.31  5590.4  537.47
#Mann=8,-1,0
  4336.1   0.035       0  4983.2   0.035       0  4999.3   0.035       0
  5162.0    0.07       0  5265.7    0.05       0  5457.3   0.035       0
  5475.4    0.16       0  5563.1   0.035       0
Bank Sta=4983.2,4999.3
Exp/Cntr=0.3,0.1

Type RM Length L Ch R = 1,7824,545,545,545
BEGIN DESCRIPTION:
LITTLE CREEK 7.0
END DESCRIPTION:
XS GIS Cut Line= 3
      2309274.98     13774524.99      2308775.00     13774075.00
      2308413.91     13773984.18
#Sta/Elev= 30
  4327.3  534.56  4369.5  532.83  4433.8  527.78  4489.8  524.67  4589.3  522.06
  4702.9  520.76  4782.6  518.85  4829.9  517.12  4879.3  518.43  4900.9  517.25
  4921.9  517.22  4929.3  516.36  4950.3  516.22  4971.9  514.36  4975.9  515.12
  4991.1  515.33  5017.9  515.61  5023.1  514.10  5030.9  513.94  5059.1  516.01
  5100.2  516.75  5105.3  514.45  5115.6  513.01  5116.1  512.51  5131.7  513.01
  5154.6  516.10  5175.3  517.64  5182.4  519.22  5223.6  521.05  5372.3  524.48
#Mann=6,-1,0
  4327.3    0.07       0  4782.6   0.035       0  4975.9    0.07       0
  4991.1    0.12       0  5115.6    0.05       0  5131.7    0.12       0
Bank Sta=5115.6,5131.7
Exp/Cntr=0.3,0.1

Type RM Length L Ch R = 1,7279,648,648,648
BEGIN DESCRIPTION:
A19671
END DESCRIPTION:
XS GIS Cut Line= 3
      2309829.72     13774377.73      2308962.01     13773715.53
      2308628.56     13773811.46
#Sta/Elev= 30
  4088.6  542.22  4194.6  535.11  4358.9  528.29  4414.9  526.07  4485.6  521.28
  4527.7  521.11  4622.7  519.05  4649.8  515.91  4672.6  517.81  4743.3  516.99
  4764.1  515.76  4818.0  517.26  4857.6  517.91  4899.6  514.67  4978.2  513.74
  4986.4  512.99  4992.2  506.19  4992.7  505.69  5008.4  506.19  5013.5  510.62
  5028.1  514.49  5036.3  515.02  5042.6  517.36  5063.4  518.87  5100.7  519.02
  5161.5  521.35  5322.7  524.60  5459.8  523.71  5461.5  523.72  5527.1  523.59
#Mann=9,-1,0
  4088.6    0.07       0  4358.9   0.035       0  4527.7    0.07       0
  4818.0    0.12       0  4992.2    0.05       0  5008.4    0.12       0
  5161.5    0.07       0  5459.8    0.12       0  5461.5    0.07       0
Bank Sta=4992.2,5008.4
Exp/Cntr=0.3,0.1

Type RM Length L Ch R = 1,6631,633,633,633
BEGIN DESCRIPTION:
A19670
END DESCRIPTION:
XS GIS Cut Line= 3
      2310126.59     13773738.37      2309019.10     13773538.56
      2308665.15     13773715.54
#Sta/Elev= 30
  4391.4  560.47  4403.0  560.45  4446.7  559.66  4575.9  558.72  4708.0  552.18
  4738.5  549.23  4775.3  543.44  4828.8  536.91  4880.8  532.10  4901.5  528.66
  4921.4  523.33  4941.1  516.40  4992.5  508.52  4996.5  506.91  4997.0  506.41
  5013.0  506.91  5023.0  513.03  5043.9  513.18  5073.8  514.40  5155.1  513.11
  5224.1  516.46  5243.0  515.32  5287.8  515.37  5327.9  517.30  5348.2  516.45
  5444.0  518.12  5674.4  524.85  5866.2  525.32  5879.9  524.96  5912.5  524.34
#Mann=11,-1,0
  4391.4    0.07       0  4403.0    0.05       0  4446.7    0.07       0
  4901.5     0.1       0  4996.5    0.05       0  5013.0     0.1       0
  5043.9    0.12       0  5243.0    0.07       0  5444.0   0.035       0
  5866.2    0.07       0  5879.9   0.035       0
Bank Sta=4996.5,5013
Exp/Cntr=0.3,0.1

Type RM Length L Ch R = 1,5998,642,642,642
BEGIN DESCRIPTION:
LITTLE CREEK 6.0
END DESCRIPTION:
XS GIS Cut Line= 3
      2310225.05     13773075.00      2309225.00     13773175.00
      2308775.02     13773624.98
#Sta/Elev= 30
  3995.0  548.94  4075.4  547.73  4110.1  545.77  4143.3  542.91  4148.3  544.21
  4243.8  527.35  4339.8  519.65  4376.9  517.77  4397.0  515.02  4419.9  516.65
  4457.3  518.57  4526.7  517.04  4569.3  516.58  4626.0  515.61  4725.2  515.53
  4824.5  514.85  4909.6  511.80  4923.8  509.50  4929.7  508.80  4939.0  504.21
  4939.5  503.71  4955.5  504.21  4979.9  508.29  5004.8  509.34  5014.2  511.28
  5042.5  510.05  5212.2  517.11  5334.3  519.99  5509.2  524.33  5636.4  525.13
#Mann=14,-1,0
  3995.0    0.07       0  4110.1    0.12       0  4339.8    0.07       0
  4419.9    0.12       0  4526.7    0.07       0  4569.3    0.12       0
  4626.0    0.07       0  4725.2    0.12       0  4824.5     0.1       0
  4923.8    0.12       0  4939.0    0.05       0  4955.5    0.12       0
  5004.8    0.07       0  5334.3   0.035       0
Bank Sta=4939,4955.5
Exp/Cntr=0.3,0.1

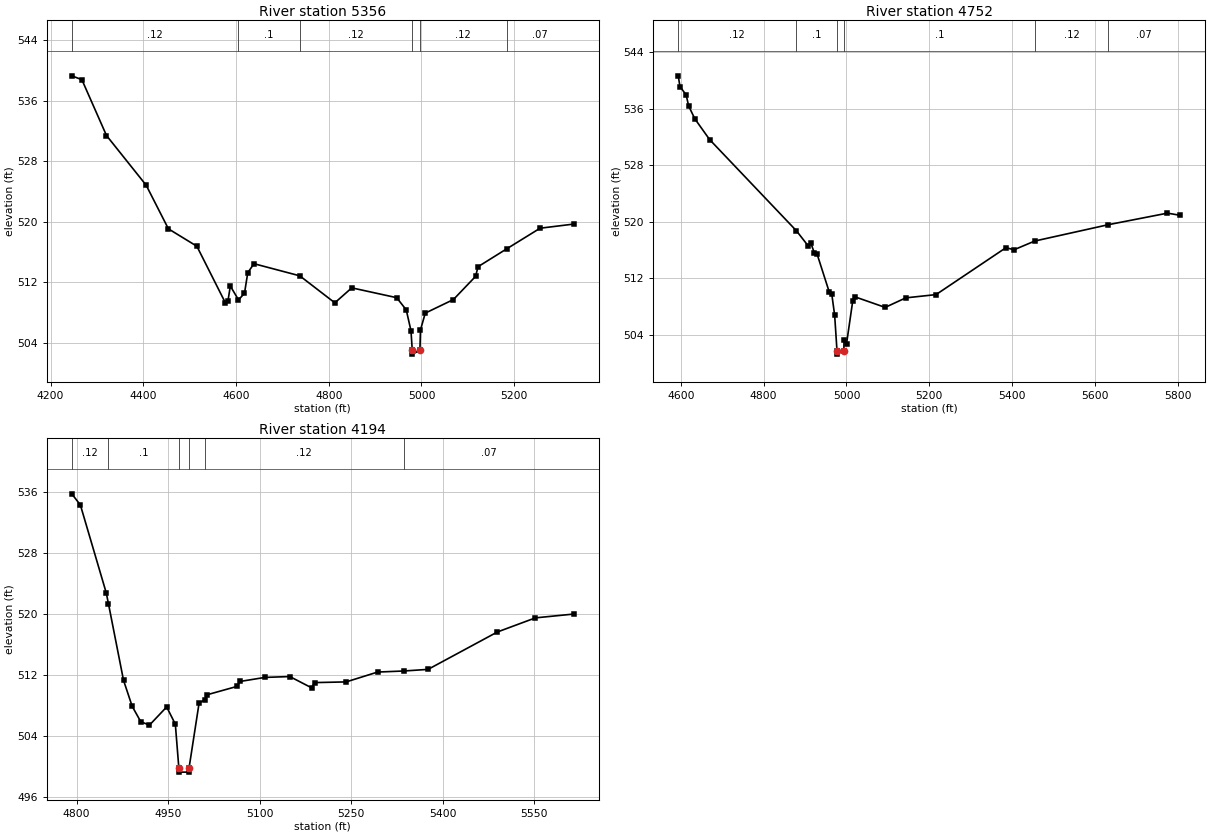
Type RM Length L Ch R = 1,5356,604,604,604
BEGIN DESCRIPTION:
A19669
END DESCRIPTION:
XS GIS Cut Line= 3
      2310137.96     13773015.65      2309270.28     13772815.85
      2309092.32     13772742.42
#Sta/Elev= 30
  4245.7  539.27  4267.5  538.76  4320.6  531.38  4406.2  524.81  4454.1  519.05
  4515.5  516.75  4577.1  509.26  4582.5  509.50  4587.7  511.49  4605.3  509.66
  4618.2  510.53  4625.3  513.25  4638.7  514.44  4737.4  512.84  4813.1  509.27
  4849.6  511.25  4946.5  509.95  4967.1  508.34  4977.3  505.59  4980.1  502.99
  4980.6  502.49  4996.6  502.99  4997.8  505.68  5008.1  507.91  5068.8  509.70
  5116.7  512.77  5121.9  514.04  5183.4  516.39  5255.8  519.13  5328.6  519.68
#Mann=6,-1,0
  4245.7    0.12       0  4605.3     0.1       0  4737.4    0.12       0
  4980.1    0.05       0  4996.6    0.12       0  5183.4    0.07       0
Bank Sta=4980.1,4996.6
Exp/Cntr=0.3,0.1

Type RM Length L Ch R = 1,4752,558,558,558
BEGIN DESCRIPTION:
A19668
END DESCRIPTION:
XS GIS Cut Line= 3
      2310234.99     13772981.38      2309726.97     13772627.47
      2309134.07     13772653.25
#Sta/Elev= 30
  4593.7  540.64  4597.9  539.11  4612.8  537.94  4618.9  536.36  4633.7  534.56
  4669.5  531.61  4879.3  518.68  4907.7  516.54  4913.8  516.97  4922.6  515.53
  4928.7  515.46  4958.4  510.02  4964.4  509.78  4971.5  506.72  4977.1  501.72
  4977.6  501.22  4993.7  501.72  4994.1  503.17  5000.2  502.70  5015.1  508.73
  5021.2  509.32  5093.4  507.84  5143.3  509.19  5216.3  509.65  5385.0  516.29
  5405.0  516.01  5454.8  517.24  5632.1  519.55  5775.3  521.19  5806.3  520.88
#Mann=6,-1,0
  4593.7    0.12       0  4879.3     0.1       0  4977.1    0.05       0
  4993.7     0.1       0  5454.8    0.12       0  5632.1    0.07       0
Bank Sta=4977.1,4993.7
Exp/Cntr=0.3,0.1

Type RM Length L Ch R = 1,4194,0,0,0
BEGIN DESCRIPTION:
LITTLE CREEK 5.0
END DESCRIPTION:
XS GIS Cut Line= 3
      2309824.98     13772225.02      2309675.00     13772375.00
      2309083.59     13772526.83
#Sta/Elev= 30
  4792.1  535.72  4806.2  534.26  4848.6  522.74  4852.2  521.33  4876.9  511.29
  4891.1  507.88  4905.2  505.86  4919.4  505.42  4947.6  507.80  4961.8  505.54
  4967.6  499.76  4968.1  499.26  4983.7  499.26  4984.2  499.76  5000.7  508.30
  5009.9  508.75  5014.5  509.41  5062.8  510.49  5067.9  511.14  5108.7  511.67
  5149.4  511.78  5185.0  510.31  5190.2  510.99  5241.7  511.08  5293.3  512.37
  5336.3  512.51  5375.9  512.72  5489.5  517.62  5551.8  519.47  5614.8  519.97
#Mann=6,-1,0
  4792.1    0.12       0  4852.2     0.1       0  4967.6    0.05       0
  4984.2     0.1       0  5009.9    0.12       0  5336.3    0.07       0
Bank Sta=4967.6,4984.2
Exp/Cntr=0.3,0.1

Chan Stop Cuts=-1