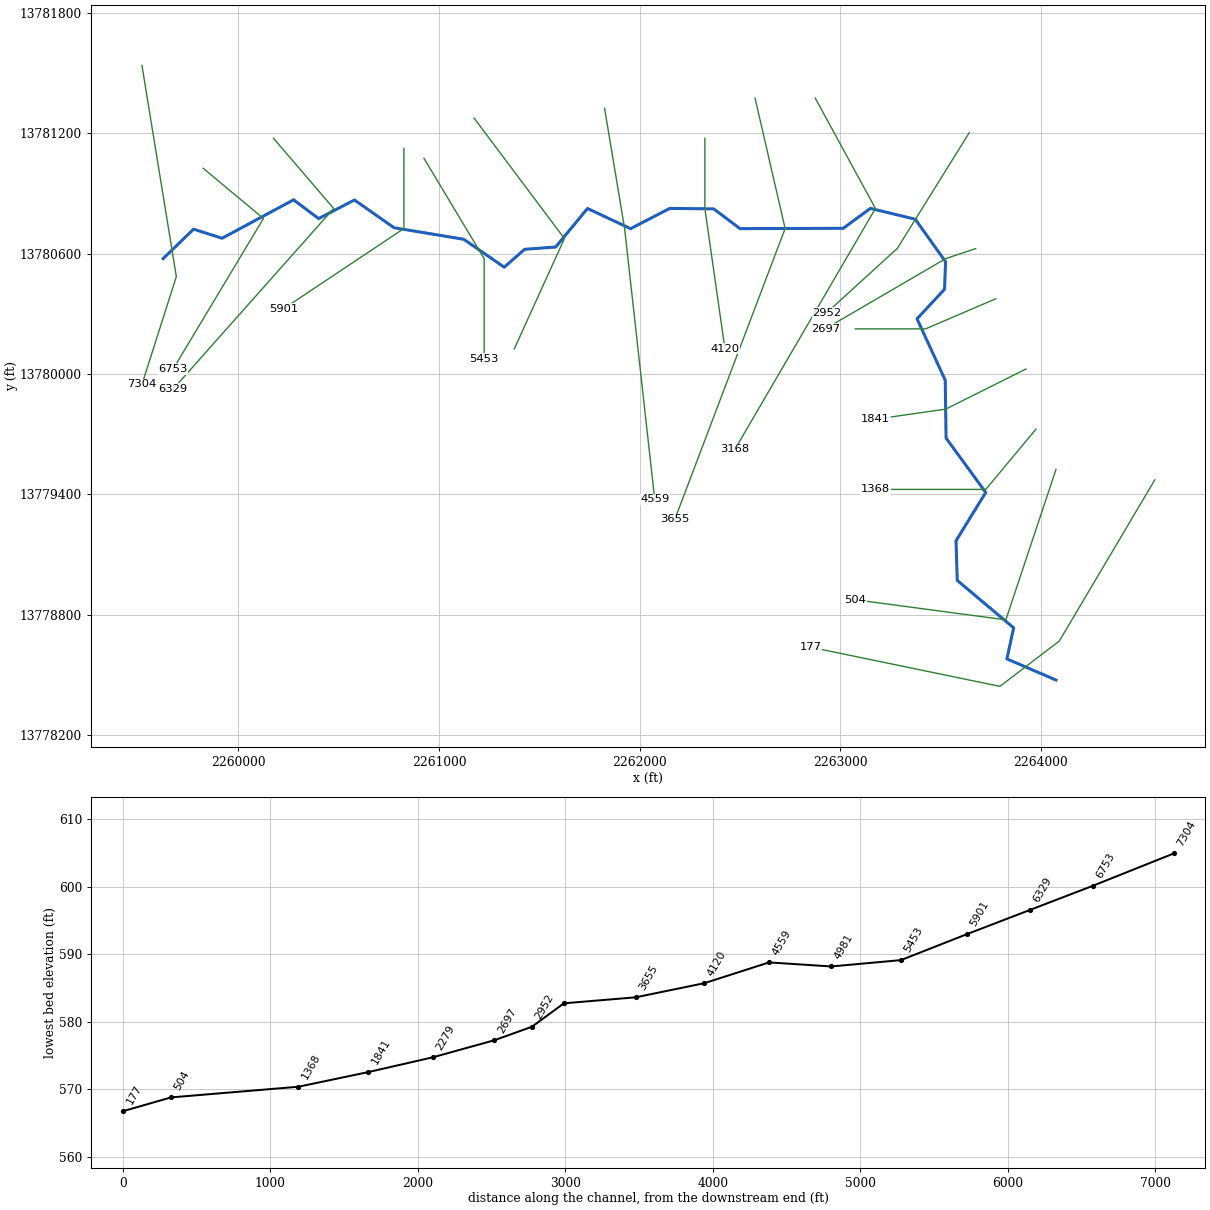
--- LONG BRANCH TRIBUTARY 2 2.prj (project) ---

Proj Title=LONG BRANCH TRIBUTARY 2 2 Base Level Engineering
Current Plan=p01
Default Exp/Contr=0.3,0.1
English Units
Geom File=g01
Flow File=f01
Plan File=p01
BEGIN DESCRIPTION:
LONG BRANCH TRIBUTARY 2 2
END DESCRIPTION:

--- LONG BRANCH TRIBUTARY 2 2.p01 (plan) ---

Plan Title=Multiple Run
Short Identifier=Multiple
Geom File=g01
Flow File=f01
Subcritical Flow
K Sum by GR= 0
Std Step Tol= 0.01
Critical Tol= 0.01
Num of Std Step Trials= 20
Max Error Tol= 0.3
Flow Tol Ratio= 0.001
Split Flow NTrial= 30
Split Flow Tol= 0.02
Split Flow Ratio= 0.02
Log Output Level= 0
Friction Slope Method= 1
Unsteady Friction Slope Method= 2
Unsteady Bridges Friction Slope Method= 1
Parabolic Critical Depth
Global Vel Dist=  1 , 1 , 1
Global Log Level= 0
CheckData=True
Encroach Param= -1, 0, 0, 0
BEGIN DESCRIPTION:
Multiple Run
END DESCRIPTION:

--- LONG BRANCH TRIBUTARY 2 2.f01 (steady flow) ---

Flow Title=Multiple
Number of Profiles=7
Profile Names=10-year,25-year,50-year,1pct_min,100-year,1pct_plu,500-year
River Rch & RM= LONG BRANCH TRIB,Reach-1,7304
     701    1136    1531     999    1993    3976    3341
River Rch & RM= LONG BRANCH TRIB,Reach-1,4981
     910    1494    2030    1334    2662    5312    4531
Boundary for River Rch & Prof#=LONG BRANCH TRIB,Reach-1,1
Up Type=0
Dn Type=3
Dn Slope=0.005
Boundary for River Rch & Prof#=LONG BRANCH TRIB,Reach-1,2
Up Type=0
Dn Type=3
Dn Slope=0.005
Boundary for River Rch & Prof#=LONG BRANCH TRIB,Reach-1,3
Up Type=0
Dn Type=3
Dn Slope=0.005
Boundary for River Rch & Prof#=LONG BRANCH TRIB,Reach-1,4
Up Type=0
Dn Type=3
Dn Slope=0.005
Boundary for River Rch & Prof#=LONG BRANCH TRIB,Reach-1,5
Up Type=0
Dn Type=3
Dn Slope=0.005
Boundary for River Rch & Prof#=LONG BRANCH TRIB,Reach-1,6
Up Type=0
Dn Type=3
Dn Slope=0.005
Boundary for River Rch & Prof#=LONG BRANCH TRIB,Reach-1,7
Up Type=0
Dn Type=3
Dn Slope=0.005

--- LONG BRANCH TRIBUTARY 2 2.g01 (geometry) ---

Geom Title=Existing Conditions

River Reach=LONG BRANCH TRIB,Reach-1
Reach XY= 30
      2259625.00     13780575.00      2259776.63     13780721.88
      2259918.96     13780676.63      2260275.00     13780867.90
      2260399.97     13780774.50      2260578.40     13780867.22
      2260776.55     13780728.75      2261123.50     13780671.38
      2261325.08     13780532.30      2261426.47     13780621.43
      2261581.21     13780632.81      2261740.09     13780824.82
      2261954.93     13780724.32      2262149.88     13780825.29
      2262369.14     13780822.93      2262499.97     13780724.52
      2263014.56     13780726.06      2263149.96     13780825.49
      2263373.52     13780771.39      2263524.51     13780559.78
      2263519.55     13780422.55      2263382.32     13780275.10
      2263522.93     13779969.14      2263527.06     13779680.86
      2263724.76     13779409.78      2263576.62     13779168.96
      2263582.82     13778971.59      2263863.91     13778735.08
      2263830.10     13778580.44      2264075.00     13778475.00

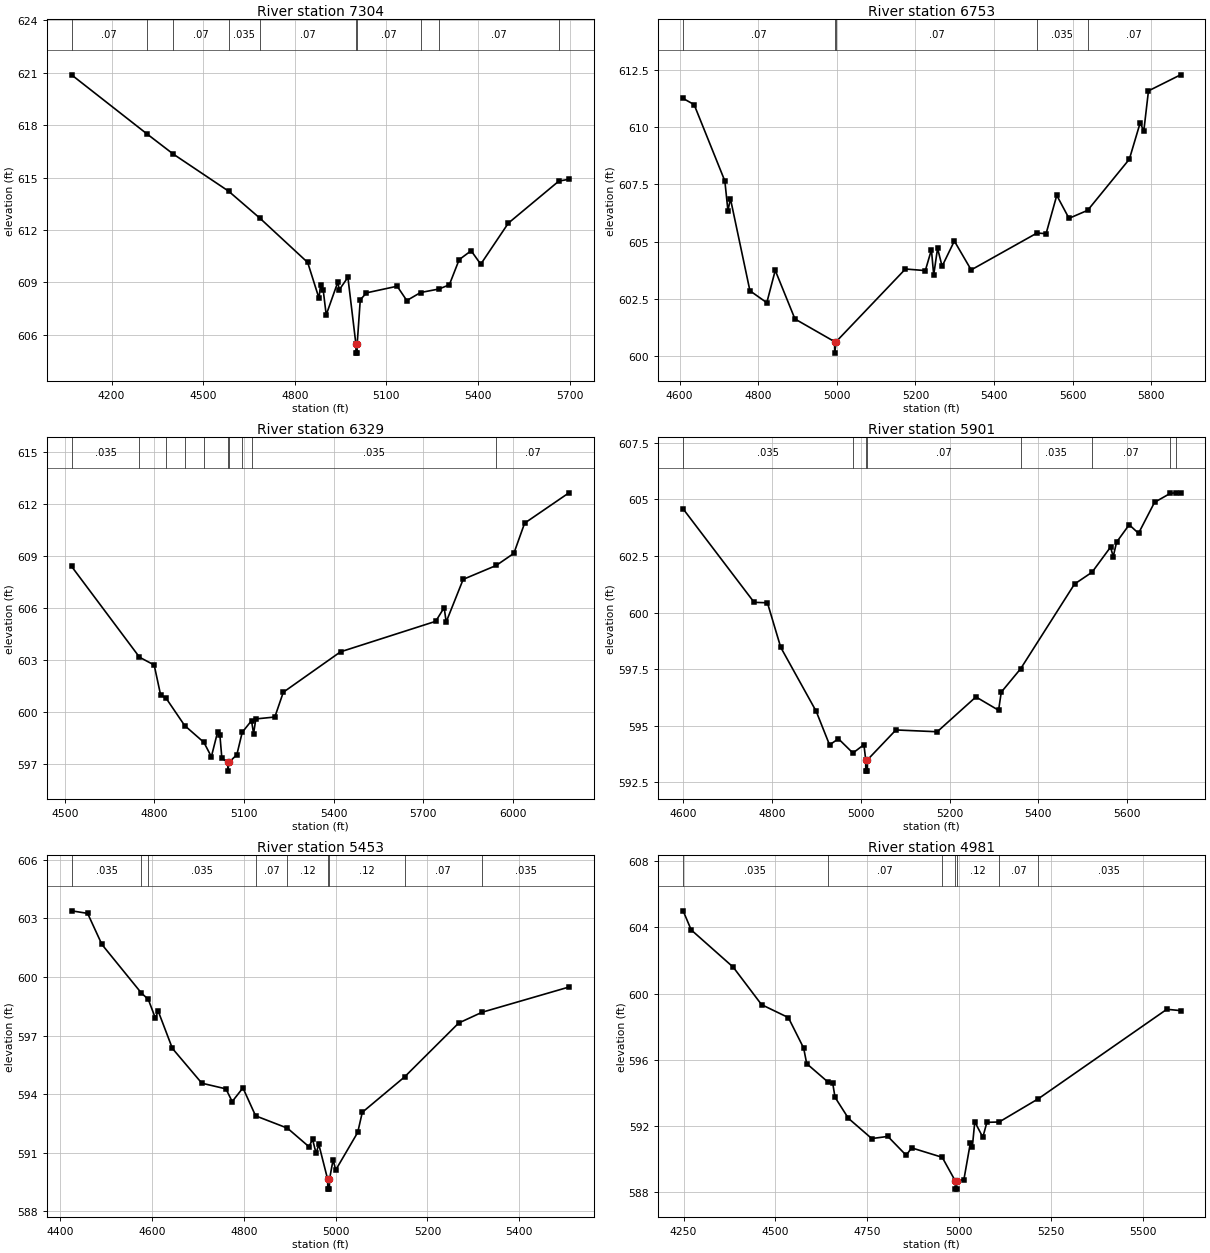
Type RM Length L Ch R = 1,7304,551,551,551
BEGIN DESCRIPTION:
A19751
END DESCRIPTION:
XS GIS Cut Line= 3
      2259519.41     13781538.09      2259690.90     13780485.78
      2259520.03     13779949.85
#Sta/Elev= 30
  4069.0  620.88  4315.1  617.51  4402.4  616.34  4583.3  614.22  4686.0  612.67
  4842.2  610.14  4879.3  608.09  4884.3  608.85  4892.8  608.59  4902.9  607.14
  4940.7  609.01  4945.8  608.58  4973.9  609.29  5000.2  605.45  5000.5  604.95
  5004.0  604.95  5004.2  605.45  5014.4  608.00  5034.7  608.40  5135.2  608.78
  5166.7  607.96  5212.0  608.42  5272.1  608.62  5306.0  608.86  5338.2  610.30
  5377.4  610.81  5408.9  610.04  5499.2  612.39  5664.8  614.80  5697.7  614.90
#Mann=10,-1,0
  4069.0    0.07       0  4315.1   0.035       0  4402.4    0.07       0
  4583.3   0.035       0  4686.0    0.07       0  5000.2    0.05       0
  5004.2    0.07       0  5212.0   0.035       0  5272.1    0.07       0
  5664.8   0.035       0
Bank Sta=5000.2,5004.2
Exp/Cntr=0.3,0.1

Type RM Length L Ch R = 1,6753,424,424,424
BEGIN DESCRIPTION:
LONG BRANCH TRIBUTARY 2 2 14.0
END DESCRIPTION:
XS GIS Cut Line= 3
      2259825.01     13781024.99      2260125.00     13780775.00
      2259675.02     13780025.04
#Sta/Elev= 30
  4609.1  611.25  4637.1  610.98  4715.2  607.65  4723.0  606.36  4729.5  606.87
  4779.0  602.86  4821.9  602.34  4843.4  603.75  4893.5  601.63  4994.3  600.64
  4994.6  600.14  4998.3  600.64  5174.5  603.81  5225.1  603.74  5240.6  604.65
  5246.4  603.55  5256.2  604.71  5267.8  603.93  5298.9  605.03  5341.7  603.77
  5509.2  605.38  5532.2  605.35  5559.4  607.02  5590.5  606.02  5638.0  606.37
  5744.0  608.60  5771.2  610.17  5780.9  609.85  5792.6  611.58  5874.2  612.28
#Mann=5,-1,0
  4609.1    0.07       0  4994.3    0.05       0  4998.3    0.07       0
  5509.2   0.035       0  5638.0    0.07       0
Bank Sta=4994.3,4998.3
Exp/Cntr=0.3,0.1

Type RM Length L Ch R = 1,6329,428,428,428
BEGIN DESCRIPTION:
LONG BRANCH TRIBUTARY 2 2 13.0
END DESCRIPTION:
XS GIS Cut Line= 3
      2260175.01     13781174.99      2260475.00     13780825.00
      2259675.02     13779925.02
#Sta/Elev= 30
  4522.4  608.39  4749.9  603.15  4799.0  602.70  4820.4  600.99  4839.5  600.77
  4901.0  599.21  4965.4  598.24  4990.5  597.41  5011.4  598.84  5018.9  598.68
  5025.6  597.33  5045.3  597.08  5045.6  596.58  5049.3  597.08  5075.8  597.53
  5093.8  598.82  5124.9  599.49  5131.8  598.74  5139.3  599.59  5202.9  599.70
  5231.3  601.13  5422.8  603.46  5741.4  605.22  5769.8  606.01  5776.5  605.18
  5833.4  607.64  5943.9  608.44  6003.1  609.14  6039.1  610.88  6187.5  612.63
#Mann=10,-1,0
  4522.4   0.035       0  4749.9   0.063       0  4839.5   0.035       0
  4901.0   0.063       0  4965.4   0.035       0  5045.3   0.035       0
  5049.3   0.035       0  5093.8   0.063       0  5124.9   0.035       0
  5943.9    0.07       0
Bank Sta=5045.3,5049.3
Exp/Cntr=0.3,0.1

Type RM Length L Ch R = 1,5901,448,448,448
BEGIN DESCRIPTION:
LONG BRANCH TRIBUTARY 2 2 12.0
END DESCRIPTION:
XS GIS Cut Line= 3
      2260825.00     13781124.98      2260825.00     13780725.00
      2260224.99     13780324.99
#Sta/Elev= 30
  4599.3  604.58  4759.3  600.45  4789.3  600.43  4819.3  598.46  4899.3  595.63
  4929.3  594.15  4949.3  594.42  4982.0  593.79  5006.8  594.16  5010.8  593.49
  5011.0  592.99  5014.5  592.99  5014.8  593.49  5078.9  594.81  5172.0  594.73
  5259.2  596.27  5310.3  595.68  5316.3  596.48  5360.2  597.52  5481.5  601.26
  5520.9  601.78  5562.6  602.89  5568.7  602.47  5576.2  603.11  5604.7  603.88
  5625.7  603.50  5661.8  604.87  5697.6  605.27  5709.6  605.29  5720.4  605.29
#Mann=8,-1,0
  4599.3   0.035       0  4982.0    0.07       0  5010.8    0.05       0
  5014.8    0.07       0  5360.2   0.035       0  5520.9    0.07       0
  5697.6   0.035       0  5709.6    0.07       0
Bank Sta=5010.8,5014.8
Exp/Cntr=0.3,0.1

Type RM Length L Ch R = 1,5453,472,472,472
BEGIN DESCRIPTION:
LONG BRANCH TRIBUTARY 2 2 11.0
END DESCRIPTION:
XS GIS Cut Line= 3
      2260925.01     13781074.98      2261225.00     13780575.00
      2261225.00     13780074.97
#Sta/Elev= 30
  4425.1  603.38  4460.1  603.25  4491.2  601.66  4577.3  599.17  4592.2  598.85
  4607.8  597.88  4613.6  598.26  4644.7  596.34  4708.8  594.56  4761.3  594.27
  4774.9  593.62  4798.3  594.32  4825.9  592.89  4895.2  592.26  4942.1  591.31
  4949.9  591.69  4957.6  590.97  4963.5  591.43  4982.8  589.64  4983.1  589.14
  4986.6  589.14  4986.8  589.64  4994.6  590.64  5000.4  590.12  5048.2  592.04
  5058.2  593.07  5150.2  594.88  5268.2  597.64  5319.0  598.19  5508.2  599.48
#Mann=9,-1,0
  4425.1   0.035       0  4577.3    0.07       0  4592.2   0.035       0
  4825.9    0.07       0  4895.2    0.12       0  4982.8    0.05       0
  4986.8    0.12       0  5150.2    0.07       0  5319.0   0.035       0
Bank Sta=4982.8,4986.8
Exp/Cntr=0.3,0.1

Type RM Length L Ch R = 1,4981,422,422,422
BEGIN DESCRIPTION:
LONG BRANCH TRIBUTARY 2 2 10.0
END DESCRIPTION:
XS GIS Cut Line= 3
      2261175.01     13781274.99      2261625.00     13780675.00
      2261375.01     13780125.03
#Sta/Elev= 30
  4248.7  604.99  4270.6  603.84  4385.1  601.59  4462.2  599.33  4535.1  598.55
  4576.8  596.71  4585.1  595.77  4642.0  594.68  4656.0  594.58  4662.2  593.74
  4698.7  592.47  4762.2  591.25  4806.0  591.38  4856.0  590.24  4870.6  590.69
  4954.0  590.12  4989.4  588.70  4989.6  588.20  4993.1  588.20  4993.4  588.70
  5013.0  588.77  5030.5  590.97  5036.0  590.74  5042.6  592.26  5064.6  591.33
  5075.6  592.23  5109.0  592.25  5215.5  593.65  5565.5  599.05  5602.8  598.97
#Mann=7,-1,0
  4248.7   0.035       0  4642.0    0.07       0  4954.0    0.12       0
  4989.4    0.05       0  4993.4    0.12       0  5109.0    0.07       0
  5215.5   0.035       0
Bank Sta=4989.4,4993.4
Exp/Cntr=0.3,0.1

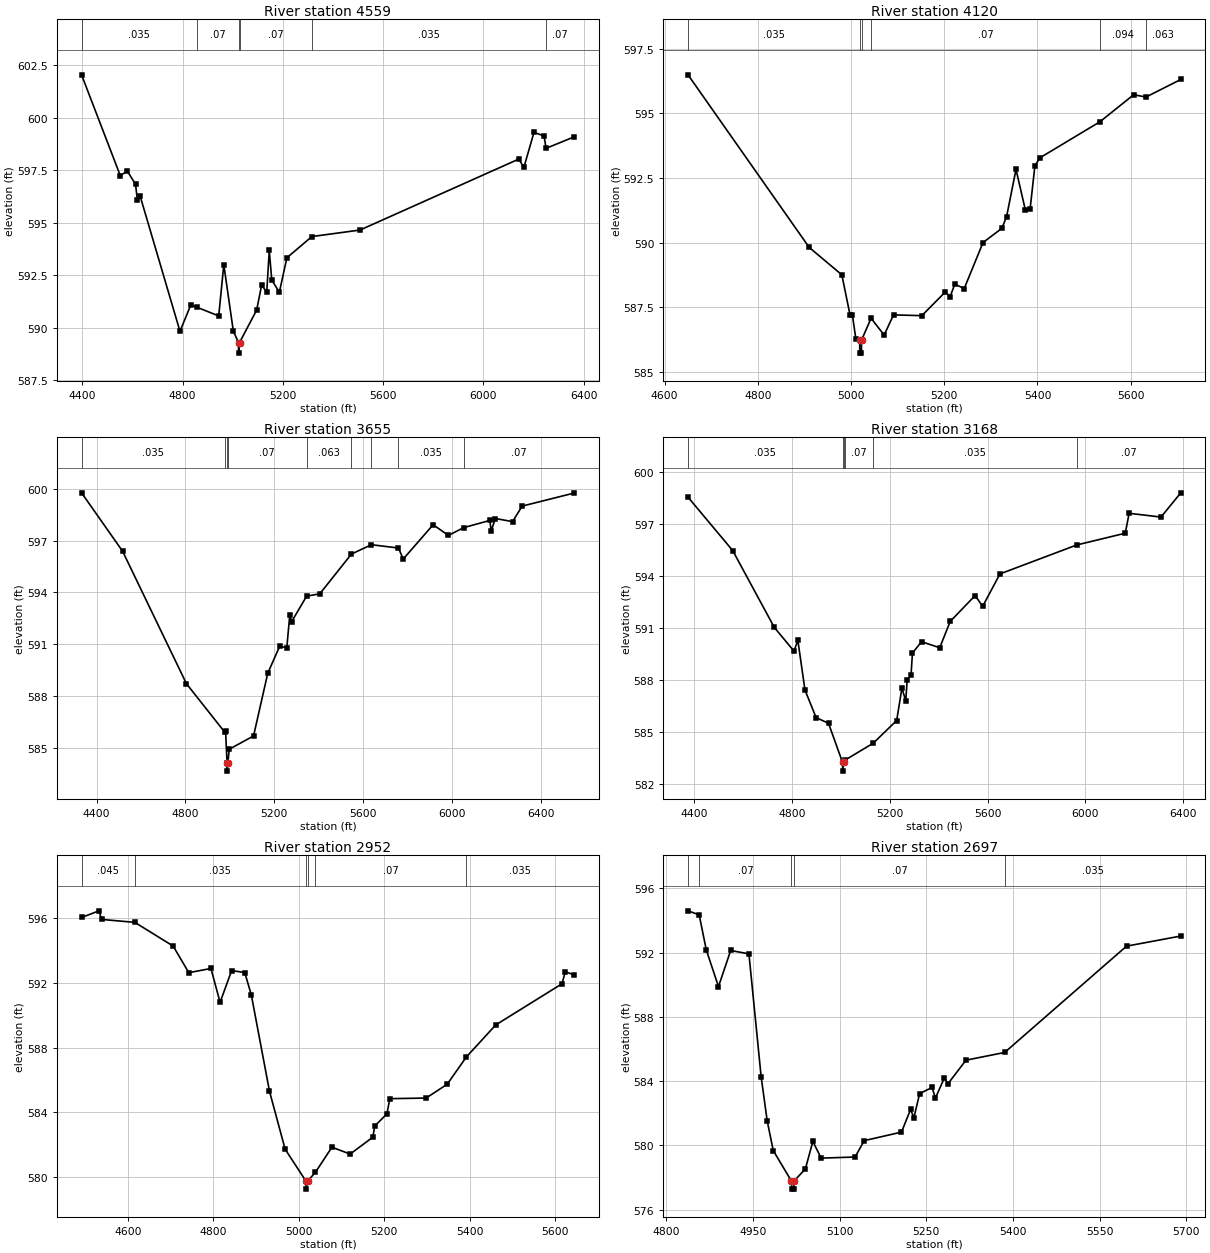
Type RM Length L Ch R = 1,4559,439,439,439
BEGIN DESCRIPTION:
LONG BRANCH TRIBUTARY 2 2 9.0
END DESCRIPTION:
XS GIS Cut Line= 3
      2261825.00     13781324.98      2261925.00     13780725.00
      2262075.00     13779374.96
#Sta/Elev= 30
  4396.4  602.05  4551.0  597.25  4578.9  597.47  4611.8  596.84  4619.4  596.07
  4629.6  596.30  4789.2  589.84  4832.3  591.09  4855.8  590.99  4943.8  590.57
  4964.1  593.01  5002.1  589.85  5022.8  589.30  5023.0  588.80  5026.8  589.30
  5095.2  590.85  5115.3  592.05  5135.5  591.69  5145.5  593.69  5155.6  592.28
  5185.8  591.70  5215.9  593.34  5315.6  594.35  5507.7  594.66  6141.6  598.04
  6161.7  597.64  6202.0  599.31  6242.2  599.14  6250.3  598.55  6363.0  599.10
#Mann=6,-1,0
  4396.4   0.035       0  4855.8    0.07       0  5022.8    0.05       0
  5026.8    0.07       0  5315.6   0.035       0  6250.3    0.07       0
Bank Sta=5022.8,5026.8
Exp/Cntr=0.3,0.1

Type RM Length L Ch R = 1,4120,465,465,465
BEGIN DESCRIPTION:
LONG BRANCH TRIBUTARY 2 2 8.0
END DESCRIPTION:
XS GIS Cut Line= 3
      2262325.00     13781175.04      2262325.00     13780825.00
      2262424.99     13780125.04
#Sta/Elev= 30
  4650.4  596.49  4910.4  589.81  4980.4  588.75  4997.9  587.20  5003.0  587.20
  5010.5  586.26  5018.6  586.22  5018.9  585.72  5022.4  585.72  5022.6  586.22
  5043.1  587.07  5071.1  586.42  5091.3  587.20  5152.0  587.17  5202.5  588.09
  5212.6  587.90  5222.7  588.39  5242.9  588.22  5283.3  590.00  5323.7  590.55
  5333.8  591.00  5354.0  592.83  5374.2  591.25  5384.3  591.30  5394.4  592.95
  5404.5  593.27  5533.8  594.67  5606.5  595.72  5632.8  595.63  5707.5  596.31
#Mann=6,-1,0
  4650.4   0.035       0  5018.6   0.035       0  5022.6   0.035       0
  5043.1    0.07       0  5533.8   0.094       0  5632.8   0.063       0
Bank Sta=5018.6,5022.6
Exp/Cntr=0.3,0.1

Type RM Length L Ch R = 1,3655,487,487,487
BEGIN DESCRIPTION:
LONG BRANCH TRIBUTARY 2 2 7.0
END DESCRIPTION:
XS GIS Cut Line= 3
      2262574.99     13781375.04      2262725.00     13780725.00
      2262175.01     13779275.03
#Sta/Elev= 30
  4332.5  599.77  4517.3  596.38  4804.6  588.70  4976.3  585.90  4980.8  585.94
  4987.3  584.13  4987.6  583.63  4991.4  584.13  4997.1  584.90  5106.6  585.67
  5170.7  589.31  5224.2  590.87  5256.3  590.79  5269.9  592.71  5277.7  592.29
  5345.7  593.78  5404.6  593.91  5547.3  596.22  5637.2  596.76  5758.8  596.57
  5780.4  595.93  5915.0  597.92  5983.6  597.30  6052.2  597.75  6170.3  598.17
  6176.1  597.55  6195.1  598.28  6272.4  598.10  6315.6  599.00  6550.4  599.76
#Mann=9,-1,0
  4332.5   0.035       0  4976.3    0.07       0  4987.3    0.05       0
  4991.4    0.07       0  5345.7   0.063       0  5547.3   0.035       0
  5637.2   0.063       0  5758.8   0.035       0  6052.2    0.07       0
Bank Sta=4987.3,4991.4
Exp/Cntr=0.3,0.1

Type RM Length L Ch R = 1,3168,216,216,216
BEGIN DESCRIPTION:
LONG BRANCH TRIBUTARY 2 2 6.0
END DESCRIPTION:
XS GIS Cut Line= 3
      2262875.02     13781374.97      2263175.00     13780825.00
      2262475.00     13779625.01
#Sta/Elev= 30
  4374.5  598.55  4557.2  595.47  4727.6  591.03  4807.8  589.67  4823.9  590.28
  4852.9  587.42  4898.4  585.83  4949.2  585.50  5006.7  583.24  5007.0  582.74
  5010.9  583.24  5016.1  583.37  5132.0  584.35  5228.0  585.66  5249.5  587.53
  5265.2  586.79  5271.0  588.02  5286.7  588.26  5292.5  589.55  5329.7  590.21
  5404.1  589.86  5447.1  591.38  5548.8  592.87  5579.8  592.25  5650.5  594.12
  5964.3  595.79  6163.2  596.47  6178.9  597.62  6309.2  597.40  6390.2  598.80
#Mann=6,-1,0
  4374.5   0.035       0  5006.7   0.035       0  5010.9   0.035       0
  5016.1    0.07       0  5132.0   0.035       0  5964.3    0.07       0
Bank Sta=5006.7,5010.9
Exp/Cntr=0.3,0.1

Type RM Length L Ch R = 1,2952,255,255,255
BEGIN DESCRIPTION:
A19752
END DESCRIPTION:
XS GIS Cut Line= 3
      2263642.75     13781202.87      2263284.20     13780626.08
      2262933.42     13780306.48
#Sta/Elev= 30
  4491.5  596.01  4532.4  596.42  4538.3  595.89  4616.2  595.71  4705.9  594.25
  4742.6  592.61  4794.5  592.87  4815.8  590.78  4842.9  592.74  4873.6  592.62
  4889.0  591.24  4931.5  585.31  4968.1  581.74  5016.7  579.78  5017.0  579.28
  5021.1  579.78  5039.1  580.32  5077.7  581.86  5120.4  581.44  5173.5  582.48
  5178.0  583.17  5206.4  583.91  5213.2  584.85  5298.3  584.89  5347.6  585.74
  5392.5  587.42  5461.1  589.39  5616.5  591.93  5623.9  592.66  5645.2  592.48
#Mann=6,-1,0
  4491.5   0.045       0  4616.2   0.035       0  5016.7   0.035       0
  5021.1   0.035       0  5039.1    0.07       0  5392.5   0.035       0
Bank Sta=5016.7,5021.1
Exp/Cntr=0.3,0.1

Type RM Length L Ch R = 1,2697,418,418,418
BEGIN DESCRIPTION:
LONG BRANCH TRIBUTARY 2 2 5.0
END DESCRIPTION:
XS GIS Cut Line= 3
      2263674.97     13780624.99      2263525.00     13780575.00
      2262925.00     13780225.00
#Sta/Elev= 30
  4837.8  594.60  4857.1  594.35  4869.4  592.17  4890.5  589.88  4911.6  592.13
  4943.2  591.92  4964.3  584.28  4974.8  581.52  4985.3  579.67  5016.8  577.77
  5017.1  577.27  5020.9  577.27  5021.2  577.77  5040.9  578.53  5053.8  580.24
  5068.2  579.20  5126.9  579.27  5142.7  580.29  5207.2  580.82  5222.9  582.23
  5228.7  581.72  5238.6  583.22  5260.1  583.60  5265.9  582.94  5281.6  584.21
  5287.4  583.82  5318.8  585.30  5385.7  585.78  5596.6  592.40  5690.5  593.03
#Mann=5,-1,0
  4837.8   0.035       0  4857.1    0.07       0  5016.8    0.05       0
  5021.2    0.07       0  5385.7   0.035       0
Bank Sta=5016.8,5021.2
Exp/Cntr=0.3,0.1

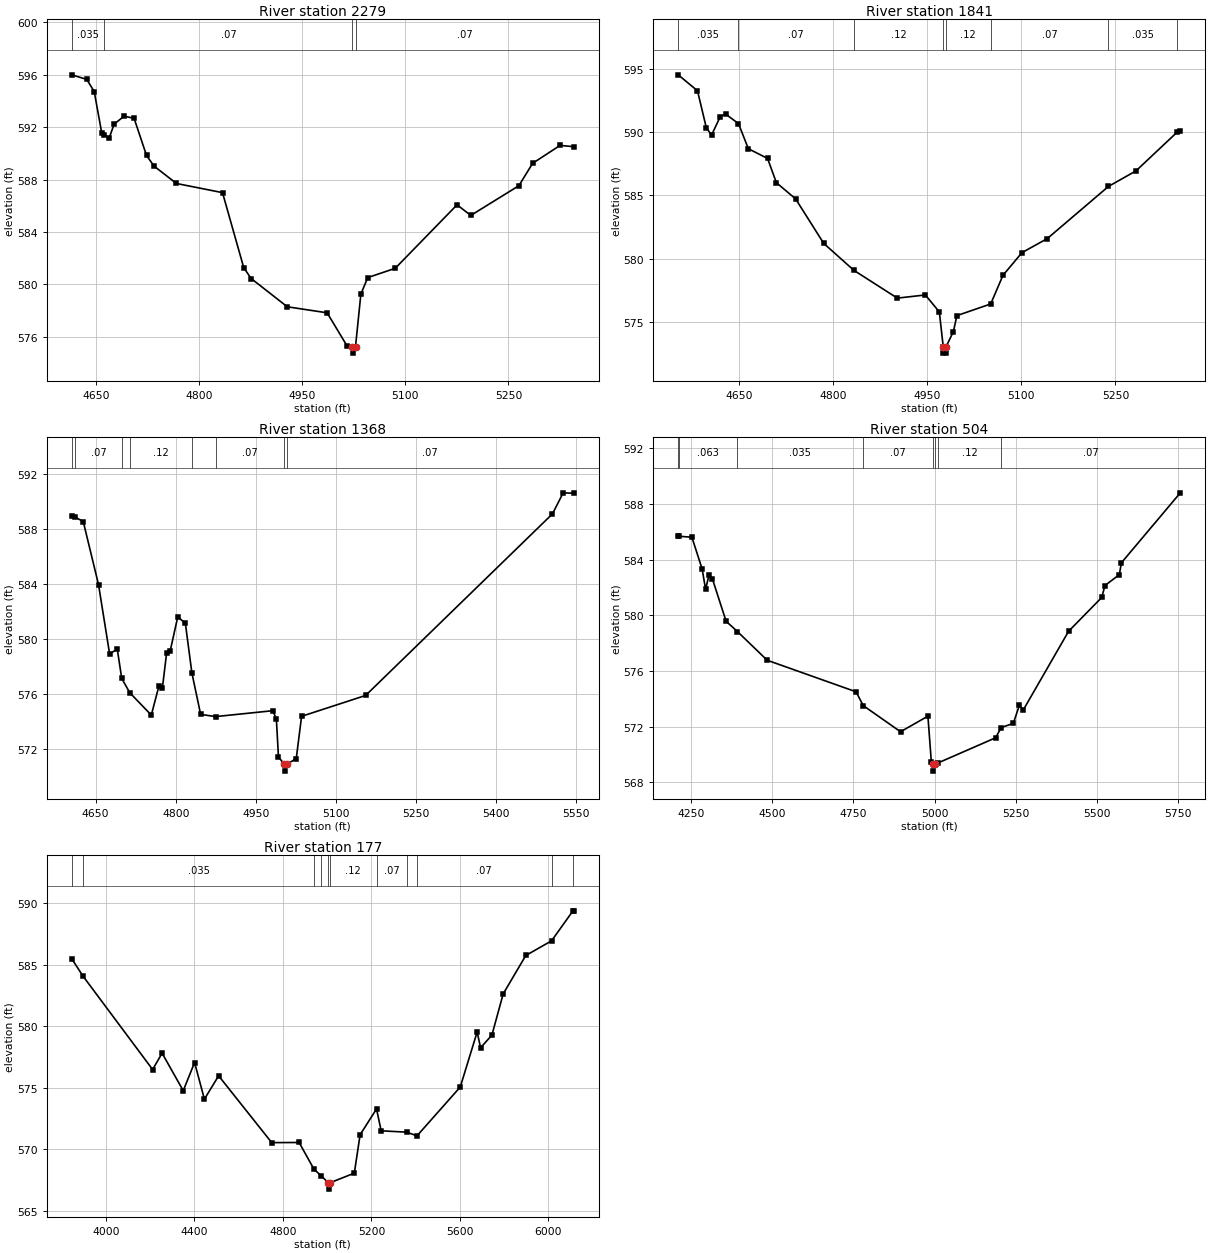
Type RM Length L Ch R = 1,2279,438,438,438
BEGIN DESCRIPTION:
LONG BRANCH TRIBUTARY 2 2 4.0
END DESCRIPTION:
XS GIS Cut Line= 3
      2263775.02     13780375.01      2263425.00     13780225.00
      2263075.01     13780225.00
#Sta/Elev= 30
  4614.4  596.00  4636.2  595.65  4647.1  594.72  4657.9  591.59  4661.8  591.44
  4668.8  591.16  4676.1  592.24  4690.6  592.84  4705.1  592.68  4723.2  589.84
  4734.1  589.03  4766.7  587.70  4833.8  587.00  4864.7  581.27  4875.5  580.44
  4928.1  578.28  4986.1  577.82  5015.2  575.28  5023.0  575.24  5023.3  574.74
  5027.4  575.24  5035.2  579.25  5045.2  580.51  5085.2  581.22  5175.2  586.07
  5195.2  585.26  5265.2  587.53  5285.2  589.24  5325.2  590.61  5345.2  590.51
#Mann=4,-1,0
  4614.4   0.035       0  4661.8    0.07       0  5023.0    0.05       0
  5027.4    0.07       0
Bank Sta=5023,5027.4
Exp/Cntr=0.3,0.1

Type RM Length L Ch R = 1,1841,473,473,473
BEGIN DESCRIPTION:
LONG BRANCH TRIBUTARY 2 2 3.0
END DESCRIPTION:
XS GIS Cut Line= 3
      2263924.98     13780024.99      2263525.00     13779825.00
      2263175.04     13779775.01
#Sta/Elev= 30
  4552.8  594.51  4583.5  593.25  4597.5  590.35  4605.9  589.75  4619.9  591.22
  4628.2  591.42  4648.9  590.66  4664.6  588.68  4695.3  587.91  4709.3  586.00
  4740.0  584.72  4784.8  581.21  4833.0  579.08  4902.2  576.89  4946.9  577.14
  4969.2  575.80  4975.4  573.05  4975.7  572.55  4979.6  572.55  4979.9  573.05
  4991.6  574.25  4997.2  575.51  5051.1  576.43  5070.7  578.69  5101.0  580.48
  5141.4  581.59  5238.8  585.70  5282.8  586.93  5348.3  589.98  5353.5  590.04
#Mann=8,-1,0
  4552.8   0.035       0  4648.9    0.07       0  4833.0    0.12       0
  4975.4    0.05       0  4979.9    0.12       0  5051.1    0.07       0
  5238.8   0.035       0  5348.3    0.07       0
Bank Sta=4975.4,4979.9
Exp/Cntr=0.3,0.1

Type RM Length L Ch R = 1,1368,864,864,864
BEGIN DESCRIPTION:
LONG BRANCH TRIBUTARY 2 2 2.0
END DESCRIPTION:
XS GIS Cut Line= 3
      2263974.98     13779724.98      2263725.00     13779425.00
      2263174.99     13779425.00
#Sta/Elev= 30
  4605.3  588.93  4611.5  588.87  4626.8  588.55  4655.4  583.96  4676.2  578.91
  4690.5  579.27  4698.9  577.13  4713.9  576.09  4754.3  574.46  4768.6  576.58
  4775.1  576.45  4783.0  578.99  4789.5  579.10  4803.8  581.61  4818.1  581.14
  4830.3  577.53  4846.7  574.51  4874.8  574.35  4982.1  574.78  4988.6  574.14
  4992.5  571.41  5003.5  570.88  5003.8  570.38  5008.0  570.88  5025.8  571.29
  5035.8  574.37  5155.8  575.89  5505.8  589.11  5525.8  590.64  5545.8  590.61
#Mann=8,-1,0
  4605.3   0.035       0  4611.5    0.07       0  4698.9   0.063       0
  4713.9    0.12       0  4830.3   0.035       0  4874.8    0.07       0
  5003.5    0.05       0  5008.0    0.07       0
Bank Sta=5003.5,5008
Exp/Cntr=0.3,0.1

Type RM Length L Ch R = 1,504,327,327,327
BEGIN DESCRIPTION:
LONG BRANCH TRIBUTARY 2 2 1.0
END DESCRIPTION:
XS GIS Cut Line= 3
      2264074.98     13779524.95      2263825.00     13778775.00
      2263074.96     13778875.01
#Sta/Elev= 30
  4210.1  585.68  4211.6  585.68  4252.2  585.61  4283.8  583.32  4294.4  581.86
  4304.9  582.90  4315.5  582.61  4357.6  579.57  4392.6  578.83  4484.1  576.77
  4758.2  574.50  4780.1  573.51  4895.2  571.63  4979.5  572.75  4990.1  569.45
  4995.7  569.30  4996.0  568.80  5000.3  569.30  5010.7  569.39  5188.5  571.20
  5204.9  571.93  5242.7  572.23  5261.7  573.56  5273.0  573.18  5413.0  578.85
  5515.1  581.28  5525.2  582.14  5569.4  582.92  5575.7  583.77  5757.3  588.80
#Mann=8,-1,0
  4210.1   0.035       0  4211.6   0.063       0  4392.6   0.035       0
  4780.1    0.07       0  4995.7    0.05       0  5000.3    0.07       0
  5010.7    0.12       0  5204.9    0.07       0
Bank Sta=4995.7,5000.3
Exp/Cntr=0.3,0.1

Type RM Length L Ch R = 1,177,0,0,0
BEGIN DESCRIPTION:
A19753
END DESCRIPTION:
XS GIS Cut Line= 4
      2264567.21     13779472.51      2264091.72     13778669.64
      2263795.53     13778443.60      2262852.35     13778638.47
#Sta/Elev= 30
  3845.9  585.47  3896.4  584.07  4211.2  576.47  4254.1  577.80  4349.6  574.75
  4400.9  577.04  4445.2  574.06  4509.5  575.96  4749.5  570.53  4873.3  570.54
  4940.3  568.37  4972.5  567.84  5006.0  567.25  5006.4  566.75  5010.7  567.25
  5122.7  568.05  5148.8  571.17  5223.1  573.27  5244.0  571.49  5359.9  571.38
  5405.9  571.08  5601.4  575.05  5677.7  579.52  5693.3  578.24  5744.4  579.27
  5795.4  582.62  5897.6  585.74  6013.9  586.93  6109.2  589.33  6114.7  589.37
#Mann=11,-1,0
  3845.9    0.07       0  3896.4   0.035       0  4940.3    0.07       0
  4972.5    0.12       0  5006.0    0.05       0  5010.7    0.12       0
  5223.1    0.07       0  5359.9    0.12       0  5405.9    0.07       0
  6013.9   0.035       0  6109.2    0.07       0
Bank Sta=5006,5010.7
Exp/Cntr=0.3,0.1

Chan Stop Cuts=-1