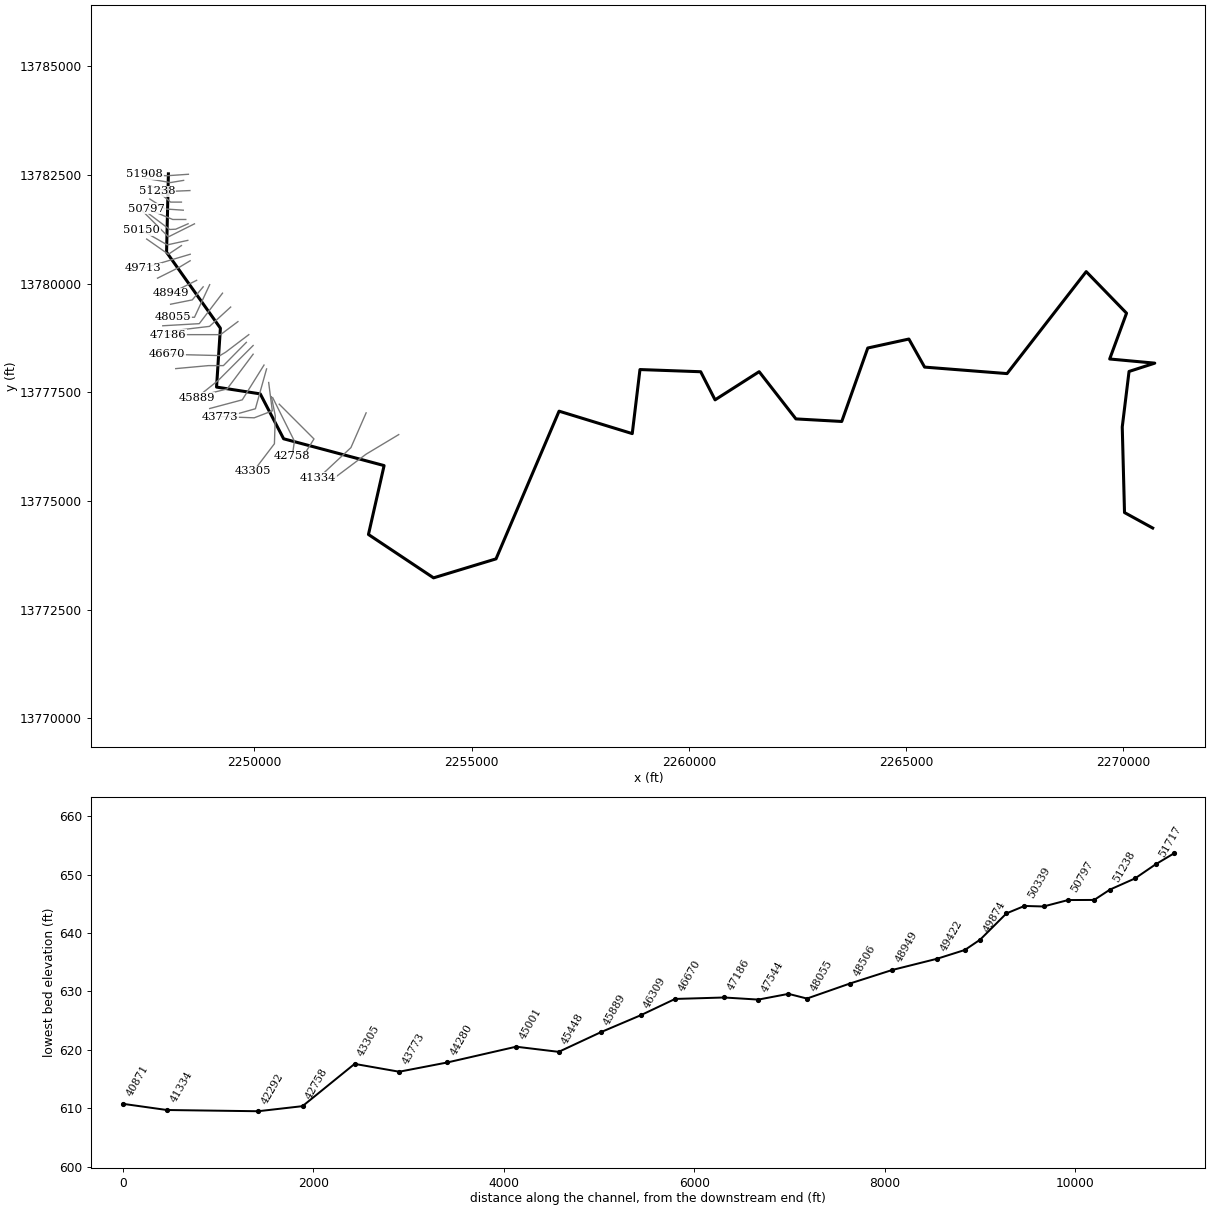
--- LONG CREEK.prj (project) ---

Proj Title=LONG CREEK Base Level Engineering
Current Plan=p01
Default Exp/Contr=0.3,0.1
English Units
Geom File=g01
Flow File=f01
Plan File=p01
Y Axis Title=Elevation
X Axis Title(PF)=Main Channel Distance
X Axis Title(XS)=Station
BEGIN DESCRIPTION:
LONG CREEK
END DESCRIPTION:
DSS Export Rating Curves= 0
DSS Export Rating Curve Sorted= 0
DSS Export Volume Flow Curves= 0
DXF OffsetX= 0
DXF OffsetY= 0
DXF ScaleX= 1
DXF ScaleY= 10

--- LONG CREEK.p01 (plan) ---

Plan Title=Multiple Run
Short Identifier=Multiple
Geom File=g01
Flow File=f01
Subcritical Flow
K Sum by GR= 0
Std Step Tol= 0.01
Critical Tol= 0.01
Num of Std Step Trials= 20
Max Error Tol= 0.3
Flow Tol Ratio= 0.001
Split Flow NTrial= 30
Split Flow Tol= 0.02
Split Flow Ratio= 0.02
Log Output Level= 0
Friction Slope Method= 1
Unsteady Friction Slope Method= 2
Unsteady Bridges Friction Slope Method= 1
Parabolic Critical Depth
Global Vel Dist=  1 , 1 , 1
Global Log Level= 0
CheckData=True
Encroach Param= -1, 0, 0, 0
BEGIN DESCRIPTION:
Multiple Run
END DESCRIPTION:

--- LONG CREEK.f01 (steady flow) ---

Flow Title=Multiple
Number of Profiles=7
Profile Names=10-year,25-year,50-year,1pct_min,100-year,1pct_plu,500-year
River Rch & RM= LONG CREEK,Reach-1,51908
     589     945    1265     820    1637    3266    2710
River Rch & RM= LONG CREEK,Reach-1,48949
    1215    2025    2780    1843    3678    7339    6375
River Rch & RM= LONG CREEK,Reach-1,43305
    1527    2578    3569    2384    4757    9492    8375
River Rch & RM= LONG CREEK,Reach-1,41334
    1857    3146    4363    2917    5820   11612   10264
River Rch & RM= LONG CREEK,Reach-1,36805
    2109    3594    5003    3356    6695   13359   11887
River Rch & RM= LONG CREEK,Reach-1,35446
    2201    3745    5208    3488    6959   13886   12320
River Rch & RM= LONG CREEK,Reach-1,32191
    2307    3920    5446    3643    7269   14503   12835
River Rch & RM= LONG CREEK,Reach-1,26452
    2450    4141    5733    3820    7622   15207   13348
River Rch & RM= LONG CREEK,Reach-1,20126
    2445    4124    5700    3791    7564   15092   13198
River Rch & RM= LONG CREEK,Reach-1,17350
    2900    4920    6829    4559    9096   18150   15990
Boundary for River Rch & Prof#=LONG CREEK,Reach-1,1
Up Type=0
Dn Type=3
Dn Slope=0.005
Boundary for River Rch & Prof#=LONG CREEK,Reach-1,2
Up Type=0
Dn Type=3
Dn Slope=0.005
Boundary for River Rch & Prof#=LONG CREEK,Reach-1,3
Up Type=0
Dn Type=3
Dn Slope=0.005
Boundary for River Rch & Prof#=LONG CREEK,Reach-1,4
Up Type=0
Dn Type=3
Dn Slope=0.005
Boundary for River Rch & Prof#=LONG CREEK,Reach-1,5
Up Type=0
Dn Type=3
Dn Slope=0.005
Boundary for River Rch & Prof#=LONG CREEK,Reach-1,6
Up Type=0
Dn Type=3
Dn Slope=0.005
Boundary for River Rch & Prof#=LONG CREEK,Reach-1,7
Up Type=0
Dn Type=3
Dn Slope=0.005

--- LONG CREEK.g01 (geometry) ---

Geom Title=Existing Conditions
Program Version=4.10

River Reach=LONG CREEK      ,Reach-1
Reach XY= 30
        2248025.       13782525.      2247982.77     13780721.59
      2249221.46     13778973.54      2249132.76      13777618.2
      2250138.69     13777461.74       2250676.5     13776428.61
      2252988.63     13775812.04      2252628.54     13774226.47
      2254126.46     13773228.53      2255564.24     13773665.32
      2257014.94     13777064.39      2258698.84     13776547.85
       2258876.4     13778021.81      2260273.78     13777971.57
      2260604.82     13777324.71      2261619.14     13777972.95
      2262464.94      13776886.1      2263519.54     13776827.05
      2264118.68      13778517.5      2265064.57     13778723.95
      2265426.43     13778078.07      2267323.45     13777928.75
      2269145.17     13780275.29      2270073.24     13779318.88
      2269685.38     13778264.89      2270722.95     13778169.14
      2270130.83     13777977.87       2269974.5     13776700.04
       2270026.6      13774731.1        2270675.       13774375.

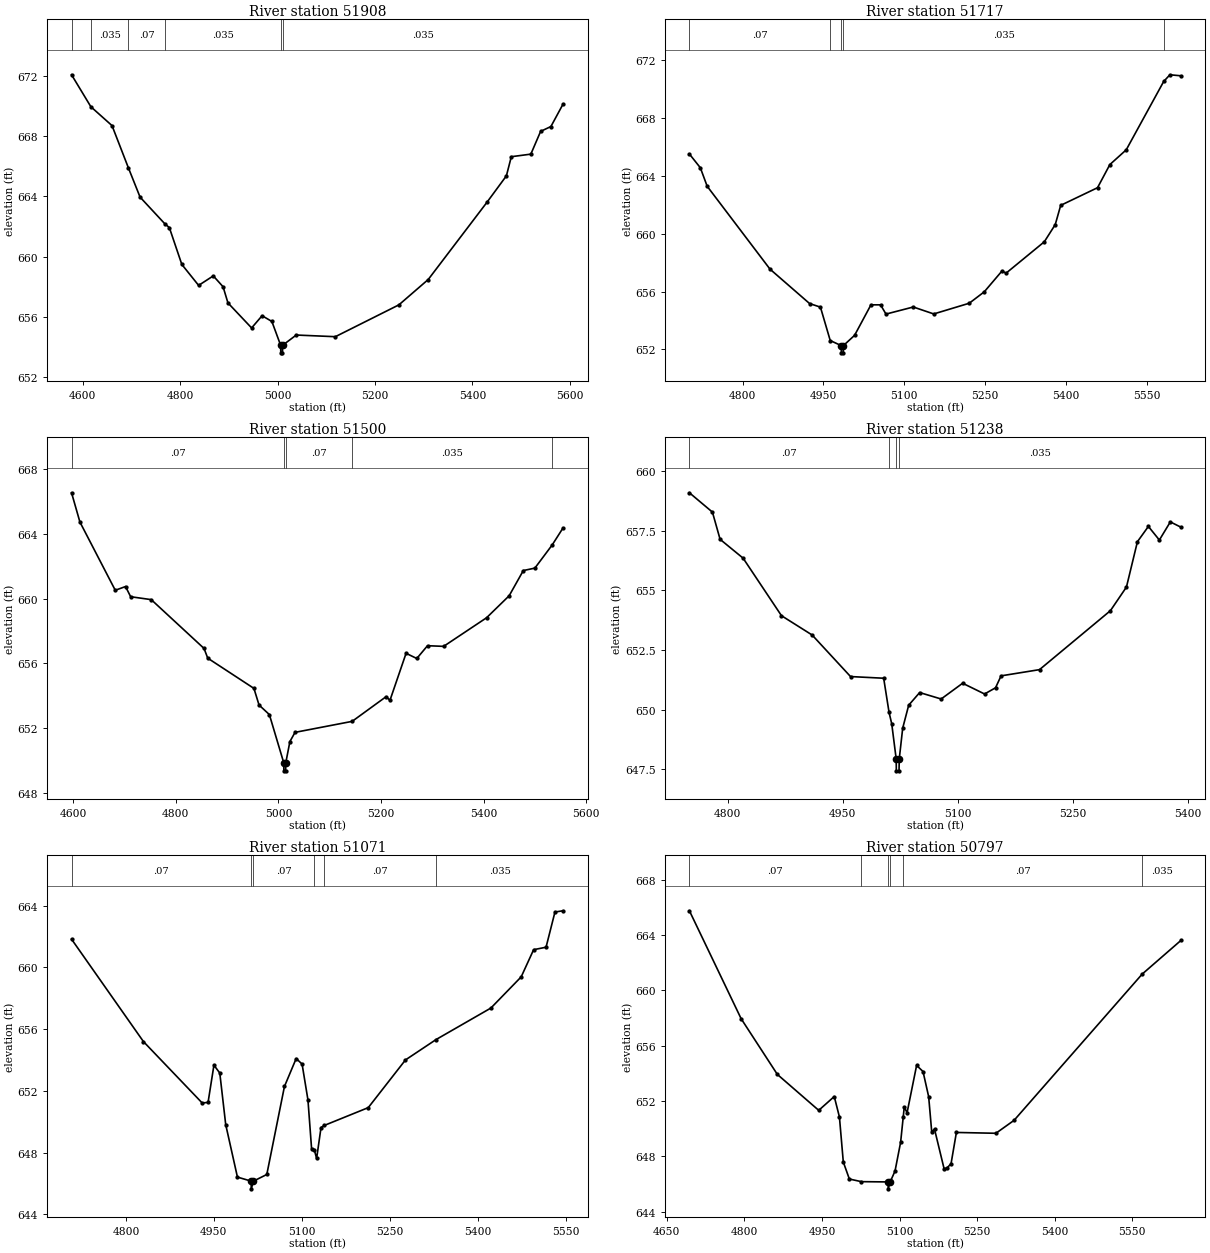
Type RM Length L Ch R = 1 ,51908   ,191,191,191
BEGIN DESCRIPTION:
A19820
END DESCRIPTION:
XS GIS Cut Line= 3
      2248485.33     13782515.51      2247978.43     13782480.79
      2247479.25     13782522.39
#Sta/Elev= 30
  4576.8  672.05  4616.5  669.93  4659.9  668.68  4693.4  665.89  4717.5  663.94
  4768.1  662.18  4777.6  661.92  4803.2  659.48  4837.7  658.09  4867.8  658.72
  4887.9     658  4897.9  656.93  4946.5  655.27    4968  656.08  4988.1   655.7
  5006.1  654.12  5006.4  653.62  5009.9  653.62  5010.1  654.12  5038.2   654.8
  5118.4  654.69  5248.9   656.8  5309.1  658.48  5429.5  663.59  5469.6  665.35
  5479.7  666.62  5519.8  666.79  5539.9   668.3    5561  668.62  5585.8   670.1
#Mann= 6 ,-1 , 0
  4576.8     .07       0  4616.5    .035       0  4693.4     .07       0
  4768.1    .035       0  5006.1    .035       0  5010.1    .035       0
Bank Sta=5006.1,5010.1
XS Rating Curve= 0 ,0
Exp/Cntr=0.3,0.1

Type RM Length L Ch R = 1 ,51717   ,217,217,217
BEGIN DESCRIPTION:
LONG CREEK 81.0
END DESCRIPTION:
XS GIS Cut Line= 3
      2248375.04     13782375.01        2248075.       13782325.
      2247474.95     13782425.01
#Sta/Elev= 30
  4701.1  665.51  4721.4  664.56  4734.1  663.28  4850.7  657.55  4924.2  655.17
  4944.4  654.92  4962.6  652.61    4983  652.26  4983.3  651.76  4986.8  651.76
    4987  652.26  5007.8  652.97  5038.2  655.08    5056  655.08  5066.1  654.44
  5116.8  654.93  5154.8  654.45  5220.7  655.19  5248.6  655.98  5281.5  657.42
  5289.1  657.27  5360.1  659.44  5380.4  660.63  5390.5  661.96  5458.9  663.18
  5481.8  664.78  5512.2   665.8  5581.8  670.53  5593.3  670.99  5613.6  670.92
#Mann= 5 ,-1 , 0
  4701.1     .07       0  4962.6    .035       0    4983    .035       0
    4987    .035       0  5581.8     .05       0
Bank Sta=4983,4987
XS Rating Curve= 0 ,0
Exp/Cntr=0.3,0.1

Type RM Length L Ch R = 1 ,51500   ,262,262,262
BEGIN DESCRIPTION:
A19819
END DESCRIPTION:
XS GIS Cut Line= 3
      2248520.13     13782140.51      2248013.15     13782119.68
      2247582.62     13782251.61
#Sta/Elev= 30
  4596.8  666.54  4613.1  664.73    4682  660.51    4702  660.74    4712  660.11
  4752.1  659.93    4855  656.91  4862.2  656.31  4952.2  654.44  4962.2  653.41
  4982.3  652.82  5010.3  649.84  5010.5  649.34    5014  649.34  5014.3  649.84
  5022.3  651.15  5032.3  651.72  5143.6   652.4  5209.9  653.93  5217.3   653.7
  5248.7  656.61  5269.6  656.29  5290.5  657.08  5321.9  657.04  5405.6  658.81
  5449.6  660.17  5477.2  661.73  5499.7  661.88  5533.4  663.31  5554.5  664.36
#Mann= 5 ,-1 , 0
  4596.8     .07       0  5010.3     .05       0  5014.3     .07       0
  5143.6    .035       0  5533.4     .05       0
Bank Sta=5010.3,5014.3
XS Rating Curve= 0 ,0
Exp/Cntr=0.3,0.1

Type RM Length L Ch R = 1 ,51238   ,167,167,167
BEGIN DESCRIPTION:
LONG CREEK 80.0
END DESCRIPTION:
XS GIS Cut Line= 3
      2248324.99       13781875.        2248075.       13781875.
        2247775.       13782125.
#Sta/Elev= 30
    4750  659.09    4780  658.28    4790  657.14    4820  656.35    4870  653.94
    4910  653.13    4960  651.39  5003.2  651.32  5010.2  649.89  5013.7  649.41
  5019.5  647.94  5019.7  647.44  5023.2  647.44  5023.5  647.94    5028  649.23
  5035.8  650.19  5050.1  650.72  5078.1  650.45  5106.1  651.11  5134.7  650.66
    5149  650.92  5156.2  651.42  5206.3  651.68  5298.7  654.15  5319.6  655.14
  5333.9  657.04  5348.2  657.68  5362.5  657.11  5376.8  657.87  5390.5  657.65
#Mann= 4 ,-1 , 0
    4750     .07       0  5010.2    .035       0  5019.5     .05       0
  5023.5    .035       0
Bank Sta=5019.5,5023.5
XS Rating Curve= 0 ,0
Exp/Cntr=0.3,0.1

Type RM Length L Ch R = 1 ,51071   ,274,274,274
BEGIN DESCRIPTION:
A19818
END DESCRIPTION:
XS GIS Cut Line= 3
      2248367.36     13781689.12       2247957.6      13781716.9
      2247596.48     13781946.07
#Sta/Elev= 30
  4707.3  661.83  4829.9   655.2  4930.2  651.22  4940.2  651.26  4950.2  653.67
  4960.2  653.16  4970.3  649.82  4990.3  646.42  5013.7  646.16  5013.9  645.66
  5017.7  646.16  5040.4  646.59  5070.5  652.29  5090.5   654.1  5100.6  653.74
  5110.6  651.42  5116.8  648.26  5121.6  648.16  5125.4  647.63  5132.9  649.63
  5138.7  649.77  5213.5  650.92    5277  654.01  5329.2  655.33  5422.7  657.37
  5474.4  659.39  5495.6  661.15  5516.8  661.31    5532  663.59  5545.7  663.67
#Mann= 6 ,-1 , 0
  4707.3     .07       0  5013.7     .05       0  5017.7     .07       0
  5121.6    .035       0  5138.7     .07       0  5329.2    .035       0
Bank Sta=5013.7,5017.7
XS Rating Curve= 0 ,0
Exp/Cntr=0.3,0.1

Type RM Length L Ch R = 1 ,50797   ,258,258,258
BEGIN DESCRIPTION:
LONG CREEK 79.0
END DESCRIPTION:
XS GIS Cut Line= 3
      2248424.97       13781475.        2248125.       13781475.
      2247524.98     13781725.01
#Sta/Elev= 30
  4693.7  665.76  4793.7  657.95  4863.7  653.92  4943.7  651.32  4973.7  652.32
  4983.7  650.84  4991.2  647.58  5002.9  646.35  5026.1  646.16  5077.8  646.14
    5078  645.64  5081.8  646.14  5091.2  646.93    5102  649.01    5107  650.82
    5109  651.55  5114.5  651.15  5132.9  654.57  5145.3  654.13  5156.2  652.31
  5162.1  649.77  5167.5  649.96    5186   647.1  5191.4  647.14  5199.5  647.46
  5209.8  649.72  5286.2  649.66  5321.4   650.6    5569  661.18  5643.7  663.61
#Mann= 6 ,-1 , 0
  4693.7     .07       0  5026.1    .033       0  5077.8     .05       0
  5081.8    .033       0    5107     .07       0    5569    .035       0
Bank Sta=5077.8,5081.8
XS Rating Curve= 0 ,0
Exp/Cntr=0.3,0.1

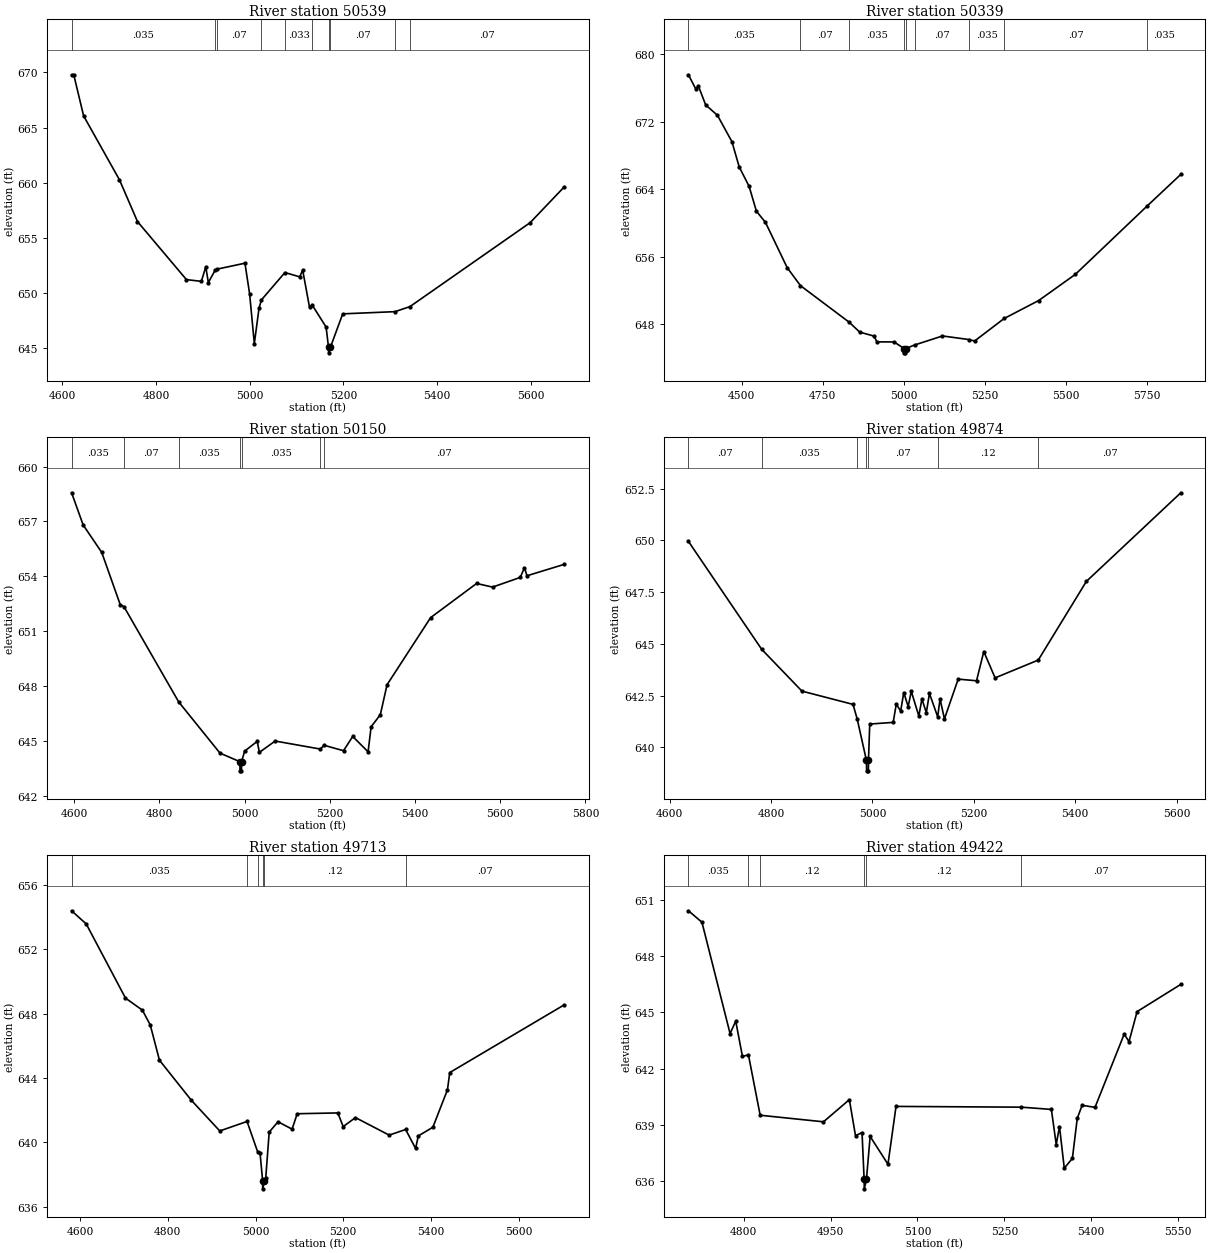
Type RM Length L Ch R = 1 ,50539   ,200,200,200
BEGIN DESCRIPTION:
A19817
END DESCRIPTION:
XS GIS Cut Line= 4
      2248478.42     13781376.61      2248193.71     13781251.62
      2248054.82     13781244.68      2247575.65     13781605.79
#Sta/Elev= 30
  4620.2  669.79  4624.8  669.79  4645.8  666.06  4722.2  660.26  4760.7  656.46
  4865.1  651.19    4897  651.03  4906.4  652.36  4911.8  650.92  4926.3  652.04
  4930.4  652.14  4989.9  652.68  4999.9  649.88  5009.9  645.38    5020  648.62
  5025.1  649.35  5075.1  651.83  5106.8  651.44    5113  652.06  5127.6  648.67
  5133.9  648.84    5163  646.88  5168.1  645.04  5168.4  644.54  5172.1  645.04
  5198.4  648.08    5310  648.28  5341.8  648.74  5598.1  656.36  5670.2  659.58
#Mann= 10 ,-1 , 0
  4620.2    .035       0  4926.3    .033       0  4930.4     .07       0
  5025.1    .035       0  5075.1    .033       0  5133.9     .07       0
  5168.1     .05       0  5172.1     .07       0    5310    .035       0
  5341.8     .07       0
Bank Sta=5168.1,5172.1
XS Rating Curve= 0 ,0
Exp/Cntr=0.3,0.1

Type RM Length L Ch R = 1 ,50339   ,189,189,189
BEGIN DESCRIPTION:
LONG CREEK 78.0
END DESCRIPTION:
XS GIS Cut Line= 3
      2248625.02     13781375.01        2248025.       13781075.
      2247424.98     13781675.02
#Sta/Elev= 30
    4336  677.57  4358.4   675.9  4366.8  676.23  4389.1     674  4425.5  672.77
  4470.2  669.64  4492.5  666.67  4523.3  664.34  4545.7  661.41  4573.6  660.09
  4640.7  654.72  4681.7  652.59  4832.3  648.25  4864.3  647.09    4909  646.61
  4917.4  645.93  4970.5  645.92    5002  645.13  5002.3  644.63  5005.8  644.63
    5006  645.13  5033.9  645.56    5120  646.63  5202.5   646.2    5219  646.03
  5310.4   648.7    5417  650.83  5530.1  653.93  5751.7  662.03  5855.4  665.77
#Mann= 9 ,-1 , 0
    4336    .035       0  4681.7     .07       0  4832.3    .035       0
    5002    .035       0    5006    .035       0  5033.9     .07       0
  5202.5    .035       0  5310.4     .07       0  5751.7    .035       0
Bank Sta=5002,5006
XS Rating Curve= 0 ,0
Exp/Cntr=0.3,0.1

Type RM Length L Ch R = 1 ,50150   ,276,276,276
BEGIN DESCRIPTION:
A19816
END DESCRIPTION:
XS GIS Cut Line= 3
      2248471.47     13780994.67      2247999.26     13780890.51
      2247415.94     13781223.84
#Sta/Elev= 30
  4594.1  658.57  4621.2  656.81  4664.8  655.31  4708.4  652.44    4717  652.34
  4845.4  647.13  4942.3  644.33  4989.1  643.86  4989.3  643.36  4992.8  643.36
  4993.1  643.86  5000.1  644.44  5029.7  644.97  5034.8  644.37  5071.8  644.99
  5178.2  644.55  5186.4  644.76  5232.2  644.46  5253.8  645.24  5289.9   644.4
    5297  645.77  5318.6  646.43  5334.4  648.07  5436.6  651.74  5544.6  653.61
    5582  653.41  5646.9  653.94  5656.9  654.47  5662.7  654.03  5749.5  654.65
#Mann= 7 ,-1 , 0
  4594.1    .035       0    4717     .07       0  4845.4    .035       0
  4989.1    .035       0  4993.1    .035       0  5178.2     .12       0
  5186.4     .07       0
Bank Sta=4989.1,4993.1
XS Rating Curve= 0 ,0
Exp/Cntr=0.3,0.1

Type RM Length L Ch R = 1 ,49874   ,161,161,161
BEGIN DESCRIPTION:
LONG CREEK 77.0
END DESCRIPTION:
XS GIS Cut Line= 3
      2248324.99     13780874.99        2248025.       13780675.
      2247524.98     13781025.02
#Sta/Elev= 30
  4637.3  649.95  4781.7  644.74  4861.1  642.72  4961.8  642.08  4970.1  641.37
  4988.3  639.37  4988.6  638.87  4992.1  638.87  4992.3  639.37  4994.8  641.13
    5041  641.21  5047.1  642.09  5055.8  641.76  5061.9  642.65  5070.6  641.97
  5076.7  642.71  5091.6  641.52  5097.7  642.34  5106.4  641.68  5112.5  642.61
  5128.8  641.48  5133.4  642.34  5142.1  641.38  5169.2   643.3  5205.4  643.22
  5219.7  644.63    5242  643.36  5327.1  644.22    5422  648.02  5608.2   652.3
#Mann= 7 ,-1 , 0
  4637.3     .07       0  4781.7    .035       0  4970.1     .07       0
  4988.3     .05       0  4992.3     .07       0  5128.8     .12       0
  5327.1     .07       0
Bank Sta=4988.3,4992.3
XS Rating Curve= 0 ,0
Exp/Cntr=0.3,0.1

Type RM Length L Ch R = 1 ,49713   ,291,291,291
BEGIN DESCRIPTION:
A19815
END DESCRIPTION:
XS GIS Cut Line= 2
        2248527.     13780675.22       2247450.7      13780355.8
#Sta/Elev= 30
  4580.6  654.39    4614  653.57  4703.5  648.96    4742  648.21    4760  647.29
  4780.9   645.1  4853.9   642.6  4918.5   640.7  4980.7  641.29  5004.6  639.42
  5010.4  639.31  5016.2   637.6  5016.4   637.1  5020.2   637.6  5023.4   637.8
  5031.2  640.63  5051.4  641.27  5083.4  640.81    5095  641.77  5187.7  641.82
  5199.9  640.97  5227.9  641.53  5304.8  640.44  5342.3  640.79    5365  639.61
  5371.2  640.39  5404.4  640.93  5437.7  643.26  5442.9  644.33  5703.3  648.53
#Mann= 6 ,-1 , 0
  4580.6    .035       0  4980.7     .07       0  5004.6     .12       0
  5016.2     .05       0  5020.2     .12       0  5342.3     .07       0
Bank Sta=5016.2,5020.2
XS Rating Curve= 0 ,0
Exp/Cntr=0.3,0.1

Type RM Length L Ch R = 1 ,49422   ,473,473,473
BEGIN DESCRIPTION:
LONG CREEK 76.0
END DESCRIPTION:
XS GIS Cut Line= 3
      2248525.01     13780525.01        2248275.       13780375.
      2247774.98     13780124.99
#Sta/Elev= 30
  4704.3  650.41  4727.6   649.8  4776.2  643.87    4786  644.53  4797.6  642.65
  4807.9  642.74  4828.2  639.52  4937.6  639.17  4982.3  640.35  4992.9  638.43
  5004.2   638.6  5007.8   636.1  5008.1   635.6  5011.8   636.1  5018.2  638.39
    5049  636.91  5062.9  639.99  5279.6  639.95  5331.3  639.83  5339.7  637.96
  5345.3  638.92  5353.6   636.7  5367.6  637.22    5376  639.35  5384.4  640.05
  5406.7  639.94  5457.1  643.84  5465.4  643.44  5479.4  645.04  5554.9  646.49
#Mann= 6 ,-1 , 0
  4704.3    .035       0  4807.9     .07       0  4828.2     .12       0
  5007.8     .05       0  5011.8     .12       0  5279.6     .07       0
Bank Sta=5007.8,5011.8
XS Rating Curve= 0 ,0
Exp/Cntr=0.3,0.1

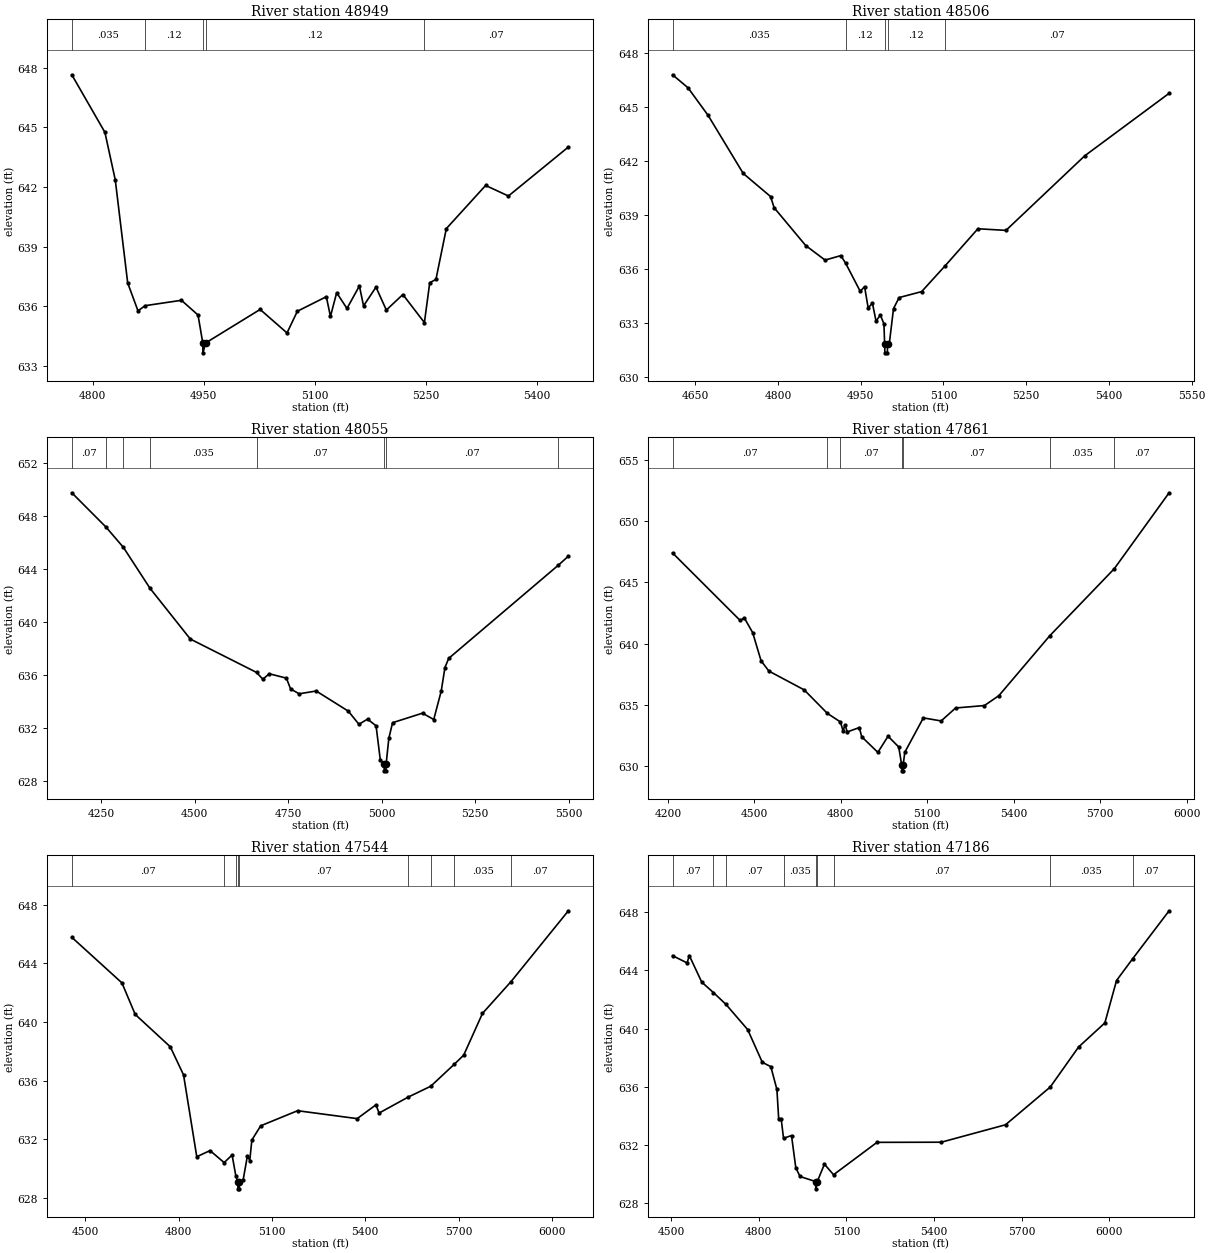
Type RM Length L Ch R = 1 ,48949   ,443,443,443
BEGIN DESCRIPTION:
LONG CREEK 75.0
END DESCRIPTION:
XS GIS Cut Line= 3
        2248675.       13780075.        2248475.       13779975.
      2248075.02     13779775.01
#Sta/Elev= 30
  4771.8  647.64  4816.5  644.75  4830.5  642.36  4847.3  637.18  4861.2  635.78
  4870.9  636.04  4919.9  636.31  4942.3  635.57  4948.7  634.17  4948.9  633.67
  4952.7  634.17  5026.2  635.85  5062.5  634.67  5076.5  635.76  5115.6  636.49
  5121.2   635.5  5129.6  636.69  5143.5   635.9  5160.3  637.03  5165.9  636.03
  5182.7  636.97  5196.7  635.82    5219   636.6  5248.1  635.19  5255.3  637.19
  5263.7  637.36  5277.7  639.91  5330.8  642.08  5361.6  641.55  5442.6  644.01
#Mann= 5 ,-1 , 0
  4771.8    .035       0  4870.9     .12       0  4948.7     .05       0
  4952.7     .12       0  5248.1     .07       0
Bank Sta=4948.7,4952.7
XS Rating Curve= 0 ,0
Exp/Cntr=0.3,0.1

Type RM Length L Ch R = 1 ,48506   ,451,451,451
BEGIN DESCRIPTION:
LONG CREEK 74.0
END DESCRIPTION:
XS GIS Cut Line= 3
      2248824.98     13779924.98        2248575.       13779625.
      2248074.99       13779525.
#Sta/Elev= 30
  4608.7   646.8  4636.7  646.08  4673.1  644.55  4736.9  641.32  4786.4  640.04
  4792.9  639.42  4850.1  637.32  4885.3  636.51  4913.9  636.76  4922.7  636.33
  4949.1  634.77  4956.9  635.04  4963.4  633.86  4971.2  634.11  4977.7  633.12
  4985.5  633.46    4992  632.97  4993.3  631.86  4993.7  631.36  4998.2  631.36
  4998.6  631.86  5001.7  631.86  5009.4  633.82  5019.6  634.43  5060.4  634.76
  5103.2   636.2  5162.4  638.25  5213.3  638.16  5356.1   642.3  5509.1  645.77
#Mann= 5 ,-1 , 0
  4608.7    .035       0  4922.7     .12       0  4993.3     .05       0
  4998.6     .12       0  5103.2     .07       0
Bank Sta=4993.3,4998.6
XS Rating Curve= 0 ,0
Exp/Cntr=0.3,0.1

Type RM Length L Ch R = 1 ,48055   ,194,194,194
BEGIN DESCRIPTION:
LONG CREEK 73.0
END DESCRIPTION:
XS GIS Cut Line= 3
      2248974.98     13779974.96        2248625.       13779225.
      2248125.01       13779225.
#Sta/Elev= 30
  4171.7  649.76  4263.2  647.17  4309.7  645.64  4380.7  642.56  4488.5  638.73
  4665.7  636.21  4682.4   635.7  4699.8  636.11  4745.5  635.78  4756.5  634.97
  4779.4   634.6  4825.1  634.81    4911  633.29  4939.4   632.3  4962.3  632.69
  4985.1  632.19  4996.5  629.61  5006.6  629.29  5007.1  628.79  5011.6  628.79
    5012  629.29  5019.3  631.25  5029.3  632.42  5109.3  633.14  5139.3  632.66
  5159.3   634.8  5169.3  636.58  5179.3  637.27  5472.5   644.3  5499.3  644.98
#Mann= 8 ,-1 , 0
  4171.7     .07       0  4263.2    .035       0  4309.7     .07       0
  4380.7    .035       0  4665.7     .07       0  5006.6     .05       0
    5012     .07       0  5472.5    .035       0
Bank Sta=5006.6,5012
XS Rating Curve= 0 ,0
Exp/Cntr=0.3,0.1

Type RM Length L Ch R = 1 ,47861   ,317,317,317
BEGIN DESCRIPTION:
A19814
END DESCRIPTION:
XS GIS Cut Line= 3
      2249270.09     13779779.39      2248735.38     13779078.01
      2247895.15      13779029.4
#Sta/Elev= 30
  4215.8  647.41  4450.4  641.89  4464.9   642.1    4494  640.89  4523.1  638.59
  4550.2  637.75  4672.8  636.21  4753.2  634.29  4798.5  633.59  4807.9  632.84
  4814.2  633.36  4822.4  632.77  4864.1  633.13  4872.3  632.38  4928.5   631.1
  4963.9  632.42    5001  631.54    5011  630.09  5011.5  629.59    5016  629.59
  5016.4  630.09    5022  631.11  5086.4  633.92  5148.2  633.67  5198.3  634.73
  5298.5  634.93  5348.6  635.74  5524.9  640.63  5749.1  646.12  5939.4  652.33
#Mann= 7 ,-1 , 0
  4215.8     .07       0  4753.2    .035       0  4798.5     .07       0
    5011     .05       0  5016.4     .07       0  5524.9    .035       0
  5749.1     .07       0
Bank Sta=5011,5016.4
XS Rating Curve= 0 ,0
Exp/Cntr=0.3,0.1

Type RM Length L Ch R = 1 ,47544   ,358,358,358
BEGIN DESCRIPTION:
A19813
END DESCRIPTION:
XS GIS Cut Line= 3
      2249457.59     13779459.95      2248971.49     13779015.51
      2248040.95      13778904.4
#Sta/Elev= 30
  4457.1  645.77  4618.2  642.66  4660.8  640.51  4773.6   638.3  4816.2  636.38
  4858.7   630.8  4901.3  631.22  4946.7   630.4  4972.2  630.92  4984.3  629.48
  4990.5  629.11  4990.9  628.61  4995.5  628.61  4995.9  629.11  5007.4  629.18
  5021.5  630.87    5029  630.54  5035.7  631.94  5064.1  632.91  5182.7  633.94
  5374.1   633.4  5434.5  634.34  5444.6  633.78  5538.2  634.87  5610.6  635.61
  5685.8   637.1  5716.5  637.73  5776.9  640.58  5868.7  642.75  6052.9  647.58
#Mann= 9 ,-1 , 0
  4457.1     .07       0  4946.7    .035       0  4984.3     .07       0
  4990.5     .05       0  4995.9     .07       0  5538.2    .035       0
  5610.6     .07       0  5685.8    .035       0  5868.7     .07       0
Bank Sta=4990.5,4995.9
XS Rating Curve= 0 ,0
Exp/Cntr=0.3,0.1

Type RM Length L Ch R = 1 ,47186   ,516,516,516
BEGIN DESCRIPTION:
LONG CREEK 72.0
END DESCRIPTION:
XS GIS Cut Line= 3
        2249625.       13779125.        2249225.       13778825.
        2248025.       13778825.
#Sta/Elev= 30
  4504.5  645.02  4554.5  644.52  4561.8  645.03  4604.5   643.2  4644.5  642.48
  4686.8  641.68  4761.8  639.93  4811.8  637.68    4841  637.38  4861.8  635.81
    4868  633.76  4876.4  633.79  4884.5  632.45  4911.8  632.64  4926.4  630.43
    4941  629.82  4994.5  629.47  4994.9  628.97    5000  629.47  5024.5  630.67
  5055.7  629.94  5204.5  632.17  5424.5  632.18  5644.5  633.38  5797.7  635.98
  5894.5  638.73  5984.5  640.39  6024.5  643.31  6079.4   644.8  6204.5  648.11
#Mann= 9 ,-1 , 0
  4504.5     .07       0  4644.5    .035       0  4686.8     .07       0
  4884.5    .035       0  4994.5    .035       0    5000    .035       0
  5055.7     .07       0  5797.7    .035       0  6079.4     .07       0
Bank Sta=4994.5,5000
XS Rating Curve= 0 ,0
Exp/Cntr=0.3,0.1

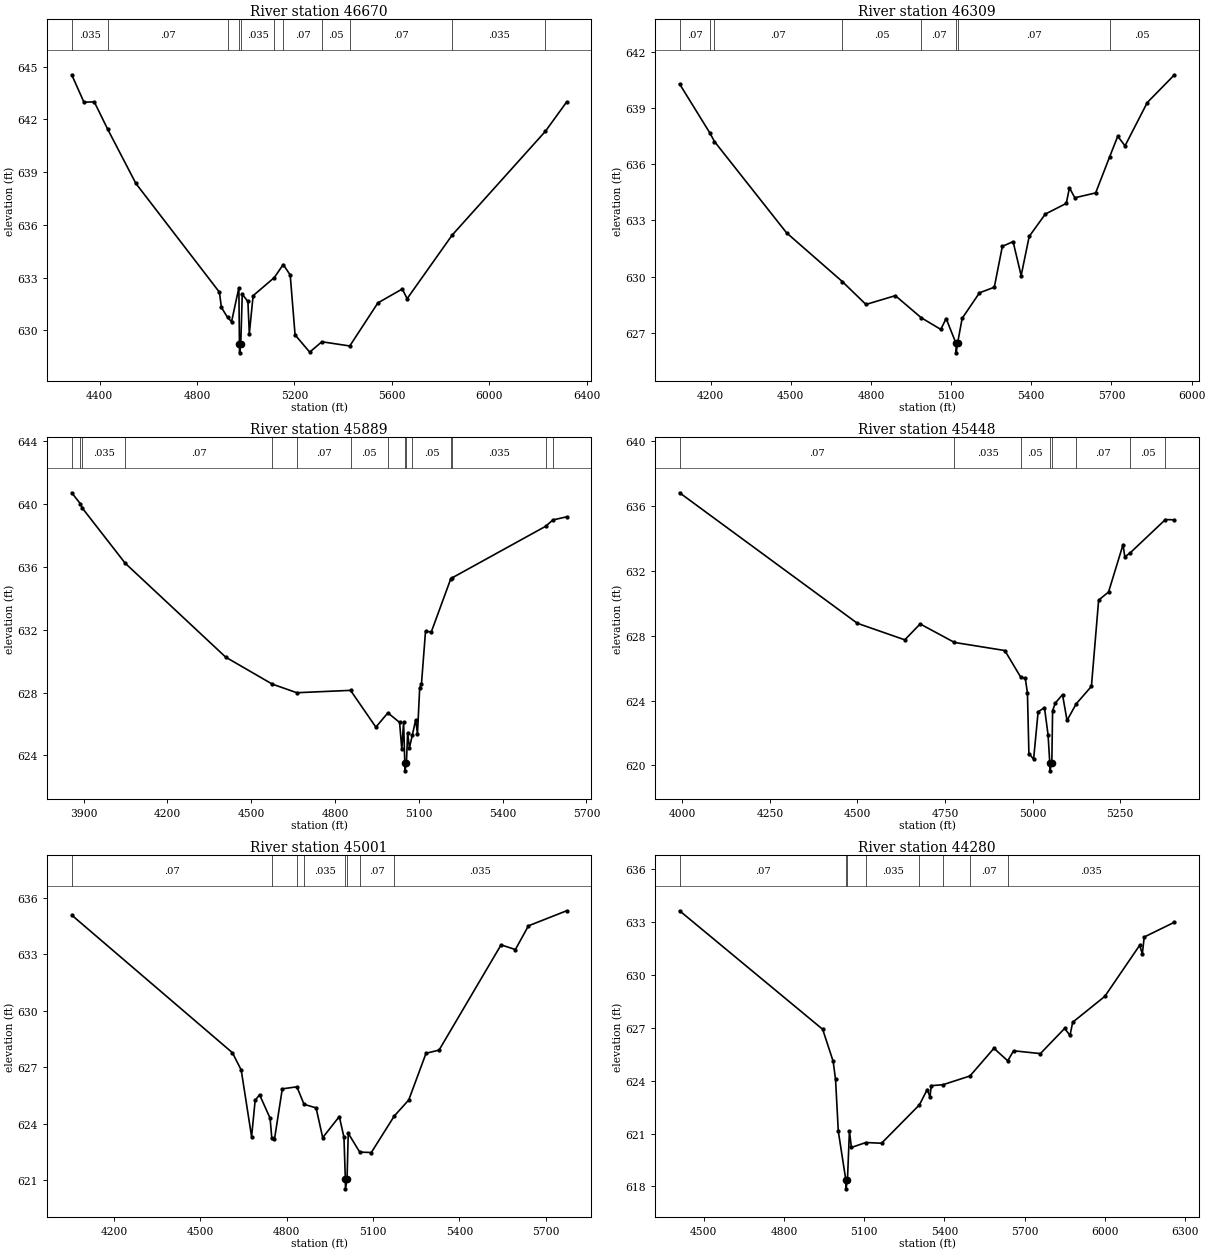
Type RM Length L Ch R = 1 ,46670   ,361,361,361
BEGIN DESCRIPTION:
LONG CREEK 71.0
END DESCRIPTION:
XS GIS Cut Line= 4
      2249874.99       13778825.      2249339.33     13778419.16
      2249211.29      13778343.2      2248000.39     13778373.58
#Sta/Elev= 30
  4285.4  644.53  4335.6  642.97    4378  642.99  4432.9  641.44  4548.9  638.35
  4891.8  632.17  4900.1   631.3  4925.2  630.74  4941.8  630.49  4971.8  632.42
  4974.1  629.22  4974.6  628.72  4979.6  629.22  4985.7  632.05  5008.9  631.64
  5014.7   629.8  5030.3  631.97  5117.4     633  5153.8  633.74  5182.6  633.15
  5202.6  629.74  5262.7  628.76  5312.7  629.35  5427.2  629.11  5542.7  631.56
  5642.8  632.35  5662.8   631.8  5847.4  635.41  6230.8  641.32  6317.6  642.98
#Mann= 11 ,-1 , 0
  4285.4    .035       0  4432.9     .07       0  4925.2    .035       0
  4974.1     .05       0  4979.6    .035       0  5117.4    .035       0
  5153.8     .07       0  5312.7     .05       0  5427.2     .07       0
  5847.4    .035       0  6230.8     .07       0
Bank Sta=4974.1,4979.6
XS Rating Curve= 0 ,0
Exp/Cntr=0.3,0.1

Type RM Length L Ch R = 1 ,46309   ,420,420,420
BEGIN DESCRIPTION:
A19812
END DESCRIPTION:
XS GIS Cut Line= 4
      2249818.72     13778647.46      2249290.93     13778112.73
      2248950.65     13778112.73      2248193.74     13778043.29
#Sta/Elev= 30
    4084  640.27  4197.1  637.66  4214.5   637.2  4484.3  632.33    4693  629.73
  4781.3  628.51  4891.3  628.98  4988.4   627.8  5061.3  627.18  5081.3  627.76
  5118.5  626.43    5119  625.93    5124  626.43  5141.3  627.77    5206  629.13
  5261.6  629.43  5291.7  631.61  5331.9  631.86    5362  630.05  5392.2  632.14
  5452.4  633.33  5530.8   633.9  5542.8  634.73  5562.9   634.2  5640.8  634.46
    5693  636.38  5723.5  637.48  5750.7  636.97    5834  639.28  5935.7  640.76
#Mann= 8 ,-1 , 0
    4084     .07       0  4197.1    .035       0  4214.5     .07       0
    4693     .05       0  4988.4     .07       0  5118.5     .05       0
    5124     .07       0    5693     .05       0
Bank Sta=5118.5,5124
XS Rating Curve= 0 ,0
Exp/Cntr=0.3,0.1

Type RM Length L Ch R = 1 ,45889   ,441,441,441
BEGIN DESCRIPTION:
LONG CREEK 70.0
END DESCRIPTION:
XS GIS Cut Line= 3
      2249974.99     13778574.99        2249175.       13777775.
      2248674.97     13777374.98
#Sta/Elev= 30
  3857.2  640.71  3888.3  640.01    3895  639.74  4048.6  636.23  4408.7  630.25
    4575  628.54  4662.9  627.99  4855.4  628.14  4946.1   625.8  4989.1  626.71
    5031   626.1    5039  624.38  5045.4  626.13  5049.6  623.52  5050.1  623.02
  5055.5  623.52  5059.8  625.45  5066.2  624.48  5076.9  625.31  5088.6  626.27
    5095  625.37    5103   628.3  5109.4  628.56  5123.8  631.89  5144.6  631.86
  5214.1  635.23  5218.3  635.29  5554.1  638.58  5579.7  638.98  5628.9  639.18
#Mann= 15 ,-1 , 0
  3857.2    .035       0  3888.3     .07       0    3895    .035       0
  4048.6     .07       0    4575     .05       0  4662.9     .07       0
  4855.4     .05       0  4989.1     .07       0  5049.6     .05       0
  5055.5     .07       0  5076.9     .05       0  5214.1     .07       0
  5218.3    .035       0  5554.1     .05       0  5579.7    .035       0
Bank Sta=5049.6,5055.5
XS Rating Curve= 0 ,0
Exp/Cntr=0.3,0.1

Type RM Length L Ch R = 1 ,45448   ,447,447,447
BEGIN DESCRIPTION:
LONG CREEK 69.0
END DESCRIPTION:
XS GIS Cut Line= 3
      2249975.02     13778375.03        2249375.       13777575.
      2248975.04     13777475.01
#Sta/Elev= 30
  3992.4  636.82  4499.7  628.77  4635.1  627.75  4678.9  628.73  4776.7  627.59
  4920.6  627.09  4966.4  625.43  4978.9  625.39  4985.1  624.47  4989.3  620.73
  5002.7  620.39  5015.6  623.31  5033.7  623.57    5044  621.89  5048.8  620.17
  5049.3  619.67  5054.7  620.17  5056.9  623.38  5064.6  623.85  5085.2  624.37
  5098.1  622.78  5124.2   623.8  5167.7  624.88  5188.3   630.2  5216.6   630.7
  5257.9  633.62    5263  632.87  5278.1  633.11  5378.9  635.17  5404.7  635.15
#Mann= 8 ,-1 , 0
  3992.4     .07       0  4776.7    .035       0  4966.4     .05       0
  5048.8     .05       0  5054.7     .05       0  5124.2     .07       0
  5278.1     .05       0  5378.9    .035       0
Bank Sta=5048.8,5054.7
XS Rating Curve= 0 ,0
Exp/Cntr=0.3,0.1

Type RM Length L Ch R = 1 ,45001   ,721,721,721
BEGIN DESCRIPTION:
LONG CREEK 68.0
END DESCRIPTION:
XS GIS Cut Line= 3
        2250225.       13778125.        2249725.       13777325.
      2248975.01       13777125.
#Sta/Elev= 30
  4052.8  635.09  4611.2  627.78  4641.8  626.86  4677.8  623.32  4690.2  625.25
  4705.5  625.55  4742.1   624.3  4748.1  623.24  4757.4  623.19  4784.5  625.86
  4835.3  625.97    4860  625.04  4901.9  624.85  4924.9  623.27  4982.6  624.39
  4998.8  623.29  5003.6  621.05  5004.1  620.55  5009.5  621.05  5013.7   623.5
  5053.7   622.5  5093.9  622.48  5173.7  624.42  5223.9  625.27    5284  627.75
  5329.3  627.92  5544.7  633.51  5594.5  633.26  5639.8  634.52  5772.4  635.32
#Mann= 8 ,-1 , 0
  4052.8     .07       0  4748.1    .035       0  4835.3     .07       0
    4860    .035       0  5003.6    .035       0  5009.5    .035       0
  5053.7     .07       0  5173.7    .035       0
Bank Sta=5003.6,5009.5
XS Rating Curve= 0 ,0
Exp/Cntr=0.3,0.1

Type RM Length L Ch R = 1 ,44280   ,507,507,507
BEGIN DESCRIPTION:
A19811
END DESCRIPTION:
XS GIS Cut Line= 4
      2250283.98     13778036.32      2250027.04     13777119.68
      2249631.21     13777008.57      2249145.11     13777036.34
#Sta/Elev= 30
  4409.7  633.65  4944.5  626.92  4983.8   625.1  4992.7  624.07    5003  621.13
  5031.2  618.36  5031.7  617.86  5037.2  618.36  5044.6  621.13    5052  620.21
    5106  620.49  5164.7  620.45  5306.3  622.63  5335.4   623.5  5345.6  623.08
  5350.8  623.72  5393.9  623.77  5495.3  624.27  5584.8  625.84  5636.5  625.13
  5658.2   625.7  5758.5  625.54  5849.1  626.97  5869.2  626.57  5879.2  627.32
  5999.4  628.79  6129.6  631.69  6139.6   631.2  6146.6  632.16  6259.7     633
#Mann= 8 ,-1 , 0
  4409.7     .07       0  5031.2     .05       0  5037.2     .07       0
    5106    .035       0  5306.3     .05       0  5393.9    .035       0
  5495.3     .07       0  5636.5    .035       0
Bank Sta=5031.2,5037.2
XS Rating Curve= 0 ,0
Exp/Cntr=0.3,0.1

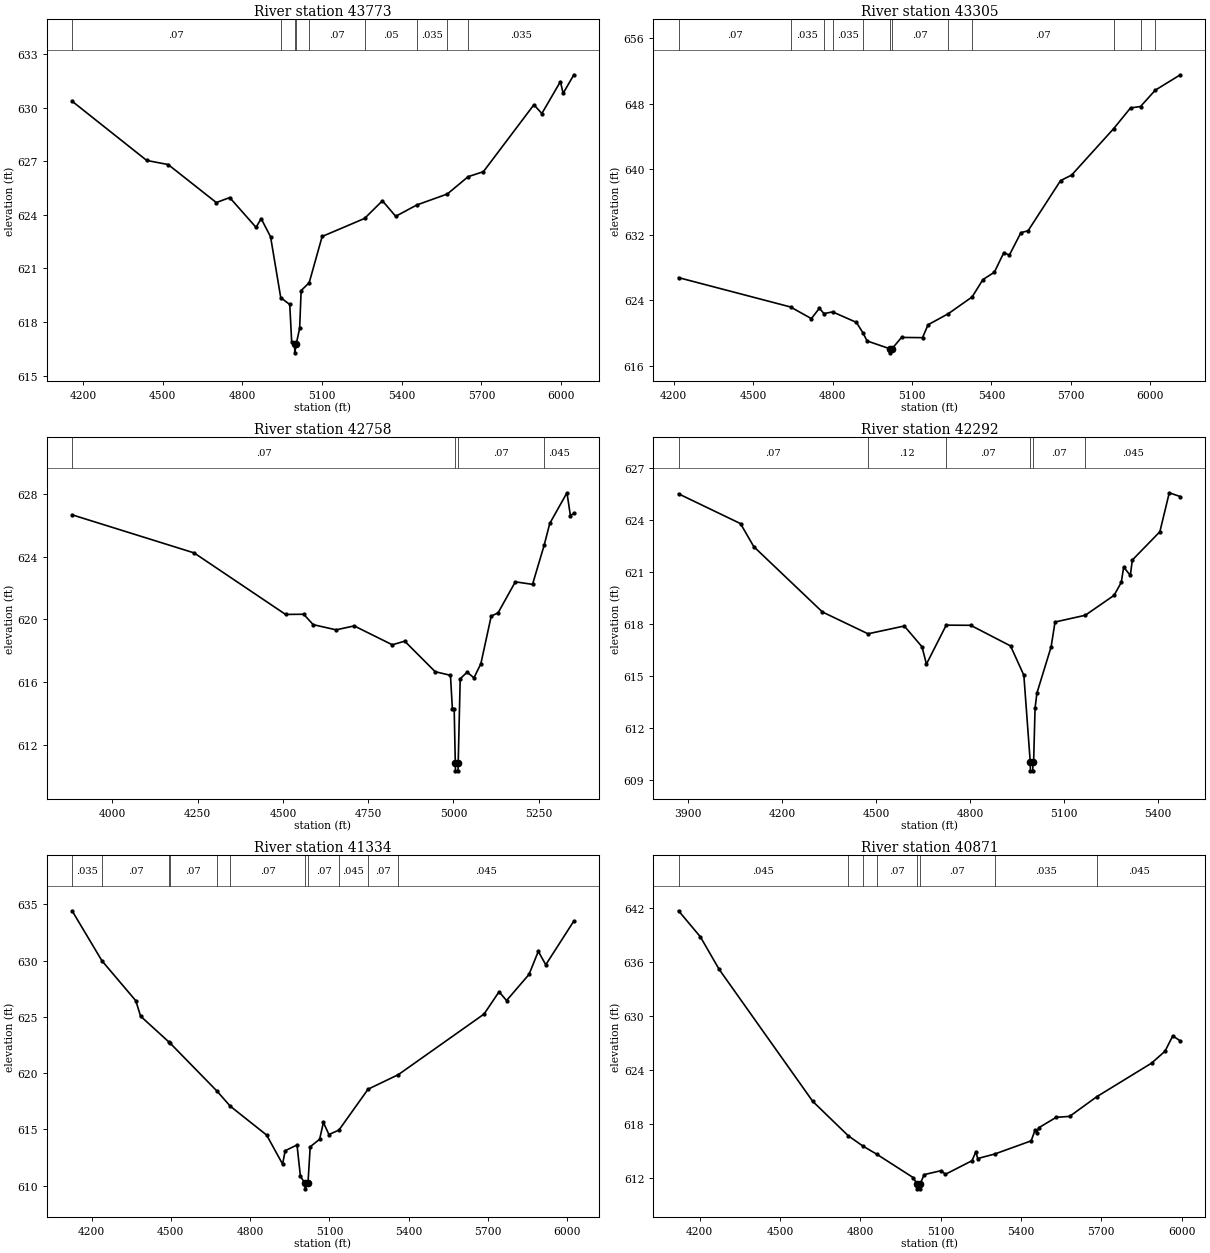
Type RM Length L Ch R = 1 ,43773   ,468,468,468
BEGIN DESCRIPTION:
A19810
END DESCRIPTION:
XS GIS Cut Line= 4
       2250332.6     13777723.84      2250415.93     13777071.07
      2249999.26     13776911.34      2249214.56     13776939.12
#Sta/Elev= 30
  4158.5  630.37  4439.6  627.05  4520.3  626.82  4701.7  624.69  4752.1  624.97
  4851.3   623.3  4870.6  623.79    4906  622.77  4944.3  619.36  4978.2  618.98
  4985.4  616.89  4996.6  616.77  4997.1  616.27  5002.6  616.77  5015.4  617.64
  5021.1  619.76  5051.4   620.2  5100.2  622.79  5259.9   623.8  5327.1  624.79
  5377.1  623.92  5457.4  624.56  5571.5  625.17  5649.9  626.14  5707.3  626.42
  5897.5  630.17  5927.5  629.68  5997.5  631.47  6007.5  630.81    6048  631.85
#Mann= 9 ,-1 , 0
  4158.5     .07       0  4944.3    .035       0  4996.6    .035       0
  5002.6    .035       0  5051.4     .07       0  5259.9     .05       0
  5457.4    .035       0  5571.5     .05       0  5649.9    .035       0
Bank Sta=4996.6,5002.6
XS Rating Curve= 0 ,0
Exp/Cntr=0.3,0.1

Type RM Length L Ch R = 1 ,43305   ,547,547,547
BEGIN DESCRIPTION:
A19809
END DESCRIPTION:
XS GIS Cut Line= 4
       2250395.1     13777397.44      2250485.38     13776953.01
      2250464.54     13776314.12      2249979.24     13775676.29
#Sta/Elev= 30
  4218.6  626.78  4641.5   623.2  4720.1  621.78  4750.2  623.05  4767.4   622.4
  4800.5   622.6  4890.2  621.32  4914.5  620.06  4930.3  619.06  5016.1  618.11
  5016.6  617.61  5024.5  618.11  5060.3  619.49  5139.6  619.46  5160.4  621.03
  5236.9  622.38  5326.7  624.42  5367.6  626.54  5410.8  627.44  5446.6  629.83
  5467.4  629.52    5511  632.26  5538.1  632.49  5660.7  638.61  5702.4  639.28
  5861.6  644.96  5924.8  647.47  5962.5  647.64  6018.1  649.63  6112.8  651.51
#Mann= 12 ,-1 , 0
  4218.6     .07       0  4641.5    .035       0  4767.4     .07       0
  4800.5    .035       0  4914.5     .07       0  5016.1     .05       0
  5024.5     .07       0  5236.9     .05       0  5326.7     .07       0
  5861.6     .05       0  5962.5    .035       0  6018.1     .05       0
Bank Sta=5016.1,5024.5
XS Rating Curve= 0 ,0
Exp/Cntr=0.3,0.1

Type RM Length L Ch R = 1 ,42758   ,466,466,466
BEGIN DESCRIPTION:
LONG CREEK 67.0
END DESCRIPTION:
XS GIS Cut Line= 3
      2250424.99     13777375.02        2250925.       13776375.
        2250875.       13776025.
#Sta/Elev= 30
  3881.5  626.65  4239.3  624.23  4507.6  620.32  4560.7  620.33  4588.7  619.67
  4655.8  619.34  4708.9  619.59  4820.7  618.39    4857  618.62  4946.4  616.68
  4991.2  616.45  4996.8  614.34  5002.1  614.34  5005.4  610.88  5005.9  610.38
  5013.4  610.38  5013.9  610.88  5019.8  616.23    5040  616.65  5060.2  616.29
  5080.4  617.19  5110.7  620.21  5130.9  620.42  5181.4  622.39  5231.9  622.23
  5266.3  624.74  5282.4   626.1  5332.9  628.05    5343  626.59  5353.1  626.75
#Mann= 4 ,-1 , 0
  3881.5     .07       0  5005.4     .05       0  5013.9     .07       0
  5266.3    .045       0
Bank Sta=5005.4,5013.9
XS Rating Curve= 0 ,0
Exp/Cntr=0.3,0.1

Type RM Length L Ch R = 1 ,42292   ,958,958,958
BEGIN DESCRIPTION:
LONG CREEK 66.0
END DESCRIPTION:
XS GIS Cut Line= 3
      2250575.02     13777224.98        2251375.       13776425.
      2251125.02     13776025.04
#Sta/Elev= 30
  3869.2   625.5  4067.2  623.78  4109.6  622.45  4328.8  618.68  4474.5  617.42
  4590.4  617.87    4647  616.67  4661.1  615.67  4724.3  617.92  4802.6  617.91
  4929.8  616.72  4972.3  615.03  4992.8  610.01  4993.3  609.51  5000.8  609.51
  5001.3  610.01  5003.5  610.01  5008.2  613.14  5014.1     614  5059.5  616.67
  5071.9   618.1  5168.5  618.49  5260.6  619.64  5283.6  620.39  5291.2  621.27
  5312.5  620.79  5318.9  621.68  5406.8  623.31  5436.9  625.56  5472.2  625.34
#Mann= 6 ,-1 , 0
  3869.2     .07       0  4474.5     .12       0  4724.3     .07       0
  4992.8     .05       0  5001.3     .07       0  5168.5    .045       0
Bank Sta=4992.8,5001.3
XS Rating Curve= 0 ,0
Exp/Cntr=0.3,0.1

Type RM Length L Ch R = 1 ,41334   ,463,463,463
BEGIN DESCRIPTION:
LONG CREEK 65.0
END DESCRIPTION:
XS GIS Cut Line= 3
      2252575.02     13777025.04        2252225.       13776225.
      2251474.98     13775524.98
#Sta/Elev= 30
  4126.1  634.44  4239.3  629.99  4367.4  626.44  4385.4  625.07  4494.7  622.73
  4495.3  622.72    4675   618.4  4724.7  617.07  4862.5   614.5  4922.9  611.92
  4932.7  613.11  4977.5  613.62  4990.4  610.83  5007.6  610.22  5008.1  609.72
    5019  610.22  5027.4  613.46  5063.1  614.13  5077.3  615.62  5098.3  614.55
    5136  614.94  5246.5  618.58  5360.9  619.87  5685.5  625.26  5742.2  627.24
  5770.5  626.46  5855.5  628.78  5890.7  630.83    5919  629.64  6025.3  633.53
#Mann= 11 ,-1 , 0
  4126.1    .035       0  4239.3     .07       0  4494.7    .035       0
  4495.3     .07       0    4675    .035       0  4724.7     .07       0
  5007.6     .05       0    5019     .07       0    5136    .045       0
  5246.5     .07       0  5360.9    .045       0
Bank Sta=5007.6,5019
XS Rating Curve= 0 ,0
Exp/Cntr=0.3,0.1

Type RM Length L Ch R = 1 ,40871   ,451,451,451
BEGIN DESCRIPTION:
LONG CREEK 64.0
END DESCRIPTION:
XS GIS Cut Line= 3
      2253325.01     13776525.01        2252575.       13776075.
      2251774.97     13775474.97
#Sta/Elev= 30
  4120.8  641.72  4202.4  638.82  4272.4  635.21  4622.3  620.51  4755.5  616.67
  4809.7  615.54  4860.9  614.64  4998.6  612.01  5011.6  611.28  5012.1  610.78
  5022.6  610.78  5023.1  611.28  5038.2  612.36  5102.7  612.81  5117.3  612.39
  5217.3  613.91  5231.9  614.93  5238.2  614.15  5301.7  614.65  5438.2  616.12
  5452.7   617.3    5459  617.03  5467.3  617.59  5531.9  618.74  5581.9  618.84
  5683.8  621.04  5888.2  624.77  5938.2  626.09  5967.3   627.8  5995.5  627.24
#Mann= 8 ,-1 , 0
  4120.8    .045       0  4755.5     .07       0  4809.7    .045       0
  4860.9     .07       0  5011.6     .05       0  5023.1     .07       0
  5301.7    .035       0  5683.8    .045       0
Bank Sta=5011.6,5023.1
XS Rating Curve= 0 ,0
Exp/Cntr=0.3,0.1