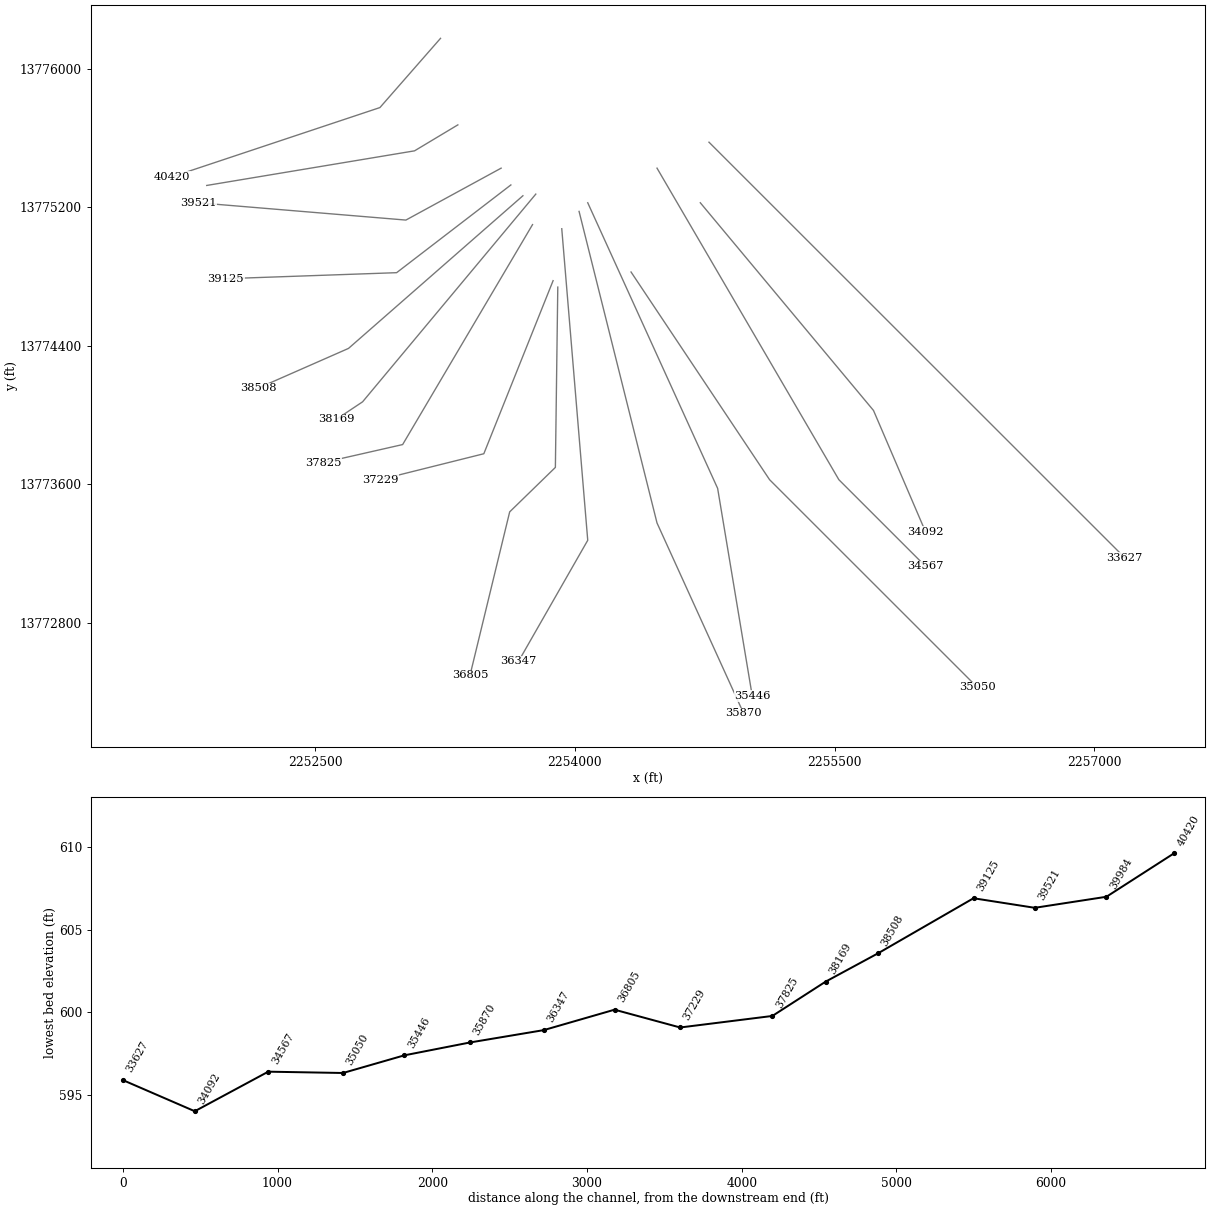
HEC-RAS study LONG CREEK.prj: LONG CREEK Base Level Engineering

--- LONG CREEK.g01 (geometry) --- (continued)

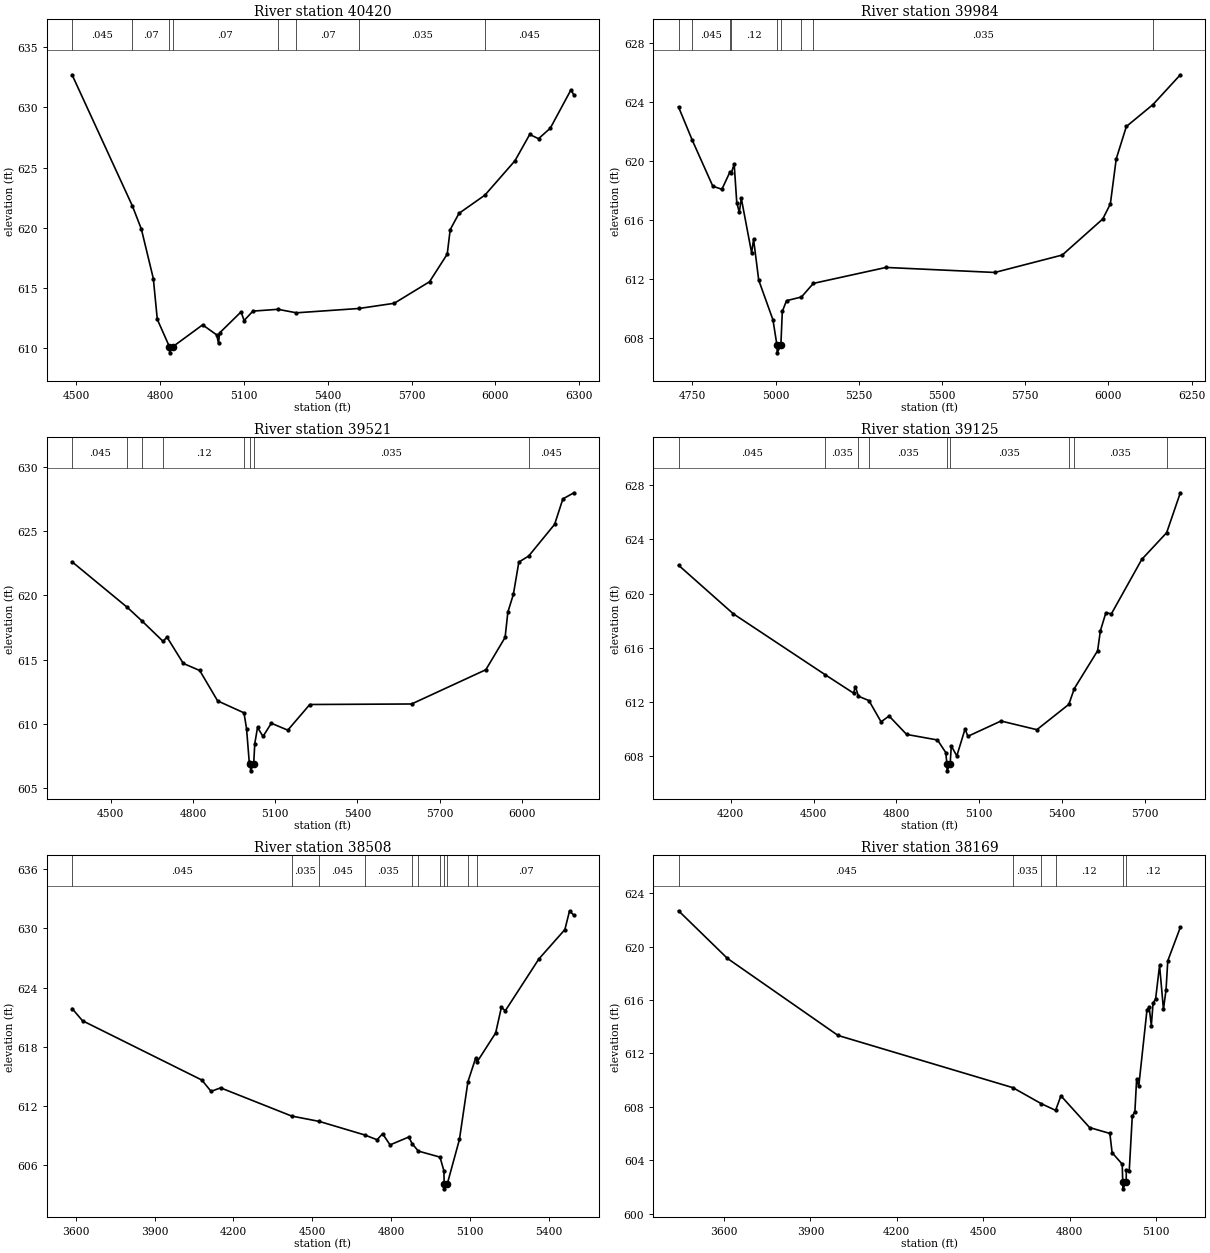
Type RM Length L Ch R = 1 ,40420   ,436,436,436
BEGIN DESCRIPTION:
LONG CREEK 63.0
END DESCRIPTION:
XS GIS Cut Line= 3
      2253224.97     13776174.97        2252875.       13775775.
      2251674.97     13775374.99
#Sta/Elev= 30
  4484.3  632.69  4700.1  621.82  4732.4  619.89  4775.2  615.79  4789.4  612.41
    4833  610.13  4833.5  609.63  4844.5  610.13  4951.7  611.95    5002  611.12
  5008.6  610.43  5012.4  611.28  5089.5  613.03  5100.1  612.31  5131.7  613.09
  5221.3  613.24  5287.4  612.95  5512.1  613.31  5637.7  613.74  5764.2  615.53
  5827.4  617.82    5838  619.85  5869.6   621.2  5962.3  622.71  6069.9  625.56
  6122.6  627.74  6154.2  627.39  6196.3  628.26  6270.1  631.43  6280.7  631.02
#Mann= 8 ,-1 , 0
  4484.3    .045       0  4700.1     .07       0    4833     .05       0
  4844.5     .07       0  5221.3    .035       0  5287.4     .07       0
  5512.1    .035       0  5962.3    .045       0
Bank Sta=4833,4844.5
XS Rating Curve= 0 ,0
Exp/Cntr=0.3,0.1

Type RM Length L Ch R = 1 ,39984   ,463,463,463
BEGIN DESCRIPTION:
LONG CREEK 62.0
END DESCRIPTION:
XS GIS Cut Line= 3
      2253325.03     13775675.02        2253075.       13775525.
      2251875.04     13775325.01
#Sta/Elev= 30
  4708.1  623.64  4749.6  621.38  4811.1  618.28  4838.4  618.07  4862.4  619.23
  4866.5  619.15  4875.3  619.79  4883.1  617.17  4890.8  616.51  4896.7  617.46
  4927.8  613.76  4933.6  614.69  4949.1  611.92  4991.9  609.23    5004   607.5
  5004.5     607  5015.6   607.5    5020   609.8  5032.6  610.53  5077.5  610.78
  5113.3   611.7  5331.7  612.78  5658.6  612.44  5861.4  613.62  5983.1  616.06
  6005.9  617.08  6023.6  620.13    6054  622.32  6133.8   623.8  6216.2  625.82
#Mann= 9 ,-1 , 0
  4708.1     .07       0  4749.6    .045       0  4862.4     .07       0
  4866.5     .12       0    5004     .05       0  5015.6     .12       0
  5077.5     .07       0  5113.3    .035       0  6133.8    .045       0
Bank Sta=5004,5015.6
XS Rating Curve= 0 ,0
Exp/Cntr=0.3,0.1

Type RM Length L Ch R = 1 ,39521   ,396,396,396
BEGIN DESCRIPTION:
LONG CREEK 61.0
END DESCRIPTION:
XS GIS Cut Line= 3
      2253574.98     13775424.99        2253025.       13775125.
      2251825.04       13775225.
#Sta/Elev= 30
  4359.1  622.62  4561.1  619.06  4613.7  618.02  4691.2  616.42  4705.1  616.76
  4764.9   614.7  4824.7  614.15  4890.2  611.78  4986.3  610.85  4995.6  609.62
  5005.6  606.98  5009.9  606.83  5010.4  606.33  5021.5  606.83  5025.7  608.46
  5035.7  609.71  5055.8  609.01  5085.9  610.04  5146.1   609.5  5226.4   611.5
  5597.7  611.54  5868.6  614.21  5938.9  616.73  5948.9   618.7    5969  620.08
    5989   622.6  6024.9  623.07  6119.5  625.54  6149.6  627.52  6189.7     628
#Mann= 8 ,-1 , 0
  4359.1    .045       0  4561.1     .07       0  4613.7    .045       0
  4691.2     .12       0  4986.3    .035       0  5009.9    .035       0
  5021.5    .035       0  6024.9    .045       0
Bank Sta=5009.9,5021.5
XS Rating Curve= 0 ,0
Exp/Cntr=0.3,0.1

Type RM Length L Ch R = 1 ,39125   ,617,617,617
BEGIN DESCRIPTION:
A19808
END DESCRIPTION:
XS GIS Cut Line= 3
       2253631.2       13775328.      2252971.49     13774821.07
      2251985.39     13774786.34
#Sta/Elev= 30
  4010.8   622.1  4209.3  618.51  4541.6  614.02  4645.2  612.65  4651.5  613.14
    4663  612.42  4700.8   612.1  4744.9  610.53  4773.9  610.96  4837.4   609.6
  4949.3  609.19  4979.4  608.26  4983.6  607.41  4984.1  606.91  4995.2  607.41
  4999.4  608.75  5019.4  608.01  5049.4  610.01  5059.4  609.46  5179.5  610.59
  5309.6  609.95  5425.4  611.82  5445.3  612.99  5529.7  615.78  5539.7  617.25
  5559.7  618.59  5579.7  618.51  5689.8  622.53  5779.9   624.5  5829.5  627.45
#Mann= 9 ,-1 , 0
  4010.8    .045       0  4541.6    .035       0    4663     .12       0
  4700.8    .035       0  4983.6    .035       0  4995.2    .035       0
  5425.4     .07       0  5445.3    .035       0  5779.9    .045       0
Bank Sta=4983.6,4995.2
XS Rating Curve= 0 ,0
Exp/Cntr=0.3,0.1

Type RM Length L Ch R = 1 ,38508   ,339,339,339
BEGIN DESCRIPTION:
A19807
END DESCRIPTION:
XS GIS Cut Line= 3
      2253700.63     13775265.49      2252693.71     13774383.57
      2252172.84     13774154.38
#Sta/Elev= 30
  3586.5  621.87  3626.2  620.63  4079.9  614.61    4115  613.46    4151  613.82
    4421  610.96  4526.6  610.41  4698.8  609.04  4746.1  608.55    4767  609.16
  4795.4  608.03  4866.6  608.83  4879.5  608.14    4903   607.4  4985.2  606.79
  5000.1  605.39  5001.1  604.07  5001.6  603.57  5012.9  604.07  5059.1  608.58
  5091.4  614.44  5120.3   616.8  5127.1  616.49  5196.8  619.39  5218.6  621.99
  5233.4  621.64  5361.1   626.9  5459.9  629.88  5477.8  631.79  5494.1  631.33
#Mann= 11 ,-1 , 0
  3586.5    .045       0    4421    .035       0  4526.6    .045       0
  4698.8    .035       0  4879.5     .07       0    4903     .12       0
  4985.2     .07       0  5001.1     .05       0  5012.9     .07       0
  5091.4     .12       0  5127.1     .07       0
Bank Sta=5001.1,5012.9
XS Rating Curve= 0 ,0
Exp/Cntr=0.3,0.1

Type RM Length L Ch R = 1 ,38169   ,344,344,344
BEGIN DESCRIPTION:
LONG CREEK 60.0
END DESCRIPTION:
XS GIS Cut Line= 3
      2253775.03     13775275.03        2252775.       13774075.
      2252624.97     13773974.98
#Sta/Elev= 30
  3442.1  622.68    3612  619.11    3996  613.34  4602.9  609.43  4701.7  608.23
  4751.4  607.73  4769.9  608.82  4869.5  606.44  4939.8     606  4947.6  604.56
  4982.7   603.7  4984.6  602.35  4985.1  601.85  4996.5  602.35    4997  603.25
  5007.2  603.22  5017.7  607.31  5026.7  607.62  5032.7  610.05  5040.2  609.55
  5068.8  615.27  5076.3  615.45  5083.8  614.08  5089.8  615.75  5098.8  616.09
  5112.4  618.59  5125.9   615.3  5134.9  616.76  5140.9  618.93  5184.5  621.44
#Mann= 6 ,-1 , 0
  3442.1    .045       0  4602.9    .035       0  4701.7    .045       0
  4751.4     .12       0  4984.6     .05       0  4996.5     .12       0
Bank Sta=4984.6,4996.5
XS Rating Curve= 0 ,0
Exp/Cntr=0.3,0.1

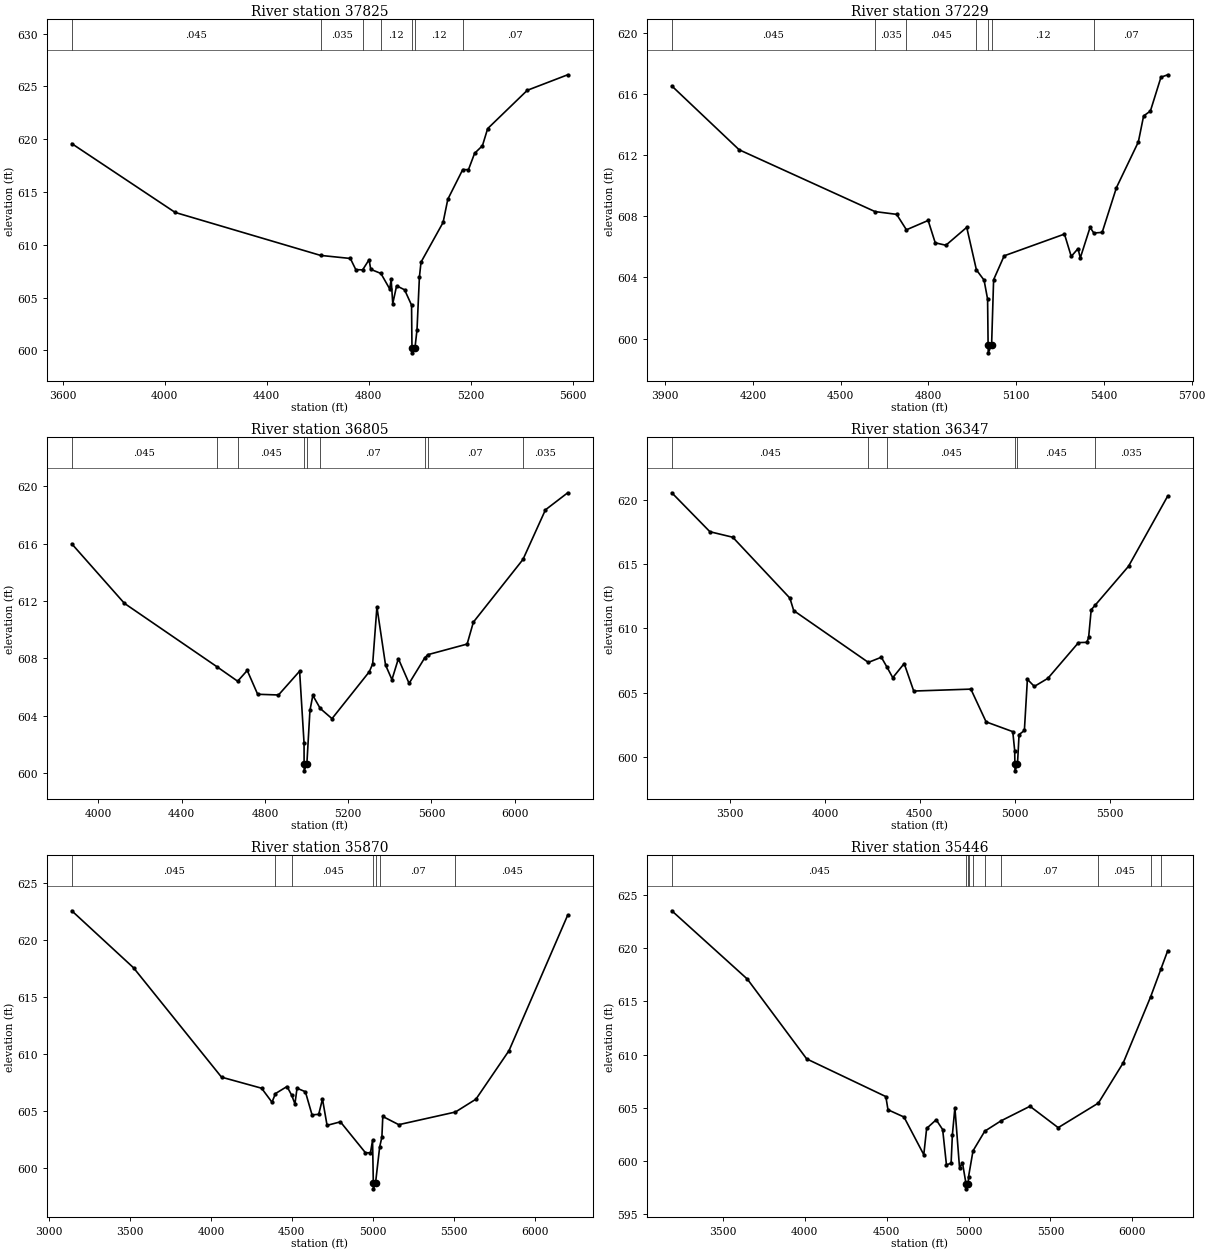
Type RM Length L Ch R = 1 ,37825   ,596,596,596
BEGIN DESCRIPTION:
A19806
END DESCRIPTION:
XS GIS Cut Line= 3
      2253756.23     13775098.87      2253006.21     13773828.01
      2252548.95     13773724.09
#Sta/Elev= 30
    3636  619.59  4041.4  613.07  4611.5     609  4728.3  608.71  4749.7  607.65
  4776.4  607.63  4801.7  608.59  4808.3  607.68  4848.1  607.29  4882.5  605.83
  4888.3  606.72  4894.6  604.44  4909.7  606.12    4941  605.74  4968.3  604.29
  4969.9  600.27  4970.4  599.77  4981.8  600.27  4989.7  601.96  4999.1  606.95
  5005.4  608.36  5091.9  612.12  5110.5  614.32    5169  617.13  5191.4  617.12
  5215.5  618.67  5246.2  619.39  5266.7  621.01  5422.1  624.64  5580.6  626.11
#Mann= 7 ,-1 , 0
    3636    .045       0  4611.5    .035       0  4776.4    .045       0
  4848.1     .12       0  4969.9     .05       0  4981.8     .12       0
    5169     .07       0
Bank Sta=4969.9,4981.8
XS Rating Curve= 0 ,0
Exp/Cntr=0.3,0.1

Type RM Length L Ch R = 1 ,37229   ,424,424,424
BEGIN DESCRIPTION:
LONG CREEK 59.0
END DESCRIPTION:
XS GIS Cut Line= 3
      2253874.99     13774774.97        2253475.       13773775.
      2252874.96     13773624.99
#Sta/Elev= 30
  3922.7  616.51  4152.9  612.34  4617.5   608.3  4691.4  608.12  4724.8  607.11
  4799.1  607.72  4823.3  606.26  4859.7   606.1    4931  607.27  4964.1  604.49
  4990.3  603.82  5002.3  602.58  5004.1  599.57  5004.6  599.07    5016  599.57
  5022.9  603.85    5059  605.41  5265.1  606.83  5288.3  605.37  5311.5  605.88
  5319.2  605.27  5352.7  607.27  5365.4   606.9    5394  606.94  5442.9  609.87
  5517.7  612.85  5535.7  614.55  5558.9  614.87    5595  617.08  5618.2  617.24
#Mann= 7 ,-1 , 0
  3922.7    .045       0  4617.5    .035       0  4724.8    .045       0
  4964.1     .12       0  5004.1     .05       0    5016     .12       0
  5365.4     .07       0
Bank Sta=5004.1,5016
XS Rating Curve= 0 ,0
Exp/Cntr=0.3,0.1

Type RM Length L Ch R = 1 ,36805   ,458,458,458
BEGIN DESCRIPTION:
A19805
END DESCRIPTION:
XS GIS Cut Line= 4
      2253902.04     13774737.76      2253888.15     13773696.07
      2253624.26     13773439.12      2253395.09     13772494.64
#Sta/Elev= 30
  3872.4  615.98  4125.2  611.83  4570.6   607.4  4669.1   606.4  4715.2  607.15
  4765.2  605.49  4865.3  605.44  4966.7   607.1    4988  602.09  4988.3  600.65
  4988.8  600.15  5001.6  600.65  5016.3  604.36  5030.2  605.41  5065.7   604.5
  5122.3  603.79  5301.4  607.06  5317.6  607.61    5338  611.58  5379.4  607.53
  5410.2  606.51  5441.1  607.97  5492.6  606.25  5567.7  608.03  5582.6  608.25
  5771.3  608.99  5801.3  610.52  6039.5  614.89  6147.4  618.35  6254.4  619.54
#Mann= 9 ,-1 , 0
  3872.4    .045       0  4570.6    .035       0  4669.1    .045       0
  4988.3    .045       0  5001.6    .045       0  5065.7     .07       0
  5567.7    .035       0  5582.6     .07       0  6039.5    .035       0
Bank Sta=4988.3,5001.6
XS Rating Curve= 0 ,0
Exp/Cntr=0.3,0.1

Type RM Length L Ch R = 1 ,36347   ,477,477,477
BEGIN DESCRIPTION:
LONG CREEK 58.0
END DESCRIPTION:
XS GIS Cut Line= 3
        2253925.       13775075.        2254075.       13773275.
      2253674.98     13772574.97
#Sta/Elev= 30
  3193.5  620.55  3394.2  617.52  3514.6  617.09  3815.6  612.35  3835.7  611.38
  4228.9  607.35  4297.3  607.75  4327.5  606.97  4357.5  606.16  4417.7  607.26
  4467.9  605.12  4768.9  605.27  4849.2  602.72  4989.7  601.96  4999.7  600.49
    5001  599.41  5001.5  598.91  5014.4  599.41  5022.8  601.73  5050.8  602.05
  5066.7  606.03  5103.4  605.48  5174.7  606.11  5335.9  608.89  5379.8  608.91
  5389.2  609.29  5402.8  611.45  5423.1  611.79  5599.4  614.83    5806   620.3
#Mann= 6 ,-1 , 0
  3193.5    .045       0  4228.9    .035       0  4327.5    .045       0
    5001    .045       0  5014.4    .045       0  5423.1    .035       0
Bank Sta=5001,5014.4
XS Rating Curve= 0 ,0
Exp/Cntr=0.3,0.1

Type RM Length L Ch R = 1 ,35870   ,424,424,424
BEGIN DESCRIPTION:
LONG CREEK 57.0
END DESCRIPTION:
XS GIS Cut Line= 3
        2254025.     13775174.98        2254475.       13773375.
      2254975.01     13772274.98
#Sta/Elev= 30
  3140.7  622.56  3522.1  617.56  4065.8  607.96  4313.2  606.99  4377.6  605.76
    4399  606.52  4470.4  607.14  4499.7  606.36  4519.3  605.61  4532.2  606.99
  4583.8  606.68    4625  604.65  4666.2   604.7  4689.4  606.04  4717.8  603.73
  4800.2  604.04  4954.8  601.33  4985.8  601.32  4998.8  602.41  5003.6  598.66
  5004.1  598.16  5017.1  598.66  5042.8  601.84  5056.5   602.7    5062  604.51
  5160.8  603.79  5510.6   604.9  5637.6  606.03  5841.9  610.29  6204.4  622.18
#Mann= 7 ,-1 , 0
  3140.7    .045       0    4399    .035       0  4499.7    .045       0
  5003.6    .045       0  5017.1    .045       0  5042.8     .07       0
  5510.6    .045       0
Bank Sta=5003.6,5017.1
XS Rating Curve= 0 ,0
Exp/Cntr=0.3,0.1

Type RM Length L Ch R = 1 ,35446   ,396,396,396
BEGIN DESCRIPTION:
LONG CREEK 56.0
END DESCRIPTION:
XS GIS Cut Line= 3
      2254074.99     13775225.02        2254825.       13773575.
      2255024.99     13772375.03
#Sta/Elev= 30
  3187.3  623.51  3648.7  617.09  4011.2  609.59  4494.5  606.05  4507.7  604.81
  4605.4  604.13  4726.3  600.59  4743.8  603.06  4802.1  603.87  4841.6  602.95
  4864.7  599.64  4893.2  599.78  4900.9  602.44  4916.3  605.01  4944.9  599.32
  4962.4  599.84    4984  597.88  4984.5  597.38    4998  597.88  4999.5   598.5
    5027  600.95  5098.8   602.8  5198.1  603.77  5374.9  605.14  5547.2  603.13
  5792.7  605.44  5945.1  609.24  6111.7  615.42  6174.5  618.03  6216.3  619.76
#Mann= 10 ,-1 , 0
  3187.3    .045       0    4984    .035       0    4998    .045       0
  4999.5    .035       0    5027     .07       0  5098.8    .035       0
  5198.1     .07       0  5792.7    .045       0  6111.7     .07       0
  6174.5    .045       0
Bank Sta=4984,4998
XS Rating Curve= 0 ,0
Exp/Cntr=0.3,0.1

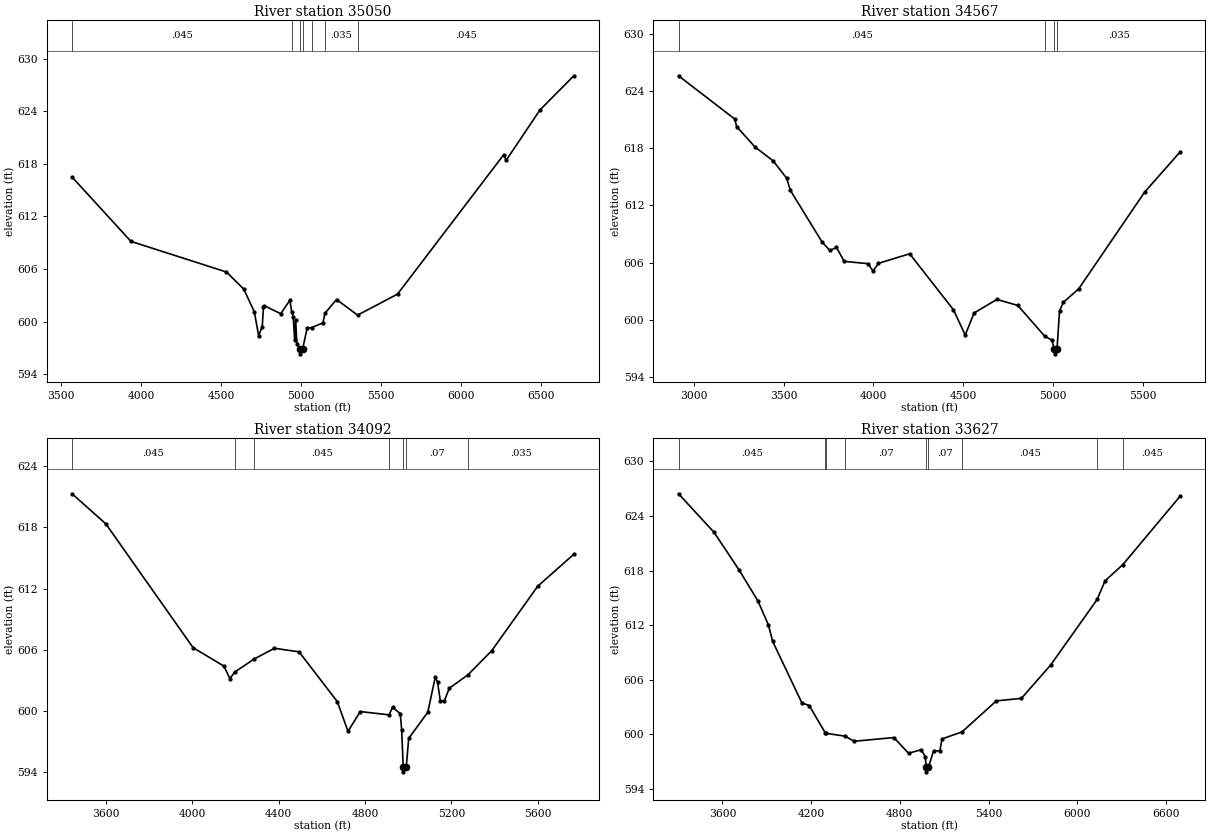
Type RM Length L Ch R = 1 ,35050   ,483,483,483
BEGIN DESCRIPTION:
LONG CREEK 55.0
END DESCRIPTION:
XS GIS Cut Line= 3
      2254324.98     13774825.04        2255125.       13773625.
      2256324.99     13772425.01
#Sta/Elev= 30
  3567.5  616.49  3935.6  609.15  4533.5  605.65  4641.7   603.7  4707.8   601.1
  4734.8  598.39  4757.4  599.42  4764.9  601.67  4770.9   601.8  4873.1  600.89
  4930.1  602.43  4941.9  601.07  4951.2  600.56  4960.2  597.92  4966.2  600.16
  4973.7  597.44  4995.2  596.81  4995.7  596.31  5009.3  596.81    5038  599.24
  5065.8   599.3    5137  599.85  5149.9  600.95  5221.9  602.51  5353.8  600.73
  5603.7  603.13  6268.4  619.05  6282.6  618.38  6494.7  624.15  6706.8  628.05
#Mann= 7 ,-1 , 0
  3567.5    .045       0  4941.9    .035       0  4995.2    .035       0
  5009.3    .035       0  5065.8     .07       0  5149.9    .035       0
  5353.8    .045       0
Bank Sta=4995.2,5009.3
XS Rating Curve= 0 ,0
Exp/Cntr=0.3,0.1

Type RM Length L Ch R = 1 ,34567   ,475,475,475
BEGIN DESCRIPTION:
LONG CREEK 54.0
END DESCRIPTION:
XS GIS Cut Line= 3
        2254475.       13775425.        2255525.       13773625.
      2256025.02     13773124.98
#Sta/Elev= 30
  2915.9  625.65  3228.9  621.09  3238.8  620.31  3340.5  618.17  3442.2  616.69
  3516.7  614.89  3538.2  613.58  3714.3  608.16  3757.3  607.27  3794.5  607.58
  3837.5  606.12  3969.4  605.88  3997.9   605.1  4027.3  605.91  4201.4  606.92
  4444.1  601.05  4510.6  598.37  4559.8  600.69  4686.8  602.12    4803  601.48
  4952.5  598.25  4991.9  597.84  5006.9  596.89  5007.4  596.39    5021  596.89
  5035.1  600.91  5056.3  601.81  5141.2  603.22  5508.9  613.42  5706.9  617.66
#Mann= 4 ,-1 , 0
  2915.9    .045       0  4952.5    .035       0  5006.9    .035       0
    5021    .035       0
Bank Sta=5006.9,5021
XS Rating Curve= 0 ,0
Exp/Cntr=0.3,0.1

Type RM Length L Ch R = 1 ,34092   ,465,465,465
BEGIN DESCRIPTION:
LONG CREEK 53.0
END DESCRIPTION:
XS GIS Cut Line= 3
      2254724.98     13775225.02        2255725.       13774025.
      2256025.02     13773324.96
#Sta/Elev= 30
    3443  621.31  3599.2  618.36  4003.4  606.19    4146  604.38  4173.9  603.16
  4196.2  603.79  4286.3  605.08  4380.3  606.13  4494.2  605.78  4671.2  600.89
  4720.7  597.98  4777.9  599.91  4911.2  599.59    4927  600.33  4962.8  599.71
  4969.3   598.1  4976.6  594.49  4977.1  593.99  4990.7  594.49  5001.8  597.27
  5090.3  599.85  5124.8  603.29  5135.6  602.79  5148.3  600.97  5166.5  600.95
    5190  602.21  5275.8  603.51  5385.9  605.88  5599.8  612.24  5766.7  615.37
#Mann= 7 ,-1 , 0
    3443    .045       0  4196.2    .035       0  4286.3    .045       0
  4911.2     .07       0  4976.6     .05       0  4990.7     .07       0
  5275.8    .035       0
Bank Sta=4976.6,4990.7
XS Rating Curve= 0 ,0
Exp/Cntr=0.3,0.1

Type RM Length L Ch R = 1 ,33627   ,444,444,444
BEGIN DESCRIPTION:
LONG CREEK 52.0
END DESCRIPTION:
XS GIS Cut Line= 3
      2254775.01     13775574.99        2255975.       13774375.
        2257175.       13773175.
#Sta/Elev= 30
    3303  626.45  3543.4  622.21  3713.1  618.06  3840.4  614.66  3911.1  612.02
  3939.4  610.23  4137.4  603.46  4186.9  603.17  4295.7  600.16  4299.2  600.12
  4429.2   599.8  4490.9  599.24  4759.6  599.65  4858.6  597.92  4943.5  598.31
  4971.8  597.56  4978.8  596.38  4979.3  595.88  4993.1  596.38  5028.3  598.18
  5070.8  598.19  5084.9   599.5  5220.5  600.27  5452.6  603.68  5622.3  603.96
  5820.3  607.63  6134.5  614.83    6188  616.88  6308.9  618.67  6697.1  626.21
#Mann= 9 ,-1 , 0
    3303    .045       0  4295.7    .035       0  4299.2    .045       0
  4429.2     .07       0  4978.8     .05       0  4993.1     .07       0
  5220.5    .045       0  6134.5     .07       0  6308.9    .045       0
Bank Sta=4978.8,4993.1
XS Rating Curve= 0 ,0
Exp/Cntr=0.3,0.1