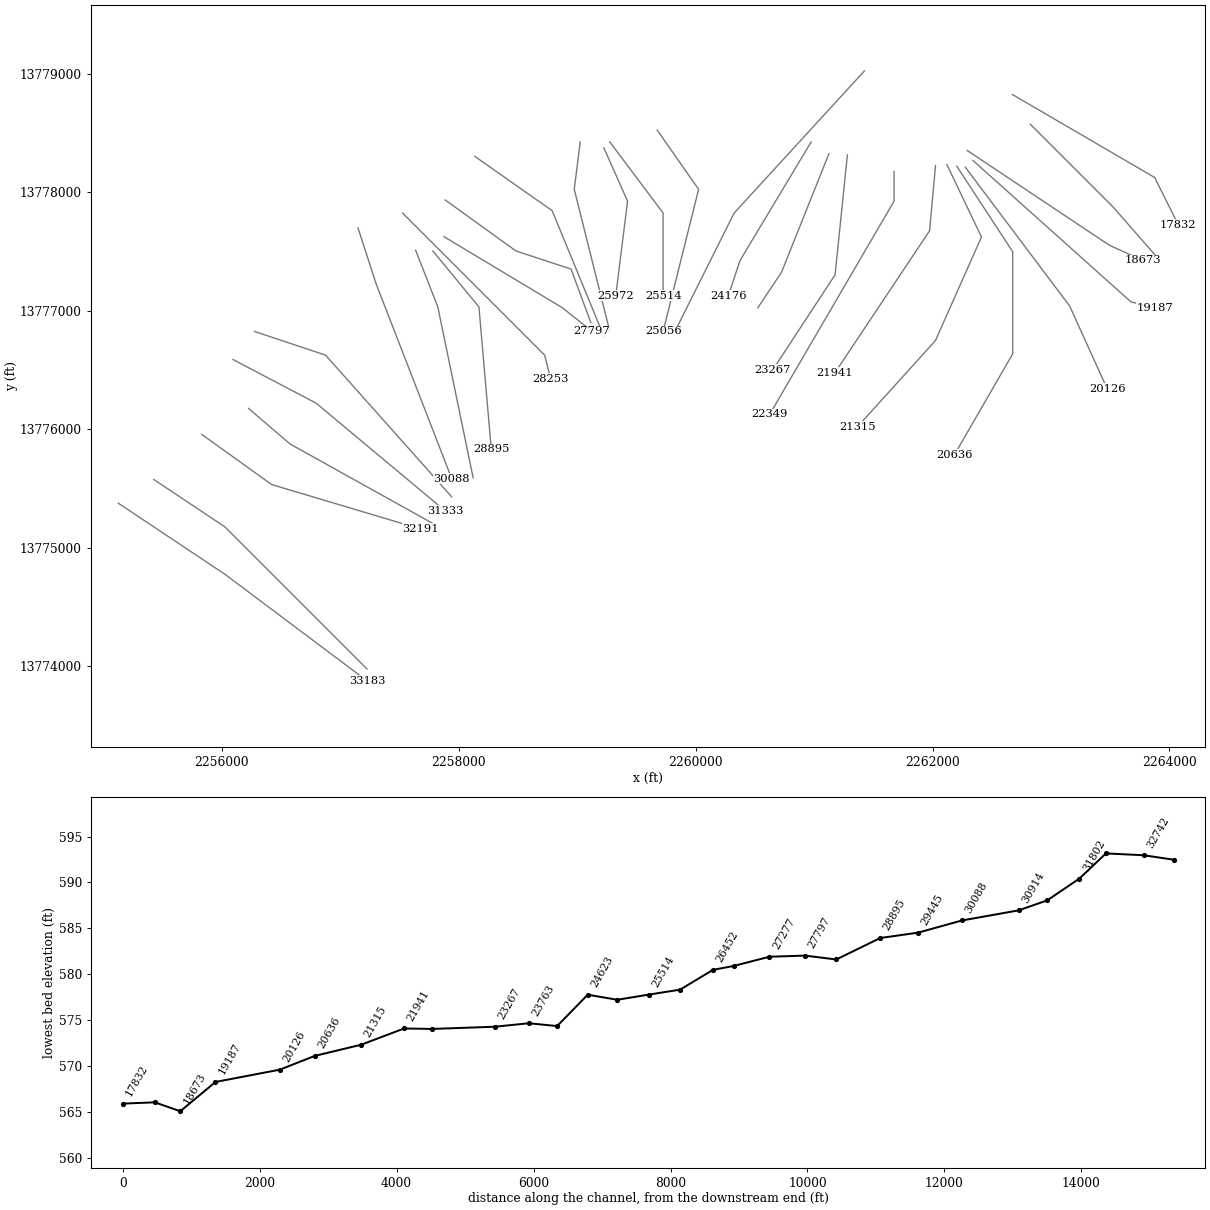
HEC-RAS study LONG CREEK.prj: LONG CREEK Base Level Engineering

--- LONG CREEK.g01 (geometry) --- (continued)

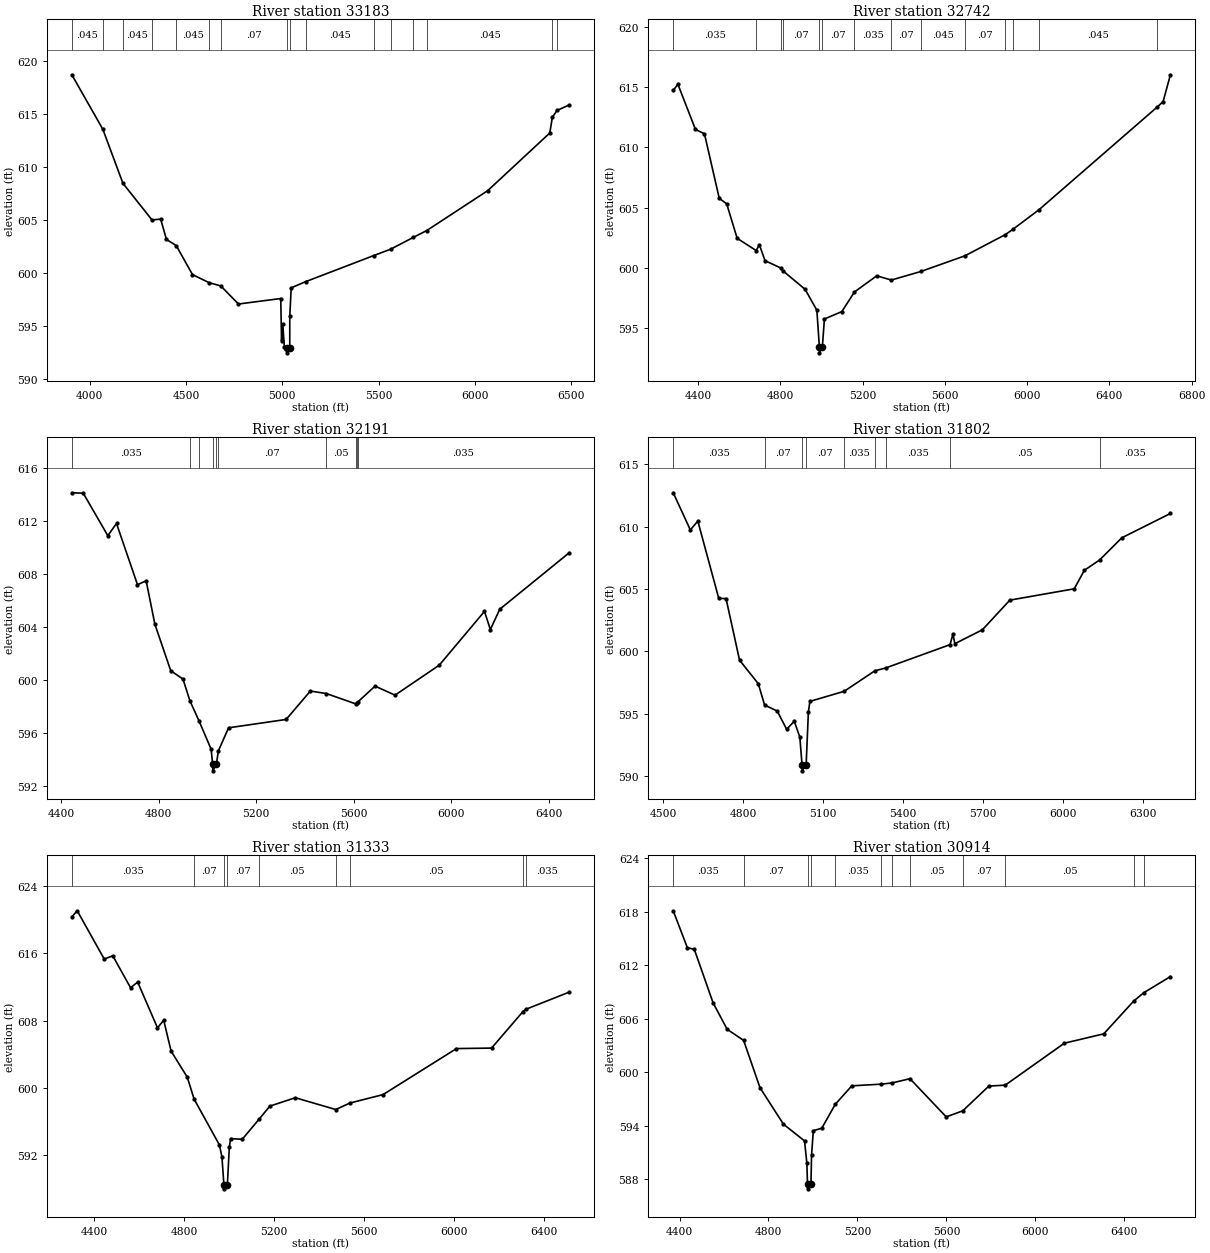
Type RM Length L Ch R = 1 ,33183   ,441,441,441
BEGIN DESCRIPTION:
LONG CREEK 51.0
END DESCRIPTION:
XS GIS Cut Line= 3
      2255124.96     13775375.02        2256025.       13774775.
      2257224.99     13773875.01
#Sta/Elev= 30
  3906.8  618.73  4067.9  613.58  4172.1  608.48    4323  605.02  4368.1   605.1
  4398.1  603.18  4449.3  602.59  4533.3  599.86  4619.2   599.1  4680.2  598.79
  4772.2  597.08  4991.6   597.6  4995.8  593.61  5002.1   595.2  5010.4  592.99
    5024  592.97  5024.5  592.47  5038.4  592.97  5038.5  595.91  5045.8  598.61
    5122   599.2    5475  601.66  5562.5  602.26  5679.7  603.37  5749.9  604.02
  6066.6  607.79  6388.5  613.23  6402.1  614.71    6426  615.36  6488.5  615.87
#Mann= 16 ,-1 , 0
  3906.8    .045       0  4067.9     .07       0  4172.1    .045       0
    4323    .035       0  4449.3    .045       0  4619.2    .035       0
  4680.2     .07       0    5024     .05       0  5038.4     .07       0
    5122    .045       0    5475     .07       0  5562.5    .045       0
  5679.7    .035       0  5749.9    .045       0  6402.1     .07       0
    6426    .045       0
Bank Sta=5024,5038.4
XS Rating Curve= 0 ,0
Exp/Cntr=0.3,0.1

Type RM Length L Ch R = 1 ,32742   ,551,551,551
BEGIN DESCRIPTION:
LONG CREEK 50.0
END DESCRIPTION:
XS GIS Cut Line= 3
      2255424.98     13775575.01        2256025.       13775175.
      2257225.01     13773974.99
#Sta/Elev= 30
  4278.4  614.73    4301  615.25  4386.6  611.49  4430.2  611.14  4502.3  605.78
  4538.3  605.33  4589.4  602.46  4681.7  601.45  4697.6  601.93  4724.6  600.61
  4802.5  599.99  4810.9  599.78  4919.9  598.23    4977  596.49  4989.3  593.46
  4989.8  592.96  5003.8  593.46  5013.7  595.77  5098.5  596.38  5159.8  598.01
  5268.2  599.35  5339.5     599    5483  599.71  5697.3  601.01  5893.8  602.77
  5930.8  603.21  6057.2  604.83  6631.5  613.34  6661.2  613.81  6696.6  616.03
#Mann= 14 ,-1 , 0
  4278.4    .035       0  4681.7     .07       0  4802.5    .045       0
  4810.9     .07       0  4989.3     .05       0  5003.8     .07       0
  5159.8    .035       0  5339.5     .07       0    5483    .045       0
  5697.3     .07       0  5893.8    .045       0  5930.8    .035       0
  6057.2    .045       0  6631.5     .07       0
Bank Sta=4989.3,5003.8
XS Rating Curve= 0 ,0
Exp/Cntr=0.3,0.1

Type RM Length L Ch R = 1 ,32191   ,389,389,389
BEGIN DESCRIPTION:
A19804
END DESCRIPTION:
XS GIS Cut Line= 3
      2255829.83     13775955.78       2256420.1     13775532.18
      2257677.01     13775157.19
#Sta/Elev= 30
    4444   614.1  4490.8  614.07  4591.5  610.87  4627.1  611.79  4713.1  607.18
  4748.7  607.47  4784.3  604.21  4849.4   600.7  4899.7  600.07  4927.9  598.44
  4965.2  596.93  5015.2  594.78  5021.2  593.66  5021.7  593.16  5036.6  593.66
  5044.7  594.66  5086.4   596.4  5322.5  597.03  5421.9  599.17  5487.4  598.98
  5608.4   598.2    5611  598.25    5616  598.34    5687  599.54    5769  598.86
  5950.4  601.12  6135.7  605.17  6159.7   603.8  6198.3  605.33  6482.2  609.57
#Mann= 10 ,-1 , 0
    4444    .035       0  4927.9     .07       0  4965.2    .035       0
  5021.2    .035       0  5036.6    .035       0  5044.7     .07       0
  5487.4     .05       0  5608.4     .07       0    5611     .05       0
    5616    .035       0
Bank Sta=5021.2,5036.6
XS Rating Curve= 0 ,0
Exp/Cntr=0.3,0.1

Type RM Length L Ch R = 1 ,31802   ,469,469,469
BEGIN DESCRIPTION:
LONG CREEK 49.0
END DESCRIPTION:
XS GIS Cut Line= 3
      2256225.03     13776174.97        2256575.       13775875.
      2257800.99     13775192.49
#Sta/Elev= 30
  4538.8  612.71    4603  609.73    4631  610.44  4709.4  604.25  4736.9  604.22
  4787.4  599.29  4857.6   597.4  4881.4  595.69  4928.9   595.2  4964.1  593.74
  4992.6  594.39  5013.5  593.11  5021.7  590.91  5022.2  590.41  5037.2  590.91
  5045.5  595.11  5051.2  595.98  5179.9  596.79  5294.5  598.43  5335.4  598.66
  5576.7  600.53  5587.4  601.37  5594.9  600.61  5697.9  601.72  5800.9   604.1
  6042.5  605.01  6080.2  606.49  6137.4  607.32  6220.8   609.1  6402.9  611.05
#Mann= 9 ,-1 , 0
  4538.8    .035       0  4881.4     .07       0  5021.7     .05       0
  5037.2     .07       0  5179.9    .035       0  5294.5     .05       0
  5335.4    .035       0  5576.7     .05       0  6137.4    .035       0
Bank Sta=5021.7,5037.2
XS Rating Curve= 0 ,0
Exp/Cntr=0.3,0.1

Type RM Length L Ch R = 1 ,31333   ,419,419,419
BEGIN DESCRIPTION:
A19803
END DESCRIPTION:
XS GIS Cut Line= 3
      2256093.73     13776587.72       2256795.1     13776219.68
      2257885.35     13775309.97
#Sta/Elev= 30
  4301.1  620.31  4325.1  621.03  4445.3   615.3  4483.2  615.69  4562.3   611.9
    4594  612.57  4682.2  607.14  4709.9  608.04  4742.7  604.38  4814.5   601.3
  4845.2  598.68  4957.5  593.26  4968.9  591.83  4977.6  588.54  4978.1  588.04
  4993.1  588.54  5001.7  592.95  5007.4     594  5059.2  593.92  5133.2  596.27
    5182  597.85  5295.2  598.85  5475.3  597.45  5538.2  598.22  5685.7  599.22
  6012.4  604.68  6168.6  604.74  6307.5  609.05    6320  609.33  6513.1  611.37
#Mann= 9 ,-1 , 0
  4301.1    .035       0  4845.2     .07       0  4977.6     .05       0
  4993.1     .07       0  5133.2     .05       0  5475.3     .07       0
  5538.2     .05       0  6307.5     .07       0    6320    .035       0
Bank Sta=4977.6,4993.1
XS Rating Curve= 0 ,0
Exp/Cntr=0.3,0.1

Type RM Length L Ch R = 1 ,30914   ,826,826,826
BEGIN DESCRIPTION:
LONG CREEK 48.0
END DESCRIPTION:
XS GIS Cut Line= 3
      2256274.95     13776825.02        2256875.       13776625.
      2257940.92     13775428.02
#Sta/Elev= 30
  4371.7  618.13    4435     614  4466.6   613.8  4550.9  607.81  4614.2  604.84
  4688.1   603.6  4761.8  598.29  4867.2   594.2    4962  592.33  4972.6  589.81
  4975.4  587.45  4975.9  586.95  4990.9  587.45  4993.7  590.76  5001.6  593.47
  5039.7  593.75    5100  596.42  5174.4   598.5  5307.7  598.69  5356.4  598.83
  5436.1   599.3  5599.1  595.02  5673.6   595.7  5790.6  598.47  5864.5  598.58
  6130.1  603.28  6307.3  604.33  6441.8     608  6487.8  608.95    6607  610.75
#Mann= 12 ,-1 , 0
  4371.7    .035       0  4688.1     .07       0  4975.4     .05       0
  4990.9     .07       0    5100    .035       0  5307.7     .07       0
  5356.4    .035       0  5436.1     .05       0  5673.6     .07       0
  5864.5     .05       0  6441.8     .07       0  6487.8    .035       0
Bank Sta=4975.4,4990.9
XS Rating Curve= 0 ,0
Exp/Cntr=0.3,0.1

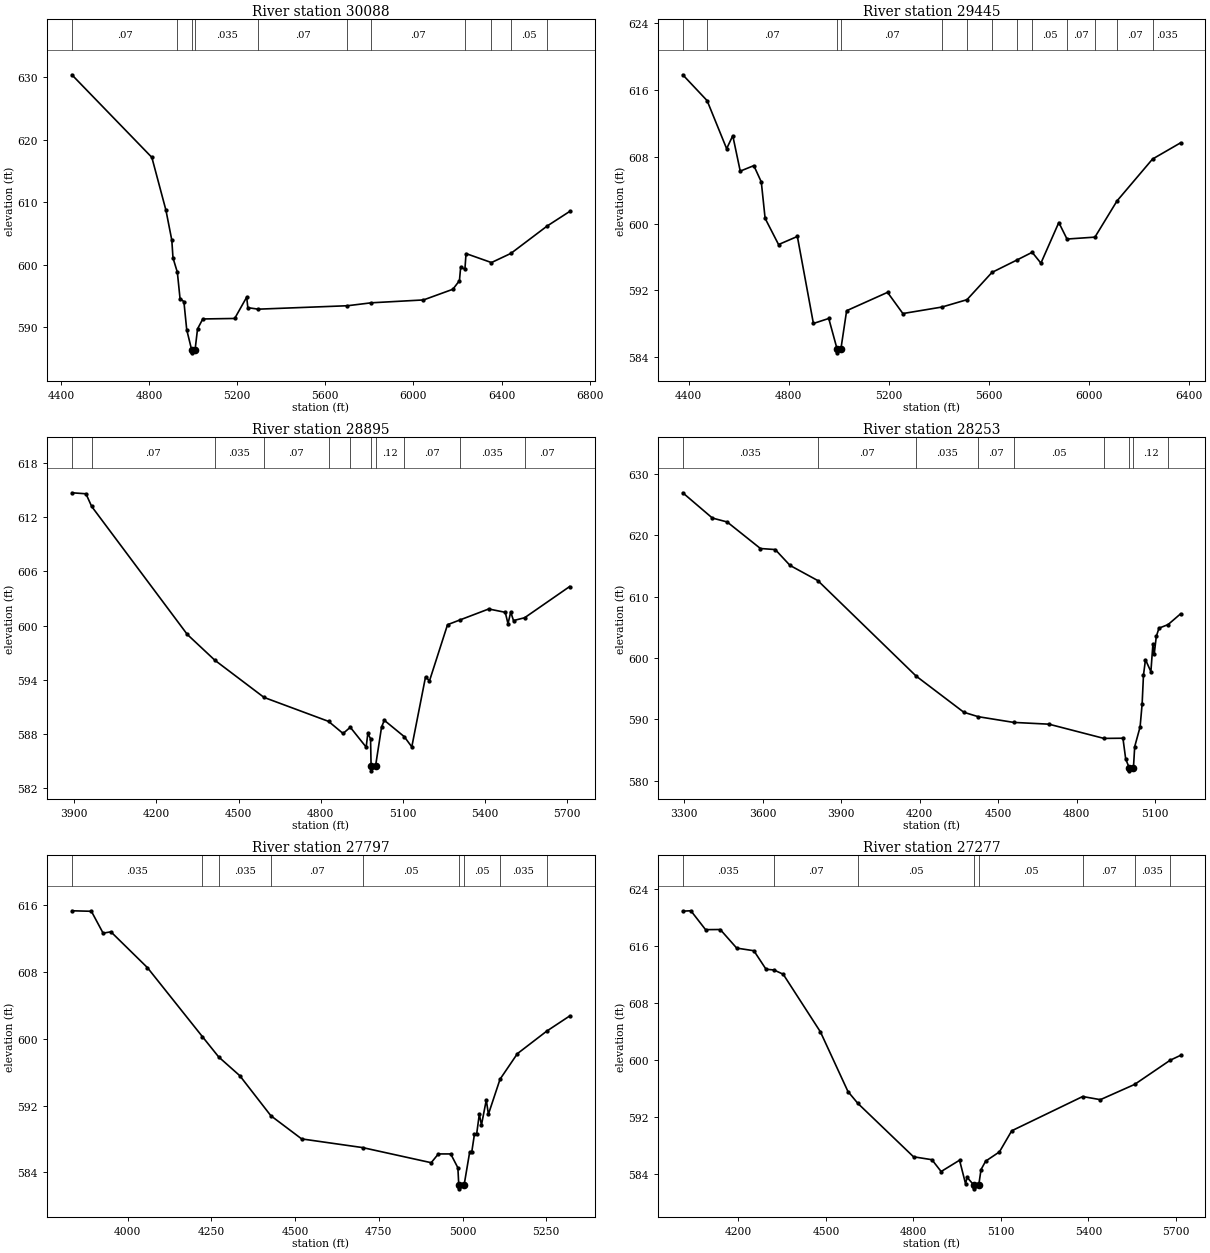
Type RM Length L Ch R = 1 ,30088   ,643,643,643
BEGIN DESCRIPTION:
LONG CREEK 47.0
END DESCRIPTION:
XS GIS Cut Line= 3
      2257149.27     13777698.82      2257302.04     13777226.62
      2257940.47     13775581.99
#Sta/Elev= 30
  4448.8  630.42    4812  617.18    4876  608.71  4902.7   603.9    4908  601.07
  4927.8  598.77    4940  594.56  4957.6  594.05  4970.4  589.55  4992.6  586.35
  4993.1  585.85  5008.4  586.35  5019.5  589.69  5043.4  591.28  5188.2  591.36
  5242.6  594.77    5248  593.09    5295  592.85  5700.5   593.4  5808.5  593.87
  6045.6  594.33    6179  596.04  6208.9  597.42  6214.3  599.55  6233.8  599.27
  6238.8  601.76  6354.2  600.32  6442.6  601.79  6607.3  606.18  6709.3  608.51
#Mann= 11 ,-1 , 0
  4448.8     .07       0  4927.8    .035       0  4992.6    .035       0
  5008.4    .035       0    5295     .07       0  5700.5     .05       0
  5808.5     .07       0  6233.8     .05       0  6354.2     .07       0
  6442.6     .05       0  6607.3     .07       0
Bank Sta=4992.6,5008.4
XS Rating Curve= 0 ,0
Exp/Cntr=0.3,0.1

Type RM Length L Ch R = 1 ,29445   ,550,550,550
BEGIN DESCRIPTION:
LONG CREEK 46.0
END DESCRIPTION:
XS GIS Cut Line= 3
      2257635.37     13777511.36      2257822.88     13777032.18
      2258121.25     13775588.86
#Sta/Elev= 30
  4376.4  617.85  4473.7  614.75  4551.7  608.99  4576.2  610.55    4606   606.3
  4660.3  606.96  4690.1  605.01  4705.4  600.64  4759.1   597.5  4834.2  598.47
  4898.3  588.04  4959.6  588.64  4992.5  585.02    4993  584.52  5008.3  585.02
    5031  589.57  5194.4  591.77  5255.7  589.23  5411.8  590.01  5511.7  590.89
  5611.6  594.16  5711.5  595.65  5772.2  596.57  5807.1  595.27  5878.6  600.14
  5911.3  598.16  6022.9  598.39  6111.1  602.73    6253  607.75  6364.8  609.69
#Mann= 13 ,-1 , 0
  4376.4    .035       0  4473.7     .07       0  4992.5     .05       0
  5008.3     .07       0  5411.8    .035       0  5511.7     .07       0
  5611.6     .05       0  5711.5     .07       0  5772.2     .05       0
  5911.3     .07       0  6022.9     .05       0  6111.1     .07       0
    6253    .035       0
Bank Sta=4992.5,5008.3
XS Rating Curve= 0 ,0
Exp/Cntr=0.3,0.1

Type RM Length L Ch R = 1 ,28895   ,642,642,642
BEGIN DESCRIPTION:
A19802
END DESCRIPTION:
XS GIS Cut Line= 3
      2257781.19     13777504.42       2258170.1     13777032.18
      2258274.27     13775830.75
#Sta/Elev= 30
  3891.5  614.69  3942.9  614.58  3963.8  613.18  4313.1  599.02  4413.7  596.17
  4593.2  592.06  4828.8  589.41  4881.9  588.07  4908.2  588.76  4966.2  586.56
  4972.2  588.07  4982.2  587.49  4984.2  584.44  4984.7  583.94  5000.3  584.44
  5022.4  588.78  5032.4  589.53  5105.3  587.72  5132.8  586.59    5183  594.33
  5197.4  593.89  5263.3   600.1  5309.7  600.64  5413.8  601.84  5474.1  601.47
  5484.1  600.21  5494.1   601.5  5504.2  600.56  5544.8  600.87  5709.2  604.32
#Mann= 11 ,-1 , 0
  3891.5    .035       0  3963.8     .07       0  4413.7    .035       0
  4593.2     .07       0  4828.8     .05       0  4908.2     .12       0
  4984.2     .05       0  5000.3     .12       0  5105.3     .07       0
  5309.7    .035       0  5544.8     .07       0
Bank Sta=4984.2,5000.3
XS Rating Curve= 0 ,0
Exp/Cntr=0.3,0.1

Type RM Length L Ch R = 1 ,28253   ,456,456,456
BEGIN DESCRIPTION:
LONG CREEK 45.0
END DESCRIPTION:
XS GIS Cut Line= 3
      2257524.97     13777825.03        2258725.       13776625.
      2258774.99     13776425.05
#Sta/Elev= 30
  3293.9  626.95  3407.1  622.83  3463.6  622.19  3590.9  617.86  3647.5  617.69
  3704.1   615.1  3810.3  612.63  4186.3  597.05  4368.7  591.15  4423.8  590.43
    4559   589.5    4694  589.21  4904.2  586.89  4976.9  586.92  4987.5  583.52
    5001   582.1  5001.5   581.6  5017.1   582.1  5021.9  585.55  5042.5  588.76
  5050.3  592.51  5055.4   597.2  5063.1  599.73  5083.8  597.78  5091.5  602.26
  5096.6  600.65  5104.4  603.51  5114.7  604.87  5149.4  605.45  5197.1   607.2
#Mann= 9 ,-1 , 0
  3293.9    .035       0  3810.3     .07       0  4186.3    .035       0
  4423.8     .07       0    4559     .05       0  4904.2     .12       0
    5001     .05       0  5017.1     .12       0  5149.4     .07       0
Bank Sta=5001,5017.1
XS Rating Curve= 0 ,0
Exp/Cntr=0.3,0.1

Type RM Length L Ch R = 1 ,27797   ,520,520,520
BEGIN DESCRIPTION:
LONG CREEK 44.0
END DESCRIPTION:
XS GIS Cut Line= 3
      2257875.02     13777624.99        2258875.       13777025.
      2259124.98     13776825.02
#Sta/Elev= 30
  3833.4  615.32  3891.7  615.26  3926.7  612.64    3950   612.8  4058.8  608.52
  4222.9  600.26  4271.9  597.81  4334.8  595.57  4427.7  590.77  4519.5     588
  4701.6  586.96  4906.3  585.15  4927.7   586.2  4964.6   586.2    4986  584.54
  4988.6  582.52  4989.1  582.02  5004.8  582.52  5021.2  586.42  5027.6  586.47
  5035.6   588.6    5042  588.57    5050  590.95  5056.4  589.67  5070.8  592.65
  5077.2  590.96  5111.9  595.15  5163.7  598.21  5251.4  600.91  5319.7  602.72
#Mann= 9 ,-1 , 0
  3833.4    .035       0  4222.9     .07       0  4271.9    .035       0
  4427.7     .07       0  4701.6     .05       0  4988.6     .05       0
  5004.8     .05       0  5111.9    .035       0  5251.4     .07       0
Bank Sta=4988.6,5004.8
XS Rating Curve= 0 ,0
Exp/Cntr=0.3,0.1

Type RM Length L Ch R = 1 ,27277   ,524,524,524
BEGIN DESCRIPTION:
A19801
END DESCRIPTION:
XS GIS Cut Line= 4
       2257885.4     13777934.94       2258482.6      13777504.4
      2258947.88     13777351.62      2259114.54     13776900.24
#Sta/Elev= 30
    4009  620.89  4036.9  620.94  4087.2  618.29  4137.6  618.31    4194   615.7
  4252.9  615.33  4294.6  612.73  4321.6  612.63  4353.5  612.03  4481.1  603.94
  4575.6  595.56  4609.7  593.89  4800.4   586.4  4863.5  585.99  4895.1  584.33
  4958.3  585.92  4978.9   582.6  4984.1  583.52  5007.8   582.4  5008.3   581.9
    5024   582.4  5031.9   584.6  5047.8  585.79  5095.1  587.09  5137.2  590.05
  5380.5  594.86  5441.2  594.42  5558.6  596.56  5680.7  599.96  5716.1  600.64
#Mann= 8 ,-1 , 0
    4009    .035       0  4321.6     .07       0  4609.7     .05       0
  5007.8     .05       0    5024     .05       0  5380.5     .07       0
  5558.6    .035       0  5680.7     .07       0
Bank Sta=5007.8,5024
XS Rating Curve= 0 ,0
Exp/Cntr=0.3,0.1

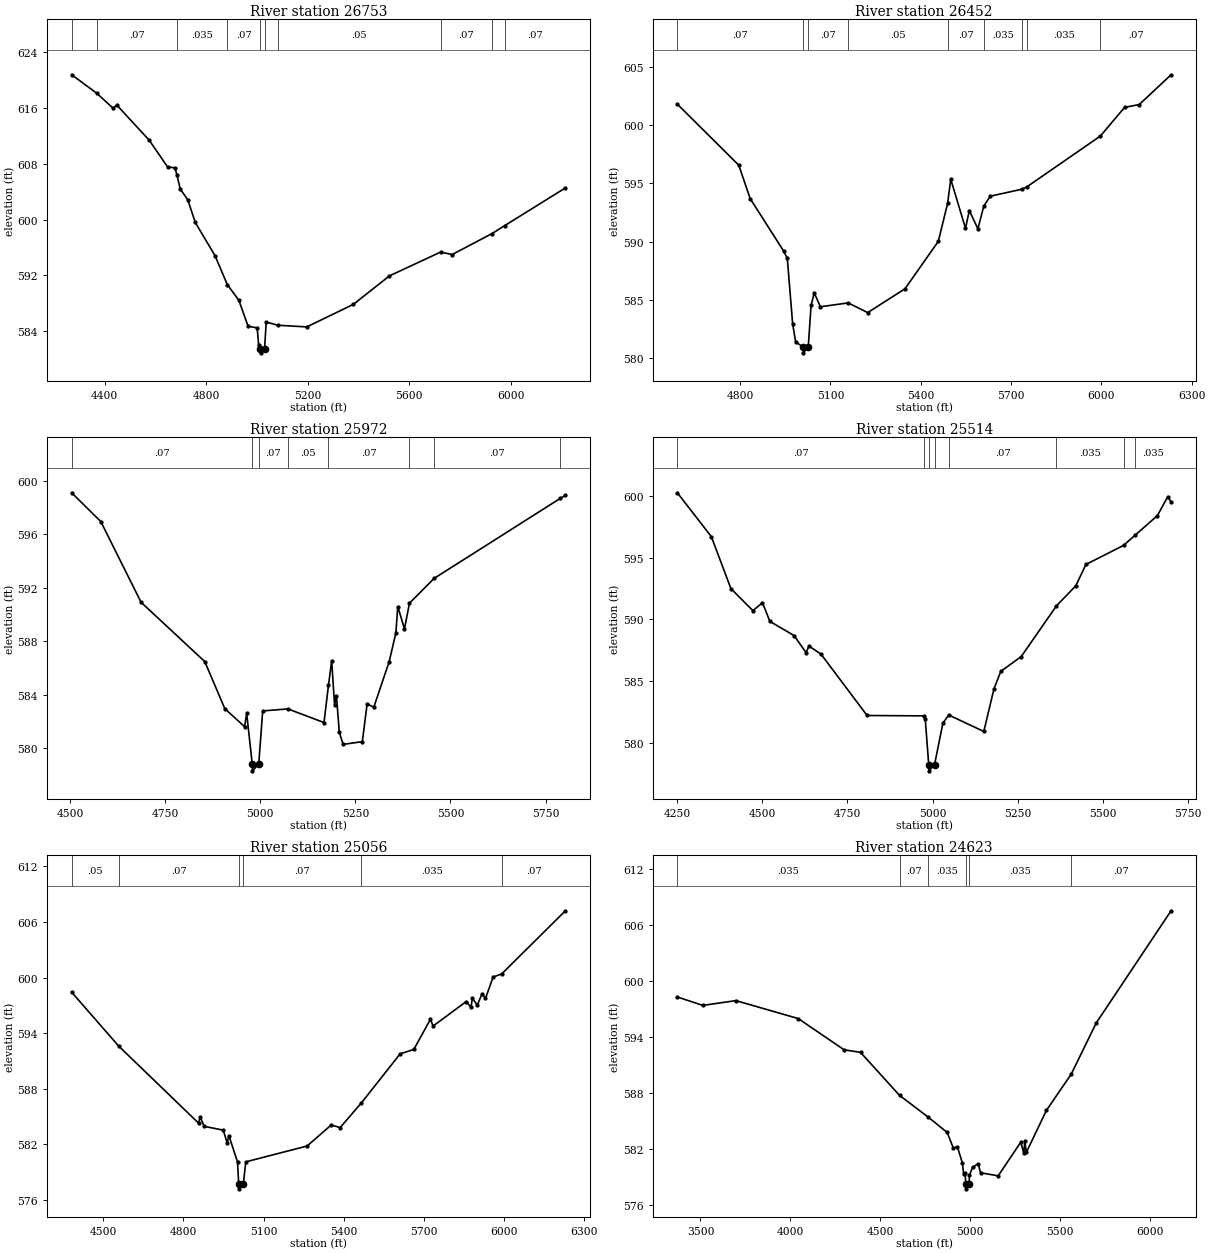
Type RM Length L Ch R = 1 ,26753   ,301,301,301
BEGIN DESCRIPTION:
A19800
END DESCRIPTION:
XS GIS Cut Line= 3
       2258135.4     13778302.99      2258788.15     13777844.68
      2259225.64     13776782.21
#Sta/Elev= 30
  4269.7  620.78  4367.9  618.15  4432.8  615.99  4447.7  616.43  4575.8  611.38
    4648  607.55  4676.9  607.43  4684.8   606.4  4697.8  604.39  4727.4  602.85
    4757   599.6  4834.6  594.85  4883.3  590.69    4929  588.42  4965.3   584.7
    5001  584.47  5007.1  581.97  5013.8  581.39  5014.3  580.89  5030.1  581.39
  5036.8  585.31  5082.4  584.85  5196.7  584.61  5380.6  587.85  5522.6  591.93
  5724.6  595.35  5769.9  594.99  5927.1     598  5977.4  599.15  6216.3  604.55
#Mann= 10 ,-1 , 0
  4269.7    .035       0  4367.9     .07       0  4684.8    .035       0
  4883.3     .07       0  5013.8     .05       0  5030.1     .07       0
  5082.4     .05       0  5724.6     .07       0  5927.1    .035       0
  5977.4     .07       0
Bank Sta=5013.8,5030.1
XS Rating Curve= 0 ,0
Exp/Cntr=0.3,0.1

Type RM Length L Ch R = 1 ,26452   ,480,480,480
BEGIN DESCRIPTION:
LONG CREEK 43.0
END DESCRIPTION:
XS GIS Cut Line= 3
        2259025.     13778424.97        2258975.       13778025.
        2259275.     13776825.01
#Sta/Elev= 30
  4591.6  601.79  4795.6  596.56  4833.4   593.7  4944.3  589.21  4956.9  588.57
  4974.5  582.98  4984.6   581.4  5009.4  580.97  5009.9  580.47  5026.4  580.97
  5035.9  584.53  5046.2  585.61  5066.8  584.42  5159.1  584.75    5224  583.92
  5347.7  585.96  5458.5  590.03  5489.4  593.29  5499.8  595.35  5548.7  591.15
  5561.6  592.67    5590   591.1  5609.5  593.05  5631.2   593.9  5736.4   594.5
  5752.6   594.7  5996.9  599.06    6077  601.51    6126  601.76  6231.6  604.31
#Mann= 9 ,-1 , 0
  4591.6     .07       0  5009.4     .05       0  5026.4     .07       0
  5159.1     .05       0  5489.4     .07       0  5609.5    .035       0
  5736.4     .07       0  5752.6    .035       0  5996.9     .07       0
Bank Sta=5009.4,5026.4
XS Rating Curve= 0 ,0
Exp/Cntr=0.3,0.1

Type RM Length L Ch R = 1 ,25972   ,458,458,458
BEGIN DESCRIPTION:
LONG CREEK 42.0
END DESCRIPTION:
XS GIS Cut Line= 3
      2259225.02     13778374.96        2259425.       13777925.
        2259325.     13777125.02
#Sta/Elev= 30
  4503.7   599.1  4580.3  596.95  4686.3  590.91  4853.8  586.48  4906.5  582.96
  4958.5  581.61    4964  582.61  4978.7  578.81  4979.2  578.31  4995.7  578.81
  5006.2  582.79  5072.5  582.94  5167.4  581.92  5179.1   584.7  5187.6  586.53
  5195.1  583.26  5200.2  583.89  5207.7  581.18  5217.8  580.29  5268.2  580.49
  5280.8  583.31  5298.4  583.07  5338.7  586.46  5356.4  588.62  5361.4  590.59
  5379.1  588.92  5392.1  590.84  5457.1   592.7  5788.8  598.68  5802.3  598.91
#Mann= 8 ,-1 , 0
  4503.7     .07       0  4978.7     .05       0  4995.7     .07       0
  5072.5     .05       0  5179.1     .07       0  5392.1     .12       0
  5457.1     .07       0  5788.8    .035       0
Bank Sta=4978.7,4995.7
XS Rating Curve= 0 ,0
Exp/Cntr=0.3,0.1

Type RM Length L Ch R = 1 ,25514   ,458,458,458
BEGIN DESCRIPTION:
LONG CREEK 41.0
END DESCRIPTION:
XS GIS Cut Line= 3
      2259275.02     13778424.97        2259725.       13777825.
        2259725.     13777124.96
#Sta/Elev= 30
  4250.5  600.23  4350.5  596.68  4407.8  592.49  4472.3  590.71  4500.5  591.35
  4522.3  589.84  4593.2   588.7  4628.6  587.32  4636.9  587.85  4672.3   587.2
  4807.8  582.24  4973.9  582.21  4978.6  581.95  4988.8  578.27  4989.3  577.77
  5005.9  578.27  5030.5  581.63  5047.6  582.28  5150.5  580.95  5180.5   584.4
  5200.5  585.81  5260.5     587    5364   591.1  5420.5  592.71  5450.5  594.44
  5560.9  595.98  5595.2  596.81  5660.5  598.39  5690.5  599.91  5700.5  599.49
#Mann= 8 ,-1 , 0
  4250.5     .07       0  4973.9     .12       0  4988.8     .05       0
  5005.9     .12       0  5047.6     .07       0    5364    .035       0
  5560.9     .07       0  5595.2    .035       0
Bank Sta=4988.8,5005.9
XS Rating Curve= 0 ,0
Exp/Cntr=0.3,0.1

Type RM Length L Ch R = 1 ,25056   ,433,433,433
BEGIN DESCRIPTION:
LONG CREEK 40.0
END DESCRIPTION:
XS GIS Cut Line= 3
        2259675.       13778525.        2260025.       13778025.
      2259724.99     13776824.96
#Sta/Elev= 30
  4381.6  598.42  4557.1  592.62  4856.3   584.3  4862.5  584.98  4877.3  583.95
  4948.8  583.54  4963.6  582.14  4969.7  582.96  5002.2  580.11  5006.6  577.71
  5007.1  577.21  5023.7  577.71  5033.2  580.12  5262.5  581.83  5352.7  584.09
  5386.2  583.82  5465.7  586.48  5610.4  591.76  5661.9  592.25  5723.8  595.49
  5734.1  594.77  5857.8  597.41  5875.8  596.79    5881   597.8    5899  597.01
  5917.1  598.24  5929.9  597.74  5958.3  600.05    5991   600.4  6228.9   607.2
#Mann= 6 ,-1 , 0
  4381.6     .05       0  4557.1     .07       0  5006.6     .05       0
  5023.7     .07       0  5465.7    .035       0    5991     .07       0
Bank Sta=5006.6,5023.7
XS Rating Curve= 0 ,0
Exp/Cntr=0.3,0.1

Type RM Length L Ch R = 1 ,24623   ,447,447,447
BEGIN DESCRIPTION:
LONG CREEK 39.0
END DESCRIPTION:
XS GIS Cut Line= 3
      2261424.98     13779024.98        2260325.       13777825.
        2259825.     13776824.99
#Sta/Elev= 30
  3371.4   598.3  3512.9   597.4    3697  597.91  4043.8  595.99  4298.5  592.65
  4390.3  592.37    4607  587.77  4767.9  585.42  4871.9   583.8  4907.1  582.09
  4928.7  582.29    4957   580.5  4963.8  579.31  4971.2  579.42  4976.7  578.26
  4977.2  577.76  4994.1  578.26  4995.9  579.21  5013.2  580.06    5044  580.45
    5058  579.48  5155.8  579.15  5281.6  582.76  5298.3  581.56  5303.9  582.87
  5312.3  581.66  5424.1  586.16  5562.4  590.05  5700.8  595.51  6117.3  607.53
#Mann= 6 ,-1 , 0
  3371.4    .035       0    4607     .07       0  4767.9    .035       0
  4976.7    .035       0  4994.1    .035       0  5562.4     .07       0
Bank Sta=4976.7,4994.1
XS Rating Curve= 0 ,0
Exp/Cntr=0.3,0.1

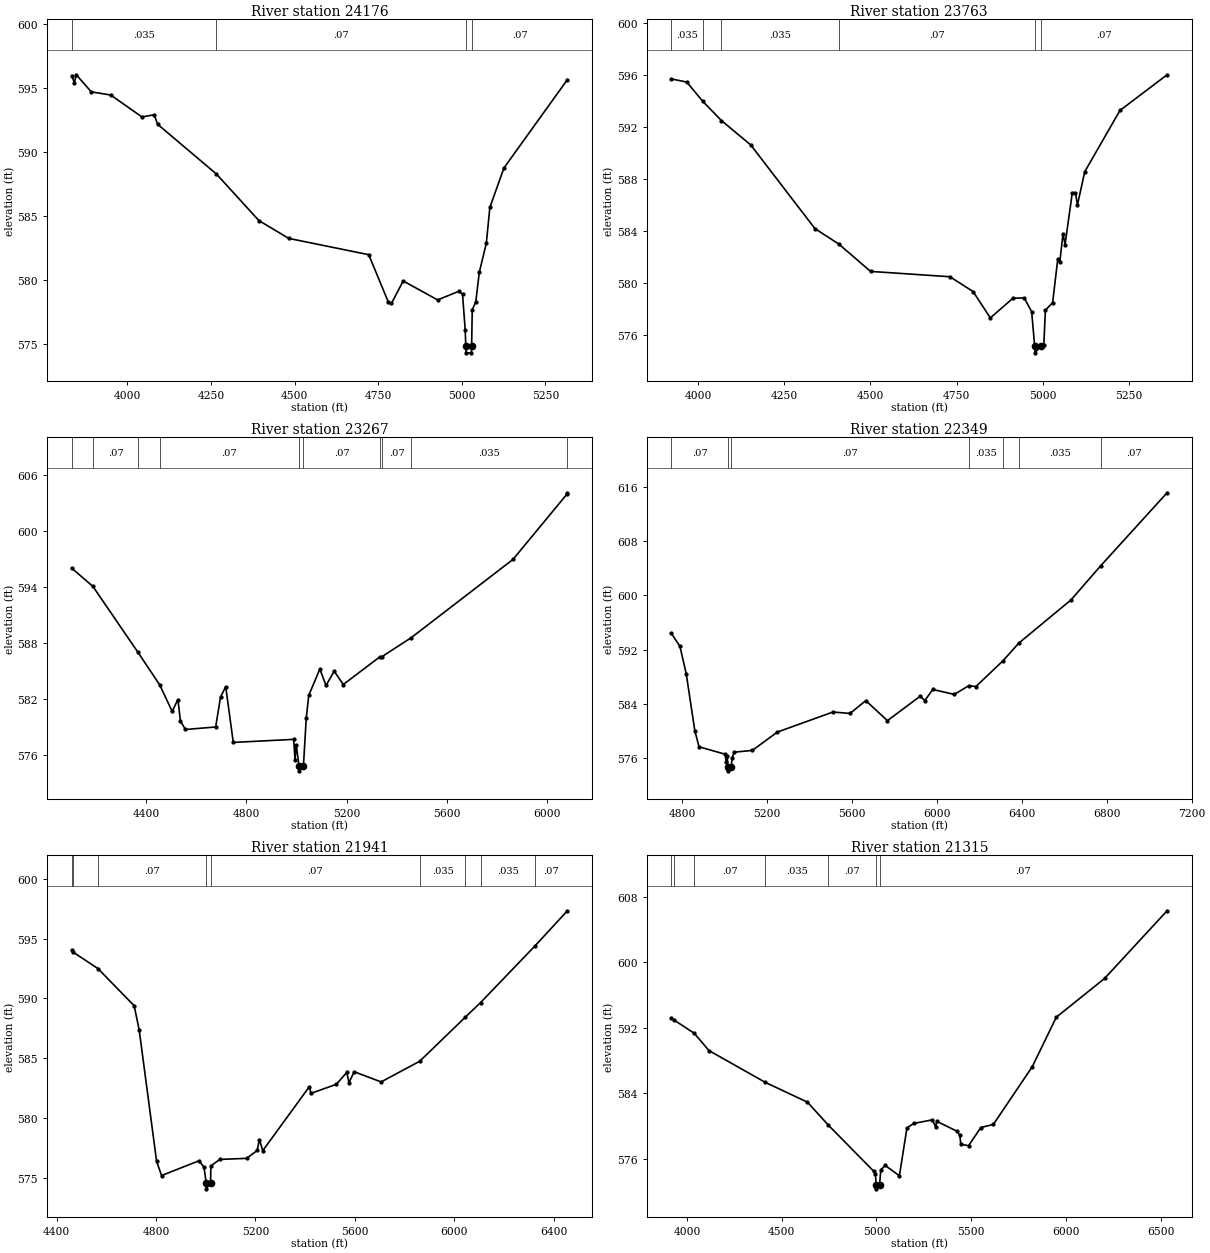
Type RM Length L Ch R = 1 ,24176   ,413,413,413
BEGIN DESCRIPTION:
LONG CREEK 38.0
END DESCRIPTION:
XS GIS Cut Line= 3
        2260975.       13778425.        2260375.       13777425.
      2260275.01     13777125.02
#Sta/Elev= 30
  3833.4  595.98  3841.2  595.42    3847  596.04  3891.7  594.71    3950  594.46
  4043.3  592.75  4080.2  592.92    4090  592.18  4265.5  588.31  4393.2  584.66
  4482.6  583.27  4721.6     582    4780  578.32  4789.7   578.2  4824.7  579.95
  4927.7  578.47  4991.8  579.15  5002.2   578.9  5010.1  576.16    5012  574.84
  5012.5  574.34  5028.9  574.34  5029.4  574.84  5031.2   577.7  5041.8  578.31
  5052.3  580.62  5073.4   582.9  5083.9  585.69  5126.1  588.77  5315.8  595.66
#Mann= 4 ,-1 , 0
  3833.4    .035       0  4265.5     .07       0    5012     .05       0
  5029.4     .07       0
Bank Sta=5012,5029.4
XS Rating Curve= 0 ,0
Exp/Cntr=0.3,0.1

Type RM Length L Ch R = 1 ,23763   ,496,496,496
BEGIN DESCRIPTION:
LONG CREEK 37.0
END DESCRIPTION:
XS GIS Cut Line= 3
      2261125.01     13778325.03        2260725.       13777325.
      2260525.01     13777025.02
#Sta/Elev= 30
  3922.9  595.67  3967.4  595.43  4014.2  593.94  4067.8  592.48  4153.1   590.6
  4338.9  584.19  4408.2     583  4500.5   580.9  4730.7  580.49    4798  579.35
  4847.8  577.33  4913.8  578.85  4946.1  578.86  4967.7  577.81  4976.5  575.15
    4977  574.65  4993.9  575.15    5003  575.26  5007.5  577.92  5028.5   578.5
  5043.5  581.85  5049.5  581.65  5058.6  583.79  5064.6  582.96  5085.6  586.94
  5094.6  586.94  5100.6  586.01  5121.7  588.55  5223.8  593.25  5360.5  595.99
#Mann= 6 ,-1 , 0
  3922.9    .035       0  4014.2     .07       0  4067.8    .035       0
  4408.2     .07       0  4976.5     .05       0  4993.9     .07       0
Bank Sta=4976.5,4993.9
XS Rating Curve= 0 ,0
Exp/Cntr=0.3,0.1

Type RM Length L Ch R = 1 ,23267   ,918,918,918
BEGIN DESCRIPTION:
A19799
END DESCRIPTION:
XS GIS Cut Line= 3
      2261281.21     13778316.93      2261177.04     13777303.01
      2260650.47      13776499.3
#Sta/Elev= 30
  4102.2  596.03  4186.5  594.08  4366.9  586.99  4453.8  583.49  4503.3  580.65
  4526.3  581.93  4536.4  579.61  4556.5  578.71  4677.1  578.98  4696.7  582.21
  4717.3  583.31  4747.5  577.32  4988.8  577.65  4994.2  575.44  4999.3  577.03
  5010.2  574.77  5010.7  574.27  5027.7  574.77    5039  579.92  5049.1  582.38
  5093.4   585.2  5117.9  583.44  5150.8  584.97  5186.9  583.54    5332  586.49
  5340.2  586.51  5458.5  588.57  5865.2  596.98  6079.5  603.95  6082.3  604.13
#Mann= 10 ,-1 , 0
  4102.2    .035       0  4186.5     .07       0  4366.9    .035       0
  4453.8     .07       0  5010.2     .05       0  5027.7     .07       0
    5332    .035       0  5340.2     .07       0  5458.5    .035       0
  6079.5     .07       0
Bank Sta=5010.2,5027.7
XS Rating Curve= 0 ,0
Exp/Cntr=0.3,0.1

Type RM Length L Ch R = 1 ,22349   ,408,408,408
BEGIN DESCRIPTION:
LONG CREEK 36.0
END DESCRIPTION:
XS GIS Cut Line= 3
        2261675.     13778175.04        2261675.       13777925.
        2260625.     13776125.01
#Sta/Elev= 30
    4750  594.37    4790  592.47    4820  588.35    4860  579.97    4880  577.59
  5002.9  576.49  5007.9  575.28  5013.7  576.29  5014.4  574.53  5014.9  574.03
    5032  574.53  5035.2  575.86  5045.1  576.79  5131.1  577.06  5248.5  579.77
  5510.7  582.74  5590.9  582.53  5665.3  584.43    5767  581.46  5921.7  585.09
  5943.2  584.44  5980.4  586.08  6082.1  585.35  6149.9  586.64  6183.8  586.52
  6312.6  590.37  6385.5  592.94    6632  599.36  6771.1  604.39  7083.9  615.21
#Mann= 7 ,-1 , 0
    4750     .07       0  5014.4     .05       0    5032     .07       0
  6149.9    .035       0  6312.6     .07       0  6385.5    .035       0
  6771.1     .07       0
Bank Sta=5014.4,5032
XS Rating Curve= 0 ,0
Exp/Cntr=0.3,0.1

Type RM Length L Ch R = 1 ,21941   ,626,626,626
BEGIN DESCRIPTION:
LONG CREEK 35.0
END DESCRIPTION:
XS GIS Cut Line= 3
        2262025.     13778225.02        2261975.       13777675.
      2261175.01     13776475.01
#Sta/Elev= 30
    4461  594.01  4467.2  593.86  4566.3   592.5  4712.1  589.39  4732.1   587.4
  4802.4  576.38  4822.5  575.19  4973.1  576.43  4993.2  575.88  5001.9  574.58
  5002.4  574.08  5019.6  574.58  5020.8     576  5056.9  576.54    5165  576.63
  5207.1  577.29  5216.1   578.2  5229.6  577.27  5417.4  582.63  5423.4  582.06
  5525.6  582.82  5567.6  583.81  5576.7  582.97  5597.7  583.87  5705.9  583.02
  5861.4  584.75  6044.5  588.43  6106.4  589.66    6325  594.39  6455.5  597.33
#Mann= 9 ,-1 , 0
    4461     .07       0  4467.2    .035       0  4566.3     .07       0
  5001.9     .05       0  5019.6     .07       0  5861.4    .035       0
  6044.5     .07       0  6106.4    .035       0    6325     .07       0
Bank Sta=5001.9,5019.6
XS Rating Curve= 0 ,0
Exp/Cntr=0.3,0.1

Type RM Length L Ch R = 1 ,21315   ,679,679,679
BEGIN DESCRIPTION:
A19798
END DESCRIPTION:
XS GIS Cut Line= 4
      2262121.47      13778233.6      2262413.15     13777622.45
      2262024.26     13776747.45       2261365.3     13776019.13
#Sta/Elev= 30
  3917.5  593.14  3930.4  592.95    4038  591.32  4115.4  589.21  4412.3  585.33
  4635.7   582.9  4746.6  580.08  4985.9  574.45  4993.9  574.15  4998.9  572.81
  4999.4  572.31  5016.6  572.81  5022.6  574.61  5045.8  575.17  5121.1  573.91
  5160.9  579.75  5196.3   580.3  5294.8  580.74  5312.6  579.87  5318.1  580.56
  5423.6  579.37  5439.8  578.87  5445.5  577.76  5486.3  577.58  5550.8   579.8
  5617.2  580.18  5822.7  587.24  5949.7  593.29  6204.5  598.02  6534.4  606.29
#Mann= 7 ,-1 , 0
  3917.5     .07       0  3930.4    .035       0    4038     .07       0
  4412.3    .035       0  4746.6     .07       0  4998.9     .05       0
  5016.6     .07       0
Bank Sta=4998.9,5016.6
XS Rating Curve= 0 ,0
Exp/Cntr=0.3,0.1

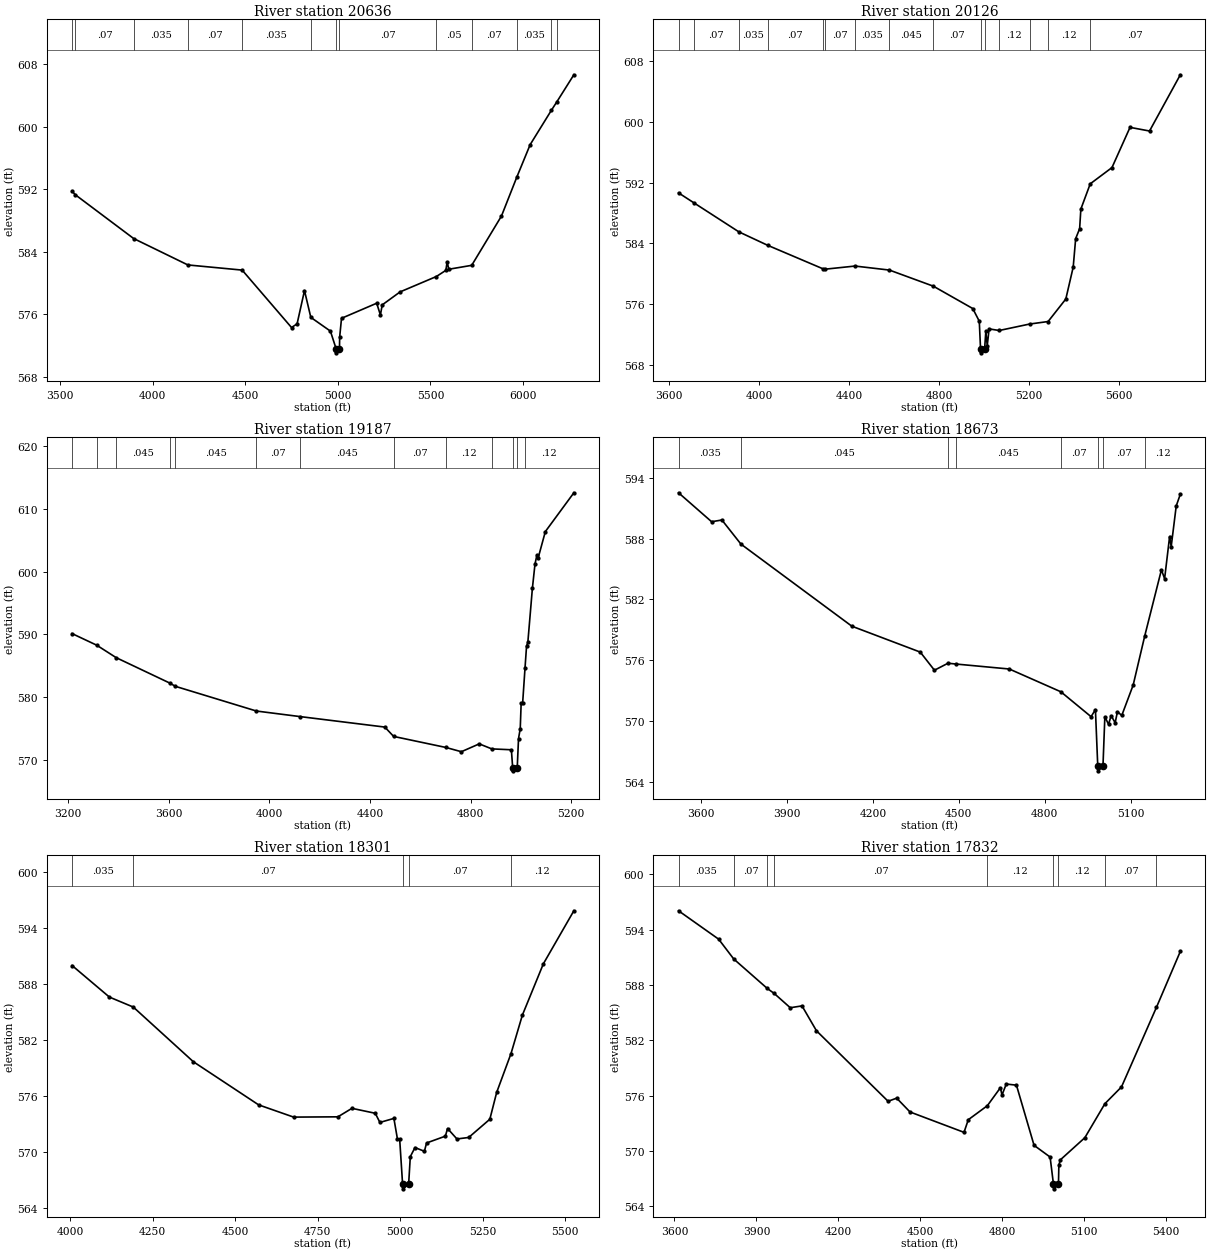
Type RM Length L Ch R = 1 ,20636   ,510,510,510
BEGIN DESCRIPTION:
A19797
END DESCRIPTION:
XS GIS Cut Line= 4
      2262204.84     13778219.64      2262677.04     13777497.45
      2262677.04     13776636.34        2262184.      13775782.2
#Sta/Elev= 30
  3564.6  591.78  3581.8  591.33  3897.3  585.72    4190  582.34  4483.3  581.68
  4749.9  574.33  4779.9   574.8  4819.9  579.06  4854.1  575.63  4959.9  573.87
    4991  571.59  4991.5  571.09  5008.9  571.59  5009.9   573.1  5019.9  575.51
  5209.9  577.44  5229.9  575.94  5239.9  577.23  5336.3  578.89  5532.3  580.86
  5583.6  581.65  5590.3  582.74  5599.4  581.79  5723.1  582.29  5883.8   588.6
  5966.5  593.57  6038.8  597.74  6153.8  602.15  6181.9  603.18  6274.8  606.68
#Mann= 13 ,-1 , 0
  3564.6    .035       0  3581.8     .07       0  3897.3    .035       0
    4190     .07       0  4483.3    .035       0  4854.1     .07       0
    4991     .05       0  5008.9     .07       0  5532.3     .05       0
  5723.1     .07       0  5966.5    .035       0  6153.8     .07       0
  6181.9    .035       0
Bank Sta=4991,5008.9
XS Rating Curve= 0 ,0
Exp/Cntr=0.3,0.1

Type RM Length L Ch R = 1 ,20126   ,939,939,939
BEGIN DESCRIPTION:
LONG CREEK 34.0
END DESCRIPTION:
XS GIS Cut Line= 3
      2262276.69     13778211.44      2263157.77     13777039.56
       2263474.6     13776340.79
#Sta/Elev= 30
    3641  590.64  3707.8  589.36  3909.5  585.51  4037.8  583.74  4282.1  580.67
  4290.8  580.59  4426.6  581.01  4579.7  580.48  4775.2  578.36  4950.5  575.42
  4979.6  573.75  4985.2  570.09  4985.7  569.59  5003.2  570.09  5008.8  572.43
    5015  570.53  5023.3  572.74  5068.2  572.53  5203.7  573.38  5285.9  573.71
  5364.7  576.67  5397.6  580.87  5408.6  584.63  5426.2  585.92  5431.7  588.51
  5473.4  591.83  5570.2  593.97  5650.5  599.26  5737.3  598.78  5874.4  606.18
#Mann= 15 ,-1 , 0
    3641    .035       0  3707.8     .07       0  3909.5    .035       0
  4037.8     .07       0  4282.1    .035       0  4290.8     .07       0
  4426.6    .035       0  4579.7    .045       0  4775.2     .07       0
  4985.2     .05       0  5003.2     .07       0  5068.2     .12       0
  5203.7     .07       0  5285.9     .12       0  5473.4     .07       0
Bank Sta=4985.2,5003.2
XS Rating Curve= 0 ,0
Exp/Cntr=0.3,0.1

Type RM Length L Ch R = 1 ,19187   ,514,514,514
BEGIN DESCRIPTION:
LONG CREEK 33.0
END DESCRIPTION:
XS GIS Cut Line= 3
      2262341.79     13778267.86        2263675.       13777075.
      2263874.99       13777025.
#Sta/Elev= 30
  3215.2  590.14  3313.2  588.29  3390.7   586.3  3603.6  582.25  3625.9  581.73
  3948.1  577.79  4122.2   576.9  4458.7  575.23  4493.7  573.74  4701.3  571.98
    4763   571.3  4834.1  572.55  4884.1  571.75  4961.9  571.61    4967  568.75
  4967.5  568.25  4985.2  568.75  4990.3   573.4  4997.1  574.98  5000.8  579.09
  5006.7  579.09    5016  584.58  5022.2  588.14  5027.3  588.73  5045.4  597.36
  5055.7   601.2  5063.4  602.68  5068.6  602.24  5096.9  606.41  5210.3   612.6
#Mann= 13 ,-1 , 0
  3215.2    .035       0  3313.2     .07       0  3390.7    .045       0
  3603.6     .07       0  3625.9    .045       0  3948.1     .07       0
  4122.2    .045       0  4493.7     .07       0  4701.3     .12       0
  4884.1     .07       0    4967     .05       0  4985.2     .07       0
    5016     .12       0
Bank Sta=4967,4985.2
XS Rating Curve= 0 ,0
Exp/Cntr=0.3,0.1

Type RM Length L Ch R = 1 ,18673   ,372,372,372
BEGIN DESCRIPTION:
LONG CREEK 32.0
END DESCRIPTION:
XS GIS Cut Line= 3
      2262292.55     13778353.12      2263492.53     13777553.13
      2263775.03     13777424.99
#Sta/Elev= 30
  3521.4  592.53  3636.9  589.67  3672.9  589.84  3739.3  587.46  4126.6  579.35
  4365.6  576.79  4415.1     575  4462.4  575.69  4490.7  575.61  4676.5  575.12
  4856.6  572.87  4962.1  570.41  4977.3  571.11  4985.4  565.56  4985.9  565.06
  5003.7  565.56  5010.2   570.4  5023.1  569.66  5032.2  570.51  5046.2  569.81
  5054.2   570.9  5069.3  570.53  5109.1  573.53  5149.7  578.41  5207.8  584.92
  5218.9  584.04  5236.4  588.21  5241.9  587.21  5259.5  591.23  5273.8  592.39
#Mann= 8 ,-1 , 0
  3521.4    .035       0  3739.3    .045       0  4462.4     .07       0
  4490.7    .045       0  4856.6     .07       0  4985.4     .05       0
  5003.7     .07       0  5149.7     .12       0
Bank Sta=4985.4,5003.7
XS Rating Curve= 0 ,0
Exp/Cntr=0.3,0.1

Type RM Length L Ch R = 1 ,18301   ,469,469,469
BEGIN DESCRIPTION:
LONG CREEK 31.0
END DESCRIPTION:
XS GIS Cut Line= 3
      2262824.97     13778575.03        2263525.       13777875.
        2263875.       13777475.
#Sta/Elev= 30
  4005.5  589.94  4118.7  586.56  4191.2  585.49  4373.2  579.64  4571.2  575.02
  4677.3  573.71  4811.6  573.74  4854.1  574.65  4924.8  574.12  4938.9  573.14
  4981.3  573.57    4992  571.38  4998.8  571.38  5007.7  566.53  5008.2  566.03
    5026  566.53  5031.1  569.48  5045.3  570.45  5073.8  570.05  5080.4  570.94
  5137.4  571.67    5144  572.49  5172.5  571.37  5208.1  571.53  5272.2  573.48
    5293  576.36  5336.4  580.51  5370.9  584.63  5434.5  590.12    5527   595.8
#Mann= 5 ,-1 , 0
  4005.5    .035       0  4191.2     .07       0  5007.7     .05       0
    5026     .07       0  5336.4     .12       0
Bank Sta=5007.7,5026
XS Rating Curve= 0 ,0
Exp/Cntr=0.3,0.1

Type RM Length L Ch R = 1 ,17832   ,482,482,482
BEGIN DESCRIPTION:
LONG CREEK 30.0
END DESCRIPTION:
XS GIS Cut Line= 3
        2262675.       13778825.        2263875.       13778125.
      2264075.02     13777724.96
#Sta/Elev= 30
  3615.1  596.06  3761.9  592.98  3817.1  590.83    3940  587.63  3965.2  587.09
    4024  585.54    4067  585.74  4119.9  583.04  4382.1  575.39  4413.5  575.73
  4462.3  574.23  4659.9  572.02  4675.6  573.39  4745.3  574.91  4793.1  576.86
  4798.9  576.07  4814.6  577.26  4851.8  577.14  4916.3  570.61    4975  569.34
  4987.3  566.39  4987.8  565.89  5005.6  566.39  5007.1  568.47  5012.7  569.04
  5102.2  571.44  5175.6  575.13  5236.3  576.95  5364.3  585.59  5451.6  591.65
#Mann= 9 ,-1 , 0
  3615.1    .035       0  3817.1     .07       0    3940    .035       0
  3965.2     .07       0  4745.3     .12       0  4987.3     .05       0
  5005.6     .12       0  5175.6     .07       0  5364.3    .035       0
Bank Sta=4987.3,5005.6
XS Rating Curve= 0 ,0
Exp/Cntr=0.3,0.1