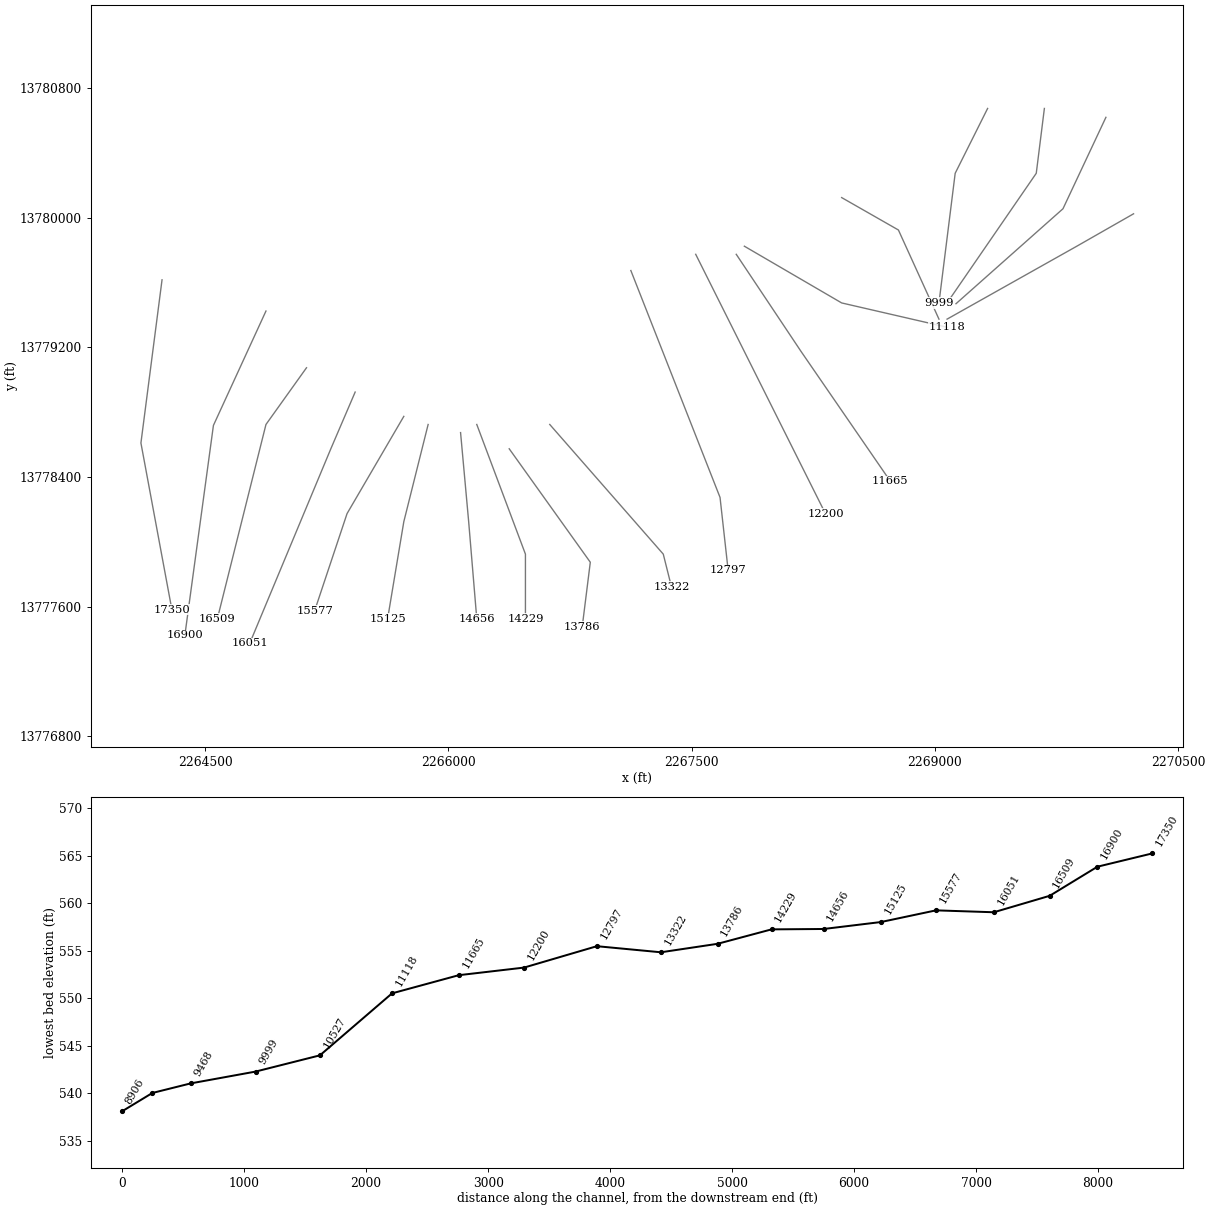
HEC-RAS study LONG CREEK.prj: LONG CREEK Base Level Engineering

--- LONG CREEK.g01 (geometry) --- (continued)

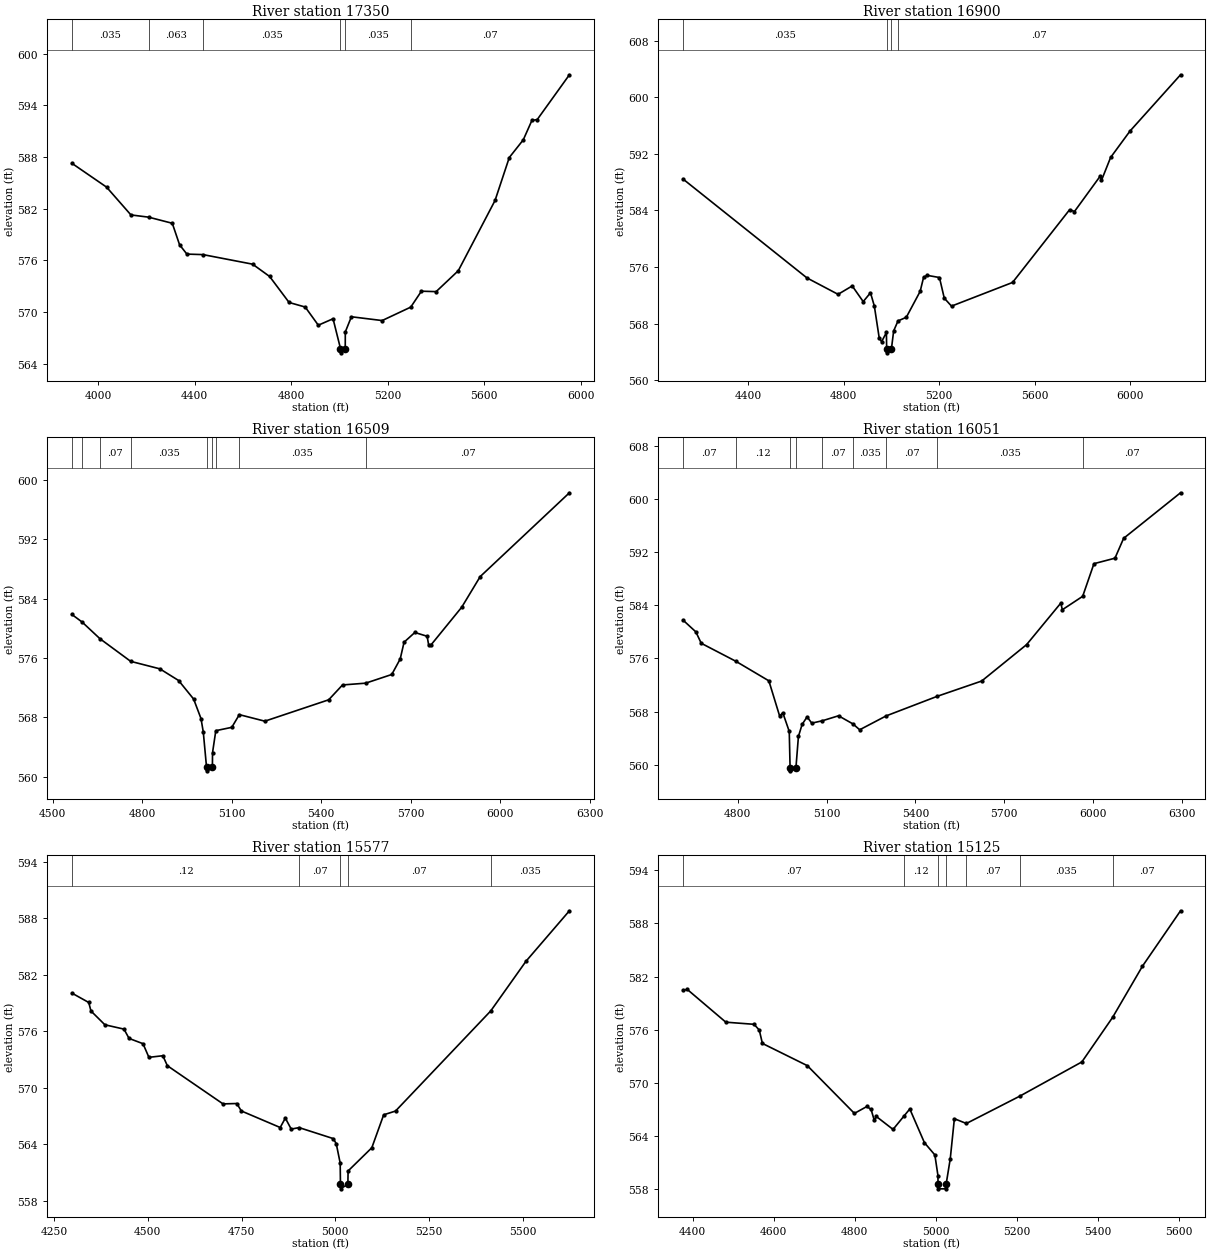
Type RM Length L Ch R = 1 ,17350   ,450,450,450
BEGIN DESCRIPTION:
A19796
END DESCRIPTION:
XS GIS Cut Line= 3
      2264234.16     13779617.65      2264103.95     13778610.74
      2264294.92     13777582.11
#Sta/Elev= 30
  3891.3  587.27  4035.1   584.5    4136  581.27  4209.5  581.01  4307.4   580.3
  4337.6   577.8  4367.9  576.72  4434.8  576.66  4640.1  575.55  4710.7  574.12
  4791.4   571.1  4858.2  570.57  4912.4  568.46  4973.5  569.21  5004.3  565.75
  5004.8  565.25    5024  565.75  5024.3  567.68  5049.5  569.44  5176.9     569
  5295.4  570.56  5339.6  572.41  5400.6  572.36  5492.4  574.79  5644.7  582.95
  5703.7  587.94  5761.6  589.99  5797.3  592.24  5819.5  592.35  5952.8  597.55
#Mann= 6 ,-1 , 0
  3891.3    .035       0  4209.5    .063       0  4434.8    .035       0
  5004.3    .035       0    5024    .035       0  5295.4     .07       0
Bank Sta=5004.3,5024
XS Rating Curve= 0 ,0
Exp/Cntr=0.3,0.1

Type RM Length L Ch R = 1 ,16900   ,391,391,391
BEGIN DESCRIPTION:
LONG CREEK 29.0
END DESCRIPTION:
XS GIS Cut Line= 3
      2264874.99     13779424.98        2264551.     13778719.24
        2264375.     13777425.01
#Sta/Elev= 30
    4128  588.45    4647  574.45  4777.2  572.13  4836.4  573.32  4882.4   571.1
  4912.9  572.35    4929  570.47  4949.2     566  4959.3  565.42  4979.5  566.73
  4980.6  564.35  4981.1  563.85  5000.3  564.35  5009.8  566.95  5028.1  568.37
  5062.8  568.88  5120.8  572.55  5135.3  574.56    5151  574.81  5201.5  574.51
  5221.7  571.59    5252  570.46  5507.5  573.81  5746.5  584.11  5766.7  583.85
  5874.7  588.87  5879.7  588.25    5918   591.5  5998.8  595.22  6210.7   603.2
#Mann= 4 ,-1 , 0
    4128    .035       0  4980.6    .035       0  5000.3    .035       0
  5028.1     .07       0
Bank Sta=4980.6,5000.3
XS Rating Curve= 0 ,0
Exp/Cntr=0.3,0.1

Type RM Length L Ch R = 1 ,16509   ,458,458,458
BEGIN DESCRIPTION:
LONG CREEK 28.0
END DESCRIPTION:
XS GIS Cut Line= 3
        2265125.       13779075.        2264875.       13778725.
      2264575.01     13777525.05
#Sta/Elev= 30
  4564.5  581.86    4599  580.83  4658.6  578.59  4761.6  575.54  4859.4  574.53
  4922.1  572.96  4972.5  570.46  4997.2  567.83  5004.9     566  5015.7  561.29
  5016.2  560.79  5035.4  561.29  5035.8  563.23  5046.8   566.2  5100.3  566.65
  5125.6  568.36  5211.1  567.48    5425  570.36  5471.3  572.36  5548.8   572.6
  5636.3  573.77  5664.6  575.86  5677.5  578.12  5713.6  579.43  5754.8  578.92
    5760  577.73  5767.7  577.75  5870.8  582.84  5932.6  586.96  6231.5  598.25
#Mann= 9 ,-1 , 0
  4564.5     .07       0    4599    .035       0  4658.6     .07       0
  4761.6    .035       0  5015.7    .035       0  5035.4    .035       0
  5046.8     .07       0  5125.6    .035       0  5548.8     .07       0
Bank Sta=5015.7,5035.4
XS Rating Curve= 0 ,0
Exp/Cntr=0.3,0.1

Type RM Length L Ch R = 1 ,16051   ,474,474,474
BEGIN DESCRIPTION:
LONG CREEK 27.0
END DESCRIPTION:
XS GIS Cut Line= 3
      2265425.01     13778925.01        2265275.       13778575.
        2264775.       13777375.
#Sta/Elev= 30
  4614.9  581.79  4658.4  580.01  4676.6  578.29  4793.4  575.58    4905  572.63
  4941.3  567.34  4952.2   567.8  4973.9     565  4976.7  559.56  4977.2  559.06
  4996.5  559.56  5004.9  564.25  5017.4  566.06  5034.2   567.2  5049.9  566.25
  5085.8  566.61  5140.3  567.36  5189.2  566.13  5211.8  565.25  5301.1  567.34
    5474   570.3    5624   572.6  5775.7  578.09  5891.1  584.34  5896.5  583.35
  5965.1  585.37  6003.2  590.29  6074.2  591.12  6103.4  594.11  6295.7  600.98
#Mann= 9 ,-1 , 0
  4614.9     .07       0  4793.4     .12       0  4976.7     .05       0
  4996.5     .12       0  5085.8     .07       0  5189.2    .035       0
  5301.1     .07       0    5474    .035       0  5965.1     .07       0
Bank Sta=4976.7,4996.5
XS Rating Curve= 0 ,0
Exp/Cntr=0.3,0.1

Type RM Length L Ch R = 1 ,15577   ,452,452,452
BEGIN DESCRIPTION:
LONG CREEK 26.0
END DESCRIPTION:
XS GIS Cut Line= 3
      2265725.02     13778775.04        2265375.       13778175.
      2265175.01     13777575.02
#Sta/Elev= 30
  4297.5  580.07  4342.6  579.07  4348.4  578.17  4385.6   576.7  4436.5  576.24
  4450.1  575.25  4487.3  574.69    4503  573.24  4540.2  573.41  4552.2  572.35
  4700.7  568.29  4737.5  568.33  4749.5  567.54  4853.2  565.78  4866.9  566.78
  4882.6  565.61  4903.6  565.77  4994.8   564.6  5002.7  564.06  5013.2     562
  5013.9  559.76  5014.4  559.26  5033.7  559.76  5034.3  561.16  5097.6  563.63
  5129.2  567.13  5160.8  567.53  5414.9  578.18  5508.7  583.45  5624.6  588.82
#Mann= 5 ,-1 , 0
  4297.5     .12       0  4903.6     .07       0  5013.9     .05       0
  5033.7     .07       0  5414.9    .035       0
Bank Sta=5013.9,5033.7
XS Rating Curve= 0 ,0
Exp/Cntr=0.3,0.1

Type RM Length L Ch R = 1 ,15125   ,469,469,469
BEGIN DESCRIPTION:
LONG CREEK 25.0
END DESCRIPTION:
XS GIS Cut Line= 3
        2265875.     13778724.98        2265725.       13778125.
        2265625.     13777525.02
#Sta/Elev= 30
  4376.4  580.43  4386.7  580.56    4482  576.85  4551.6  576.61  4564.5  575.96
  4572.2  574.45    4683  571.94    4799  566.55  4829.9  567.33  4840.2  566.99
    4848  565.77  4853.1   566.2  4894.3  564.74  4921.1  566.24  4935.6  567.05
  4971.7  563.24  4997.4  561.86    5005  559.53  5005.2  558.53  5005.7  558.03
  5024.6  558.03  5025.1  558.53  5035.4  561.44  5045.5  565.95  5075.1  565.41
  5206.9   568.5  5359.8  572.36  5435.6  577.39  5509.3  583.18  5603.1  589.43
#Mann= 7 ,-1 , 0
  4376.4     .07       0  4921.1     .12       0  5005.2     .05       0
  5025.1     .12       0  5075.1     .07       0  5206.9    .035       0
  5435.6     .07       0
Bank Sta=5005.2,5025.1
XS Rating Curve= 0 ,0
Exp/Cntr=0.3,0.1

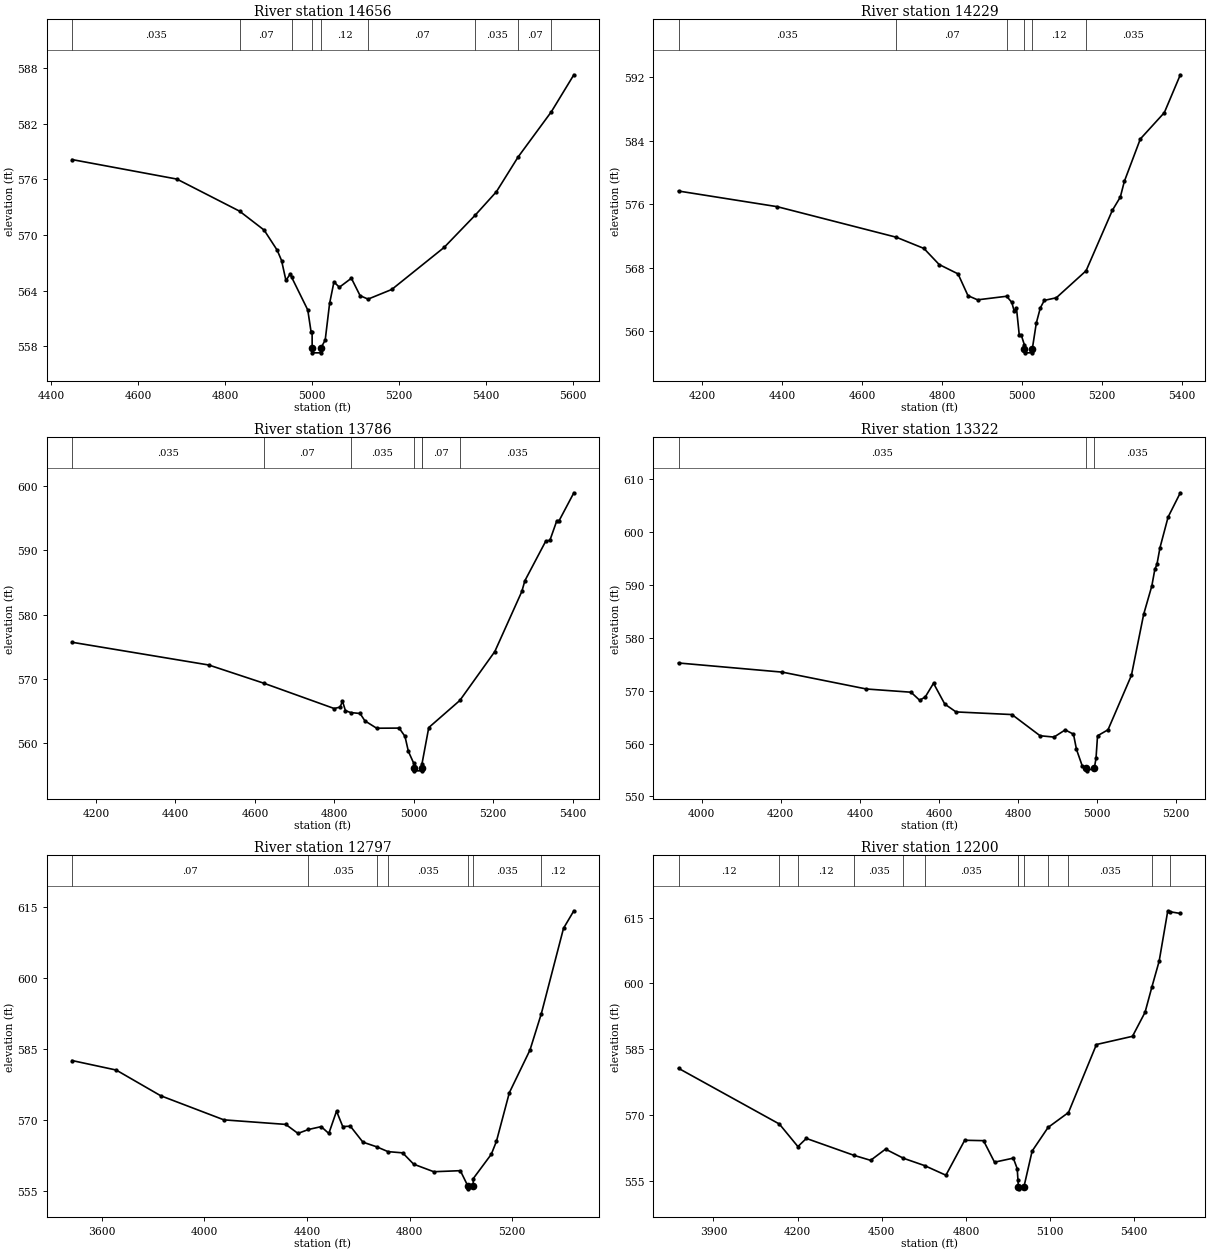
Type RM Length L Ch R = 1 ,14656   ,427,427,427
BEGIN DESCRIPTION:
LONG CREEK 24.0
END DESCRIPTION:
XS GIS Cut Line= 3
        2266075.     13778674.96        2266125.       13778125.
        2266175.     13777525.01
#Sta/Elev= 30
  4447.8  578.13  4688.8  576.03  4833.1  572.57  4889.6  570.53  4919.7  568.36
  4929.7  567.25  4939.8   565.1  4949.8  565.82  4953.1  565.43    4990  561.92
  4997.5  559.59    5000  559.59  5000.1   557.8  5000.6   557.3  5019.5   557.3
    5020   557.8  5030.1  558.68  5040.2  562.62  5050.2  564.94  5062.7  564.37
  5090.3  565.34  5110.4  563.46  5128.7  563.09  5183.2  564.13  5303.6  568.66
  5375.2  572.14    5424  574.67  5473.7   578.4  5550.4  583.29  5602.1  587.27
#Mann= 9 ,-1 , 0
  4447.8    .035       0  4833.1     .07       0  4953.1     .12       0
  5000.1     .05       0    5020     .12       0  5128.7     .07       0
  5375.2    .035       0  5473.7     .07       0  5550.4    .035       0
Bank Sta=5000.1,5020
XS Rating Curve= 0 ,0
Exp/Cntr=0.3,0.1

Type RM Length L Ch R = 1 ,14229   ,443,443,443
BEGIN DESCRIPTION:
LONG CREEK 23.0
END DESCRIPTION:
XS GIS Cut Line= 3
      2266174.98     13778725.04        2266475.       13777925.
        2266475.     13777525.05
#Sta/Elev= 30
  4140.9  577.65  4387.5  575.68  4685.2  571.83  4754.2  570.42  4792.4  568.39
  4839.6  567.21  4864.5  564.46  4888.5  563.94  4961.1  564.39    4974  563.62
  4980.2  562.48  4985.6  562.94  4992.7  559.48  4997.8  559.48  5005.3  558.29
  5005.4  557.76  5005.9  557.26  5024.8  557.26  5025.3  557.76  5035.3  561.02
  5045.3  562.92  5055.3  563.87  5085.3   564.2  5159.7   567.6  5225.3  575.21
  5245.3  576.89  5255.3  578.86  5295.3  584.21  5355.3  587.53  5395.3   592.3
#Mann= 6 ,-1 , 0
  4140.9    .035       0  4685.2     .07       0  4961.1     .12       0
  5005.4     .05       0  5025.3     .12       0  5159.7    .035       0
Bank Sta=5005.4,5025.3
XS Rating Curve= 0 ,0
Exp/Cntr=0.3,0.1

Type RM Length L Ch R = 1 ,13786   ,464,464,464
BEGIN DESCRIPTION:
LONG CREEK 22.0
END DESCRIPTION:
XS GIS Cut Line= 3
        2266375.       13778575.        2266875.       13777875.
        2266825.     13777475.04
#Sta/Elev= 30
  4139.7  575.71  4483.8  572.18    4622  569.36  4799.6  565.42  4814.4  565.64
  4820.5  566.56  4827.9  565.09  4841.3  564.79  4864.7  564.65    4877   563.5
  4906.5  562.36  4963.1  562.38  4977.8   561.1  4986.4  558.76  4999.9  556.91
  5000.1  556.24  5000.6  555.74  5019.5  555.74    5020  556.24  5020.5  556.77
  5037.7  562.46  5115.9  566.67    5204  574.27    5272   583.6  5279.6  585.26
  5332.5  591.45  5342.6  591.53  5360.2  594.61  5365.2  594.52    5403  598.93
#Mann= 7 ,-1 , 0
  4139.7    .035       0    4622     .07       0  4841.3    .035       0
  5000.1    .035       0    5020    .035       0  5020.5     .07       0
  5115.9    .035       0
Bank Sta=5000.1,5020
XS Rating Curve= 0 ,0
Exp/Cntr=0.3,0.1

Type RM Length L Ch R = 1 ,13322   ,525,525,525
BEGIN DESCRIPTION:
LONG CREEK 21.0
END DESCRIPTION:
XS GIS Cut Line= 3
      2266625.03     13778724.97        2267325.       13777925.
      2267374.99     13777725.03
#Sta/Elev= 30
  3941.4  575.26  4203.8  573.53  4416.4  570.34  4529.3  569.73  4551.2  568.21
  4565.4  568.83  4586.3  571.42  4614.8  567.48  4643.2     566  4784.7   565.5
  4855.8  561.49    4891  561.24  4919.4   562.6  4940.3  561.78  4947.9   558.9
  4962.1  555.86    4973  555.35  4973.5  554.85    4993  555.35  4997.3  557.27
  5001.1  561.48  5027.6  562.62  5086.8  572.92  5117.8  584.48  5138.4  589.83
  5146.1     593  5151.3   593.9    5159  597.07  5179.6  602.88  5210.5  607.47
#Mann= 3 ,-1 , 0
  3941.4    .035       0    4973    .035       0    4993    .035       0
Bank Sta=4973,4993
XS Rating Curve= 0 ,0
Exp/Cntr=0.3,0.1

Type RM Length L Ch R = 1 ,12797   ,597,597,597
BEGIN DESCRIPTION:
LONG CREEK 20.0
END DESCRIPTION:
XS GIS Cut Line= 3
      2267125.02     13779674.96        2267675.       13778275.
        2267725.     13777824.99
#Sta/Elev= 30
  3483.9  582.55  3655.8  580.55  3829.4  575.13    4076  570.04  4317.3  569.08
  4364.9  567.18  4405.9  568.01  4455.5  568.61  4485.2  567.17  4515.3  571.88
  4539.5  568.63  4569.2   568.7  4618.1  565.34  4672.1  564.35  4715.9  563.34
  4773.1  563.08  4816.1  560.69  4894.5   559.1  4998.1  559.32  5028.3  555.99
  5028.8  555.49  5048.3  555.99  5048.4  557.65  5118.8  562.78  5138.9  565.52
  5189.2  575.77  5269.7  584.77  5314.1  592.47  5400.5  610.45  5440.8  614.14
#Mann= 7 ,-1 , 0
  3483.9     .07       0  4405.9    .035       0  4672.1     .05       0
  4715.9    .035       0  5028.3    .035       0  5048.3    .035       0
  5314.1     .12       0
Bank Sta=5028.3,5048.3
XS Rating Curve= 0 ,0
Exp/Cntr=0.3,0.1

Type RM Length L Ch R = 1 ,12200   ,535,535,535
BEGIN DESCRIPTION:
LONG CREEK 19.0
END DESCRIPTION:
XS GIS Cut Line= 3
      2267524.98     13779775.03        2268075.       13778675.
      2268325.01     13778174.99
#Sta/Elev= 30
  3775.5  580.68  4134.9     568  4201.1  562.86  4231.1  564.72  4401.8  560.85
  4460.3  559.73  4513.4  562.28  4577.4   560.2  4652.4  558.54  4728.7  556.34
  4795.7   564.3  4862.8  564.21    4902  559.31    4969  560.23    4983  557.81
  4985.6  555.16    4987  553.74  4987.5  553.24    5007  553.74  5036.1  561.84
  5092.9  567.22  5165.7  570.62  5265.3   586.1  5393.9  587.97  5438.6  593.43
  5463.2  599.24  5488.9  605.07  5519.7  616.55  5526.6  616.34  5564.4  615.94
#Mann= 13 ,-1 , 0
  3775.5     .12       0  4134.9     .07       0  4201.1     .12       0
  4401.8    .035       0  4577.4     .05       0  4652.4    .035       0
  4985.6     .05       0    4987    .035       0    5007     .05       0
  5092.9     .05       0  5165.7    .035       0  5463.2     .05       0
  5526.6    .035       0
Bank Sta=4987,5007
XS Rating Curve= 0 ,0
Exp/Cntr=0.3,0.1

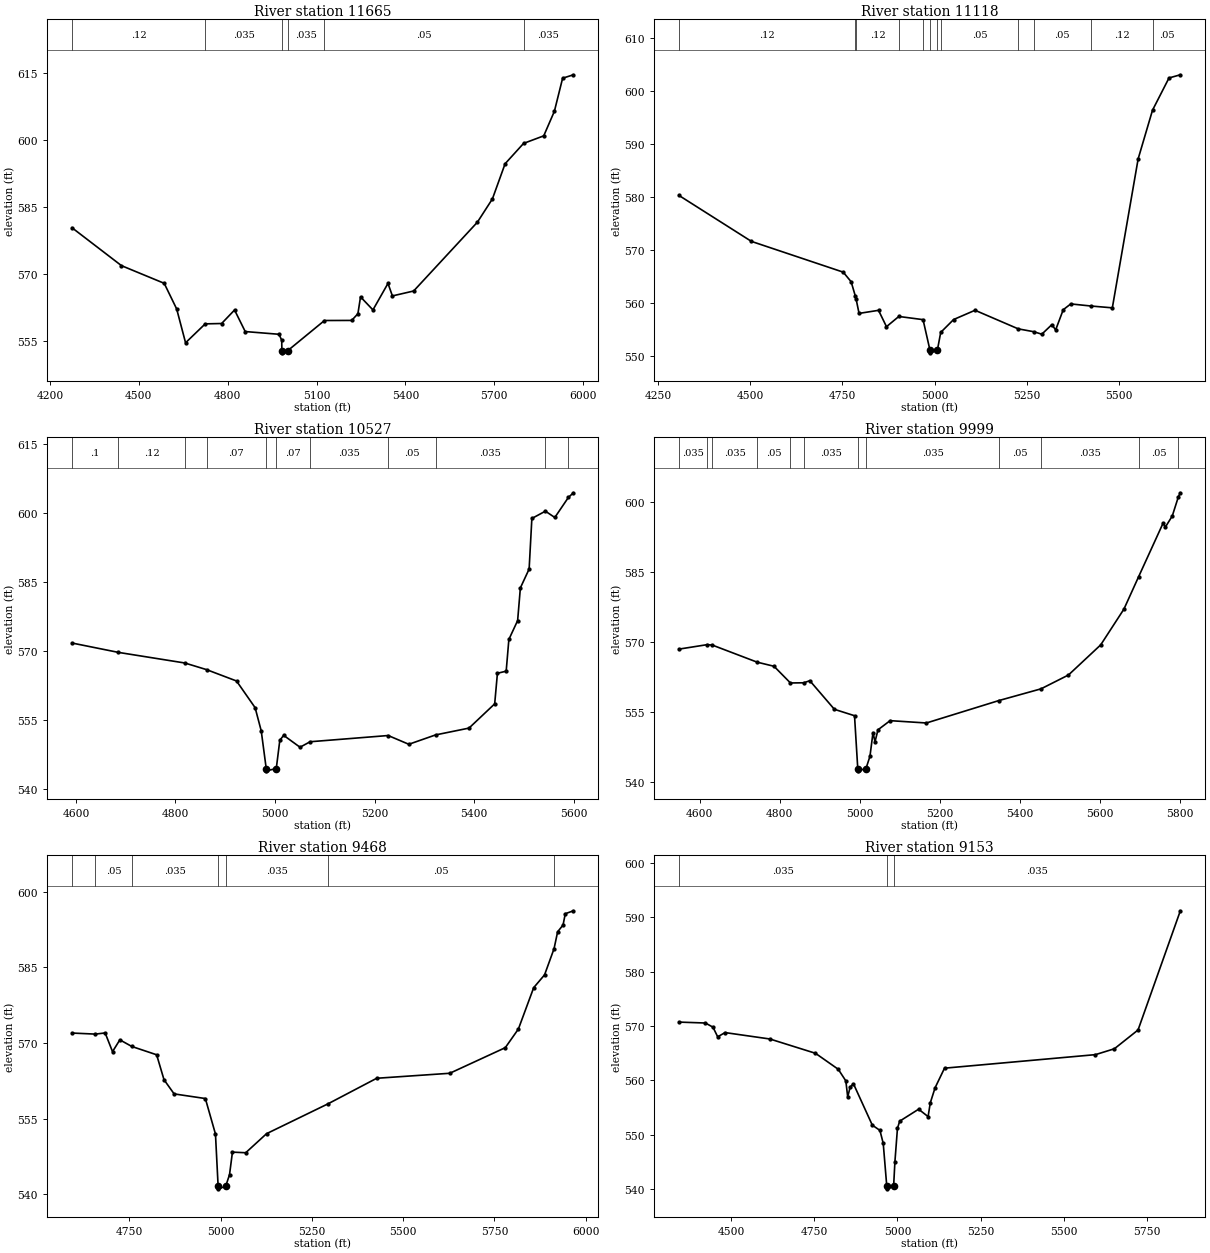
Type RM Length L Ch R = 1 ,11665   ,547,547,547
BEGIN DESCRIPTION:
LONG CREEK 18.0
END DESCRIPTION:
XS GIS Cut Line= 3
      2267774.99     13779775.02        2268175.       13779175.
      2268725.03     13778374.96
#Sta/Elev= 30
  4274.9  580.41  4441.7  571.94  4585.9  567.99    4628  562.25    4658  554.69
  4724.3  558.92  4779.7     559  4823.3  562.02  4859.3   557.2  4973.5  556.59
  4982.5  555.24    4983  552.94  4983.5  552.44    5003  552.94  5126.8  559.67
  5218.6  559.69  5239.6  561.19  5248.4  564.96  5290.3  562.04  5341.1  567.97
    5356  565.17  5427.7  566.27  5642.8  581.66  5693.5  586.87  5736.3  594.73
  5798.6  599.28  5866.7  600.97  5902.6  606.46  5930.4  613.86  5966.9  614.63
#Mann= 6 ,-1 , 0
  4274.9     .12       0  4724.3    .035       0    4983    .035       0
    5003    .035       0  5126.8     .05       0  5798.6    .035       0
Bank Sta=4983,5003
XS Rating Curve= 0 ,0
Exp/Cntr=0.3,0.1

Type RM Length L Ch R = 1 ,11118   ,591,591,591
BEGIN DESCRIPTION:
LONG CREEK 17.0
END DESCRIPTION:
XS GIS Cut Line= 3
        2267825.       13779825.        2268425.       13779475.
        2269075.       13779325.
#Sta/Elev= 30
  4305.9  580.26  4502.7  571.58    4752  565.77  4773.5  563.96  4785.2  561.18
    4787  560.69    4795  557.98  4847.9  558.56  4869.5  555.47    4903   557.4
  4968.8   556.8  4987.6  551.03  4988.1  550.53  5007.7  551.03  5016.8  554.39
  5051.8  556.82    5110  558.57  5227.3  555.06  5269.5  554.52  5291.3  554.05
  5318.7  555.86  5328.9  554.85  5349.5  558.67    5370  559.77  5423.9  559.38
  5482.9  559.03    5553  587.17    5592  596.36  5636.8  602.45  5667.6  603.05
#Mann= 12 ,-1 , 0
  4305.9     .12       0  4785.2    .035       0    4787     .12       0
    4903     .07       0  4968.8    .035       0  4987.6    .035       0
  5007.7    .035       0  5016.8     .05       0  5227.3    .035       0
  5269.5     .05       0  5423.9     .12       0    5592     .05       0
Bank Sta=4987.6,5007.7
XS Rating Curve= 0 ,0
Exp/Cntr=0.3,0.1

Type RM Length L Ch R = 1 ,10527   ,528,528,528
BEGIN DESCRIPTION:
LONG CREEK 16.0
END DESCRIPTION:
XS GIS Cut Line= 3
        2268425.       13780125.        2268775.       13779925.
      2269025.01     13779374.97
#Sta/Elev= 30
  4592.3  571.73  4685.5   569.7  4818.9   567.4  4862.6  565.96  4922.7   563.5
  4960.1  557.71  4972.4  552.67  4982.4  544.51  4982.9  544.01  5002.6  544.51
  5009.7  550.62  5017.4  551.71  5050.3  549.13  5070.6  550.32  5227.4  551.67
  5268.9  549.77  5322.6   551.8  5389.8  553.28  5441.4  558.54  5446.9  565.17
  5464.5  565.63  5469.9  572.51  5487.5   576.6    5493  583.69  5510.6  587.78
  5516.1  598.75  5543.3  600.33  5562.2  598.96  5589.6  603.33  5599.6  604.32
#Mann= 11 ,-1 , 0
  4592.3      .1       0  4685.5     .12       0  4818.9      .1       0
  4862.6     .07       0  4982.4     .05       0  5002.6     .07       0
  5070.6    .035       0  5227.4     .05       0  5322.6    .035       0
  5543.3     .12       0  5589.6     .05       0
Bank Sta=4982.4,5002.6
XS Rating Curve= 0 ,0
Exp/Cntr=0.3,0.1

Type RM Length L Ch R = 1 ,9999    ,531,531,531
BEGIN DESCRIPTION:
LONG CREEK 15.0
END DESCRIPTION:
XS GIS Cut Line= 3
      2269325.02     13780675.04        2269125.       13780275.
        2269025.     13779474.99
#Sta/Elev= 30
  4548.2   568.4  4619.1  569.36    4632  569.25  4743.7   565.6  4785.8  564.72
  4826.9  561.14  4860.4  561.18  4875.3  561.63  4936.8  555.49  4987.1  554.12
  4995.2   542.8  4995.7   542.3  5015.8   542.8  5025.7  545.42  5033.3   550.5
  5038.3  548.54  5045.8   551.1  5076.1  553.06  5166.8  552.56  5348.4  557.38
  5453.3  559.88    5522  562.85  5602.6  569.31  5660.6  576.97  5697.1  583.87
  5758.9  595.47  5763.9  594.52  5781.5  596.94  5796.9  601.09  5801.7  601.92
#Mann= 12 ,-1 , 0
  4548.2    .035       0  4619.1      .1       0    4632    .035       0
  4743.7     .05       0  4826.9      .1       0  4860.4    .035       0
  4995.2    .035       0  5015.8    .035       0  5348.4     .05       0
  5453.3    .035       0  5697.1     .05       0  5796.9    .035       0
Bank Sta=4995.2,5015.8
XS Rating Curve= 0 ,0
Exp/Cntr=0.3,0.1

Type RM Length L Ch R = 1 ,9468    ,315,315,315
BEGIN DESCRIPTION:
LONG CREEK 14.0
END DESCRIPTION:
XS GIS Cut Line= 3
        2269675.     13780675.01        2269625.       13780275.
      2269075.03     13779475.04
#Sta/Elev= 30
  4592.7  571.96  4656.8  571.75  4683.4  571.98  4703.6  568.27  4723.7  570.61
  4756.4   569.3  4824.5  567.65  4844.7   562.7  4872.4  559.89    4958  558.97
  4985.7  551.93    4993  541.56  4993.5  541.06  5013.6  541.56  5024.2  543.86
  5032.2  548.34  5068.6  548.22  5125.7     552  5293.8  557.91  5427.5  562.99
  5627.7  563.98  5779.9  569.06  5815.8  572.76  5857.7  580.96  5887.5   583.5
  5913.5  588.69  5923.3  592.04  5938.2  593.39  5944.3  595.63  5966.6  596.21
#Mann= 7 ,-1 , 0
  4592.7    .035       0  4656.8     .05       0  4756.4    .035       0
    4993    .035       0  5013.6    .035       0  5293.8     .05       0
  5913.5    .035       0
Bank Sta=4993,5013.6
XS Rating Curve= 0 ,0
Exp/Cntr=0.3,0.1

Type RM Length L Ch R = 1 ,9153    ,247,247,247
BEGIN DESCRIPTION:
A19795
END DESCRIPTION:
XS GIS Cut Line= 3
      2270054.48     13780620.29      2269789.72     13780056.05
      2269130.02     13779470.13
#Sta/Elev= 30
  4344.1  570.73  4423.5  570.56  4446.3  569.79  4460.4  568.02  4482.5   568.8
  4617.1  567.62    4754  564.99  4822.4  562.05  4845.2  559.91  4850.8  556.96
  4858.1  558.76  4868.1  559.38  4924.7  551.77  4947.6   550.8  4957.5  548.41
  4968.1  540.55  4968.6  540.05  4988.7  540.55  4992.6  545.06  5000.2  551.18
  5006.9   552.5  5063.7   554.7  5092.2  553.34  5098.8  555.87  5113.1  558.63
  5141.5  562.25  5594.7  564.74  5651.6  565.82  5722.7  569.28  5849.7  591.21
#Mann= 3 ,-1 , 0
  4344.1    .035       0  4968.1    .035       0  4988.7    .035       0
Bank Sta=4968.1,4988.7
XS Rating Curve= 0 ,0
Exp/Cntr=0.3,0.1

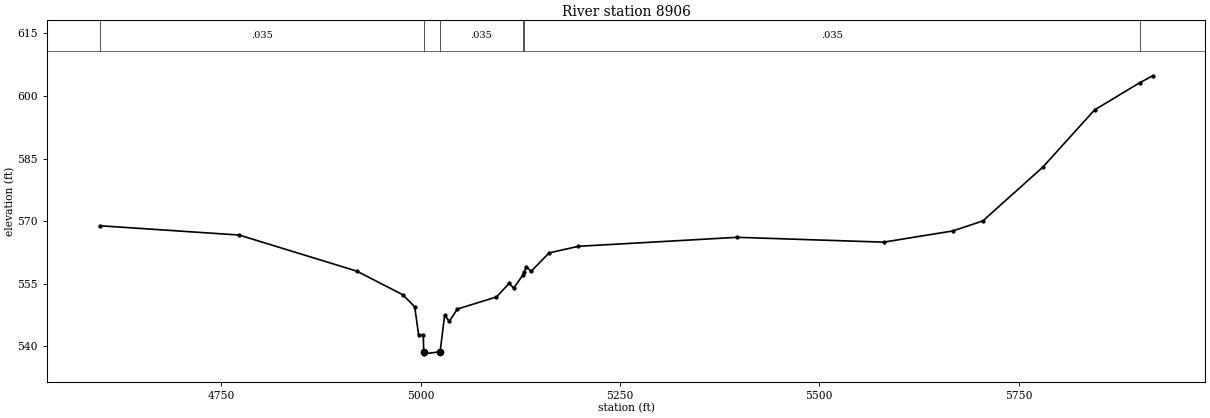
Type RM Length L Ch R = 1 ,8906    ,551,551,551
BEGIN DESCRIPTION:
LONG CREEK 13.0
END DESCRIPTION:
XS GIS Cut Line= 3
        2270225.       13780025.        2269875.       13779825.
        2269075.       13779375.
#Sta/Elev= 30
  4597.4  568.87  4772.3  566.64  4919.9  557.98  4977.5  552.33  4992.6  549.43
  4997.6  542.59  5003.4  542.59  5003.9  538.63  5004.4  538.13  5024.5  538.63
  5030.2  547.48  5035.9   545.9  5046.1  548.87  5095.2  551.79  5111.1  555.03
  5116.8  553.91  5128.2     557  5130.1  557.86  5132.8  559.07  5138.5  557.91
  5161.1  562.34  5197.8  563.93  5397.3  566.09  5580.9  564.93  5667.6  567.62
  5705.2  570.02  5780.4  582.91  5845.4  596.66    5902  603.17  5918.4  604.85
#Mann= 6 ,-1 , 0
  4597.4    .035       0  5003.9    .035       0  5024.5    .035       0
  5128.2     .05       0  5130.1    .035       0    5902     .05       0
Bank Sta=5003.9,5024.5
XS Rating Curve= 0 ,0
Exp/Cntr=0.3,0.1