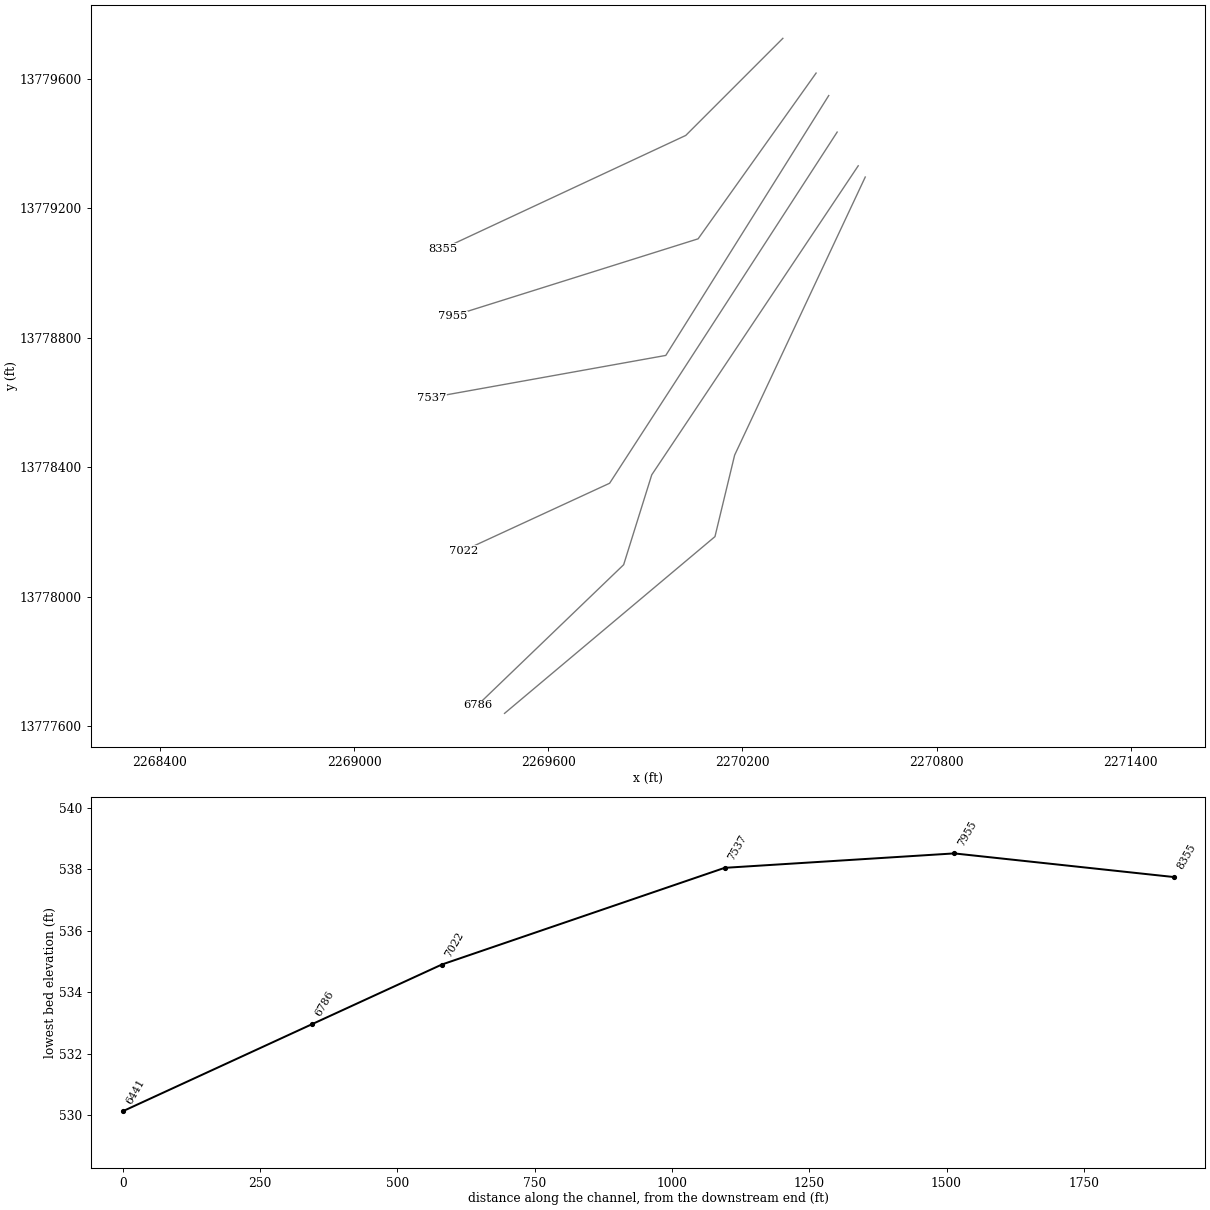
HEC-RAS study LONG CREEK.prj: LONG CREEK Base Level Engineering

--- LONG CREEK.g01 (geometry) --- (continued)

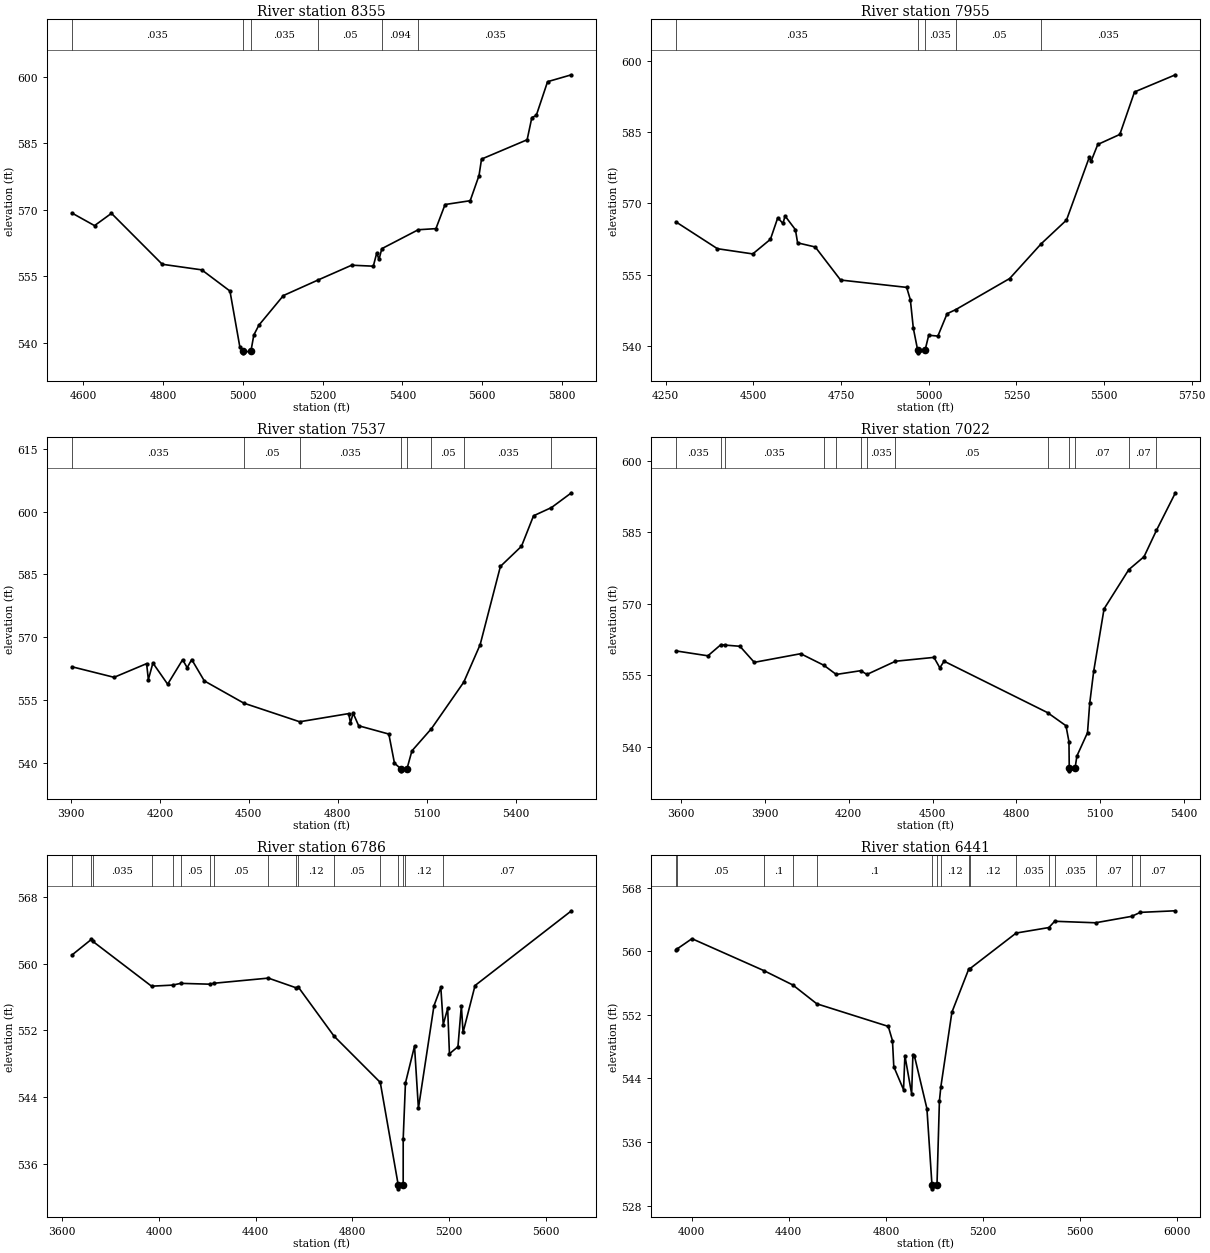
Type RM Length L Ch R = 1 ,8355    ,400,400,400
BEGIN DESCRIPTION:
LONG CREEK 12.0
END DESCRIPTION:
XS GIS Cut Line= 3
      2270325.02     13779725.02        2270025.       13779425.
      2269275.03     13779075.01
#Sta/Elev= 30
  4571.6  569.29  4628.2  566.45  4670.6  569.22  4797.9  557.73  4896.9  556.47
  4967.6  551.69  4992.4  539.07  4999.7  538.25  5000.2  537.75  5020.4  538.25
  5027.4  541.77    5040  543.98  5101.5  550.67  5188.1  554.17  5272.6  557.52
  5326.9   557.3  5335.6  560.32  5341.1  558.81  5348.2  561.25  5439.5  565.52
  5483.8  565.77  5506.7  571.21  5569.7  572.07  5591.8  577.75  5598.1  581.46
  5712.4  585.82  5724.2  590.83  5735.3   591.3  5763.6  598.92  5823.5  600.48
#Mann= 6 ,-1 , 0
  4571.6    .035       0  4999.7    .035       0  5020.4    .035       0
  5188.1     .05       0  5348.2    .094       0  5439.5    .035       0
Bank Sta=4999.7,5020.4
XS Rating Curve= 0 ,0
Exp/Cntr=0.3,0.1

Type RM Length L Ch R = 1 ,7955    ,418,418,418
BEGIN DESCRIPTION:
A19794
END DESCRIPTION:
XS GIS Cut Line= 3
      2270427.74     13779617.68      2270063.15     13779105.53
      2269303.65     13778866.83
#Sta/Elev= 30
  4278.9  566.11  4397.3  560.46  4498.1  559.36  4548.5  562.44  4569.4  566.97
  4584.2  565.78  4590.3  567.35  4619.8  564.46    4626  561.69  4676.4  560.82
  4748.6  553.86  4937.1  552.31  4947.6  549.71  4956.1  543.71  4968.7  539.02
  4969.2  538.52  4989.4  539.02    5000  542.23  5026.1  542.05  5052.4  546.76
  5077.7  547.65    5231  554.18  5320.7  561.49    5393  566.49  5457.8  579.68
    5463  578.86  5482.2  582.42  5545.1  584.53    5587  593.48  5703.7   597.1
#Mann= 5 ,-1 , 0
  4278.9    .035       0  4968.7    .035       0  4989.4    .035       0
  5077.7     .05       0  5320.7    .035       0
Bank Sta=4968.7,4989.4
XS Rating Curve= 0 ,0
Exp/Cntr=0.3,0.1

Type RM Length L Ch R = 1 ,7537    ,515,515,515
BEGIN DESCRIPTION:
A19793
END DESCRIPTION:
XS GIS Cut Line= 3
      2270466.78     13779548.21      2269963.33     13778745.28
      2269239.23     13778615.21
#Sta/Elev= 30
  3903.9  562.92  4045.9   560.4  4155.5  563.67  4161.4  559.86  4176.7  563.82
  4226.4  558.75  4276.9  564.61  4292.2   562.7  4307.5  564.65    4350  559.54
  4483.4  554.22  4671.3  549.78  4836.6  551.73  4842.5  549.51  4851.6  551.82
  4870.2  548.82  4971.8  546.84  4990.8  539.88  5012.3  538.55  5012.8  538.05
    5033  538.55  5049.6  542.82  5115.6  548.15  5224.3  559.24  5279.6  568.21
  5347.8   586.9  5418.9  591.72  5459.5     599    5520  600.97  5587.3   604.5
#Mann= 8 ,-1 , 0
  3903.9    .035       0  4483.4     .05       0  4671.3    .035       0
  5012.3    .035       0    5033    .035       0  5115.6     .05       0
  5224.3    .035       0    5520    .063       0
Bank Sta=5012.3,5033
XS Rating Curve= 0 ,0
Exp/Cntr=0.3,0.1

Type RM Length L Ch R = 1 ,7022    ,236,236,236
BEGIN DESCRIPTION:
A19792
END DESCRIPTION:
XS GIS Cut Line= 3
      2270492.82     13779435.36      2269789.72     13778350.32
      2269339.12     13778142.35
#Sta/Elev= 30
  3580.7  560.06  3695.3  559.03  3741.8  561.37  3756.3  561.28    3810  561.03
  3861.4  557.66  4027.6  559.47  4110.8  557.04    4155  555.12  4242.9  555.91
  4264.9  555.12  4367.2  557.89    4505   558.7  4526.1   556.5  4541.2   557.9
  4911.9  547.11  4977.9  544.36  4988.6     541  4989.6   535.4  4990.1   534.9
  5010.3   535.4    5017  538.01    5055   542.9  5062.9  549.05  5077.1  555.77
  5114.3  568.88  5202.8   577.1  5257.5  579.82  5301.9  585.34  5369.9  593.23
#Mann= 13 ,-1 , 0
  3580.7    .035       0  3741.8     .05       0  3756.3    .035       0
  4110.8     .05       0    4155    .035       0  4242.9     .05       0
  4264.9    .035       0  4367.2     .05       0  4911.9     .07       0
  4989.6     .05       0  5010.3     .07       0  5202.8     .07       0
  5301.9     .05       0
Bank Sta=4989.6,5010.3
XS Rating Curve= 0 ,0
Exp/Cntr=0.3,0.1

Type RM Length L Ch R = 1 ,6786    ,345,345,345
BEGIN DESCRIPTION:
A19791
END DESCRIPTION:
XS GIS Cut Line= 4
      2270557.93      13779331.2      2269919.92     13778376.36
      2269833.12     13778098.58      2269381.73     13777664.56
#Sta/Elev= 30
    3640  561.02    3720  562.89  3725.8  562.67  3969.1  557.28  4056.5  557.41
  4089.9  557.62  4210.6  557.52  4226.2  557.63  4452.2  558.25  4565.7   557.1
  4576.6  557.15  4723.7  551.29    4915  545.73    4989  533.46  4989.5  532.96
  5009.7  533.46  5009.8  538.98  5019.1  545.66  5056.6  550.08  5072.7  542.62
  5137.1  554.94  5165.4  557.14  5175.4  552.68  5193.7  554.61    5201  549.17
  5236.2  550.02  5250.3  554.94  5257.3  551.73  5306.9  557.36  5705.6  566.33
#Mann= 17 ,-1 , 0
    3640    .035       0    3720     .05       0  3725.8    .035       0
  3969.1      .1       0  4056.5    .035       0  4089.9     .05       0
  4210.6      .1       0  4226.2     .05       0  4452.2      .1       0
  4565.7     .05       0  4576.6     .12       0  4723.7     .05       0
    4915     .07       0    4989     .05       0  5009.7     .07       0
  5019.1     .12       0  5175.4     .07       0
Bank Sta=4989,5009.7
XS Rating Curve= 0 ,0
Exp/Cntr=0.3,0.1

Type RM Length L Ch R = 1 ,6441    ,0,0,0
BEGIN DESCRIPTION:
A19790
END DESCRIPTION:
XS GIS Cut Line= 4
      2270579.64      13779296.5        2270176.     13778437.12
      2270115.24     13778185.39      2269465.09     13777639.26
#Sta/Elev= 30
  3935.1  560.21  3939.5  560.28  4001.2  561.58  4297.7  557.56  4416.6  555.76
  4515.5  553.39  4809.8  550.55  4827.1  548.76  4832.6  545.48  4872.7  542.59
  4878.3  546.88  4906.1  542.06  4911.3  547.01  4917.6  546.83    4969  540.21
  4989.8  530.62  4990.3  530.12  5010.5  530.62  5020.5  541.18  5026.5  542.97
  5071.9  552.33  5141.4  557.77  5144.5  557.77  5336.6  562.29  5471.4  562.98
  5495.2  563.77  5663.5  563.58  5812.5  564.39  5847.9  564.89  5992.6  565.09
#Mann= 16 ,-1 , 0
  3935.1    .035       0  3939.5     .05       0  4297.7      .1       0
  4416.6     .05       0  4515.5      .1       0  4989.8     .05       0
  5010.5      .1       0  5026.5     .12       0  5141.4    .035       0
  5144.5     .12       0  5336.6    .035       0  5471.4     .12       0
  5495.2    .035       0  5663.5     .07       0  5812.5    .063       0
  5847.9     .07       0
Bank Sta=4989.8,5010.5
XS Rating Curve= 0 ,0
Exp/Cntr=0.3,0.1

Chan Stop Cuts=-1
Use User Specified Reach Order=0
Composite Channel Slope=5