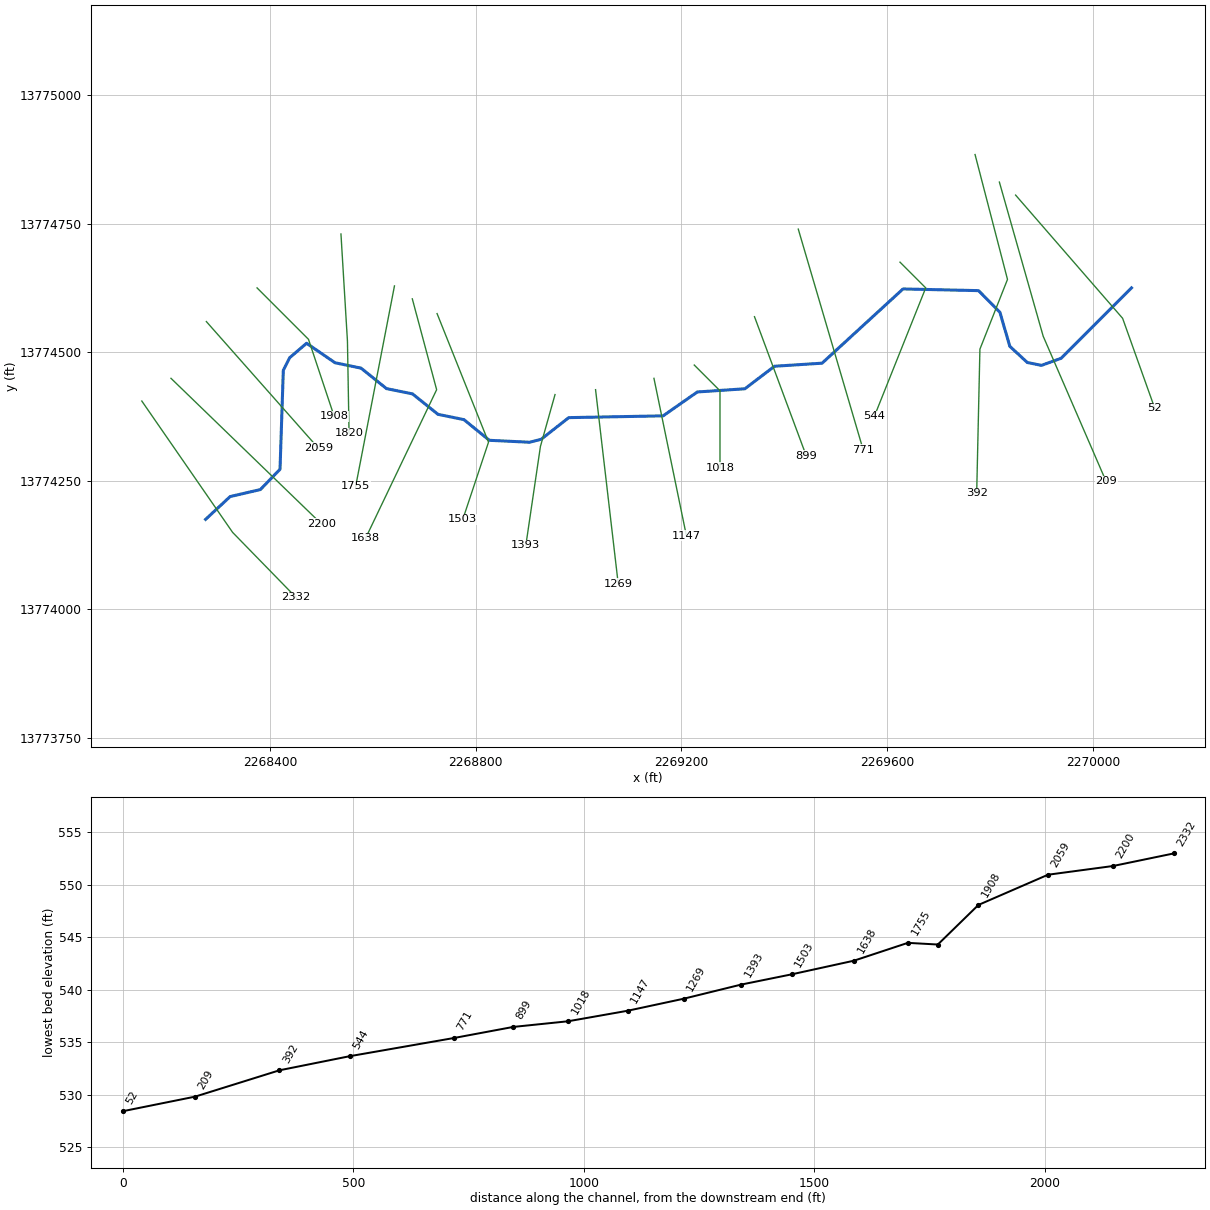
--- LONG TRIBUTARY 1.prj (project) ---

Proj Title=LONG TRIBUTARY 1 Base Level Engineering
Current Plan=p01
Default Exp/Contr=0.3,0.1
English Units
Geom File=g01
Flow File=f01
Plan File=p01
Y Axis Title=Elevation
X Axis Title(PF)=Main Channel Distance
X Axis Title(XS)=Station
BEGIN DESCRIPTION:
LONG TRIBUTARY 1
END DESCRIPTION:
DSS Export Rating Curves= 0
DSS Export Rating Curve Sorted= 0
DSS Export Volume Flow Curves= 0
DXF OffsetX= 0
DXF OffsetY= 0
DXF ScaleX= 1
DXF ScaleY= 10

--- LONG TRIBUTARY 1.p01 (plan) ---

Plan Title=Multiple Run
Short Identifier=Multiple
Geom File=g01
Flow File=f01
Subcritical Flow
K Sum by GR= 0
Std Step Tol= 0.01
Critical Tol= 0.01
Num of Std Step Trials= 20
Max Error Tol= 0.3
Flow Tol Ratio= 0.001
Split Flow NTrial= 30
Split Flow Tol= 0.02
Split Flow Ratio= 0.02
Log Output Level= 0
Friction Slope Method= 1
Unsteady Friction Slope Method= 2
Unsteady Bridges Friction Slope Method= 1
Parabolic Critical Depth
Global Vel Dist=  1 , 1 , 1
Global Log Level= 0
CheckData=True
Encroach Param= -1, 0, 0, 0
BEGIN DESCRIPTION:
Multiple Run
END DESCRIPTION:

--- LONG TRIBUTARY 1.f01 (steady flow) ---

Flow Title=Multiple
Number of Profiles=7
Profile Names=10-year,25-year,50-year,1pct_min,100-year,1pct_plu,500-year
River Rch & RM= LONG TRIBUTARY 1,Reach-1,2332
     574     923    1236     803    1603    3198    2662
Boundary for River Rch & Prof#=LONG TRIBUTARY 1,Reach-1,1
Up Type=0
Dn Type=3
Dn Slope=0.005
Boundary for River Rch & Prof#=LONG TRIBUTARY 1,Reach-1,2
Up Type=0
Dn Type=3
Dn Slope=0.005
Boundary for River Rch & Prof#=LONG TRIBUTARY 1,Reach-1,3
Up Type=0
Dn Type=3
Dn Slope=0.005
Boundary for River Rch & Prof#=LONG TRIBUTARY 1,Reach-1,4
Up Type=0
Dn Type=3
Dn Slope=0.005
Boundary for River Rch & Prof#=LONG TRIBUTARY 1,Reach-1,5
Up Type=0
Dn Type=3
Dn Slope=0.005
Boundary for River Rch & Prof#=LONG TRIBUTARY 1,Reach-1,6
Up Type=0
Dn Type=3
Dn Slope=0.005
Boundary for River Rch & Prof#=LONG TRIBUTARY 1,Reach-1,7
Up Type=0
Dn Type=3
Dn Slope=0.005

--- LONG TRIBUTARY 1.g01 (geometry) ---

Geom Title=Existing Conditions
Program Version=4.10

River Reach=LONG TRIBUTARY 1,Reach-1
Reach XY= 30
        2268275.       13774175.      2268322.68     13774219.28
      2268381.45     13774232.91      2268419.65      13774272.3
      2268426.05      13774464.9      2268438.36     13774489.14
       2268471.3     13774517.35      2268526.62     13774479.44
      2268577.18     13774468.95      2268626.72     13774429.16
       2268677.2     13774418.92      2268726.72     13774379.16
      2268777.18     13774368.88      2268826.58     13774328.67
       2268904.9      13774324.9      2268927.31     13774330.68
      2268980.94     13774372.74       2269164.5     13774376.22
      2269230.98     13774422.64       2269323.4     13774428.85
      2269380.98     13774472.64       2269473.5     13774478.61
      2269630.86     13774622.95       2269777.7     13774619.65
      2269819.25     13774577.55      2269838.49     13774511.31
      2269872.46     13774479.96      2269899.92     13774474.37
       2269938.2     13774488.09        2270075.       13774625.

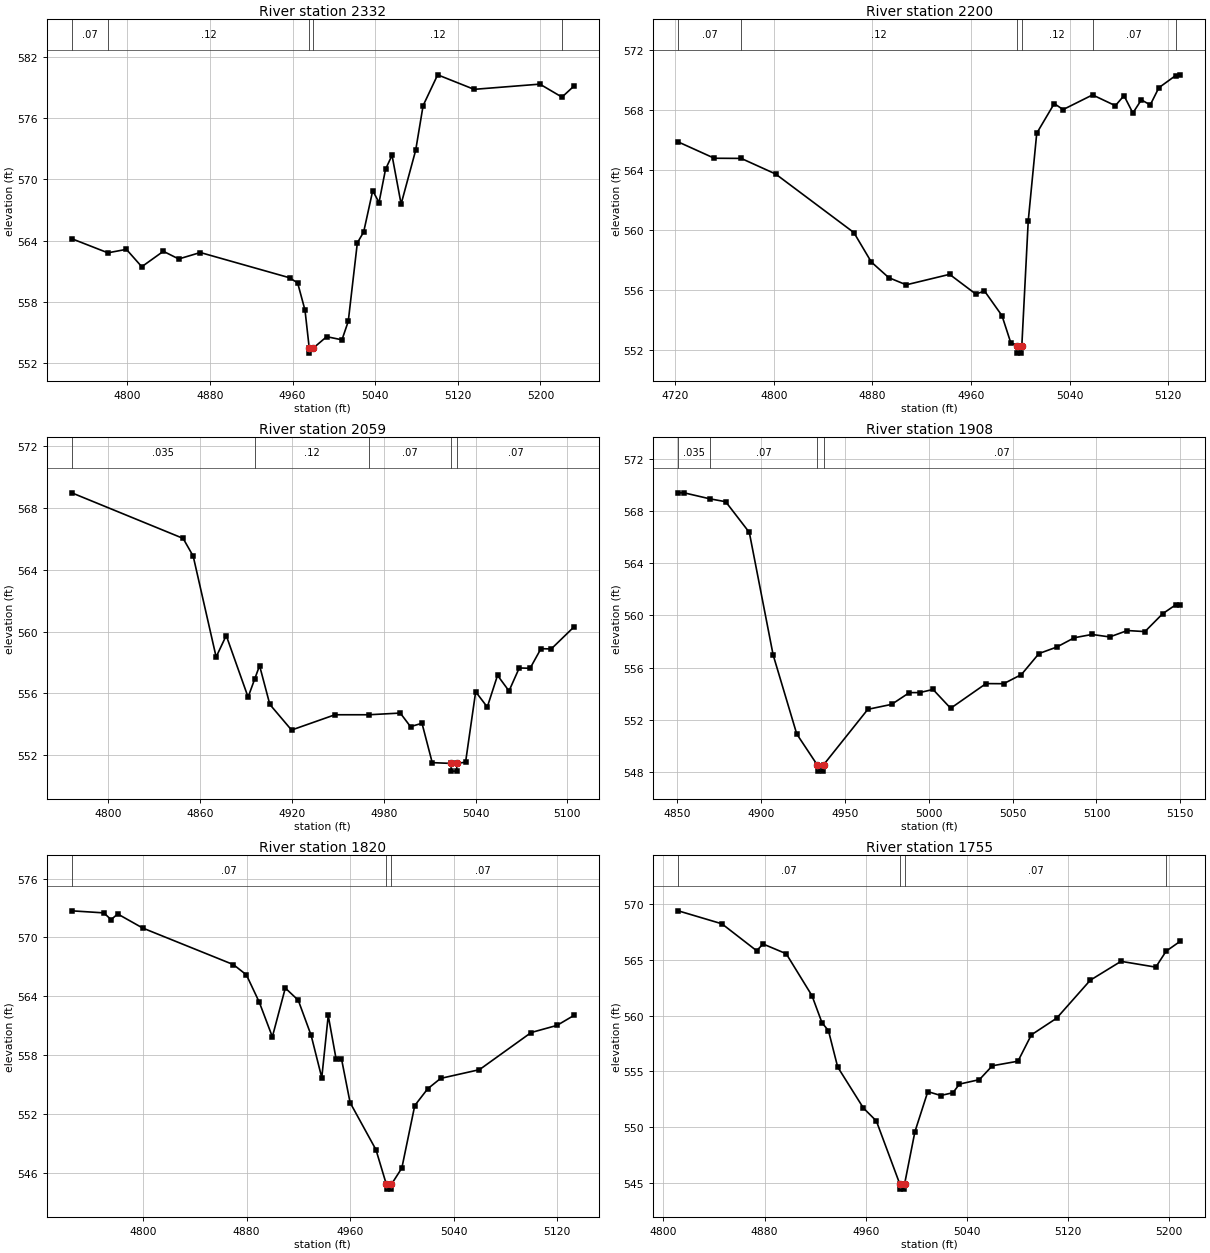
Type RM Length L Ch R = 1 ,2332    ,132,132,132
BEGIN DESCRIPTION:
A19847
END DESCRIPTION:
XS GIS Cut Line= 3
      2268150.96       13774405.      2268327.51     13774149.63
      2268450.26     13774023.73
#Sta/Elev= 30
  4746.1  564.18  4781.1   562.8    4799  563.14  4813.9  561.44  4834.8  562.95
  4849.7   562.2  4870.6  562.83  4957.1  560.36  4964.9  559.85    4972  557.19
  4976.1  553.49  4976.3  552.99  4980.1  553.49    4993   554.6  5007.8  554.29
  5013.9   556.1  5022.7  563.78  5028.8  564.83  5037.6  568.88  5043.7  567.72
    5050  570.97  5056.3  572.34  5065.1  567.57  5079.2  572.83  5086.4   577.2
  5100.5  580.21  5135.8  578.79  5199.5   579.3  5220.9  578.03  5232.4   579.1
#Mann= 5 ,-1 , 0
  4746.1     .07       0  4781.1     .12       0  4976.1     .05       0
  4980.1     .12       0  5220.9     .07       0
Bank Sta=4976.1,4980.1
XS Rating Curve= 0 ,0
Exp/Cntr=0.3,0.1

Type RM Length L Ch R = 1 ,2200    ,141,141,141
BEGIN DESCRIPTION:
A19846
END DESCRIPTION:
XS GIS Cut Line= 2
      2268207.67     13774449.18      2268500.43     13774165.87
#Sta/Elev= 30
  4722.4  565.89  4751.7   564.8  4773.5  564.79  4801.4  563.75  4864.9  559.84
  4879.1  557.87  4893.2  556.83  4907.4  556.35  4942.6  557.05  4963.9  555.73
  4970.9  555.94  4985.1  554.29  4992.2  552.49  4997.2  552.29  4997.4  551.79
  5000.9  551.79  5001.2  552.29  5006.4  560.62  5013.3  566.47  5027.5  568.45
  5034.7  568.05  5058.6  569.03  5077.1  568.31  5084.1  568.98  5091.3  567.82
  5098.2   568.7  5105.4  568.36  5112.4  569.51    5126  570.32  5129.8  570.37
#Mann= 6 ,-1 , 0
  4722.4     .07       0  4773.5     .12       0  4997.2     .05       0
  5001.2     .12       0  5058.6     .07       0    5126     .12       0
Bank Sta=4997.2,5001.2
XS Rating Curve= 0 ,0
Exp/Cntr=0.3,0.1

Type RM Length L Ch R = 1 ,2059    ,151,151,151
BEGIN DESCRIPTION:
A19845
END DESCRIPTION:
XS GIS Cut Line= 2
      2268276.44     13774559.49      2268493.97      13774313.6
#Sta/Elev= 30
    4776  568.98  4848.8  566.03  4855.4  564.88  4870.4  558.35    4877  559.74
  4891.3  555.75  4895.6  556.92  4898.8  557.79  4905.5  555.28  4919.7  553.62
  4948.1  554.61  4970.3  554.61  4990.8  554.72  4997.5  553.84    5005  554.06
  5011.7  551.51  5023.9  551.46  5024.2  550.96  5027.7  550.96  5027.9  551.46
  5033.5  551.54  5040.1   556.1  5047.7  555.11  5054.4  557.16  5061.9  556.15
  5068.6  557.64  5075.7  557.62  5082.8  558.89  5089.5  558.87  5104.3  560.29
#Mann= 5 ,-1 , 0
    4776    .035       0  4895.6     .12       0  4970.3     .07       0
  5023.9     .05       0  5027.9     .07       0
Bank Sta=5023.9,5027.9
XS Rating Curve= 0 ,0
Exp/Cntr=0.3,0.1

Type RM Length L Ch R = 1 ,1908    ,88,88,88
BEGIN DESCRIPTION:
LONG TRIBUTARY 1 4.0
END DESCRIPTION:
XS GIS Cut Line= 3
        2268375.       13774625.        2268475.       13774525.
      2268524.99     13774375.03
#Sta/Elev= 30
  4850.5  569.38    4854  569.38  4869.4  568.92  4878.8   568.7  4892.9  566.35
  4907.1  556.98  4921.2  550.92  4933.3  548.58  4933.6  548.08  4937.1  548.08
  4937.3  548.58  4963.6  552.81  4977.8  553.19  4988.4  554.09  4994.5  554.09
  5002.5  554.33    5013  552.89  5034.1  554.78  5044.6  554.77  5055.2  555.47
  5065.7  557.08  5076.2  557.57  5086.8  558.29  5097.3  558.54  5107.9  558.35
  5118.4  558.84  5128.9  558.76  5139.5  560.13  5147.4  560.82    5150  560.82
#Mann= 4 ,-1 , 0
  4850.5    .035       0  4869.4     .07       0  4933.3     .05       0
  4937.3     .07       0
Bank Sta=4933.3,4937.3
XS Rating Curve= 0 ,0
Exp/Cntr=0.3,0.1

Type RM Length L Ch R = 1 ,1820    ,65,65,65
BEGIN DESCRIPTION:
A19844
END DESCRIPTION:
XS GIS Cut Line= 3
      2268538.12     13774729.77      2268550.73     13774521.67
      2268553.88     13774341.98
#Sta/Elev= 30
  4744.8  572.71  4769.6   572.5  4775.2  571.81  4780.3  572.39  4799.7  570.95
  4869.8  567.22  4879.8  566.18  4889.8  563.38  4899.9  559.85  4909.9  564.83
  4919.9  563.59  4929.9  559.99  4938.1  555.68  4943.1  562.03  4949.1  557.64
  4953.3  557.64    4960  553.14    4980  548.33    4988  544.81  4988.2  544.31
  4991.7  544.31    4992  544.81    5000  546.46    5010  552.84    5020  554.55
    5030  555.61    5060   556.5    5100  560.29    5120  561.02    5133  562.03
#Mann= 3 ,-1 , 0
  4744.8     .07       0    4988     .05       0    4992     .07       0
Bank Sta=4988,4992
XS Rating Curve= 0 ,0
Exp/Cntr=0.3,0.1

Type RM Length L Ch R = 1 ,1755    ,117,117,117
BEGIN DESCRIPTION:
A19843
END DESCRIPTION:
XS GIS Cut Line= 2
      2268642.16     13774628.84       2268566.7     13774238.97
#Sta/Elev= 30
  4811.7  569.38  4846.2  568.22  4873.7  565.81  4878.8  566.41  4897.1  565.54
  4917.5  561.78  4925.4  559.36  4930.5  558.66  4937.8   555.4  4958.2  551.72
  4968.4  550.57  4986.8  544.97    4987  544.47  4990.5  544.47  4990.8  544.97
  4998.9  549.61  5009.1   553.2  5019.3  552.85    5029   553.1  5034.1  553.87
  5049.9  554.27  5060.1  555.51  5080.4  555.92    5091  558.28    5111  559.77
  5137.6  563.17  5161.9  564.86  5189.4  564.34  5197.6  565.77  5208.8  566.66
#Mann= 4 ,-1 , 0
  4811.7     .07       0  4986.8     .05       0  4990.8     .07       0
  5197.6     .12       0
Bank Sta=4986.8,4990.8
XS Rating Curve= 0 ,0
Exp/Cntr=0.3,0.1

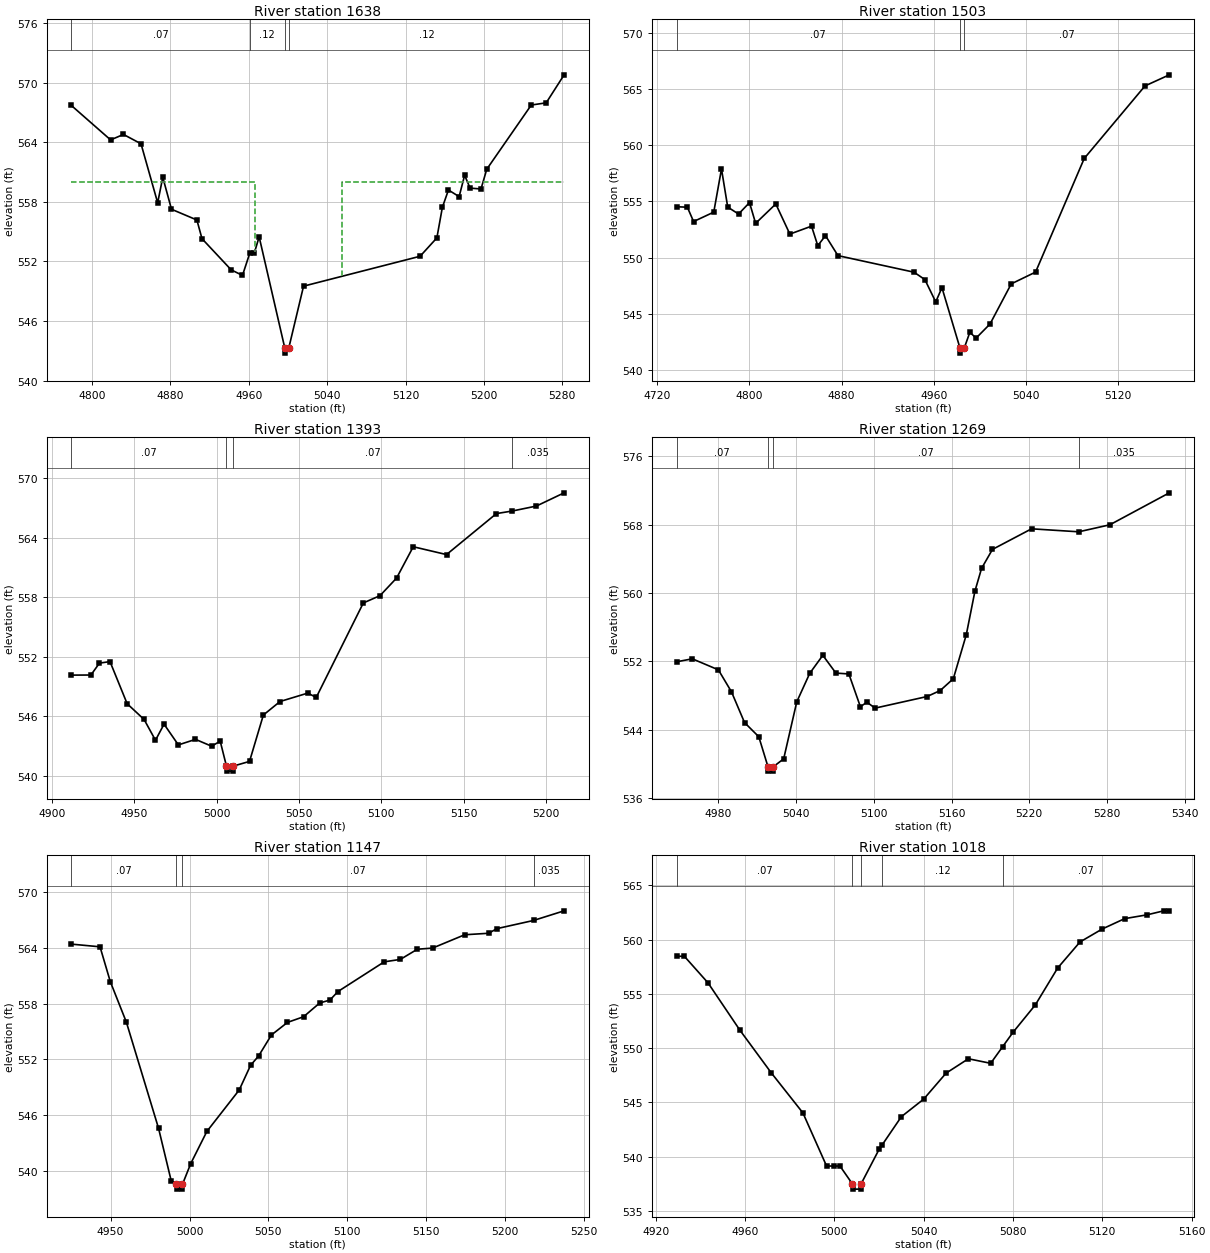
Type RM Length L Ch R = 1 ,1638    ,135,135,135
BEGIN DESCRIPTION:
A19842
END DESCRIPTION:
XS GIS Cut Line= 3
      2268676.84     13774603.69      2268724.14     13774427.08
      2268586.13     13774138.52
#Sta/Elev= 30
  4779.1   567.7  4819.2  564.23  4832.3  564.78  4850.2  563.84  4867.2   557.9
  4872.4  560.47  4881.3  557.25  4907.2  556.17  4912.4  554.29  4942.1  551.16
  4953.7  550.59  4961.3  552.88  4965.9  552.88  4970.7  554.48  4996.9  543.27
  4997.1  542.77  5000.9  543.27    5016  549.51  5134.9  552.52    5152  554.37
  5157.6  557.44  5163.8  559.19  5174.7  558.52  5180.3  560.67  5185.9  559.38
    5197  559.29  5202.9  561.28  5248.3  567.74  5263.5  567.96  5281.8  570.78
#Mann= 4 ,-1 , 0
  4779.1     .07       0  4961.3     .12       0  4996.9     .05       0
  5000.9     .12       0
#XS Ineff= 2 , 0
       0    4966     560    5055       0     560
Permanent Ineff=
       F       F
Bank Sta=4996.9,5000.9
XS Rating Curve= 0 ,0
Exp/Cntr=0.3,0.1

Type RM Length L Ch R = 1 ,1503    ,110,110,110
BEGIN DESCRIPTION:
LONG TRIBUTARY 1 3.0
END DESCRIPTION:
XS GIS Cut Line= 3
      2268725.01     13774574.98        2268825.       13774325.
      2268774.98     13774174.95
#Sta/Elev= 30
  4736.8  554.53  4746.2  554.49  4751.6  553.21  4769.1  554.05  4775.8   557.9
  4781.2   554.5  4790.6  553.88  4800.1   554.9  4805.4  553.05  4822.9  554.78
  4835.1  552.09  4853.9   552.8  4859.3  551.06    4866  551.95  4876.8  550.17
  4942.8  548.69  4952.2  548.03  4961.6  546.04    4967  547.31  4982.5  541.97
  4982.7  541.47  4986.5  541.97  4991.2  543.33  4996.6  542.81  5008.7  544.07
  5027.1  547.65  5048.2   548.7  5090.4  558.84  5143.1  565.31  5164.2   566.3
#Mann= 3 ,-1 , 0
  4736.8     .07       0  4982.5     .05       0  4986.5     .07       0
Bank Sta=4982.5,4986.5
XS Rating Curve= 0 ,0
Exp/Cntr=0.3,0.1

Type RM Length L Ch R = 1 ,1393    ,124,124,124
BEGIN DESCRIPTION:
A19841
END DESCRIPTION:
XS GIS Cut Line= 3
      2268954.29     13774417.59      2268925.92     13774316.73
      2268897.54     13774124.39
#Sta/Elev= 30
  4911.8  550.16  4923.7  550.17  4928.9  551.37  4935.3  551.52  4945.7  547.28
    4956  545.69  4962.9   543.6  4968.1  545.22  4976.8  543.13  4987.2  543.69
    4997     543  5002.2  543.51    5006  540.99  5006.2  540.49  5009.7  540.49
    5010  540.99    5020  541.47  5028.4  546.14  5038.5   547.5  5055.4  548.35
  5060.5  547.91  5089.1  557.43  5099.2  558.16  5109.3  559.94  5119.4  563.09
  5139.6   562.3  5169.9  566.43  5179.6  566.69  5194.2  567.19    5211  568.52
#Mann= 4 ,-1 , 0
  4911.8     .07       0    5006     .05       0    5010     .07       0
  5179.6    .035       0
Bank Sta=5006,5010
XS Rating Curve= 0 ,0
Exp/Cntr=0.3,0.1

Type RM Length L Ch R = 1 ,1269    ,122,122,122
BEGIN DESCRIPTION:
A19840
END DESCRIPTION:
XS GIS Cut Line= 2
      2269033.12     13774427.13      2269077.19     13774049.39
#Sta/Elev= 30
  4947.8  551.94    4960  552.29  4980.1     551  4990.2  548.43  5000.3  544.83
  5011.3  543.17  5018.4  539.65  5018.7  539.15  5022.2  539.15  5022.4  539.65
  5030.5  540.59  5040.6  547.26  5050.6  550.59  5060.7   552.7  5070.8  550.62
  5080.8  550.52  5089.7  546.68  5094.7  547.22    5101  546.52  5141.2  547.88
  5151.3  548.58  5161.4  549.96  5171.4   555.1  5178.1  560.22  5183.2  562.87
  5191.6  565.09  5221.8   567.5  5258.2  567.15  5282.2  567.97  5328.1  571.71
#Mann= 4 ,-1 , 0
  4947.8     .07       0  5018.4     .05       0  5022.4     .07       0
  5258.2    .035       0
Bank Sta=5018.4,5022.4
XS Rating Curve= 0 ,0
Exp/Cntr=0.3,0.1

Type RM Length L Ch R = 1 ,1147    ,129,129,129
BEGIN DESCRIPTION:
A19839
END DESCRIPTION:
XS GIS Cut Line= 2
      2269146.62     13774449.17      2269209.69      13774143.3
#Sta/Elev= 30
  4925.1  564.42  4943.3  564.13  4949.8  560.38    4960     556  4980.4  544.55
  4988.4   538.9  4991.5   538.5  4991.8     538  4995.3     538  4995.5   538.5
  5000.8  540.76    5011  544.22  5031.5  548.69  5038.7  551.35  5043.8  552.36
  5051.9  554.62  5062.1  555.98  5072.3  556.59  5082.5  558.07    5089  558.39
  5094.1  559.31  5123.4  562.51  5133.6  562.77  5144.4  563.87    5154  563.99
  5174.4  565.43  5189.6  565.59  5194.8  566.09    5218  566.97  5237.4  568.01
#Mann= 4 ,-1 , 0
  4925.1     .07       0  4991.5     .05       0  4995.5     .07       0
    5218    .035       0
Bank Sta=4991.5,4995.5
XS Rating Curve= 0 ,0
Exp/Cntr=0.3,0.1

Type RM Length L Ch R = 1 ,1018    ,119,119,119
BEGIN DESCRIPTION:
LONG TRIBUTARY 1 2.0
END DESCRIPTION:
XS GIS Cut Line= 3
      2269225.01     13774474.99        2269275.       13774425.
        2269275.       13774275.
#Sta/Elev= 30
  4929.3  558.47  4932.8  558.47  4943.4  556.02  4957.6  551.68  4971.7  547.73
  4985.9  544.03  4996.5  539.13    5000  539.13  5002.5  539.13    5008   537.5
  5008.2     537  5011.7     537    5012   537.5    5020  540.66  5021.5  541.11
    5030  543.68    5040   545.3    5050  547.69    5060  549.02    5070   548.6
  5075.3  550.12    5080  551.46    5090  553.99    5100  557.39    5110  559.79
    5120  560.99    5130  561.94    5140  562.29  5147.5  562.66    5150  562.66
#Mann= 5 ,-1 , 0
  4929.3     .07       0    5008     .05       0    5012     .07       0
  5021.5     .12       0  5075.3     .07       0
Bank Sta=5008,5012
XS Rating Curve= 0 ,0
Exp/Cntr=0.3,0.1

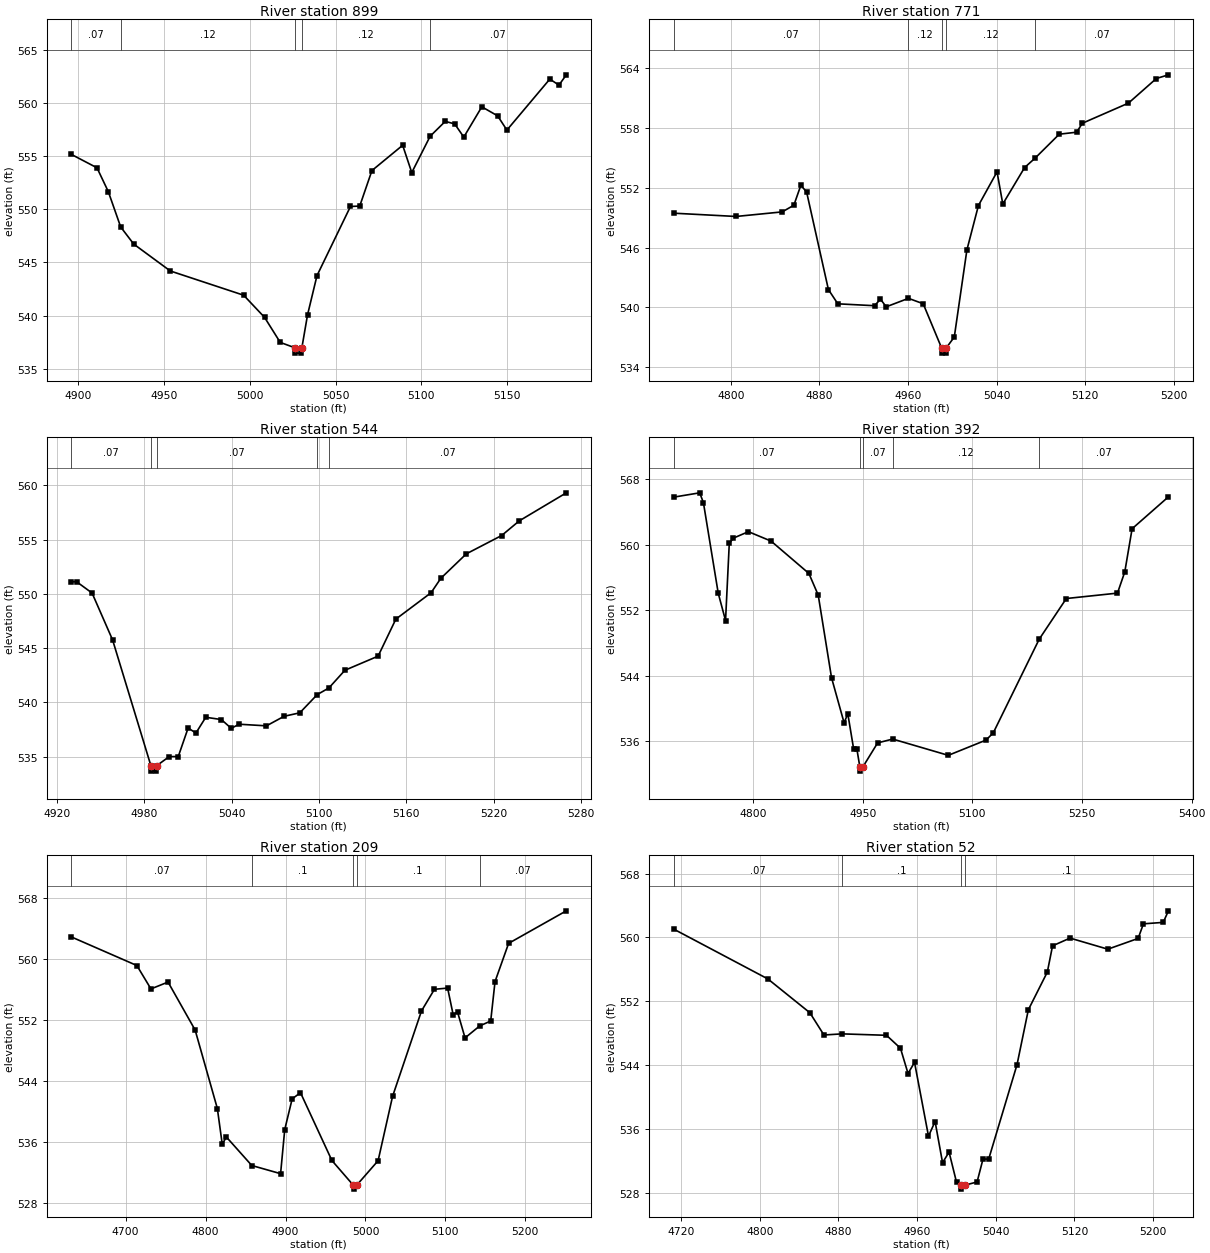
Type RM Length L Ch R = 1 ,899     ,128,128,128
BEGIN DESCRIPTION:
A19838
END DESCRIPTION:
XS GIS Cut Line= 2
      2269342.09       13774569.      2269442.59      13774298.9
#Sta/Elev= 30
  4896.2  555.16  4911.1   553.9  4917.7  551.65  4924.9  548.33  4932.5  546.72
  4953.8  544.19  4996.5  541.91  5008.7  539.82  5017.8  537.47  5026.4  536.96
  5026.6  536.46  5030.1  536.46  5030.4  536.96  5033.7  540.06  5039.2  543.75
  5058.7  550.26  5064.1   550.3  5071.2  553.64  5089.1  556.02  5094.4  553.45
  5105.1  556.87  5113.9  558.27  5119.4  558.03  5124.7  556.79  5135.2  559.64
  5144.4  558.79  5149.8  557.45  5174.8  562.25  5180.1  561.68  5184.4  562.65
#Mann= 5 ,-1 , 0
  4896.2     .07       0  4924.9     .12       0  5026.4     .05       0
  5030.4     .12       0  5105.1     .07       0
Bank Sta=5026.4,5030.4
XS Rating Curve= 0 ,0
Exp/Cntr=0.3,0.1

Type RM Length L Ch R = 1 ,771     ,227,227,227
BEGIN DESCRIPTION:
A19837
END DESCRIPTION:
XS GIS Cut Line= 2
      2269427.22     13774739.24      2269553.35      13774310.4
#Sta/Elev= 30
  4748.2  549.46  4804.7  549.13  4846.4  549.59  4856.9  550.26  4863.2  552.26
  4868.4  551.59  4888.1  541.79  4896.6  540.36  4929.8  540.17  4935.1  540.83
  4940.3  540.06  4960.4  540.91  4973.7  540.37  4990.4  535.91  4990.6  535.41
  4994.1  535.41  4994.4  535.91  5001.8  537.03  5013.2  545.78  5023.6  550.23
  5040.4  553.61  5045.6  550.38  5065.3  554.04    5075  555.01  5096.6  557.39
  5112.3  557.59  5117.5  558.49  5159.1  560.51  5184.3  562.98  5195.2  563.35
#Mann= 5 ,-1 , 0
  4748.2     .07       0  4960.4     .12       0  4990.4     .05       0
  4994.4     .12       0    5075     .07       0
Bank Sta=4990.4,4994.4
XS Rating Curve= 0 ,0
Exp/Cntr=0.3,0.1

Type RM Length L Ch R = 1 ,544     ,152,152,152
BEGIN DESCRIPTION:
LONG TRIBUTARY 1 1.0
END DESCRIPTION:
XS GIS Cut Line= 3
      2269624.98     13774675.02        2269675.       13774625.
        2269575.     13774374.99
#Sta/Elev= 30
    4930  551.11  4933.6  551.11  4944.2  550.07  4958.3  545.75  4984.6  534.17
  4984.8  533.67  4988.3  533.67  4988.6  534.17  4997.2  535.01  5003.4  535.01
  5010.2  537.65  5015.5  537.17  5022.3  538.63    5033  538.42  5039.8  537.61
  5045.2  537.99    5064  537.84  5076.1  538.72  5086.9  539.04  5098.9  540.72
  5106.9  541.33  5117.9  542.96  5140.7  544.26  5152.9  547.67  5177.1   550.1
  5183.8  551.43  5201.3  553.68  5225.6  555.37  5237.7  556.72    5270   559.3
#Mann= 5 ,-1 , 0
    4930     .07       0  4984.6     .05       0  4988.6     .07       0
  5098.9     .12       0  5106.9     .07       0
Bank Sta=4984.6,4988.6
XS Rating Curve= 0 ,0
Exp/Cntr=0.3,0.1

Type RM Length L Ch R = 1 ,392     ,183,183,183
BEGIN DESCRIPTION:
A19836
END DESCRIPTION:
XS GIS Cut Line= 4
       2269770.9     13774884.21      2269833.95     13774641.48
      2269780.35     13774505.91      2269774.05     13774225.35
#Sta/Elev= 30
    4691  565.82  4726.8  566.35  4731.9  565.16  4752.2  554.07  4762.2  550.74
  4767.3  560.16  4772.8  560.81  4793.5   561.6  4824.5  560.45  4876.2   556.5
    4889  553.85  4907.2  543.76  4924.4  538.24  4929.5  539.34  4937.4  535.08
  4941.8  535.08    4946  532.83  4946.2  532.33    4950  532.83  4970.3  535.78
  4990.9  536.25    5067  534.26  5118.5  536.12  5128.5     537  5191.4  548.46
  5228.5  553.43  5298.5  554.09  5308.5  556.69  5318.5  561.96  5368.2  565.86
#Mann= 5 ,-1 , 0
    4691     .07       0    4946     .05       0    4950     .07       0
  4990.9     .12       0  5191.4     .07       0
Bank Sta=4946,4950
XS Rating Curve= 0 ,0
Exp/Cntr=0.3,0.1

Type RM Length L Ch R = 1 ,209     ,157,157,157
BEGIN DESCRIPTION:
A19835
END DESCRIPTION:
XS GIS Cut Line= 3
      2269818.18     13774830.68      2269903.31     13774531.13
      2270025.69     13774248.72
#Sta/Elev= 30
  4632.1  562.92    4714  559.17  4731.6   556.1    4753     557  4786.9   550.7
  4814.7   540.4  4820.8  535.72    4826  536.66  4857.8  532.92  4893.8  531.85
    4899  537.64  4908.3  541.67  4918.7  542.48    4958  533.58  4984.9  530.32
  4985.2  529.82  4988.9  530.32  5015.8  533.55  5033.9  541.99  5070.1  553.21
  5086.3  556.05  5102.8  556.21  5109.7  552.72  5115.2  553.07  5124.6  549.67
  5142.9  551.24  5156.7  551.89  5162.1  557.06  5179.1  562.08  5251.3  566.35
#Mann= 5 ,-1 , 0
  4632.1     .07       0  4857.8      .1       0  4984.9     .05       0
  4988.9      .1       0  5142.9     .07       0
Bank Sta=4984.9,4988.9
XS Rating Curve= 0 ,0
Exp/Cntr=0.3,0.1

Type RM Length L Ch R = 1 ,52      ,0,0,0
BEGIN DESCRIPTION:
A19834
END DESCRIPTION:
XS GIS Cut Line= 3
      2269849.73      13774805.4       2270057.8     13774565.81
      2270120.28     13774390.86
#Sta/Elev= 30
  4712.4  561.05  4808.3  554.79    4851  550.55  4865.3  547.76  4883.9   547.9
  4928.9  547.72  4943.1   546.1  4950.8  542.93  4957.4  544.33  4971.6  535.07
  4978.3  536.91  4985.9  531.74  4992.5  533.08  5000.1  529.29  5004.8  528.93
    5005  528.43  5008.8  528.93    5021  529.33    5027   532.2  5032.8   532.2
  5061.6  544.04  5073.1  550.92  5092.4  555.65  5097.7  558.94  5115.5  559.91
  5153.9  558.52  5184.7  559.87  5190.1   561.7  5210.2  561.88  5215.5  563.33
#Mann= 4 ,-1 , 0
  4712.4     .07       0  4883.9      .1       0  5004.8     .05       0
  5008.8      .1       0
Bank Sta=5004.8,5008.8
XS Rating Curve= 0 ,0
Exp/Cntr=0.3,0.1

Chan Stop Cuts=-1
Use User Specified Reach Order=0
Composite Channel Slope=5