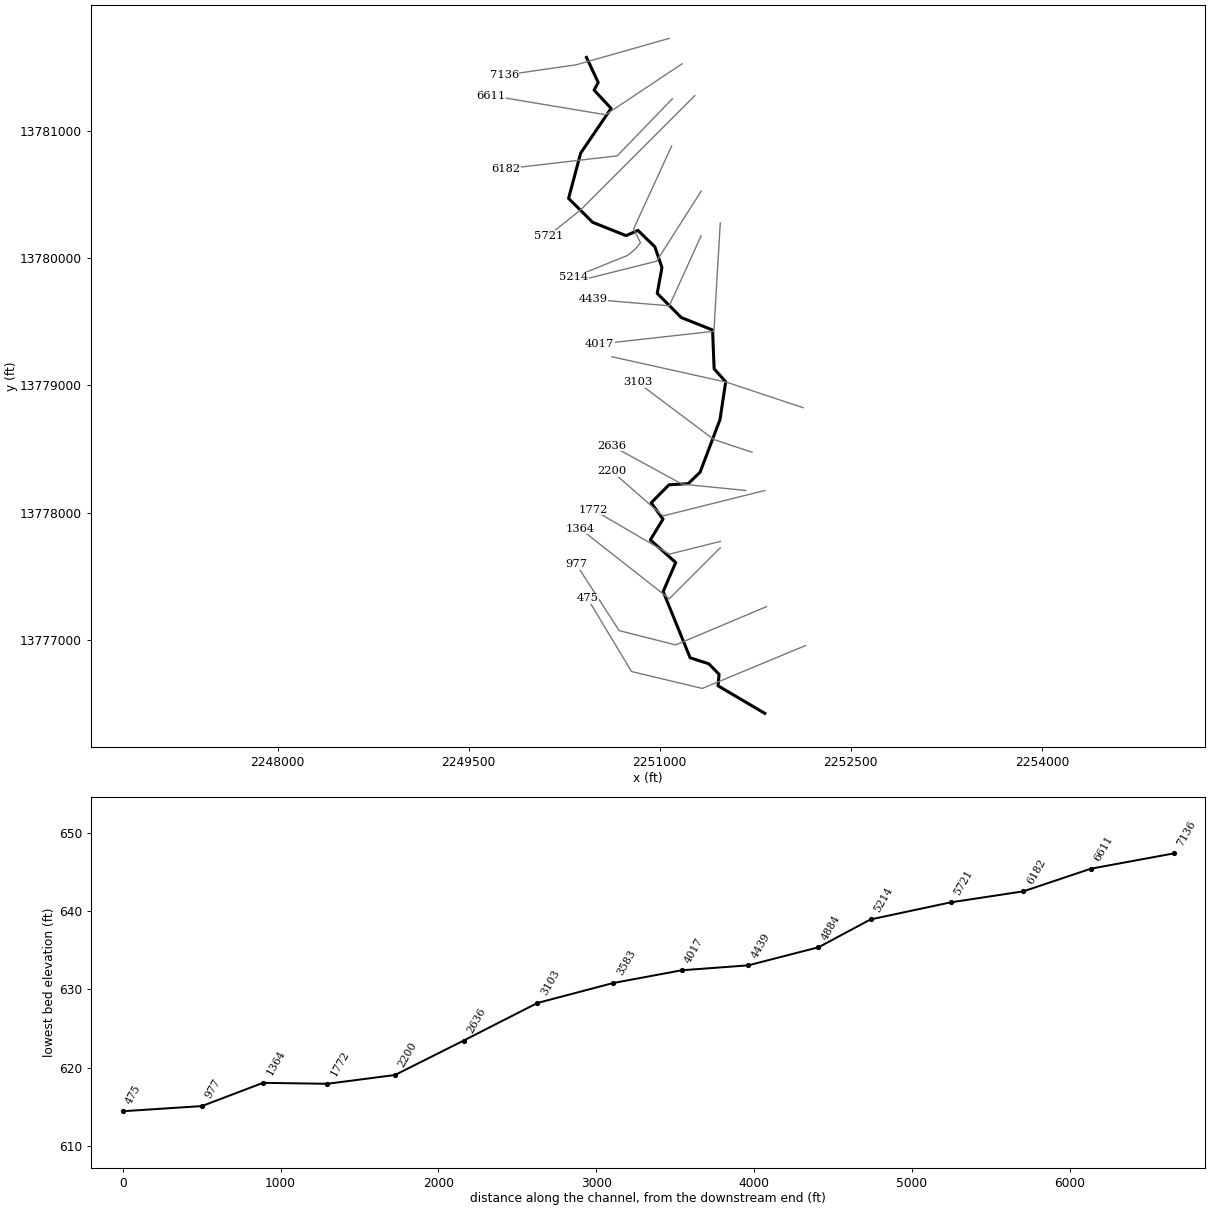
--- LONG TRIBUTARY 11.prj (project) ---

Proj Title=LONG TRIBUTARY 11 Base Level Engineering
Current Plan=p01
Default Exp/Contr=0.3,0.1
English Units
Geom File=g01
Flow File=f01
Plan File=p01
Y Axis Title=Elevation
X Axis Title(PF)=Main Channel Distance
X Axis Title(XS)=Station
BEGIN DESCRIPTION:
LONG TRIBUTARY 11
END DESCRIPTION:
DSS Export Rating Curves= 0
DSS Export Rating Curve Sorted= 0
DSS Export Volume Flow Curves= 0
DXF OffsetX= 0
DXF OffsetY= 0
DXF ScaleX= 1
DXF ScaleY= 10

--- LONG TRIBUTARY 11.p01 (plan) ---

Plan Title=Multiple Run
Short Identifier=Multiple
Geom File=g01
Flow File=f01
Subcritical Flow
K Sum by GR= 0
Std Step Tol= 0.01
Critical Tol= 0.01
Num of Std Step Trials= 20
Max Error Tol= 0.3
Flow Tol Ratio= 0.001
Split Flow NTrial= 30
Split Flow Tol= 0.02
Split Flow Ratio= 0.02
Log Output Level= 0
Friction Slope Method= 1
Unsteady Friction Slope Method= 2
Unsteady Bridges Friction Slope Method= 1
Parabolic Critical Depth
Global Vel Dist=  1 , 1 , 1
Global Log Level= 0
CheckData=True
Encroach Param= -1, 0, 0, 0
BEGIN DESCRIPTION:
Multiple Run
END DESCRIPTION:

--- LONG TRIBUTARY 11.f01 (steady flow) ---

Flow Title=Multiple
Number of Profiles=7
Profile Names=10-year,25-year,50-year,1pct_min,100-year,1pct_plu,500-year
River Rch & RM= LONG TRIBUTARY 1,Reach-1,7136
     471     740     976     623    1244    2482    1999
River Rch & RM= LONG TRIBUTARY 1,Reach-1,3583
     662    1063    1422     920    1836    3663    3029
Boundary for River Rch & Prof#=LONG TRIBUTARY 1,Reach-1,1
Up Type=0
Dn Type=3
Dn Slope=0.005
Boundary for River Rch & Prof#=LONG TRIBUTARY 1,Reach-1,2
Up Type=0
Dn Type=3
Dn Slope=0.005
Boundary for River Rch & Prof#=LONG TRIBUTARY 1,Reach-1,3
Up Type=0
Dn Type=3
Dn Slope=0.005
Boundary for River Rch & Prof#=LONG TRIBUTARY 1,Reach-1,4
Up Type=0
Dn Type=3
Dn Slope=0.005
Boundary for River Rch & Prof#=LONG TRIBUTARY 1,Reach-1,5
Up Type=0
Dn Type=3
Dn Slope=0.005
Boundary for River Rch & Prof#=LONG TRIBUTARY 1,Reach-1,6
Up Type=0
Dn Type=3
Dn Slope=0.005
Boundary for River Rch & Prof#=LONG TRIBUTARY 1,Reach-1,7
Up Type=0
Dn Type=3
Dn Slope=0.005

--- LONG TRIBUTARY 11.g01 (geometry) ---

Geom Title=Existing Conditions

River Reach=LONG TRIBUTARY 1,Reach-1
Reach XY= 30
      2250425.00     13781575.00      2250516.72     13781378.22
      2250484.30     13781318.33      2250617.93     13781175.00
      2250378.83     13780823.42      2250284.13     13780468.26
      2250472.70     13780280.83      2250735.71     13780175.82
      2250828.41     13780217.18      2250961.60     13780088.31
      2251017.22     13779924.90      2250980.11     13779722.71
      2251168.83     13779532.86      2251414.66     13779435.12
      2251426.89     13779130.78      2251517.77     13779028.45
      2251472.74     13778730.94      2251316.87     13778318.92
      2251223.54     13778228.54      2251072.55     13778219.53
      2250932.60     13778078.34      2251025.58     13777950.00
      2250926.13     13777787.03      2251125.05     13777609.66
      2251026.82     13777381.12      2251238.45     13776861.37
      2251384.83     13776814.48      2251465.70     13776731.68
      2251457.47     13776641.65      2251825.00     13776425.00

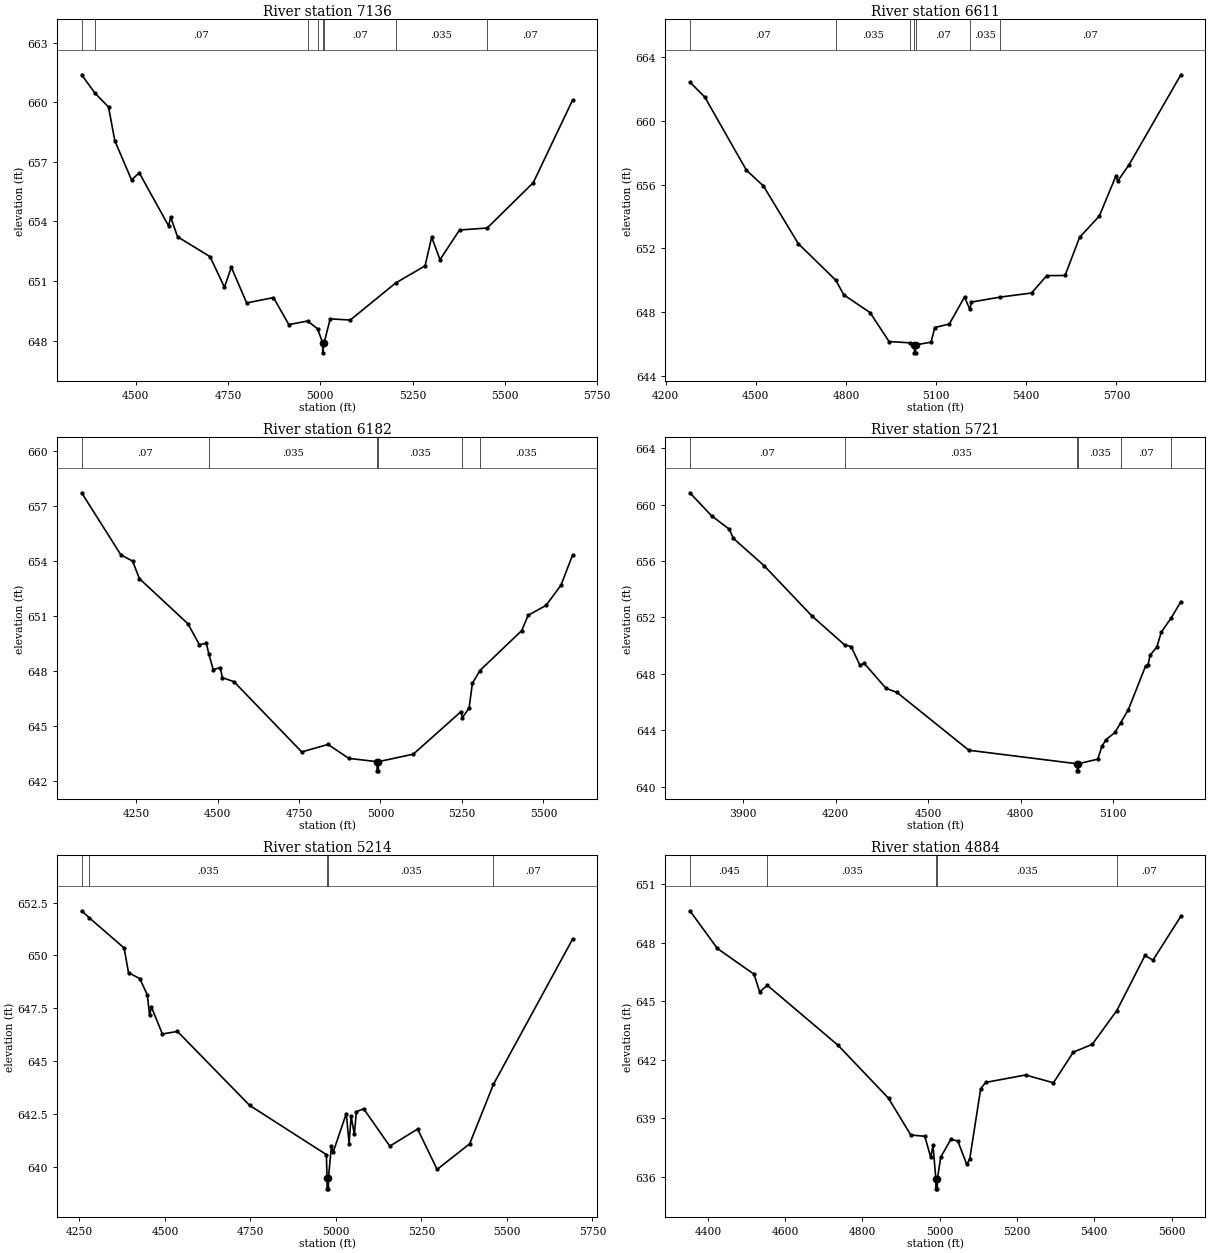
Type RM Length L Ch R = 1,7136,525,525,525
BEGIN DESCRIPTION:
LONG TRIBUTARY 11 13.0
END DESCRIPTION:
XS GIS Cut Line= 3
      2251075.01     13781725.00      2250344.84     13781517.38
      2249779.40     13781435.87
#Sta/Elev= 30
  4353.3  661.38  4389.2  660.46  4426.1  659.76  4443.2  658.06  4488.5  656.09
  4509.3  656.45  4589.1  653.77  4594.3  654.23  4613.2  653.23  4701.1  652.23
  4740.2  650.69  4758.8  651.70  4800.4  649.90  4873.1  650.17  4914.7  648.81
  4965.3  648.99  4992.6  648.60  5006.3  647.89  5006.5  647.39  5010.3  647.89
  5026.8  649.10  5081.1  649.04  5203.9  650.90  5284.0  651.77  5301.7  653.21
  5324.4  652.08  5377.2  653.57  5452.1  653.67  5577.0  655.95  5683.7  660.11
#Mann=8,-1,0
  4353.3    0.05       0  4389.2    0.07       0  4965.3   0.035       0
  4992.6    0.07       0  5006.3    0.05       0  5010.3    0.07       0
  5203.9   0.035       0  5452.1    0.07       0
Bank Sta=5006.3,5010.3
Exp/Cntr=0.3,0.1

Type RM Length L Ch R = 1,6611,429,429,429
BEGIN DESCRIPTION:
LONG TRIBUTARY 11 12.0
END DESCRIPTION:
XS GIS Cut Line= 3
      2251175.03     13781525.02      2250575.00     13781125.00
      2249674.96     13781275.01
#Sta/Elev= 30
  4280.8  662.45  4330.4  661.51  4468.6  656.92  4525.7  655.92  4641.4  652.30
  4766.3  650.00  4793.1  649.08  4880.3  647.97  4943.4  646.15  5011.9  646.07
  5027.8  645.94  5028.1  645.44  5031.6  645.44  5031.8  645.94  5083.1  646.11
  5095.7  647.03  5143.9  647.25  5194.6  648.95  5212.2  648.17  5217.4  648.63
  5312.5  648.94  5417.6  649.20  5468.3  650.29  5529.1  650.30  5577.3  652.69
  5643.2  654.04  5698.9  656.58  5704.0  656.22  5742.0  657.26  5914.4  662.91
#Mann=7,-1,0
  4280.8    0.07       0  4766.3   0.035       0  5011.9    0.07       0
  5027.8   0.035       0  5031.8    0.07       0  5212.2   0.035       0
  5312.5    0.07       0
Bank Sta=5027.8,5031.8
Exp/Cntr=0.3,0.1

Type RM Length L Ch R = 1,6182,461,461,461
BEGIN DESCRIPTION:
A19850
END DESCRIPTION:
XS GIS Cut Line= 3
      2251099.55     13781251.18      2250666.10     13780802.44
      2249789.51     13780700.51
#Sta/Elev= 30
  4083.1  657.70  4203.7  654.31  4239.2  653.98  4260.3  653.02  4409.0  650.56
  4444.3  649.42  4465.6  649.49  4473.4  648.91  4486.7  648.06  4508.1  648.17
  4515.0  647.62  4550.5  647.40  4758.4  643.57  4839.0  643.98  4902.8  643.22
  4989.4  643.04  4989.7  642.54  4993.2  642.54  4993.4  643.04  5100.7  643.45
  5247.1  645.77  5251.2  645.43  5271.9  645.97  5281.9  647.31  5305.1  648.01
  5433.0  650.18  5453.1  651.02  5507.9  651.56  5553.8  652.66  5589.5  654.31
#Mann=6,-1,0
  4083.1    0.07       0  4473.4   0.035       0  4989.4   0.035       0
  4993.4   0.035       0  5251.2    0.07       0  5305.1   0.035       0
Bank Sta=4989.4,4993.4
Exp/Cntr=0.3,0.1

Type RM Length L Ch R = 1,5721,507,507,507
BEGIN DESCRIPTION:
LONG TRIBUTARY 11 11.0
END DESCRIPTION:
XS GIS Cut Line= 3
      2251274.97     13781274.97      2250375.00     13780375.00
      2250125.00     13780175.00
#Sta/Elev= 30
  3727.2  660.84  3797.9  659.20  3854.4  658.27  3868.6  657.60  3967.6  655.68
  4123.1  652.11  4229.0  650.06  4250.4  649.94  4278.7  648.62  4292.8  648.75
  4363.5  646.98  4398.9  646.69  4632.2  642.59  4983.8  641.63  4984.1  641.13
  4987.6  641.13  4987.8  641.63  5050.4  641.96  5064.0  642.87  5077.6  643.35
  5106.4  643.85  5124.8  644.54  5149.6  645.46  5205.6  648.56  5213.6  648.64
  5220.1  649.32  5242.5  649.92  5256.1  650.94  5289.2  651.99  5320.1  653.12
#Mann=6,-1,0
  3727.2    0.07       0  4229.0   0.035       0  4983.8   0.035       0
  4987.8   0.035       0  5124.8    0.07       0  5289.2   0.035       0
Bank Sta=4983.8,4987.8
Exp/Cntr=0.3,0.1

Type RM Length L Ch R = 1,5214,330,330,330
BEGIN DESCRIPTION:
LONG TRIBUTARY 11 10.0
END DESCRIPTION:
XS GIS Cut Line= 6
      2251093.25     13780879.55      2250794.62     13780228.47
      2250848.44     13780120.83      2250806.77     13780068.75
      2250746.01     13780020.14      2250325.90     13779850.01
#Sta/Elev= 30
  4256.5  652.11  4279.3  651.77  4380.6  650.35  4393.5  649.18  4426.5  648.90
  4448.5  648.13  4455.1  647.17  4460.6  647.55  4492.5  646.28  4536.6  646.40
  4747.6  642.90  4972.0  640.57  4974.0  639.45  4974.3  638.95  4977.8  638.95
  4978.0  639.45  4986.8  640.98  4992.0  640.69  5030.2  642.51  5038.5  641.09
  5044.4  642.38  5053.8  641.53  5059.7  642.60  5080.9  642.74  5157.5  640.97
  5238.7  641.78  5295.8  639.87  5390.9  641.08  5460.3  643.89  5692.0  650.77
#Mann=5,-1,0
  4256.5    0.07       0  4279.3   0.035       0  4974.0   0.035       0
  4978.0   0.035       0  5460.3    0.07       0
Bank Sta=4974,4978
Exp/Cntr=0.3,0.1

Type RM Length L Ch R = 1,4884,445,445,445
BEGIN DESCRIPTION:
LONG TRIBUTARY 11 9.0
END DESCRIPTION:
XS GIS Cut Line= 3
      2251325.01     13780525.01      2250975.00     13779975.00
      2250375.00     13779825.00
#Sta/Elev= 30
  4353.6  649.63  4424.7  647.70  4519.6  646.38  4534.0  645.48  4554.1  645.81
  4737.1  642.74  4867.5  640.03  4925.1  638.15  4961.5  638.08  4976.8  637.00
  4982.7  637.62  4990.0  635.89  4990.2  635.39  4993.7  635.39  4994.0  635.89
  5002.6  637.01  5028.7  637.92  5046.8  637.84  5070.0  636.64  5077.7  636.92
  5106.0  640.51  5118.9  640.84  5222.0  641.22  5294.2  640.82  5345.7  642.39
  5394.7  642.79  5458.3  644.52  5531.2  647.34  5551.8  647.10  5624.0  649.35
#Mann=5,-1,0
  4353.6   0.045       0  4554.1   0.035       0  4990.0   0.035       0
  4994.0   0.035       0  5458.3    0.07       0
Bank Sta=4990,4994
Exp/Cntr=0.3,0.1

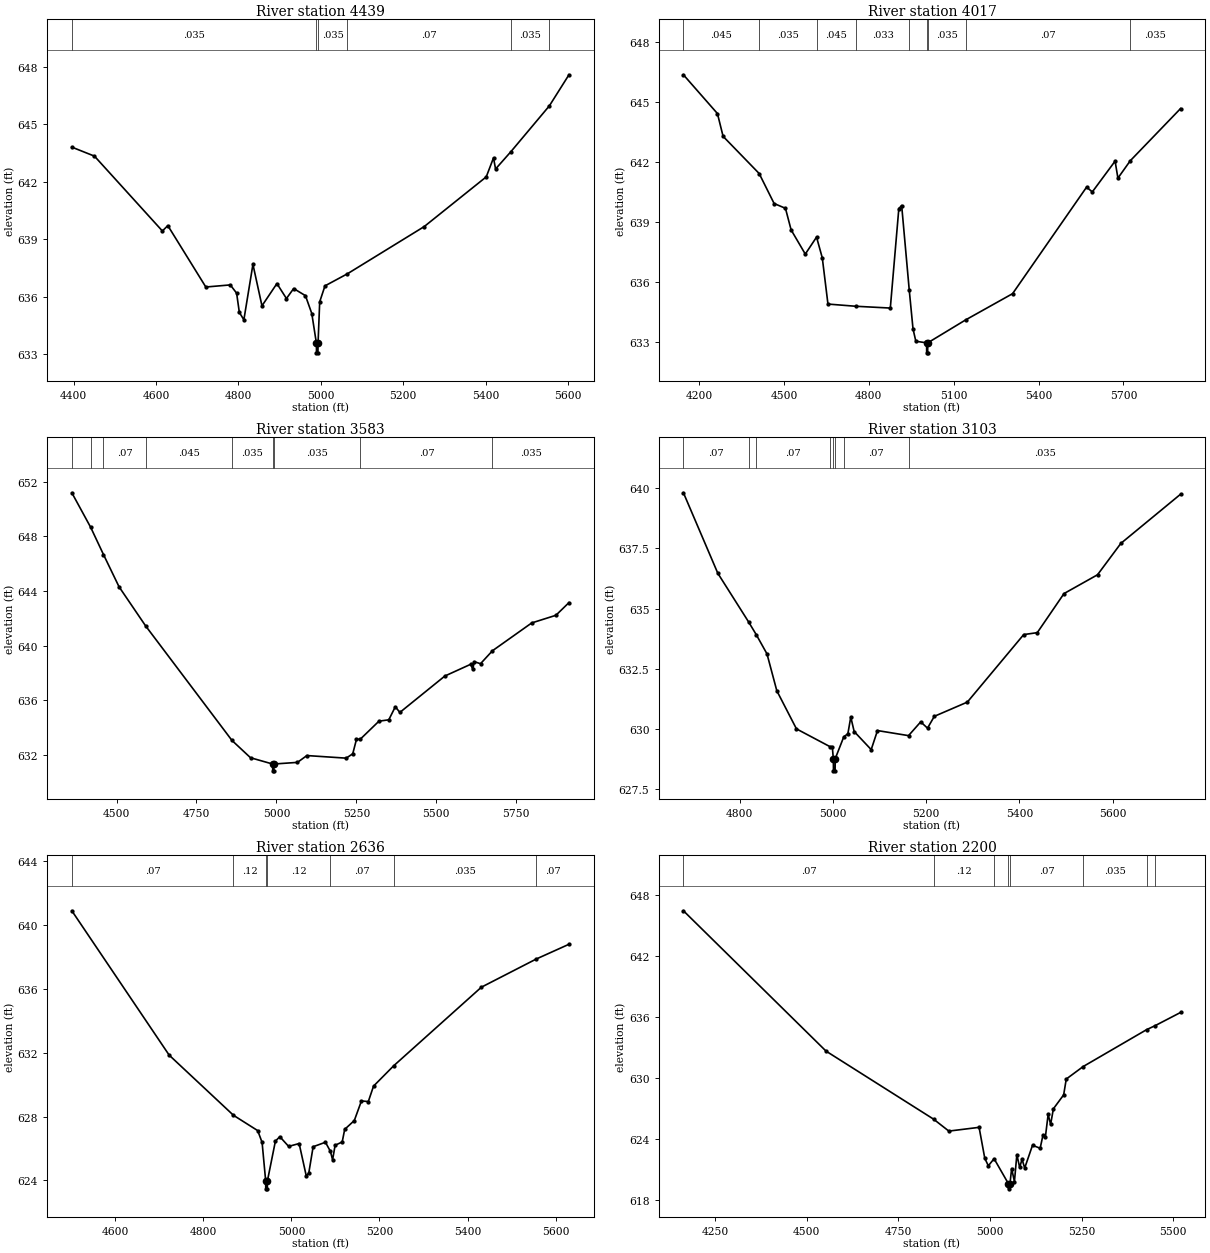
Type RM Length L Ch R = 1,4439,422,422,422
BEGIN DESCRIPTION:
LONG TRIBUTARY 11 8.0
END DESCRIPTION:
XS GIS Cut Line= 3
      2251325.00     13780174.99      2251075.00     13779625.00
      2250475.02     13779675.00
#Sta/Elev= 30
  4395.8  643.80  4450.7  643.33  4615.5  639.43  4628.7  639.71  4720.9  636.51
  4780.3  636.62  4795.6  636.19  4802.2  635.19  4813.2  634.80  4835.2  637.69
  4857.1  635.53  4893.4  636.69  4916.5  635.91  4934.0  636.43  4962.6  636.06
  4978.0  635.13  4989.2  633.58  4989.4  633.08  4992.9  633.08  4993.2  633.58
  4997.2  635.74  5010.0  636.57  5064.5  637.20  5250.8  639.66  5401.3  642.25
  5418.9  643.24  5423.9  642.66  5461.0  643.56  5554.4  645.95  5602.0  647.57
#Mann=6,-1,0
  4395.8   0.035       0  4989.2   0.035       0  4993.2   0.035       0
  5064.5    0.07       0  5461.0   0.035       0  5554.4    0.07       0
Bank Sta=4989.2,4993.2
Exp/Cntr=0.3,0.1

Type RM Length L Ch R = 1,4017,434,434,434
BEGIN DESCRIPTION:
LONG TRIBUTARY 11 7.0
END DESCRIPTION:
XS GIS Cut Line= 3
      2251475.00     13780274.96      2251425.00     13779425.00
      2250524.97     13779325.00
#Sta/Elev= 30
  4144.7  646.36  4264.9  644.42  4284.9  643.28  4412.4  641.42  4465.2  639.92
  4505.3  639.68  4525.3  638.60  4575.4  637.39  4615.2  638.24  4635.5  637.20
  4655.5  634.89  4753.8  634.78  4875.9  634.69  4906.0  639.67  4916.0  639.82
  4942.8  635.59  4956.1  633.65  4966.1  633.03  5004.2  632.95  5004.4  632.45
  5007.9  632.45  5008.2  632.95  5142.4  634.10  5308.0  635.41  5569.6  640.74
  5589.8  640.50  5670.3  642.04  5680.3  641.19  5724.0  642.06  5901.7  644.67
#Mann=9,-1,0
  4144.7   0.045       0  4412.4   0.035       0  4615.2   0.045       0
  4753.8   0.033       0  4942.8   0.035       0  5004.2   0.035       0
  5008.2   0.035       0  5142.4    0.07       0  5724.0   0.035       0
Bank Sta=5004.2,5008.2
Exp/Cntr=0.3,0.1

Type RM Length L Ch R = 1,3583,480,480,480
BEGIN DESCRIPTION:
LONG TRIBUTARY 11 6.0
END DESCRIPTION:
XS GIS Cut Line= 3
      2252125.02     13778824.99      2251525.00     13779025.00
      2250625.03     13779224.99
#Sta/Elev= 30
  4360.3  651.20  4419.4  648.66  4459.3  646.67  4507.9  644.31  4590.8  641.45
  4860.9  633.05  4919.0  631.78  4988.1  631.32  4988.4  630.82  4991.9  630.82
  4992.1  631.32  5065.8  631.44  5095.2  631.94  5218.1  631.75  5238.6  632.07
  5250.2  633.12  5262.7  633.15  5320.6  634.46  5351.3  634.56  5371.8  635.52
  5385.9  635.10  5526.7  637.77  5607.4  638.63  5613.8  638.27  5618.9  638.82
  5638.1  638.67  5675.4  639.62  5798.2  641.66  5873.8  642.22  5914.7  643.15
#Mann=9,-1,0
  4360.3    0.07       0  4419.4   0.035       0  4459.3    0.07       0
  4590.8   0.045       0  4860.9   0.035       0  4988.1   0.035       0
  4992.1   0.035       0  5262.7    0.07       0  5675.4   0.035       0
Bank Sta=4988.1,4992.1
Exp/Cntr=0.3,0.1

Type RM Length L Ch R = 1,3103,467,467,467
BEGIN DESCRIPTION:
LONG TRIBUTARY 11 5.0
END DESCRIPTION:
XS GIS Cut Line= 3
      2251725.00     13778475.00      2251425.00     13778575.00
      2250825.02     13779024.99
#Sta/Elev= 30
  4679.4  639.80  4753.2  636.46  4819.0  634.45  4835.5  633.92  4858.6  633.12
  4879.7  631.59  4921.8  630.01  4994.0  629.27  4998.7  629.27  5000.9  628.77
  5001.2  628.27  5004.7  628.27  5004.9  628.77  5023.3  629.68  5032.1  629.81
  5038.3  630.50  5045.6  629.90  5082.1  629.15  5095.6  629.94  5162.2  629.73
  5188.3  630.30  5202.9  630.04  5217.5  630.53  5288.3  631.12  5409.2  633.92
  5438.3  634.00  5495.6  635.62  5567.5  636.40  5617.5  637.70  5745.6  639.74
#Mann=8,-1,0
  4679.4    0.07       0  4819.0   0.035       0  4835.5    0.07       0
  4994.0    0.12       0  5000.9    0.05       0  5004.9    0.12       0
  5023.3    0.07       0  5162.2   0.035       0
Bank Sta=5000.9,5004.9
Exp/Cntr=0.3,0.1

Type RM Length L Ch R = 1,2636,436,436,436
BEGIN DESCRIPTION:
LONG TRIBUTARY 11 4.0
END DESCRIPTION:
XS GIS Cut Line= 3
      2251674.96     13778175.00      2251175.00     13778225.00
      2250624.96     13778525.02
#Sta/Elev= 30
  4501.4  640.90  4722.5  631.85  4868.5  628.08  4923.5  627.12  4933.5  626.38
  4941.6  623.97  4941.8  623.47  4945.3  623.47  4945.6  623.97  4963.7  626.46
  4973.7  626.74  4993.8  626.13  5017.6  626.31  5033.8  624.28  5039.5  624.46
  5049.4  626.11  5077.4  626.39  5088.6  625.82  5093.6  625.29  5099.3  626.20
  5115.4  626.41  5121.1  627.20  5142.9  627.75  5159.1  628.98  5174.7  628.94
  5186.6  629.91  5232.2  631.18  5431.5  636.11  5556.4  637.88  5630.4  638.80
#Mann=7,-1,0
  4501.4    0.07       0  4868.5    0.12       0  4941.6    0.05       0
  4945.6    0.12       0  5088.6    0.07       0  5232.2   0.035       0
  5556.4    0.07       0
Bank Sta=4941.6,4945.6
Exp/Cntr=0.3,0.1

Type RM Length L Ch R = 1,2200,428,428,428
BEGIN DESCRIPTION:
LONG TRIBUTARY 11 3.0
END DESCRIPTION:
XS GIS Cut Line= 3
      2251825.03     13778175.01      2251025.00     13777975.00
      2250624.97     13778325.03
#Sta/Elev= 30
  4163.9  646.46  4553.0  632.63  4846.2  625.93  4888.0  624.75  4970.5  625.12
  4986.0  622.07  4995.7  621.33  5011.4  622.03  5050.6  619.56  5050.8  619.06
  5054.7  619.56  5059.3  621.06  5066.9  619.77  5073.5  622.43  5081.1  621.18
  5087.7  621.97  5094.9  621.11  5116.2  623.35  5137.1  623.06  5144.7  624.34
  5151.3  624.16  5158.9  626.40  5165.6  625.41  5173.2  626.95  5201.2  628.32
  5208.3  629.88  5254.4  631.11  5427.2  634.74  5451.3  635.15  5520.1  636.44
#Mann=8,-1,0
  4163.9    0.07       0  4846.2    0.12       0  5011.4    0.07       0
  5050.6    0.05       0  5054.7    0.07       0  5254.4   0.035       0
  5427.2    0.07       0  5451.3   0.035       0
Bank Sta=5050.6,5054.7
Exp/Cntr=0.3,0.1

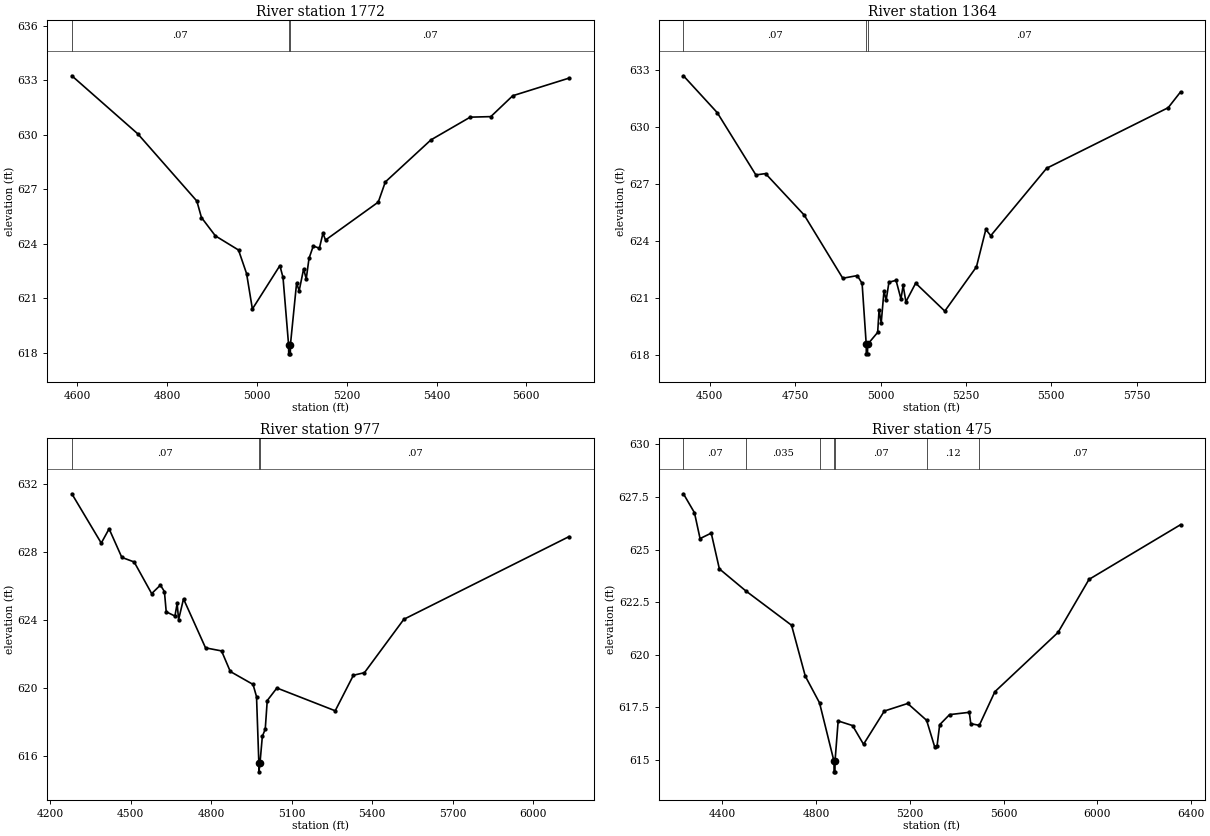
Type RM Length L Ch R = 1,1772,408,408,408
BEGIN DESCRIPTION:
LONG TRIBUTARY 11 2.0
END DESCRIPTION:
XS GIS Cut Line= 3
      2251475.01     13777775.00      2251075.00     13777675.00
      2250475.04     13778024.98
#Sta/Elev= 30
  4588.0  633.26  4734.9  630.06  4866.3  626.36  4876.6  625.45  4907.6  624.44
  4959.1  623.66  4977.1  622.36  4990.0  620.41  5051.2  622.80  5058.2  622.15
  5070.6  618.44  5070.9  617.94  5074.5  617.94  5074.7  618.44  5088.4  621.83
  5094.2  621.42  5104.1  622.62  5109.9  622.07  5116.1  623.20  5125.6  623.88
  5139.2  623.76  5147.1  624.58  5152.9  624.21  5270.3  626.30  5286.0  627.41
  5387.7  629.73  5475.0  630.98  5520.9  631.01  5569.7  632.16  5694.9  633.13
#Mann=3,-1,0
  4588.0    0.07       0  5070.6    0.05       0  5074.7    0.07       0
Bank Sta=5070.6,5074.7
Exp/Cntr=0.3,0.1

Type RM Length L Ch R = 1,1364,387,387,387
BEGIN DESCRIPTION:
LONG TRIBUTARY 11 1.0
END DESCRIPTION:
XS GIS Cut Line= 3
      2251475.03     13777725.03      2251075.00     13777325.00
      2250374.96     13777875.03
#Sta/Elev= 30
  4422.8  632.70  4521.8  630.76  4635.0  627.48  4663.3  627.55  4776.4  625.37
  4889.5  622.04  4932.0  622.18  4946.1  621.77  4958.2  618.56  4958.4  618.06
  4962.0  618.06  4962.3  618.56  4991.7  619.19  4995.8  620.37  5002.1  619.69
  5010.2  621.37  5016.6  620.89  5024.7  621.83  5045.5  621.93  5059.9  620.95
  5066.3  621.66  5074.4  620.80  5103.0  621.78  5188.3  620.31  5281.0  622.64
  5308.5  624.61  5322.9  624.28  5486.5  627.83  5842.6  631.02  5878.8  631.85
#Mann=3,-1,0
  4422.8    0.07       0  4958.2    0.05       0  4962.3    0.07       0
Bank Sta=4958.2,4962.3
Exp/Cntr=0.3,0.1

Type RM Length L Ch R = 1,977,502,502,502
BEGIN DESCRIPTION:
A19849
END DESCRIPTION:
XS GIS Cut Line= 4
      2251838.97     13777263.44      2251125.05     13776962.57
      2250681.40     13777074.76      2250344.82     13777594.92
#Sta/Elev= 30
  4281.1  631.44  4390.7  628.54  4419.9  629.38  4467.3  627.70  4513.3  627.43
  4578.5  625.57  4611.0  626.07  4626.0  625.69  4632.7  624.50  4665.2  624.25
  4673.4  624.99  4678.8  624.04  4697.1  625.26  4779.2  622.38  4838.8  622.20
  4871.4  620.99  4956.1  620.23  4969.1  619.51  4977.8  615.59  4978.0  615.09
  4981.9  615.59  4990.8  617.18  5001.6  617.60  5009.0  619.28  5045.0  620.02
  5262.2  618.68  5330.0  620.77  5371.1  620.92  5517.9  624.06  6133.0  628.92
#Mann=3,-1,0
  4281.1    0.07       0  4977.8    0.05       0  4981.9    0.07       0
Bank Sta=4977.8,4981.9
Exp/Cntr=0.3,0.1

Type RM Length L Ch R = 1,475,0,0,0
BEGIN DESCRIPTION:
A19848
END DESCRIPTION:
XS GIS Cut Line= 4
      2252144.93     13776957.47      2251334.13     13776620.91
      2250778.29     13776753.50      2250431.55     13777329.70
#Sta/Elev= 30
  4233.4  627.65  4280.5  626.75  4304.4  625.52  4352.1  625.78  4386.8  624.08
  4499.9  623.03  4694.9  621.40  4753.5  618.98  4814.3  617.71  4876.1  614.93
  4876.4  614.43  4880.1  614.43  4880.4  614.93  4893.8  616.85  4955.2  616.63
  5002.1  615.74  5090.8  617.32  5190.5  617.68  5271.3  616.88  5305.7  615.62
  5316.0  615.67  5327.1  616.67  5369.2  617.15  5453.5  617.26  5459.9  616.72
  5496.1  616.64  5562.7  618.24  5832.4  621.06  5964.5  623.58  6355.2  626.18
#Mann=7,-1,0
  4233.4    0.07       0  4499.9   0.035       0  4814.3    0.07       0
  4876.1    0.05       0  4880.4    0.07       0  5271.3    0.12       0
  5496.1    0.07       0
Bank Sta=4876.1,4880.4
Exp/Cntr=0.3,0.1

Chan Stop Cuts=-1