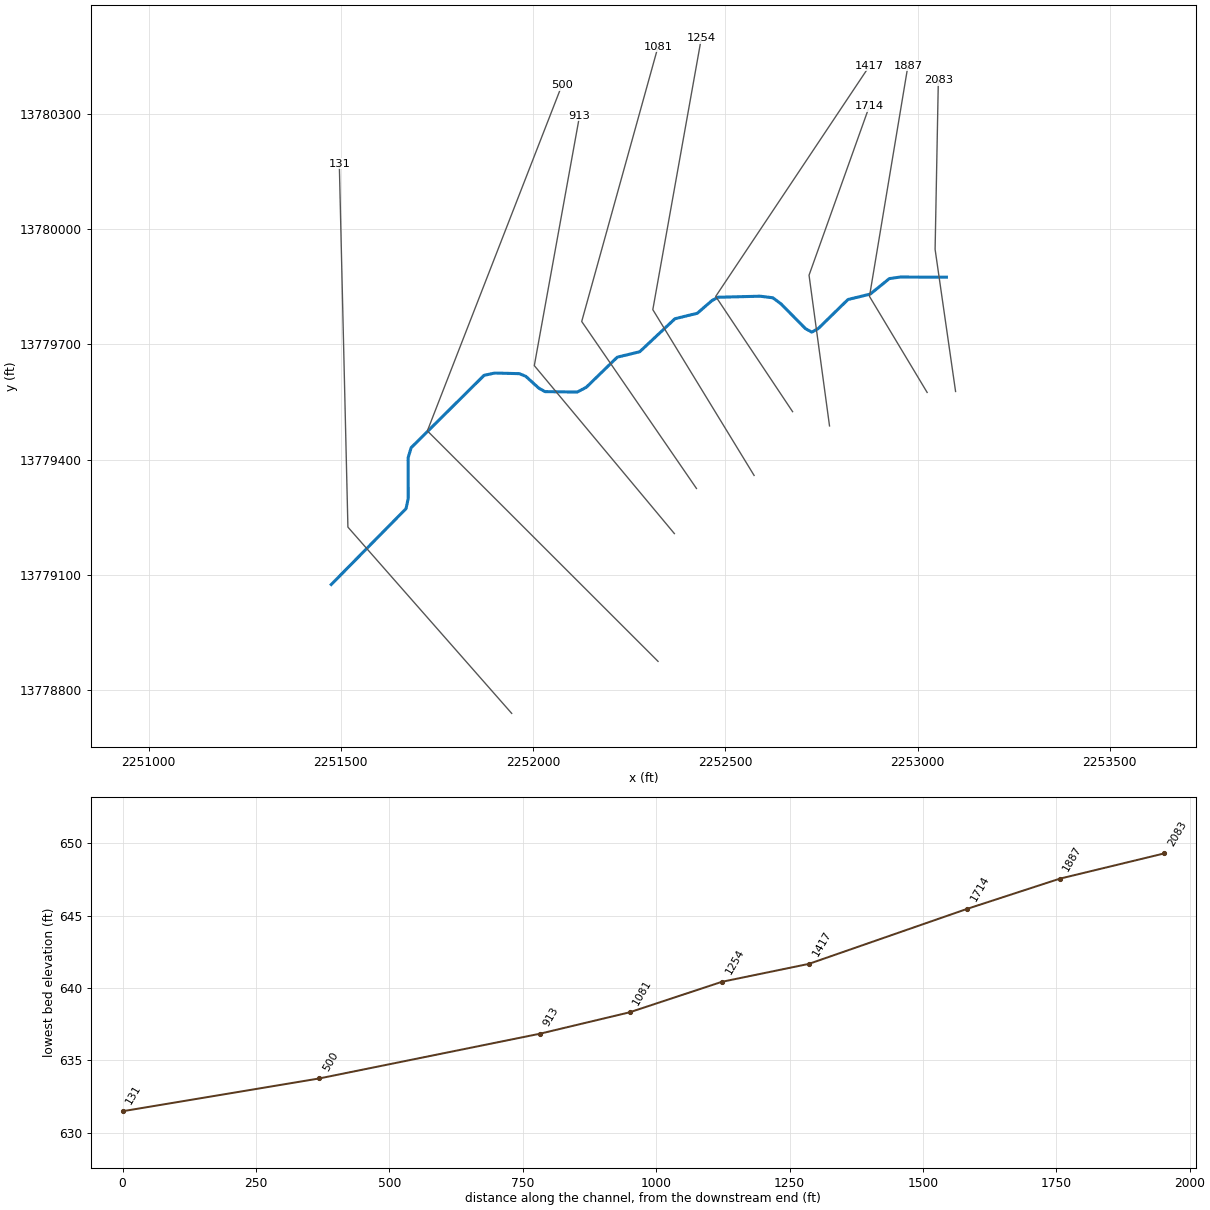
--- LONG TRIBUTARY 12.prj (project) ---

Proj Title=LONG TRIBUTARY 12 Base Level Engineering
Current Plan=p01
Default Exp/Contr=0.3,0.1
English Units
Geom File=g01
Flow File=f01
Plan File=p01
BEGIN DESCRIPTION:
LONG TRIBUTARY 12
END DESCRIPTION:

--- LONG TRIBUTARY 12.p01 (plan) ---

Plan Title=Multiple Run
Short Identifier=Multiple
Geom File=g01
Flow File=f01
Subcritical Flow
K Sum by GR= 0
Std Step Tol= 0.01
Critical Tol= 0.01
Num of Std Step Trials= 20
Max Error Tol= 0.3
Flow Tol Ratio= 0.001
Split Flow NTrial= 30
Split Flow Tol= 0.02
Split Flow Ratio= 0.02
Log Output Level= 0
Friction Slope Method= 1
Unsteady Friction Slope Method= 2
Unsteady Bridges Friction Slope Method= 1
Parabolic Critical Depth
Global Vel Dist=  1 , 1 , 1
Global Log Level= 0
CheckData=True
Encroach Param= -1, 0, 0, 0
BEGIN DESCRIPTION:
Multiple Run
END DESCRIPTION:

--- LONG TRIBUTARY 12.f01 (steady flow) ---

Flow Title=Multiple
Number of Profiles=7
Profile Names=10-year,25-year,50-year,1pct_min,100-year,1pct_plu,500-year
River Rch & RM= LONG TRIBUTARY 1,Reach-1,2083
     387     610     808     520    1038    2072    1691
Boundary for River Rch & Prof#=LONG TRIBUTARY 1,Reach-1,1
Up Type=0
Dn Type=3
Dn Slope=0.005
Boundary for River Rch & Prof#=LONG TRIBUTARY 1,Reach-1,2
Up Type=0
Dn Type=3
Dn Slope=0.005
Boundary for River Rch & Prof#=LONG TRIBUTARY 1,Reach-1,3
Up Type=0
Dn Type=3
Dn Slope=0.005
Boundary for River Rch & Prof#=LONG TRIBUTARY 1,Reach-1,4
Up Type=0
Dn Type=3
Dn Slope=0.005
Boundary for River Rch & Prof#=LONG TRIBUTARY 1,Reach-1,5
Up Type=0
Dn Type=3
Dn Slope=0.005
Boundary for River Rch & Prof#=LONG TRIBUTARY 1,Reach-1,6
Up Type=0
Dn Type=3
Dn Slope=0.005
Boundary for River Rch & Prof#=LONG TRIBUTARY 1,Reach-1,7
Up Type=0
Dn Type=3
Dn Slope=0.005

--- LONG TRIBUTARY 12.g01 (geometry) ---

Geom Title=Existing Conditions

River Reach=LONG TRIBUTARY 1,Reach-1
Reach XY= 30
      2253075.00     13779875.00      2252954.82     13779875.44
      2252926.54     13779871.28      2252877.17     13779831.14
      2252818.94     13779816.82      2252741.65     13779741.23
      2252725.00     13779732.09      2252708.35     13779741.23
      2252645.16     13779805.31      2252623.53     13779821.45
      2252590.19     13779825.53      2252480.93     13779822.77
      2252465.33     13779814.21      2252427.17     13779781.14
      2252368.95     13779766.84      2252277.28     13779680.87
      2252218.96     13779666.82      2252138.29     13779588.36
      2252114.52     13779575.94      2252030.98     13779577.17
      2252015.37     13779585.82      2251981.04     13779616.91
      2251964.45     13779623.90      2251899.96     13779625.50
      2251872.57     13779619.60      2251682.82     13779431.19
      2251674.98     13779405.01      2251675.27     13779299.89
      2251669.53     13779272.55      2251475.00     13779075.00

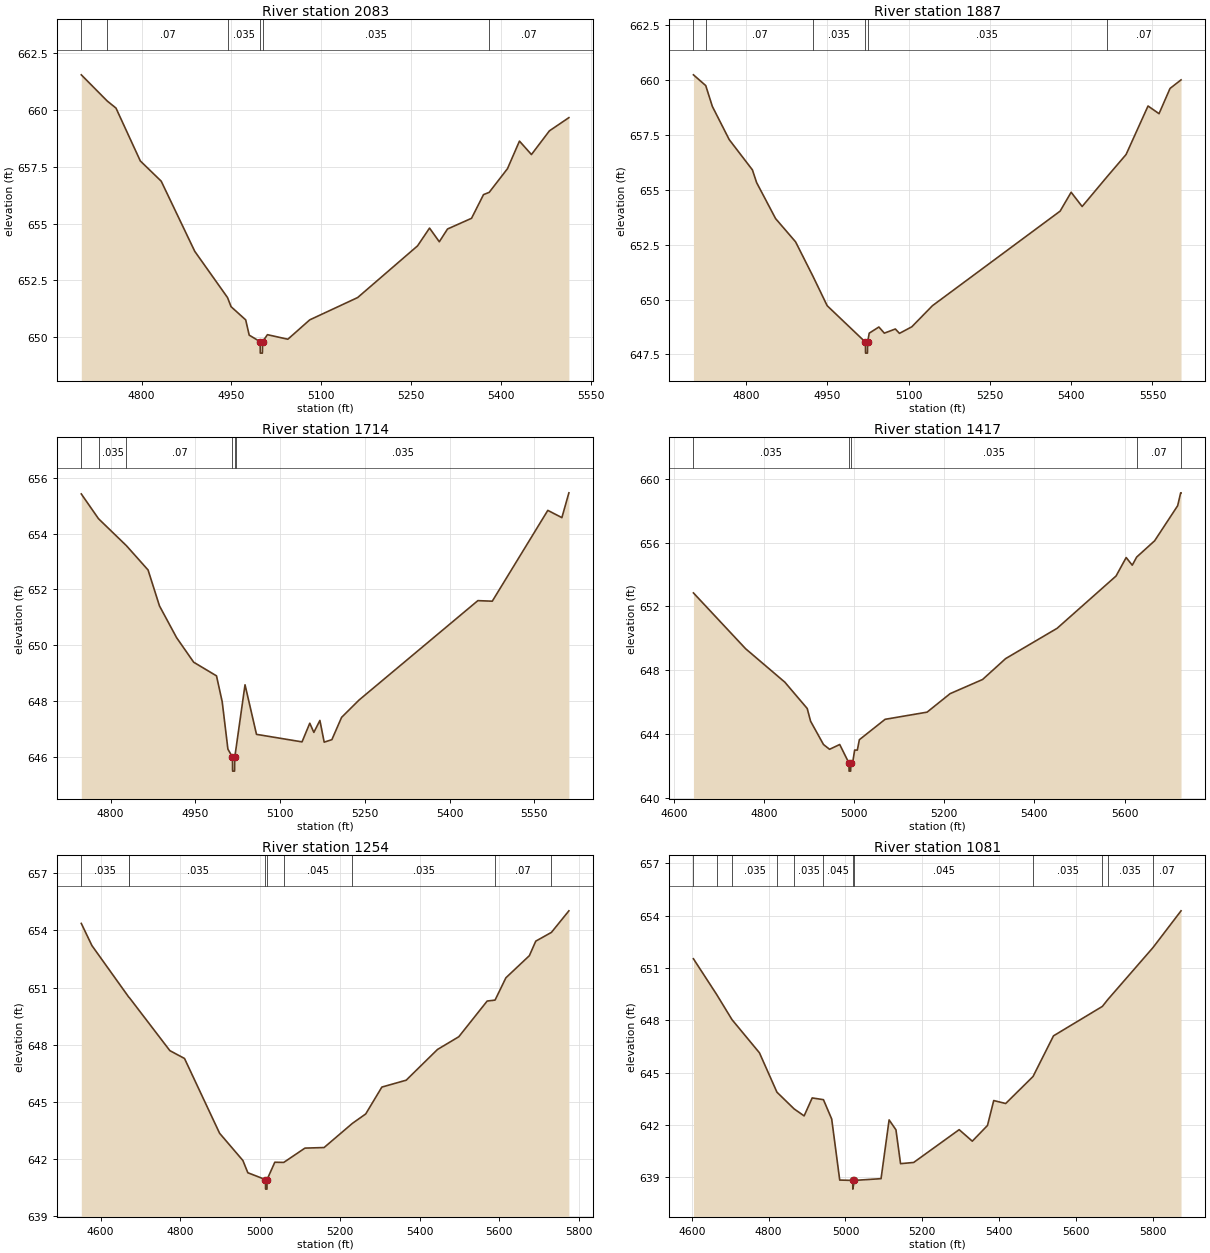
Type RM Length L Ch R = 1,2083,196,196,196
BEGIN DESCRIPTION:
A19855
END DESCRIPTION:
XS GIS Cut Line= 3
      2253098.96     13779577.51      2253045.70     13779947.49
      2253054.11     13780387.52
#Sta/Elev= 30
  4699.4  661.53  4742.7  660.38  4757.3  660.07  4797.9  657.75  4832.8  656.86
  4888.8  653.78  4943.5  651.75  4949.4  651.35  4973.8  650.77  4979.7  650.10
  4998.0  649.81  4998.2  649.31  5001.7  649.31  5002.0  649.81  5010.1  650.12
  5044.2  649.92  5080.7  650.77  5160.7  651.75  5260.7  654.02  5280.7  654.80
  5297.0  654.20  5310.7  654.76  5350.8  655.23  5370.8  656.27  5380.3  656.37
  5410.8  657.41  5430.8  658.62  5450.8  658.03  5480.8  659.07  5513.3  659.65
#Mann=6,-1,0
  4699.4   0.035       0  4742.7    0.07       0  4943.5   0.035       0
  4998.0   0.035       0  5002.0   0.035       0  5380.3    0.07       0
Bank Sta=4998,5002
Exp/Cntr=0.3,0.1

Type RM Length L Ch R = 1,1887,173,173,173
BEGIN DESCRIPTION:
LONG TRIBUTARY 12 4.0
END DESCRIPTION:
XS GIS Cut Line= 3
      2253024.98     13779575.04      2252875.00     13779825.00
      2252975.00     13780425.02
#Sta/Elev= 30
  4702.9  660.24  4725.6  659.75  4737.8  658.80  4768.9  657.29  4811.7  655.91
  4819.5  655.33  4854.5  653.69  4891.4  652.63  4923.7  651.05  4949.7  649.72
  5020.3  648.06  5020.5  647.56  5024.0  647.56  5024.3  648.06  5027.3  648.47
  5045.1  648.75  5055.2  648.47  5075.5  648.66  5083.1  648.46  5105.9  648.76
  5143.9  649.72  5379.6  654.03  5399.9  654.89  5420.2  654.24  5466.3  655.60
  5501.3  656.61  5541.8  658.82  5562.1  658.47  5582.4  659.62  5602.7  660.01
#Mann=6,-1,0
  4702.9   0.035       0  4725.6    0.07       0  4923.7   0.035       0
  5020.3   0.035       0  5024.3   0.035       0  5466.3    0.07       0
Bank Sta=5020.3,5024.3
Exp/Cntr=0.3,0.1

Type RM Length L Ch R = 1,1714,297,297,297
BEGIN DESCRIPTION:
A19854
END DESCRIPTION:
XS GIS Cut Line= 3
      2252771.05     13779487.87      2252717.80     13779880.23
      2252874.71     13780320.13
#Sta/Elev= 30
  4748.0  655.43  4778.5  654.54  4828.0  653.57  4866.2  652.70  4886.4  651.41
  4916.7  650.27  4946.9  649.39  4987.3  648.90  4997.4  647.97  5007.5  646.27
  5015.6  645.98  5015.8  645.48  5019.3  645.48  5019.6  645.98  5021.9  646.30
  5037.8  648.58  5058.1  646.80  5138.7  646.53  5152.4  647.20  5159.6  646.87
  5170.3  647.30  5177.9  646.52  5191.5  646.61  5208.7  647.41  5239.5  648.03
  5449.9  651.60  5475.4  651.58  5573.7  654.84  5598.6  654.58  5611.0  655.47
#Mann=6,-1,0
  4748.0    0.07       0  4778.5   0.035       0  4828.0    0.07       0
  5015.6    0.05       0  5019.6    0.07       0  5021.9   0.035       0
Bank Sta=5015.6,5019.6
Exp/Cntr=0.3,0.1

Type RM Length L Ch R = 1,1417,163,163,163
BEGIN DESCRIPTION:
LONG TRIBUTARY 12 3.0
END DESCRIPTION:
XS GIS Cut Line= 3
      2252675.01     13779524.98      2252475.00     13779825.00
      2252875.01     13780425.01
#Sta/Elev= 30
  4643.6  652.85  4759.3  649.35  4846.4  647.25  4896.0  645.60  4903.5  644.80
  4932.1  643.34  4945.6  643.04  4968.1  643.34  4988.7  642.17  4988.9  641.67
  4992.4  641.67  4992.7  642.17  4996.7  642.17  5001.2  642.99  5007.2  642.99
  5011.7  643.64  5068.8  644.92  5161.9  645.37  5213.0  646.53  5285.1  647.42
  5336.2  648.73  5450.4  650.63  5581.1  653.91  5603.6  655.07  5617.1  654.59
  5626.9  655.10  5666.7  656.12  5717.8  658.32  5724.5  659.13  5725.3  659.13
#Mann=5,-1,0
  4643.6   0.035       0  4988.7   0.035       0  4992.7   0.035       0
  5626.9    0.07       0  5724.5   0.035       0
Bank Sta=4988.7,4992.7
Exp/Cntr=0.3,0.1

Type RM Length L Ch R = 1,1254,173,173,173
BEGIN DESCRIPTION:
A19853
END DESCRIPTION:
XS GIS Cut Line= 3
      2252574.89     13779358.94      2252311.43     13779790.55
      2252437.55     13780496.81
#Sta/Elev= 30
  4551.6  654.36  4578.2  653.20  4670.9  650.49  4672.5  650.46  4773.8  647.69
  4810.5  647.28  4898.5  643.36  4957.0  641.93  4969.3  641.29  5013.6  640.93
  5013.9  640.43  5017.4  640.43  5017.6  640.93  5037.0  641.84  5059.4  641.83
  5112.6  642.58  5160.6  642.61  5231.8  643.88  5265.0  644.37  5305.6  645.78
  5366.5  646.14  5445.0  647.75  5498.6  648.42  5569.7  650.29  5589.5  650.34
  5616.7  651.51  5675.6  652.67  5691.6  653.43  5730.9  653.89  5774.7  655.02
#Mann=9,-1,0
  4551.6   0.035       0  4670.9    0.07       0  4672.5   0.035       0
  5013.6   0.035       0  5017.6   0.035       0  5059.4   0.045       0
  5231.8   0.035       0  5589.5    0.07       0  5730.9   0.035       0
Bank Sta=5013.6,5017.6
Exp/Cntr=0.3,0.1

Type RM Length L Ch R = 1,1081,168,168,168
BEGIN DESCRIPTION:
LONG TRIBUTARY 12 2.0
END DESCRIPTION:
XS GIS Cut Line= 3
      2252424.98     13779325.03      2252126.46     13779759.72
      2252324.99     13780474.96
#Sta/Elev= 30
  4604.2  651.53  4665.0  649.47  4704.6  648.04  4776.0  646.14  4821.6  643.88
  4866.4  642.92  4892.4  642.52  4913.4  643.55  4942.7  643.45  4964.2  642.34
  4985.1  638.84  5019.0  638.82  5019.2  638.32  5023.0  638.82  5092.7  638.92
  5113.7  642.29  5131.5  641.72  5143.5  639.78  5177.7  639.85  5296.1  641.73
  5330.3  641.07  5369.8  641.97  5386.1  643.40  5417.2  643.23  5488.5  644.78
  5541.7  647.11  5669.1  648.80  5682.7  649.18  5800.7  652.17  5873.8  654.28
#Mann=12,-1,0
  4604.2   0.035       0  4665.0    0.07       0  4704.6   0.035       0
  4821.6   0.045       0  4866.4   0.035       0  4942.7   0.045       0
  5019.0   0.045       0  5023.0   0.045       0  5488.5   0.035       0
  5669.1    0.07       0  5682.7   0.035       0  5800.7    0.07       0
Bank Sta=5019,5023
Exp/Cntr=0.3,0.1

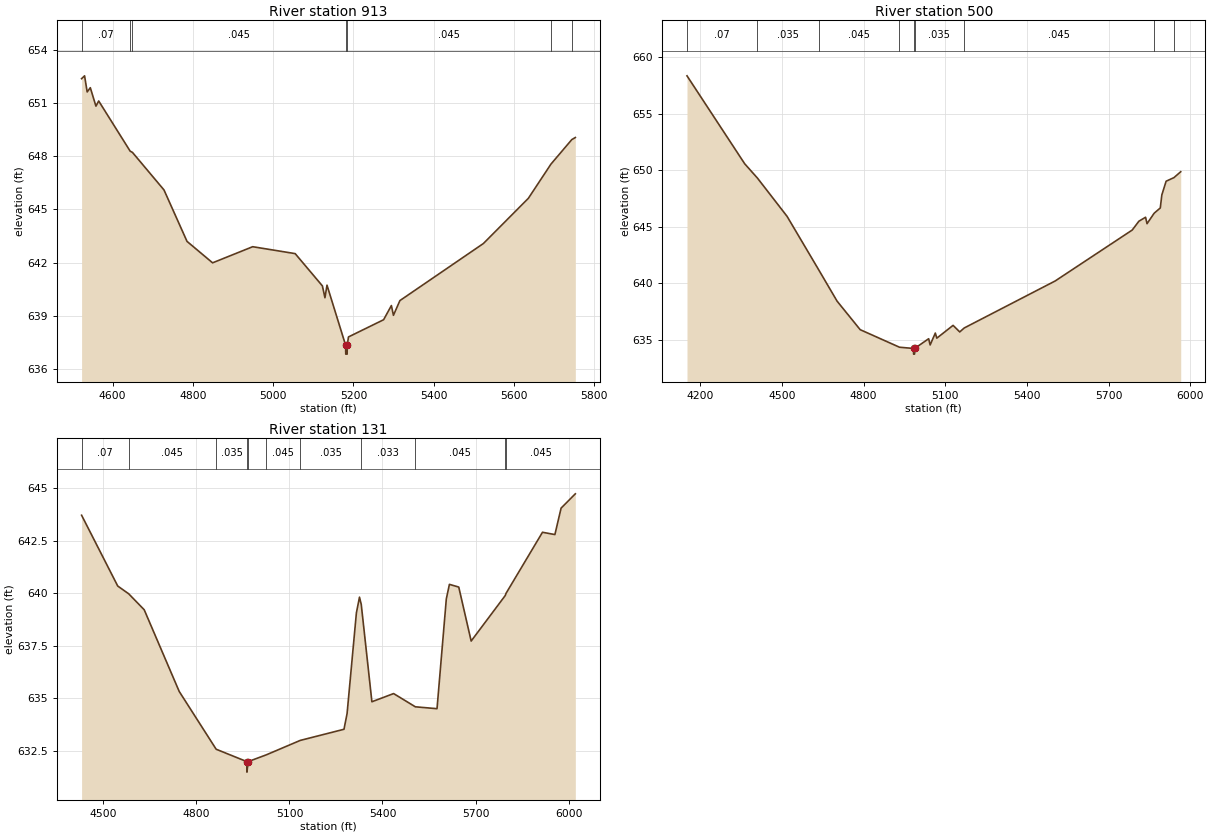
Type RM Length L Ch R = 1,913,413,413,413
BEGIN DESCRIPTION:
A19852
END DESCRIPTION:
XS GIS Cut Line= 3
      2252367.51     13779207.59      2252003.15     13779644.82
      2252120.86     13780295.01
#Sta/Elev= 30
  4522.7  652.38  4530.1  652.54  4536.6  651.63  4544.4  651.87  4558.4  650.83
  4565.3  651.12  4643.7  648.29  4649.4  648.22  4728.0  646.10  4785.3  643.20
  4849.0  641.99  4948.9  642.90  5054.7  642.51  5122.5  640.69  5128.9  640.02
  5134.0  640.73  5180.4  637.34  5180.7  636.84  5184.2  636.84  5184.4  637.34
  5187.5  637.81  5275.0  638.78  5294.4  639.58  5299.5  639.03  5315.6  639.86
  5523.6  643.08  5635.6  645.63  5691.9  647.56  5743.7  648.94  5752.6  649.06
#Mann=7,-1,0
  4522.7    0.07       0  4643.7   0.035       0  4649.4   0.045       0
  5180.4   0.045       0  5184.4   0.045       0  5691.9   0.035       0
  5743.7    0.07       0
Bank Sta=5180.4,5184.4
Exp/Cntr=0.3,0.1

Type RM Length L Ch R = 1,500,369,369,369
BEGIN DESCRIPTION:
LONG TRIBUTARY 12 1.0
END DESCRIPTION:
XS GIS Cut Line= 3
      2252325.00     13778875.00      2251725.00     13779475.00
      2252075.01     13780375.02
#Sta/Elev= 30
  4150.8  658.33  4362.9  650.56  4409.6  649.30  4518.5  645.92  4634.2  641.22
  4702.3  638.43  4787.2  635.91  4931.6  634.36  4983.2  634.25  4983.4  633.75
  4986.9  633.75  4987.2  634.25  5038.8  635.11  5044.2  634.56  5063.3  635.61
  5068.7  635.16  5128.5  636.29  5153.0  635.71  5169.5  636.06  5503.6  640.21
  5786.8  644.71  5811.3  645.49  5835.8  645.84  5841.2  645.27  5867.2  646.19
  5889.9  646.66  5895.6  647.81  5911.3  649.02  5940.1  649.34  5965.0  649.86
#Mann=9,-1,0
  4150.8    0.07       0  4409.6   0.035       0  4634.2   0.045       0
  4931.6   0.035       0  4983.2   0.035       0  4987.2   0.035       0
  5169.5   0.045       0  5867.2   0.035       0  5940.1    0.07       0
Bank Sta=4983.2,4987.2
Exp/Cntr=0.3,0.1

Type RM Length L Ch R = 1,131,0,0,0
BEGIN DESCRIPTION:
A19851
END DESCRIPTION:
XS GIS Cut Line= 3
      2251944.32     13778739.57      2251518.31     13779224.43
      2251495.91     13780170.84
#Sta/Elev= 30
  4429.8  643.71  4546.3  640.34  4581.7  639.97  4631.7  639.21  4744.6  635.32
  4863.7  632.57  4962.7  631.98  4963.0  631.48  4966.7  631.98  5024.9  632.30
  5134.8  632.99  5275.9  633.52  5285.9  634.27  5315.9  639.06  5325.9  639.81
  5331.6  639.46  5365.9  634.83  5435.9  635.22  5506.0  634.59  5575.9  634.50
  5605.9  639.73  5615.9  640.42  5646.0  640.29  5686.0  637.72  5796.0  639.89
  5798.4  639.99  5916.0  642.90  5956.0  642.79  5976.0  644.05  6021.9  644.73
#Mann=11,-1,0
  4429.8    0.07       0  4581.7   0.045       0  4863.7   0.035       0
  4962.7   0.035       0  4966.7   0.035       0  5024.9   0.045       0
  5134.8   0.035       0  5331.6   0.033       0  5506.0   0.045       0
  5796.0   0.035       0  5798.4   0.045       0
Bank Sta=4962.7,4966.7
Exp/Cntr=0.3,0.1

Chan Stop Cuts=-1