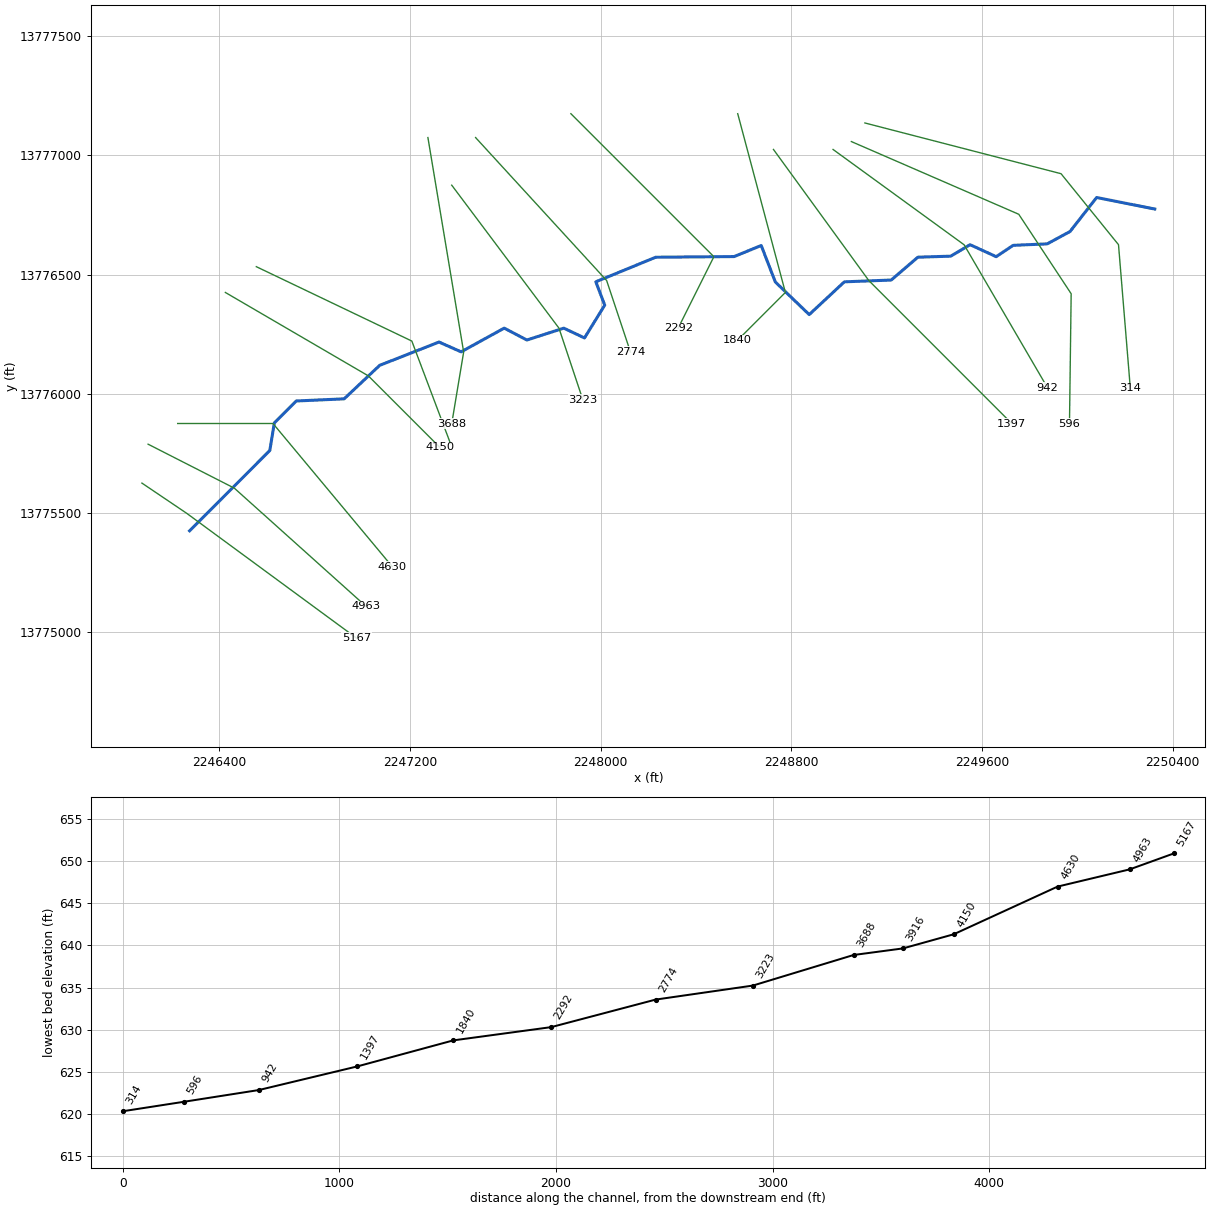
--- LONG TRIBUTARY 14.prj (project) ---

Proj Title=LONG TRIBUTARY 14 Base Level Engineering
Current Plan=p01
Default Exp/Contr=0.3,0.1
English Units
Geom File=g01
Flow File=f01
Plan File=p01
BEGIN DESCRIPTION:
LONG TRIBUTARY 14
END DESCRIPTION:

--- LONG TRIBUTARY 14.p01 (plan) ---

Plan Title=Multiple Run
Short Identifier=Multiple
Geom File=g01
Flow File=f01
Subcritical Flow
K Sum by GR= 0
Std Step Tol= 0.01
Critical Tol= 0.01
Num of Std Step Trials= 20
Max Error Tol= 0.3
Flow Tol Ratio= 0.001
Split Flow NTrial= 30
Split Flow Tol= 0.02
Split Flow Ratio= 0.02
Log Output Level= 0
Friction Slope Method= 1
Unsteady Friction Slope Method= 2
Unsteady Bridges Friction Slope Method= 1
Parabolic Critical Depth
Global Vel Dist=  1 , 1 , 1
Global Log Level= 0
CheckData=True
Encroach Param= -1, 0, 0, 0
BEGIN DESCRIPTION:
Multiple Run
END DESCRIPTION:

--- LONG TRIBUTARY 14.f01 (steady flow) ---

Flow Title=Multiple
Number of Profiles=7
Profile Names=10-year,25-year,50-year,1pct_min,100-year,1pct_plu,500-year
River Rch & RM= LONG TRIBUTARY 1,Reach-1,5167
     348     545     718     460     918    1831    1479
River Rch & RM= LONG TRIBUTARY 1,Reach-1,3223
     733    1198    1624    1066    2127    4243    3610
Boundary for River Rch & Prof#=LONG TRIBUTARY 1,Reach-1,1
Up Type=0
Dn Type=3
Dn Slope=0.005
Boundary for River Rch & Prof#=LONG TRIBUTARY 1,Reach-1,2
Up Type=0
Dn Type=3
Dn Slope=0.005
Boundary for River Rch & Prof#=LONG TRIBUTARY 1,Reach-1,3
Up Type=0
Dn Type=3
Dn Slope=0.005
Boundary for River Rch & Prof#=LONG TRIBUTARY 1,Reach-1,4
Up Type=0
Dn Type=3
Dn Slope=0.005
Boundary for River Rch & Prof#=LONG TRIBUTARY 1,Reach-1,5
Up Type=0
Dn Type=3
Dn Slope=0.005
Boundary for River Rch & Prof#=LONG TRIBUTARY 1,Reach-1,6
Up Type=0
Dn Type=3
Dn Slope=0.005
Boundary for River Rch & Prof#=LONG TRIBUTARY 1,Reach-1,7
Up Type=0
Dn Type=3
Dn Slope=0.005

--- LONG TRIBUTARY 14.g01 (geometry) ---

Geom Title=Existing Conditions

River Reach=LONG TRIBUTARY 1,Reach-1
Reach XY= 30
      2246275.00     13775425.00      2246611.60     13775761.70
      2246630.52     13775877.44      2246722.53     13775969.55
      2246923.54     13775978.54      2247072.70     13776119.17
      2247321.71     13776216.90      2247414.30     13776175.80
      2247595.17     13776275.29      2247690.27     13776225.40
      2247845.21     13776275.20      2247932.02     13776234.03
      2248016.92     13776371.72      2247979.65     13776469.74
      2248230.93     13776572.76      2248559.79     13776575.54
      2248673.61     13776621.97      2248732.86     13776468.83
      2248875.00     13776332.07      2249022.55     13776469.54
      2249219.14     13776477.07      2249330.86     13776572.92
      2249469.07     13776577.30      2249550.00     13776625.39
      2249659.60     13776575.10      2249730.93     13776622.70
      2249873.47     13776628.74      2249969.39     13776680.59
      2250081.02     13776823.39      2250325.00     13776775.00

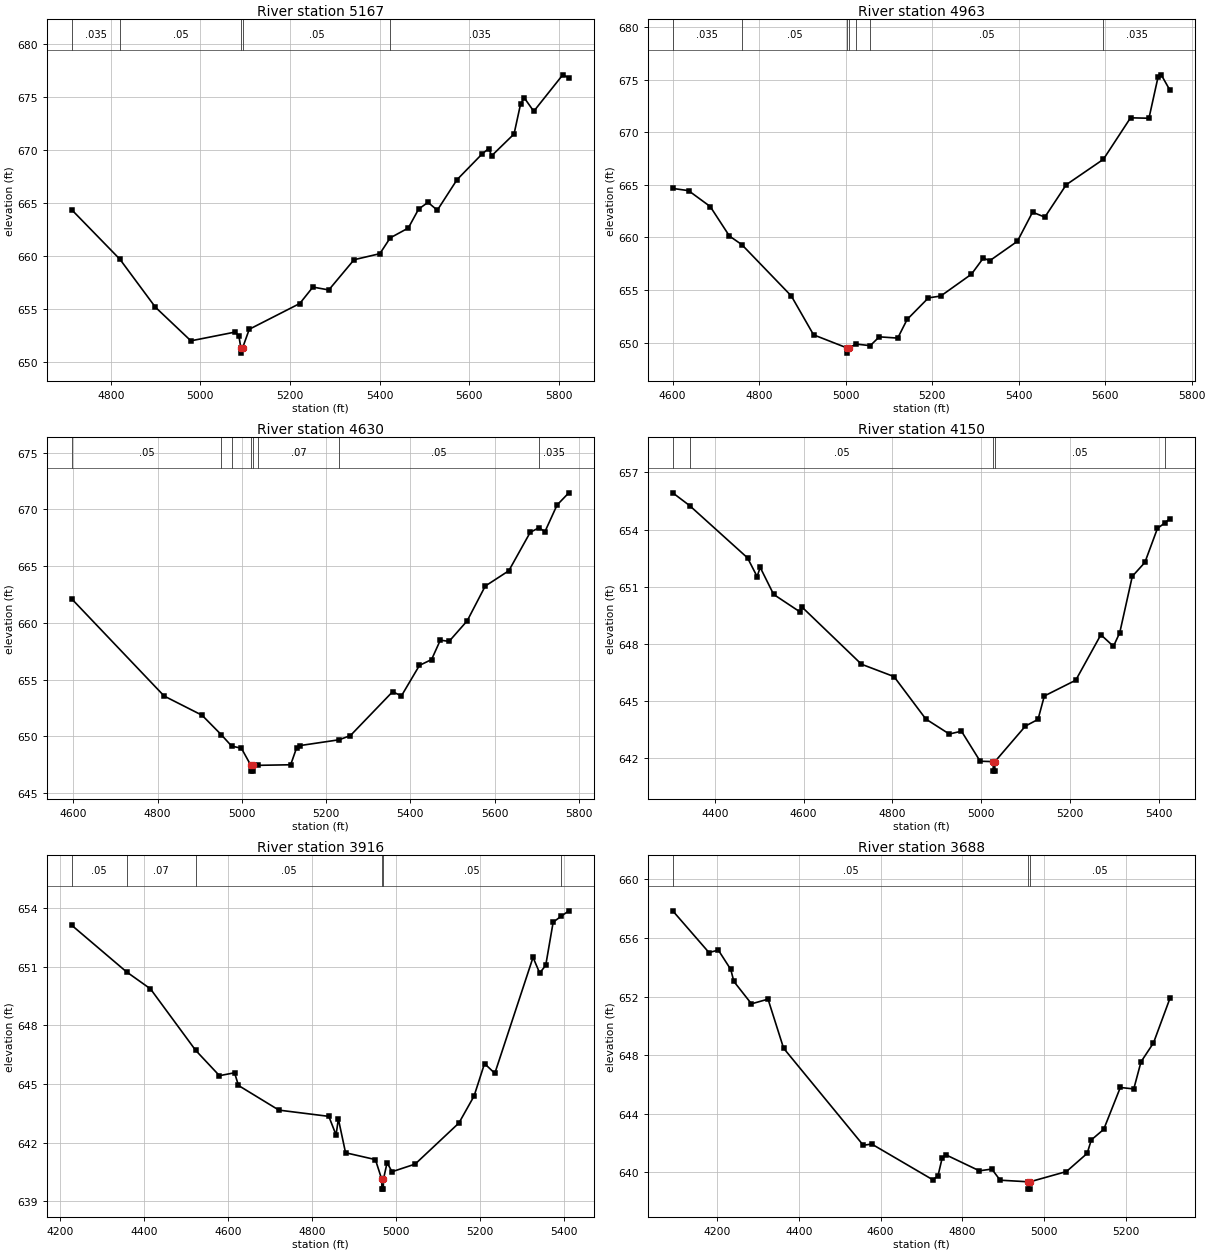
Type RM Length L Ch R = 1,5167,204,204,204
BEGIN DESCRIPTION:
LONG TRIBUTARY 14 10.0
END DESCRIPTION:
XS GIS Cut Line= 3
      2246075.01     13775624.99      2246264.04     13775497.44
      2246974.99     13774975.01
#Sta/Elev= 30
  4712.3  664.42  4820.4  659.73  4899.6  655.21  4978.8  652.04  5078.0  652.87
  5086.1  652.46  5090.3  651.38  5090.6  650.88  5094.3  651.38  5109.1  653.13
  5221.9  655.56  5251.2  657.11  5286.7  656.84  5343.1  659.69  5400.7  660.26
  5423.8  661.75  5464.2  662.68  5487.3  664.47  5508.2  665.10  5529.0  664.36
  5573.0  667.24  5629.3  669.68  5644.0  670.18  5650.2  669.49  5700.3  671.55
  5715.0  674.40  5723.3  674.95  5744.3  673.69  5809.1  677.13  5822.6  676.85
#Mann=5,-1,0
  4712.3   0.035       0  4820.4    0.05       0  5090.3    0.05       0
  5094.3    0.05       0  5423.8   0.035       0
Bank Sta=5090.3,5094.3
Exp/Cntr=0.3,0.1

Type RM Length L Ch R = 1,4963,333,333,333
BEGIN DESCRIPTION:
A19858
END DESCRIPTION:
XS GIS Cut Line= 3
      2246100.83     13775788.31      2246462.67     13775603.84
      2247015.98     13775107.28
#Sta/Elev= 30
  4600.4  664.66  4636.9  664.45  4687.0  662.94  4731.5  660.13  4760.2  659.31
  4874.5  654.43  4926.0  650.73  5003.0  649.49  5003.3  648.99  5007.0  649.49
  5024.8  649.85  5056.9  649.70  5077.9  650.54  5120.5  650.42  5142.2  652.19
  5191.5  654.25  5219.9  654.42  5290.9  656.50  5318.7  658.05  5332.8  657.77
  5397.1  659.63  5432.2  662.40  5460.6  661.93  5510.0  665.01  5595.9  667.43
  5658.7  671.38  5701.3  671.34  5722.3  675.26  5729.7  675.47  5750.0  673.99
#Mann=7,-1,0
  4600.4   0.035       0  4760.2    0.05       0  5003.0    0.05       0
  5007.0    0.05       0  5024.8    0.07       0  5056.9    0.05       0
  5595.9   0.035       0
Bank Sta=5003,5007
Exp/Cntr=0.3,0.1

Type RM Length L Ch R = 1,4630,480,480,480
BEGIN DESCRIPTION:
LONG TRIBUTARY 14 9.0
END DESCRIPTION:
XS GIS Cut Line= 3
      2246224.98     13775875.00      2246625.00     13775875.00
      2247124.97     13775275.03
#Sta/Elev= 30
  4595.4  662.13  4815.4  653.56  4905.4  651.87  4950.9  650.16  4975.7  649.15
  4998.7  648.97  5021.4  647.45  5021.7  646.95  5025.2  646.95  5025.4  647.45
  5038.2  647.46  5115.8  647.51  5130.1  649.02  5138.0  649.20  5230.8  649.71
  5257.7  650.08  5357.9  653.94  5378.8  653.57  5421.7  656.26  5450.4  656.77
  5471.2  658.48  5492.0  658.37  5535.0  660.18  5577.9  663.24  5633.9  664.59
  5684.7  667.97  5705.2  668.37  5719.8  668.04  5748.5  670.38  5776.4  671.45
#Mann=8,-1,0
  4595.4    0.05       0  4950.9    0.07       0  4975.7    0.05       0
  5021.4    0.05       0  5025.4    0.05       0  5038.2    0.07       0
  5230.8    0.05       0  5705.2   0.035       0
Bank Sta=5021.4,5025.4
Exp/Cntr=0.3,0.1

Type RM Length L Ch R = 1,4150,234,234,234
BEGIN DESCRIPTION:
LONG TRIBUTARY 14 8.0
END DESCRIPTION:
XS GIS Cut Line= 3
      2246424.99     13776425.01      2247025.00     13776075.00
      2247325.00     13775775.00
#Sta/Elev= 30
  4305.6  655.93  4343.5  655.26  4473.9  652.51  4495.4  651.53  4502.4  652.01
  4532.6  650.59  4591.3  649.68  4597.1  649.91  4730.2  646.92  4803.4  646.27
  4875.0  644.04  4927.9  643.25  4955.2  643.40  4997.3  641.82  5026.5  641.80
  5026.8  641.30  5030.3  641.30  5030.5  641.80  5099.2  643.67  5127.5  644.02
  5141.7  645.25  5212.4  646.08  5268.9  648.47  5297.2  647.86  5311.4  648.58
  5339.6  651.54  5367.9  652.27  5396.2  654.06  5414.1  654.37  5424.5  654.58
#Mann=5,-1,0
  4305.6   0.035       0  4343.5    0.05       0  5026.5    0.05       0
  5030.5    0.05       0  5414.1    0.07       0
Bank Sta=5026.5,5030.5
Exp/Cntr=0.3,0.1

Type RM Length L Ch R = 1,3916,228,228,228
BEGIN DESCRIPTION:
A19859
END DESCRIPTION:
XS GIS Cut Line= 3
      2246554.87     13776533.16      2247207.53     13776221.02
      2247370.01     13775790.10
#Sta/Elev= 30
  4227.4  653.13  4358.3  650.74  4415.3  649.87  4522.8  646.73  4579.6  645.43
  4615.5  645.58  4624.9  644.93  4721.1  643.67  4840.0  643.35  4857.2  642.40
  4862.7  643.22  4879.8  641.49  4950.9  641.14  4966.0  640.13  4966.2  639.63
  4969.7  639.63  4970.0  640.13  4978.7  640.98  4990.5  640.52  5045.5  640.91
  5149.7  643.01  5185.8  644.39  5210.7  646.05  5235.2  645.55  5326.2  651.48
  5342.0  650.68  5356.4  651.07  5374.1  653.28  5393.0  653.58  5411.4  653.86
#Mann=6,-1,0
  4227.4    0.05       0  4358.3    0.07       0  4522.8    0.05       0
  4966.0    0.05       0  4970.0    0.05       0  5393.0    0.07       0
Bank Sta=4966,4970
Exp/Cntr=0.3,0.1

Type RM Length L Ch R = 1,3688,465,465,465
BEGIN DESCRIPTION:
LONG TRIBUTARY 14 7.0
END DESCRIPTION:
XS GIS Cut Line= 3
      2247275.01     13777074.96      2247425.00     13776175.00
      2247375.00     13775875.01
#Sta/Elev= 30
  4091.6  657.85  4180.3  655.00  4203.1  655.17  4233.5  653.85  4241.1  653.03
  4284.2  651.50  4324.7  651.82  4362.8  648.47  4557.9  641.84  4578.2  641.93
  4727.7  639.49  4740.4  639.75  4750.5  640.95  4760.7  641.18  4841.8  640.10
  4872.2  640.22  4892.5  639.46  4961.4  639.35  4961.7  638.85  4965.2  638.85
  4965.4  639.35  5054.7  640.05  5105.4  641.29  5115.5  642.21  5145.9  642.93
  5186.5  645.79  5219.4  645.69  5237.1  647.54  5267.6  648.83  5308.1  651.89
#Mann=3,-1,0
  4091.6    0.05       0  4961.4    0.05       0  4965.4    0.05       0
Bank Sta=4961.4,4965.4
Exp/Cntr=0.3,0.1

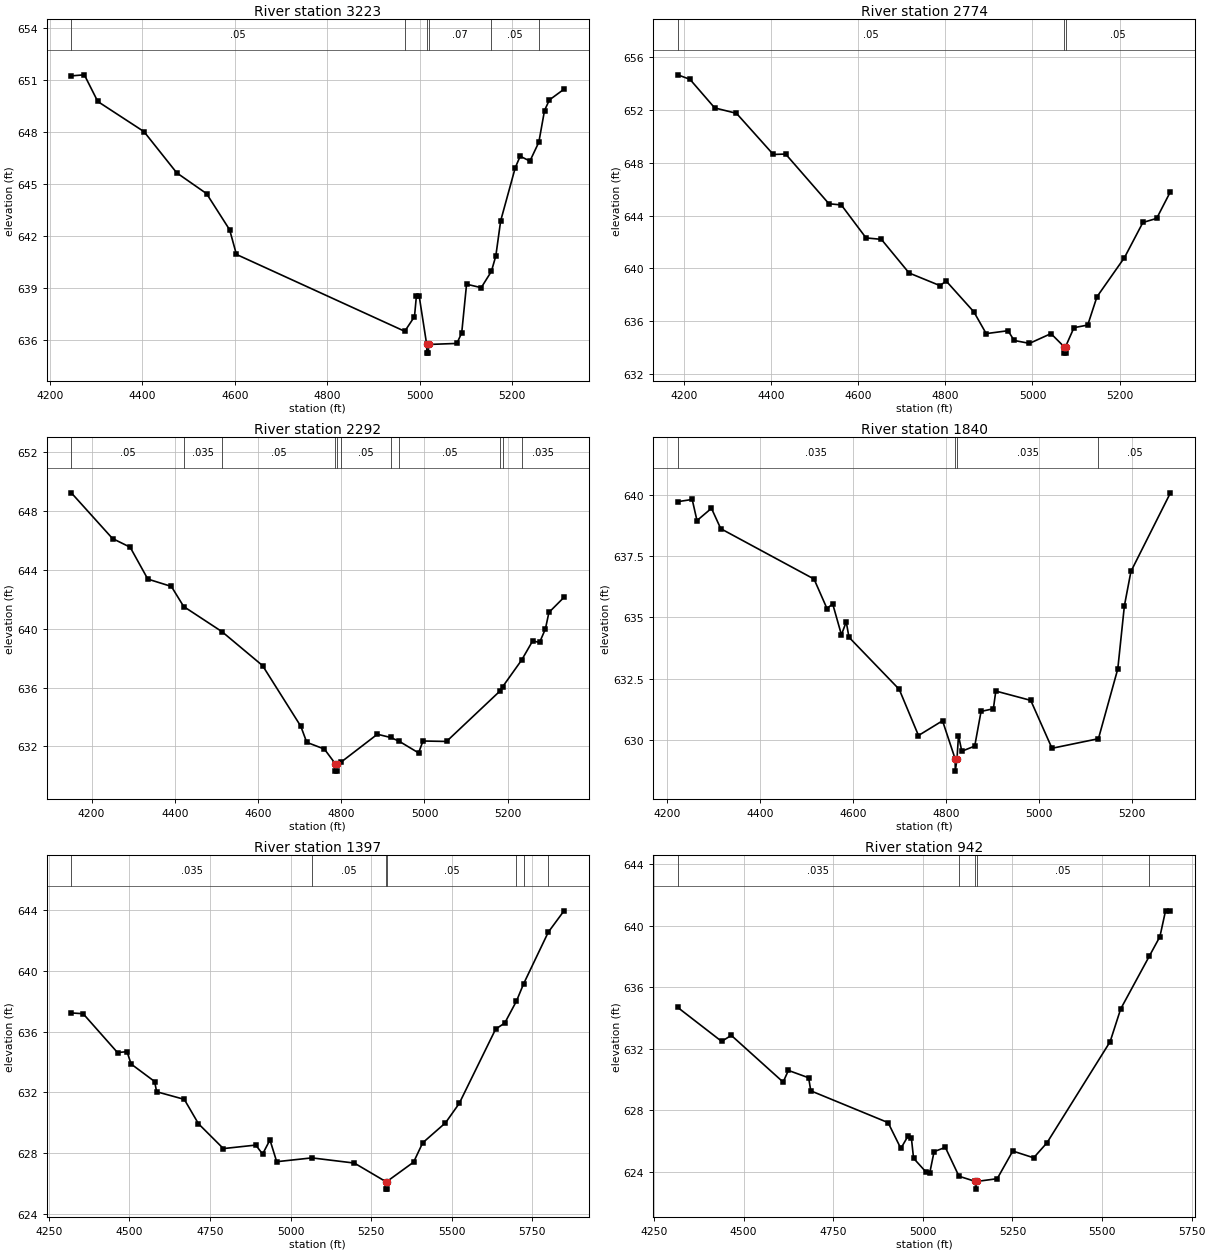
Type RM Length L Ch R = 1,3223,449,449,449
BEGIN DESCRIPTION:
LONG TRIBUTARY 14 6.0
END DESCRIPTION:
XS GIS Cut Line= 3
      2247374.98     13776875.02      2247825.00     13776275.00
      2247925.01     13775974.96
#Sta/Elev= 30
  4246.1  651.24  4274.3  651.30  4303.4  649.76  4403.4  648.02  4474.3  645.64
  4538.8  644.44  4588.8  642.35  4603.4  640.93  4967.7  636.49  4988.8  637.34
  4993.0  638.55  4998.8  638.55  5015.2  635.73  5015.5  635.23  5019.0  635.23
  5019.2  635.73  5080.5  635.79  5091.0  636.40  5101.5  639.21  5133.2  639.01
  5155.2  639.95  5164.8  640.84  5175.3  642.87  5206.9  645.94  5217.5  646.60
  5238.6  646.32  5257.9  647.41  5270.2  649.24  5280.7  649.85  5312.4  650.47
#Mann=6,-1,0
  4246.1    0.05       0  4967.7    0.07       0  5015.2    0.05       0
  5019.2    0.07       0  5155.2    0.05       0  5257.9   0.035       0
Bank Sta=5015.2,5019.2
Exp/Cntr=0.3,0.1

Type RM Length L Ch R = 1,2774,482,482,482
BEGIN DESCRIPTION:
LONG TRIBUTARY 14 5.0
END DESCRIPTION:
XS GIS Cut Line= 3
      2247475.02     13777074.98      2248025.00     13776475.00
      2248124.99     13776175.04
#Sta/Elev= 30
  4186.3  654.68  4214.3  654.34  4271.1  652.17  4321.0  651.76  4405.5  648.64
  4433.8  648.67  4533.1  644.90  4561.5  644.81  4618.2  642.31  4653.4  642.20
  4716.9  639.65  4787.8  638.69  4802.0  639.04  4865.5  636.70  4893.8  635.05
  4943.8  635.27  4958.0  634.53  4993.1  634.31  5042.4  635.05  5072.0  634.07
  5072.2  633.57  5075.7  633.57  5076.0  634.07  5095.1  635.50  5126.7  635.70
  5147.8  637.84  5211.0  640.82  5253.2  643.48  5284.8  643.79  5316.4  645.82
#Mann=3,-1,0
  4186.3    0.05       0  5072.0    0.05       0  5076.0    0.05       0
Bank Sta=5072,5076
Exp/Cntr=0.3,0.1

Type RM Length L Ch R = 1,2292,452,452,452
BEGIN DESCRIPTION:
LONG TRIBUTARY 14 4.0
END DESCRIPTION:
XS GIS Cut Line= 3
      2247875.01     13777174.99      2248475.00     13776575.00
      2248325.01     13776275.02
#Sta/Elev= 30
  4151.4  649.25  4250.4  646.14  4292.8  645.55  4335.2  643.38  4391.8  642.88
  4421.5  641.51  4513.5  639.80  4611.0  637.49  4702.9  633.36  4717.1  632.27
  4759.5  631.81  4785.8  630.81  4786.0  630.31  4789.5  630.31  4789.8  630.81
  4799.9  630.93  4886.8  632.82  4918.7  632.60  4938.8  632.35  4985.8  631.55
  4996.4  632.36  5053.0  632.33  5181.0  635.75  5187.5  636.04  5233.5  637.87
  5259.9  639.17  5276.6  639.07  5290.6  639.99  5299.0  641.11  5335.3  642.14
#Mann=11,-1,0
  4151.4    0.05       0  4421.5   0.035       0  4513.5    0.05       0
  4785.8    0.05       0  4789.8    0.05       0  4799.9    0.05       0
  4918.7   0.035       0  4938.8    0.05       0  5181.0   0.035       0
  5187.5    0.05       0  5233.5   0.035       0
Bank Sta=4785.8,4789.8
Exp/Cntr=0.3,0.1

Type RM Length L Ch R = 1,1840,443,443,443
BEGIN DESCRIPTION:
LONG TRIBUTARY 14 3.0
END DESCRIPTION:
XS GIS Cut Line= 3
      2248575.00     13777175.01      2248775.00     13776425.00
      2248574.97     13776224.97
#Sta/Elev= 30
  4223.5  639.71  4254.6  639.80  4264.9  638.94  4296.0  639.44  4316.0  638.61
  4516.5  636.56  4544.3  635.36  4556.6  635.55  4575.4  634.29  4585.7  634.82
  4591.6  634.19  4699.6  632.07  4741.0  630.19  4792.7  630.79  4819.8  629.24
  4820.1  628.74  4823.8  629.24  4827.0  630.19  4834.1  629.55  4861.9  629.76
  4875.5  631.17  4902.0  631.28  4907.2  632.00  4982.3  631.62  5028.0  629.67
  5127.8  630.06  5169.4  632.90  5183.6  635.47  5197.7  636.87  5282.6  640.07
#Mann=4,-1,0
  4223.5   0.035       0  4819.8   0.035       0  4823.8   0.035       0
  5127.8    0.05       0
Bank Sta=4819.8,4823.8
Exp/Cntr=0.3,0.1

Type RM Length L Ch R = 1,1397,455,455,455
BEGIN DESCRIPTION:
LONG TRIBUTARY 14 2.0
END DESCRIPTION:
XS GIS Cut Line= 3
      2248724.98     13777025.02      2249125.00     13776475.00
      2249724.98     13775875.02
#Sta/Elev= 30
  4319.9  637.22  4356.6  637.17  4463.3  634.62  4492.7  634.68  4505.4  633.87
  4578.4  632.72  4584.6  632.05  4670.4  631.55  4714.4  629.95  4791.7  628.32
  4892.2  628.55  4913.4  627.96  4936.2  628.89  4957.1  627.46  5066.3  627.71
  5198.0  627.37  5295.0  626.16  5295.2  625.66  5298.7  625.66  5299.0  626.16
  5381.8  627.43  5410.1  628.70  5480.8  630.01  5523.3  631.28  5636.4  636.16
  5664.7  636.56  5701.0  638.00  5723.1  639.13  5799.7  642.52  5848.5  643.92
#Mann=7,-1,0
  4319.9   0.035       0  5066.3    0.05       0  5295.0   0.035       0
  5299.0    0.05       0  5701.0    0.12       0  5723.1    0.05       0
  5799.7    0.07       0
Bank Sta=5295,5299
Exp/Cntr=0.3,0.1

Type RM Length L Ch R = 1,942,346,346,346
BEGIN DESCRIPTION:
LONG TRIBUTARY 14 1.0
END DESCRIPTION:
XS GIS Cut Line= 3
      2248975.00     13777025.00      2249525.00     13776625.00
      2249875.00     13776024.99
#Sta/Elev= 30
  4316.1  634.69  4438.6  632.48  4465.6  632.87  4610.2  629.83  4624.8  630.59
  4681.3  630.11  4687.4  629.26  4903.0  627.19  4938.6  625.51  4959.5  626.35
  4968.0  626.19  4974.1  624.87  5009.8  623.95  5019.3  623.92  5031.3  625.30
  5062.7  625.58  5100.8  623.70  5146.7  623.36  5147.0  622.86  5150.7  623.36
  5207.5  623.54  5250.9  625.34  5309.2  624.90  5346.4  625.88  5522.5  632.46
  5551.9  634.59  5631.4  638.01  5661.4  639.30  5677.1  640.98  5690.8  640.96
#Mann=5,-1,0
  4316.1   0.035       0  5100.8    0.05       0  5146.7   0.035       0
  5150.7    0.05       0  5631.4    0.07       0
Bank Sta=5146.7,5150.7
Exp/Cntr=0.3,0.1

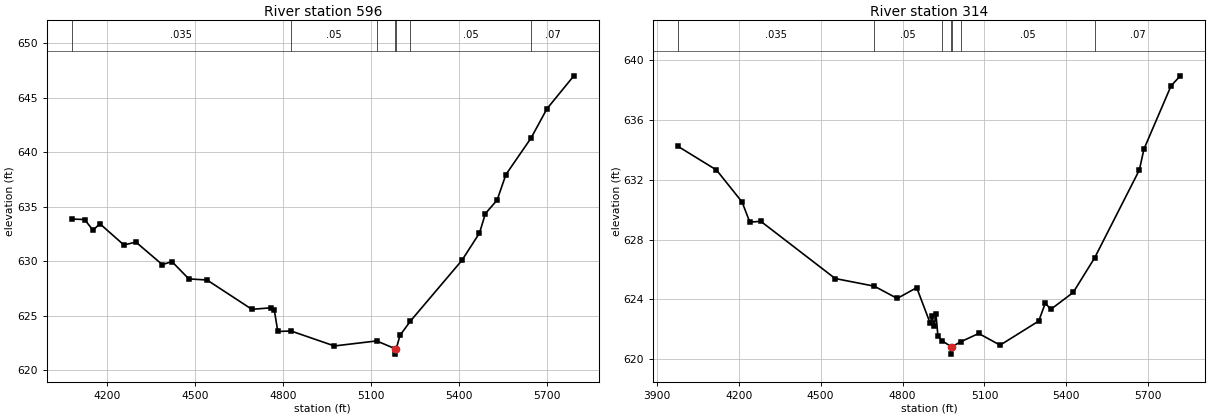
Type RM Length L Ch R = 1,596,282,282,282
BEGIN DESCRIPTION:
A19857
END DESCRIPTION:
XS GIS Cut Line= 4
      2249051.93     13777058.11      2249754.26     13776753.06
      2249974.17     13776419.65      2249967.08     13775873.42
#Sta/Elev= 30
  4080.4  633.86  4123.9  633.82  4152.8  632.84  4176.2  633.43  4258.2  631.48
  4299.0  631.75  4389.0  629.68  4421.7  629.96  4479.5  628.37  4541.6  628.27
  4694.3  625.58  4759.7  625.72  4770.6  625.53  4782.7  623.55  4828.0  623.59
  4975.6  622.22  5119.8  622.68  5182.3  621.97  5182.6  621.47  5186.3  621.97
  5199.4  623.20  5234.7  624.50  5410.2  630.07  5470.2  632.58  5490.2  634.36
  5530.2  635.60  5560.2  637.94  5645.9  641.29  5700.2  643.98  5791.8  647.00
#Mann=7,-1,0
  4080.4   0.035       0  4828.0    0.05       0  5119.8    0.07       0
  5182.3    0.05       0  5186.3    0.07       0  5234.7    0.05       0
  5645.9    0.07       0
Bank Sta=5182.3,5186.3
Exp/Cntr=0.3,0.1

Type RM Length L Ch R = 1,314,0,0,0
BEGIN DESCRIPTION:
A19856
END DESCRIPTION:
XS GIS Cut Line= 4
      2249108.69     13777136.14      2249931.61     13776923.32
      2250172.80     13776625.37      2250222.46     13776022.35
#Sta/Elev= 30
  3978.7  634.22  4118.7  632.65  4212.5  630.51  4240.6  629.17  4281.2  629.22
  4553.3  625.40  4696.5  624.89  4780.6  624.07  4851.9  624.79  4901.5  622.40
  4907.9  622.92  4915.8  622.24  4922.3  623.04  4929.5  621.57  4944.2  621.25
  4977.8  620.85  4978.0  620.35  4981.8  620.85  5013.7  621.18  5078.9  621.73
  5157.3  620.95  5298.7  622.56  5322.8  623.76  5342.8  623.34  5424.9  624.47
  5503.7  626.79  5667.1  632.65  5684.0  634.05  5783.2  638.27  5817.1  638.94
#Mann=7,-1,0
  3978.7   0.035       0  4696.5    0.05       0  4944.2    0.07       0
  4977.8    0.05       0  4981.8    0.07       0  5013.7    0.05       0
  5503.7    0.07       0
Bank Sta=4977.8,4981.8
Exp/Cntr=0.3,0.1

Chan Stop Cuts=-1