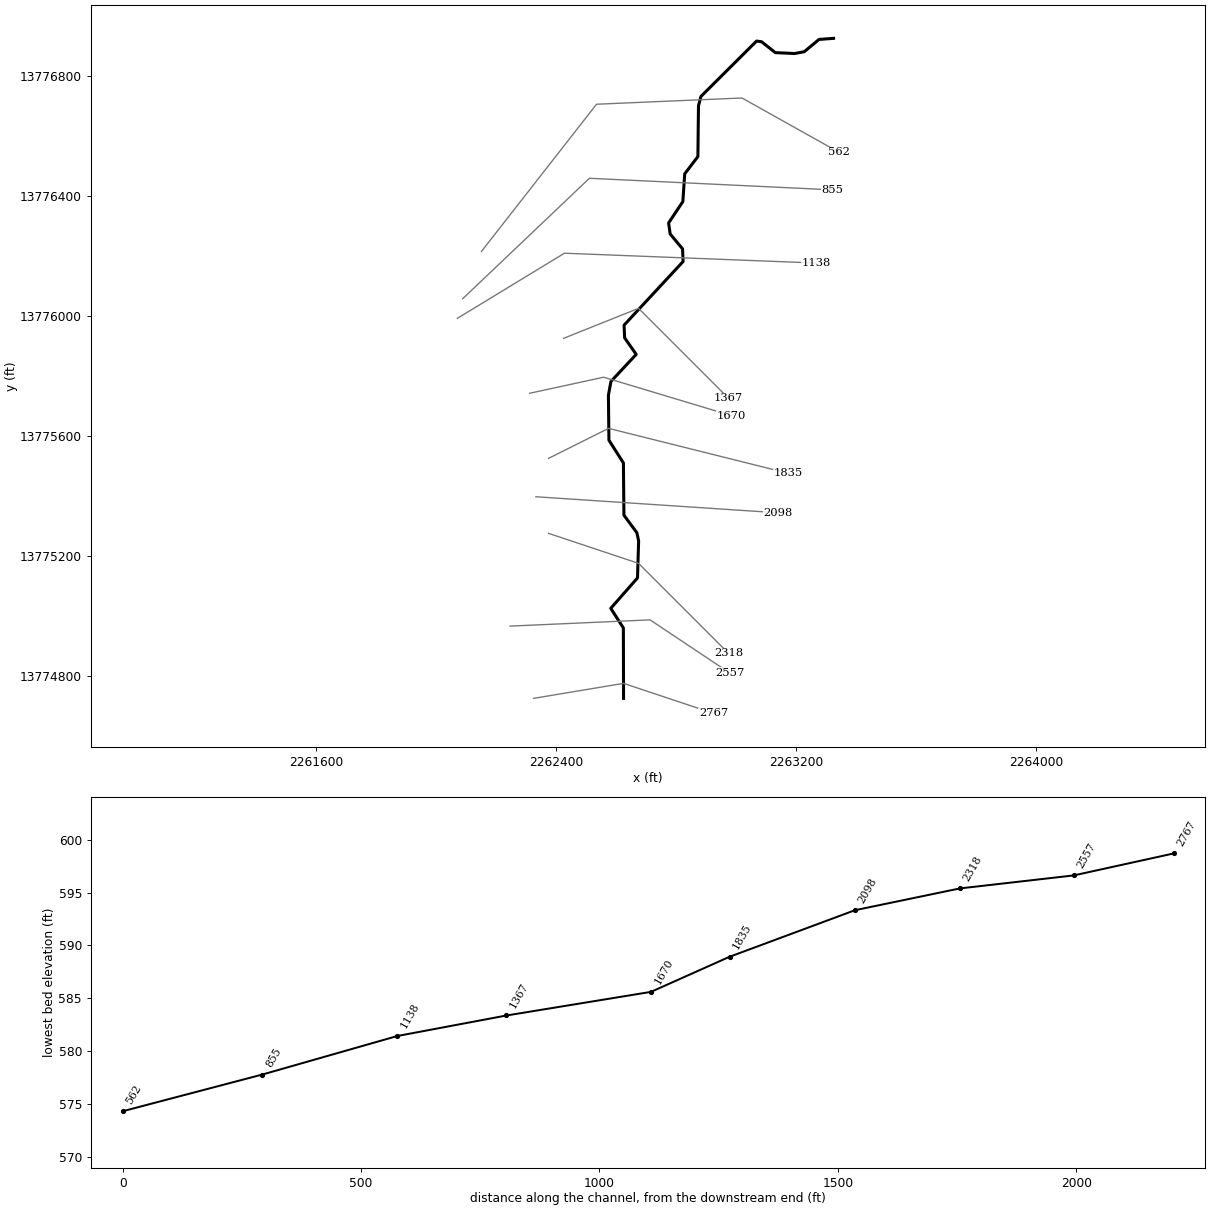
--- LONG TRIBUTARY 4.prj (project) ---

Proj Title=LONG TRIBUTARY 4 Base Level Engineering
Current Plan=p01
Default Exp/Contr=0.3,0.1
English Units
Geom File=g01
Flow File=f01
Plan File=p01
BEGIN DESCRIPTION:
LONG TRIBUTARY 4
END DESCRIPTION:

--- LONG TRIBUTARY 4.p01 (plan) ---

Plan Title=Multiple Run
Short Identifier=Multiple
Geom File=g01
Flow File=f01
Subcritical Flow
K Sum by GR= 0
Std Step Tol= 0.01
Critical Tol= 0.01
Num of Std Step Trials= 20
Max Error Tol= 0.3
Flow Tol Ratio= 0.001
Split Flow NTrial= 30
Split Flow Tol= 0.02
Split Flow Ratio= 0.02
Log Output Level= 0
Friction Slope Method= 1
Unsteady Friction Slope Method= 2
Unsteady Bridges Friction Slope Method= 1
Parabolic Critical Depth
Global Vel Dist=  1 , 1 , 1
Global Log Level= 0
CheckData=True
Encroach Param= -1, 0, 0, 0
BEGIN DESCRIPTION:
Multiple Run
END DESCRIPTION:

--- LONG TRIBUTARY 4.f01 (steady flow) ---

Flow Title=Multiple
Number of Profiles=7
Profile Names=10-year,25-year,50-year,1pct_min,100-year,1pct_plu,500-year
River Rch & RM= LONG TRIBUTARY 4,Reach-1,2767
     312     486     638     408     813    1623    1303
Boundary for River Rch & Prof#=LONG TRIBUTARY 4,Reach-1,1
Up Type=0
Dn Type=3
Dn Slope=0.005
Boundary for River Rch & Prof#=LONG TRIBUTARY 4,Reach-1,2
Up Type=0
Dn Type=3
Dn Slope=0.005
Boundary for River Rch & Prof#=LONG TRIBUTARY 4,Reach-1,3
Up Type=0
Dn Type=3
Dn Slope=0.005
Boundary for River Rch & Prof#=LONG TRIBUTARY 4,Reach-1,4
Up Type=0
Dn Type=3
Dn Slope=0.005
Boundary for River Rch & Prof#=LONG TRIBUTARY 4,Reach-1,5
Up Type=0
Dn Type=3
Dn Slope=0.005
Boundary for River Rch & Prof#=LONG TRIBUTARY 4,Reach-1,6
Up Type=0
Dn Type=3
Dn Slope=0.005
Boundary for River Rch & Prof#=LONG TRIBUTARY 4,Reach-1,7
Up Type=0
Dn Type=3
Dn Slope=0.005

--- LONG TRIBUTARY 4.g01 (geometry) ---

Geom Title=Existing Conditions

River Reach=LONG TRIBUTARY 4,Reach-1
Reach XY= 30
      2262625.00     13774725.00      2262624.34     13774959.84
      2262582.33     13775025.10      2262671.45     13775126.47
      2262675.23     13775250.07      2262669.26     13775277.33
      2262626.22     13775335.51      2262624.48     13775509.78
      2262576.22     13775585.51      2262574.50     13775735.21
      2262582.85     13775781.19      2262667.16     13775871.60
      2262628.59     13775926.65      2262626.66     13775968.95
      2262823.38     13776181.03      2262821.63     13776223.26
      2262780.42     13776272.80      2262775.10     13776309.60
      2262822.62     13776380.97      2262828.86     13776473.40
      2262872.74     13776530.94      2262874.71     13776700.12
      2262882.81     13776731.19      2263068.26     13776915.87
      2263084.85     13776913.67      2263130.89     13776877.37
      2263195.05     13776874.39      2263227.39     13776880.47
      2263276.51     13776921.35      2263325.00     13776925.00

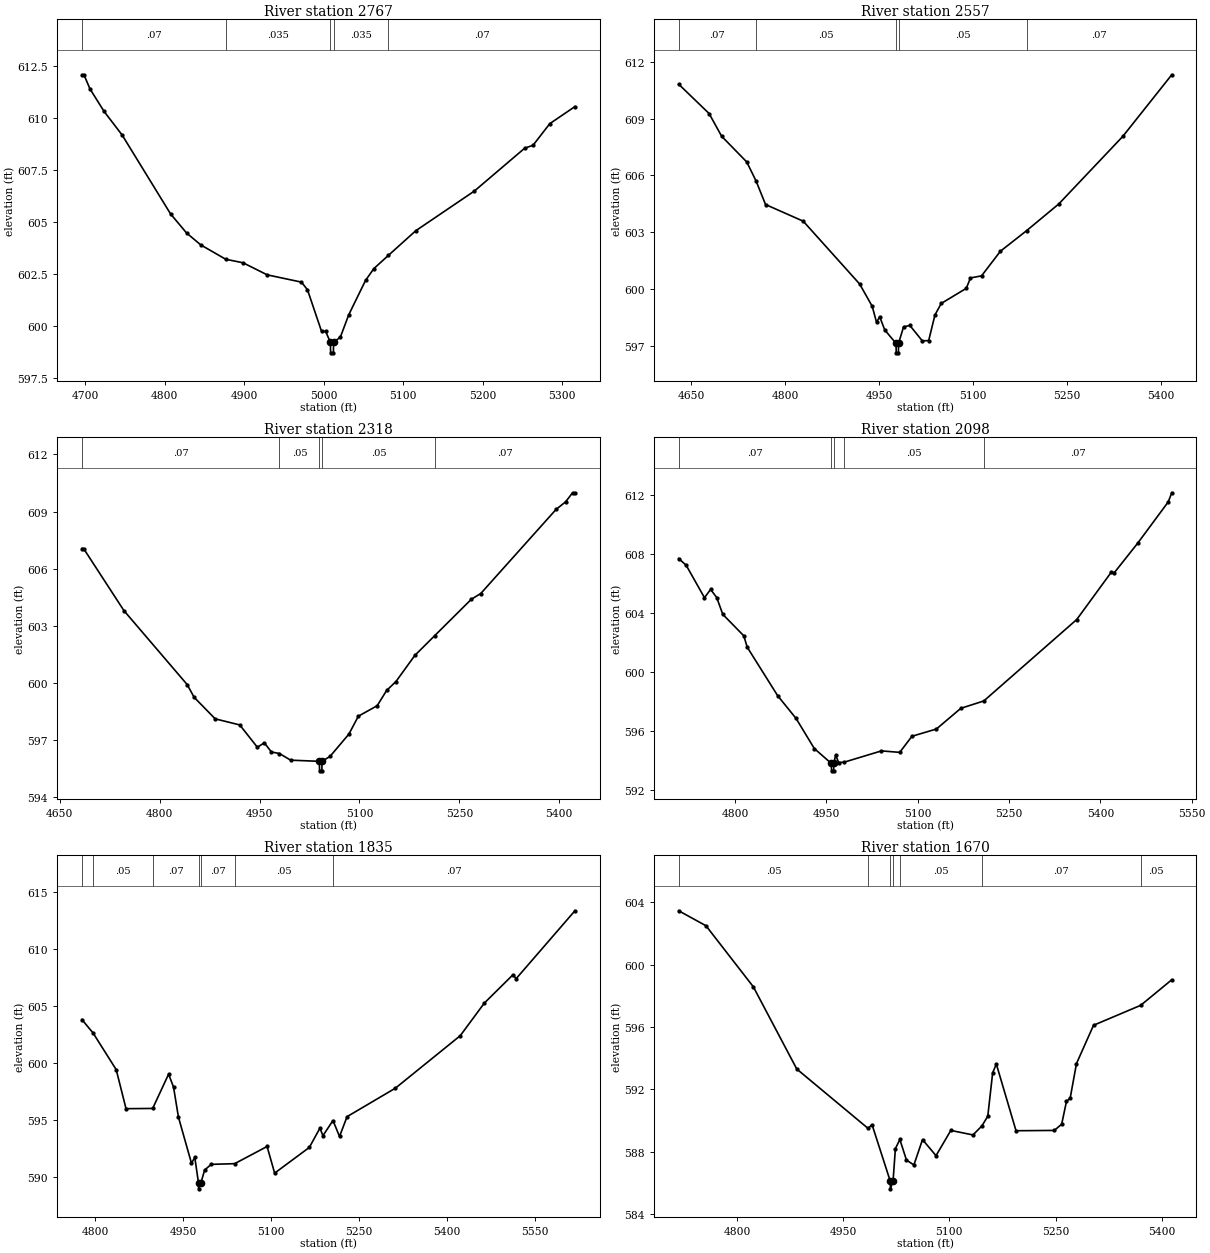
Type RM Length L Ch R = 1,2767,210,210,210
BEGIN DESCRIPTION:
LONG TRIBUTARY 4 4.0
END DESCRIPTION:
XS GIS Cut Line= 3
      2262324.96     13774724.99      2262625.00     13774775.00
      2262924.99     13774675.00
#Sta/Elev= 30
  4695.8  612.07  4698.4  612.07  4706.0  611.39  4723.7  610.31  4746.5  609.17
  4807.4  605.38  4827.6  604.46  4845.4  603.89  4876.8  603.20  4898.6  603.03
  4929.0  602.45  4972.1  602.10  4979.7  601.73  4997.4  599.73  5002.6  599.73
  5008.5  599.20  5008.8  598.70  5012.3  598.70  5012.5  599.20  5021.1  599.46
  5031.6  600.53  5052.7  602.18  5063.2  602.75  5081.6  603.39  5115.9  604.57
  5189.7  606.48  5253.0  608.54  5263.5  608.68  5284.6  609.72  5316.2  610.54
#Mann=5,-1,0
  4695.8    0.07       0  4876.8   0.035       0  5008.5   0.035       0
  5012.5   0.035       0  5081.6    0.07       0
Bank Sta=5008.5,5012.5
Exp/Cntr=0.3,0.1

Type RM Length L Ch R = 1,2557,239,239,239
BEGIN DESCRIPTION:
A19865
END DESCRIPTION:
XS GIS Cut Line= 3
      2262246.54     13774965.86      2262713.35     13774986.67
      2262979.21     13774809.43
#Sta/Elev= 30
  4630.5  610.82  4679.0  609.27  4699.0  608.07  4739.1  606.71  4754.0  605.70
  4769.1  604.46  4829.2  603.58  4919.2  600.26  4939.3  599.08  4946.2  598.23
  4951.2  598.53  4959.3  597.83  4977.3  597.12  4977.6  596.62  4981.1  596.62
  4981.3  597.12  4989.3  597.99  4999.3  598.07  5019.3  597.25  5029.4  597.27
  5039.4  598.62  5049.4  599.23  5089.4  600.03  5096.1  600.58  5113.8  600.69
  5143.8  601.99  5185.7  603.08  5237.0  604.49  5339.1  608.06  5417.3  611.32
#Mann=5,-1,0
  4630.5    0.07       0  4754.0    0.05       0  4977.3    0.05       0
  4981.3    0.05       0  5185.7    0.07       0
Bank Sta=4977.3,4981.3
Exp/Cntr=0.3,0.1

Type RM Length L Ch R = 1,2318,220,220,220
BEGIN DESCRIPTION:
LONG TRIBUTARY 4 3.0
END DESCRIPTION:
XS GIS Cut Line= 3
      2262375.05     13775274.98      2262675.00     13775175.00
      2262974.97     13774875.03
#Sta/Elev= 30
  4683.1  607.06  4685.7  607.06  4746.3  603.80  4841.2  599.92  4851.7  599.25
  4883.3  598.12  4920.2  597.80  4946.6  596.63  4957.1  596.86  4967.7  596.38
  4979.8  596.30  4996.6  595.95  5039.7  595.89  5040.0  595.39  5043.5  595.39
  5043.7  595.89  5055.8  596.15  5084.1  597.32  5098.3  598.26  5126.6  598.81
  5140.7  599.61  5154.8  600.08  5183.1  601.45  5213.0  602.49  5268.0  604.40
  5282.1  604.70  5395.3  609.12  5409.4  609.51  5420.0  609.99  5423.5  609.99
#Mann=5,-1,0
  4683.1    0.07       0  4979.8    0.05       0  5039.7    0.05       0
  5043.7    0.05       0  5213.0    0.07       0
Bank Sta=5039.7,5043.7
Exp/Cntr=0.3,0.1

Type RM Length L Ch R = 1,2098,263,263,263
BEGIN DESCRIPTION:
A19864
END DESCRIPTION:
XS GIS Cut Line= 2
      2262332.76     13775397.02      2263140.79     13775343.54
#Sta/Elev= 30
  4707.5  607.70  4719.8  607.24  4749.8  605.05  4759.9  605.61  4769.9  605.06
  4779.9  603.92  4814.4  602.47  4820.0  601.70  4870.1  598.41  4900.2  596.88
  4930.2  594.84  4958.2  593.83  4958.5  593.33  4962.0  593.33  4962.2  593.83
  4965.2  594.39  4970.3  593.89  4979.5  593.92  5040.5  594.68  5070.5  594.58
  5090.6  595.67  5130.7  596.16  5170.8  597.56  5208.6  598.06  5361.2  603.57
  5417.9  606.77  5422.9  606.74  5461.4  608.74  5511.5  611.53  5517.3  612.15
#Mann=5,-1,0
  4707.5    0.07       0  4958.2    0.05       0  4962.2    0.07       0
  4979.5    0.05       0  5208.6    0.07       0
Bank Sta=4958.2,4962.2
Exp/Cntr=0.3,0.1

Type RM Length L Ch R = 1,1835,165,165,165
BEGIN DESCRIPTION:
LONG TRIBUTARY 4 2.0
END DESCRIPTION:
XS GIS Cut Line= 3
      2262375.04     13775525.02      2262575.00     13775625.00
      2263174.98     13775475.01
#Sta/Elev= 30
  4776.9  603.80  4796.1  602.61  4835.5  599.40  4852.3  595.97  4897.8  595.99
  4925.0  599.00  4933.4  597.87  4941.8  595.23  4964.1  591.17  4969.7  591.70
  4976.1  589.43  4976.3  588.93  4980.1  589.43  4986.5  590.58  4997.7  591.08
  5037.8  591.14  5093.2  592.65  5106.1  590.31  5165.4  592.57  5183.4  594.26
  5188.6  593.60  5205.7  594.93  5216.9  593.53  5229.8  595.27  5312.3  597.77
  5423.1  602.38  5464.3  605.25  5513.3  607.74  5518.4  607.38  5618.9  613.35
#Mann=7,-1,0
  4776.9    0.07       0  4796.1    0.05       0  4897.8    0.07       0
  4976.1    0.05       0  4980.1    0.07       0  5037.8    0.05       0
  5205.7    0.07       0
Bank Sta=4976.1,4980.1
Exp/Cntr=0.3,0.1

Type RM Length L Ch R = 1,1670,303,303,303
BEGIN DESCRIPTION:
A19863
END DESCRIPTION:
XS GIS Cut Line= 3
      2262311.95     13775741.95      2262558.73     13775795.47
      2262983.90     13775667.62
#Sta/Elev= 30
  4717.7  603.46  4756.2  602.50  4823.1  598.58  4884.5  593.30  4985.2  589.49
  4990.8  589.73  5016.5  586.11  5016.8  585.61  5020.5  586.11  5023.8  588.19
  5030.1  588.78  5039.4  587.46  5049.9  587.14  5062.1  588.77  5081.2  587.74
  5102.1  589.36  5133.4  589.07  5146.0  589.65  5154.3  590.27  5161.2  593.06
  5166.4  593.62  5194.2  589.34  5248.3  589.36  5258.7  589.76  5265.5  591.23
  5270.7  591.43  5279.6  593.65  5303.7  596.11  5370.3  597.39  5414.2  599.03
#Mann=7,-1,0
  4717.7    0.05       0  4985.2    0.07       0  5016.5    0.05       0
  5020.5    0.07       0  5030.1    0.05       0  5146.0    0.07       0
  5370.3    0.05       0
Bank Sta=5016.5,5020.5
Exp/Cntr=0.3,0.1

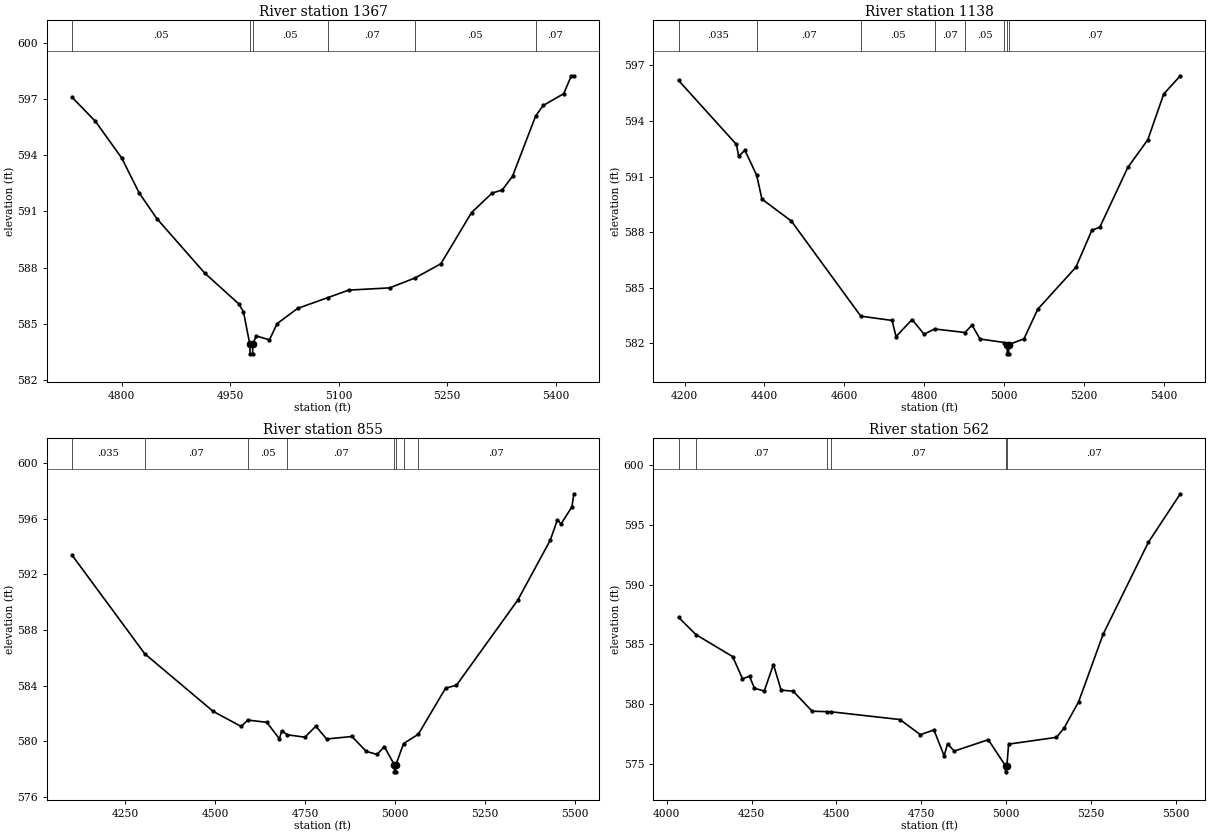
Type RM Length L Ch R = 1,1367,229,229,229
BEGIN DESCRIPTION:
LONG TRIBUTARY 4 1.0
END DESCRIPTION:
XS GIS Cut Line= 3
      2262425.02     13775925.01      2262675.00     13776025.00
      2262975.00     13775725.00
#Sta/Elev= 30
  4731.5  597.11  4763.8  595.82  4800.1  593.86  4824.4  591.98  4848.6  590.62
  4914.6  587.71  4961.7  586.06  4968.4  585.63  4977.2  583.88  4977.5  583.38
  4981.0  583.38  4981.2  583.88  4985.9  584.34  5004.3  584.13  5014.9  585.00
  5043.2  585.81  5085.0  586.39  5113.9  586.79  5170.4  586.91  5205.5  587.44
  5241.2  588.20  5283.6  590.94  5311.9  591.98  5326.0  592.15  5340.2  592.88
  5372.1  596.10  5382.6  596.67  5410.9  597.30  5421.5  598.26  5425.0  598.26
#Mann=6,-1,0
  4731.5    0.05       0  4977.2    0.05       0  4981.2    0.05       0
  5085.0    0.07       0  5205.5    0.05       0  5372.1    0.07       0
Bank Sta=4977.2,4981.2
Exp/Cntr=0.3,0.1

Type RM Length L Ch R = 1,1138,283,283,283
BEGIN DESCRIPTION:
A19862
END DESCRIPTION:
XS GIS Cut Line= 3
      2262071.09     13775991.73      2262427.90     13776208.79
      2263266.42     13776176.08
#Sta/Elev= 30
  4184.7  596.18  4329.6  592.73  4335.4  592.09  4350.9  592.42  4380.5  591.06
  4393.6  589.78  4467.2  588.60  4641.3  583.47  4719.5  583.24  4729.5  582.37
  4769.6  583.29  4799.6  582.50  4826.5  582.78  4902.3  582.59  4919.7  582.99
  4939.7  582.24  5001.0  582.05  5007.8  581.94  5008.0  581.44  5011.5  581.44
  5011.8  581.94  5049.8  582.25  5084.6  583.85  5179.9  586.11  5219.9  588.10
  5239.9  588.27  5310.0  591.49  5360.0  592.98  5400.0  595.45  5441.5  596.43
#Mann=8,-1,0
  4184.7   0.035       0  4380.5    0.07       0  4641.3    0.05       0
  4826.5    0.07       0  4902.3    0.05       0  5001.0    0.07       0
  5007.8    0.05       0  5011.8    0.07       0
Bank Sta=5007.8,5011.8
Exp/Cntr=0.3,0.1

Type RM Length L Ch R = 1,855,293,293,293
BEGIN DESCRIPTION:
A19861
END DESCRIPTION:
XS GIS Cut Line= 3
      2262088.92     13776057.15      2262511.15     13776458.56
      2263320.54     13776420.02
#Sta/Elev= 30
  4103.3  593.37  4305.2  586.28  4495.2  582.14  4572.9  581.06  4590.8  581.52
  4643.7  581.36  4678.9  580.17  4685.1  580.75  4701.2  580.46  4749.8  580.29
  4779.8  581.08  4809.9  580.16  4880.0  580.34  4920.0  579.27  4950.0  579.05
  4970.1  579.61  4998.1  578.30  4998.3  577.80  5001.8  577.80  5002.1  578.30
  5023.5  579.83  5064.4  580.50  5140.3  583.82  5170.3  584.02  5340.5  590.14
  5430.6  594.44  5450.6  595.91  5460.6  595.61  5490.7  596.84  5496.2  597.78
#Mann=8,-1,0
  4103.3   0.035       0  4305.2    0.07       0  4590.8    0.05       0
  4701.2    0.07       0  4998.1    0.05       0  5002.1    0.07       0
  5023.5    0.05       0  5064.4    0.07       0
Bank Sta=4998.1,5002.1
Exp/Cntr=0.3,0.1

Type RM Length L Ch R = 1,562,0,0,0
BEGIN DESCRIPTION:
A19860
END DESCRIPTION:
XS GIS Cut Line= 4
      2262151.37     13776214.75      2262534.94     13776705.37
      2263019.63     13776726.18      2263343.74     13776544.80
#Sta/Elev= 30
  4034.5  587.27  4085.6  585.83  4194.1  583.98  4223.0  582.13  4243.8  582.33
  4258.3  581.33  4287.2  581.10  4314.3  583.32  4336.9  581.17  4372.2  581.09
  4428.3  579.41  4471.2  579.37  4484.2  579.36  4687.3  578.71  4747.4  577.44
  4787.4  577.84  4817.5  575.67  4827.5  576.67  4847.5  576.07  4947.6  577.02
  4998.5  574.83  4998.7  574.33  5002.5  574.83  5007.6  576.65  5148.5  577.22
  5170.6  577.97  5214.0  580.20  5286.1  585.85  5419.5  593.55  5513.8  597.62
#Mann=6,-1,0
  4034.5   0.035       0  4085.6    0.07       0  4471.2    0.05       0
  4484.2    0.07       0  4998.5    0.05       0  5002.5    0.07       0
Bank Sta=4998.5,5002.5
Exp/Cntr=0.3,0.1

Chan Stop Cuts=-1