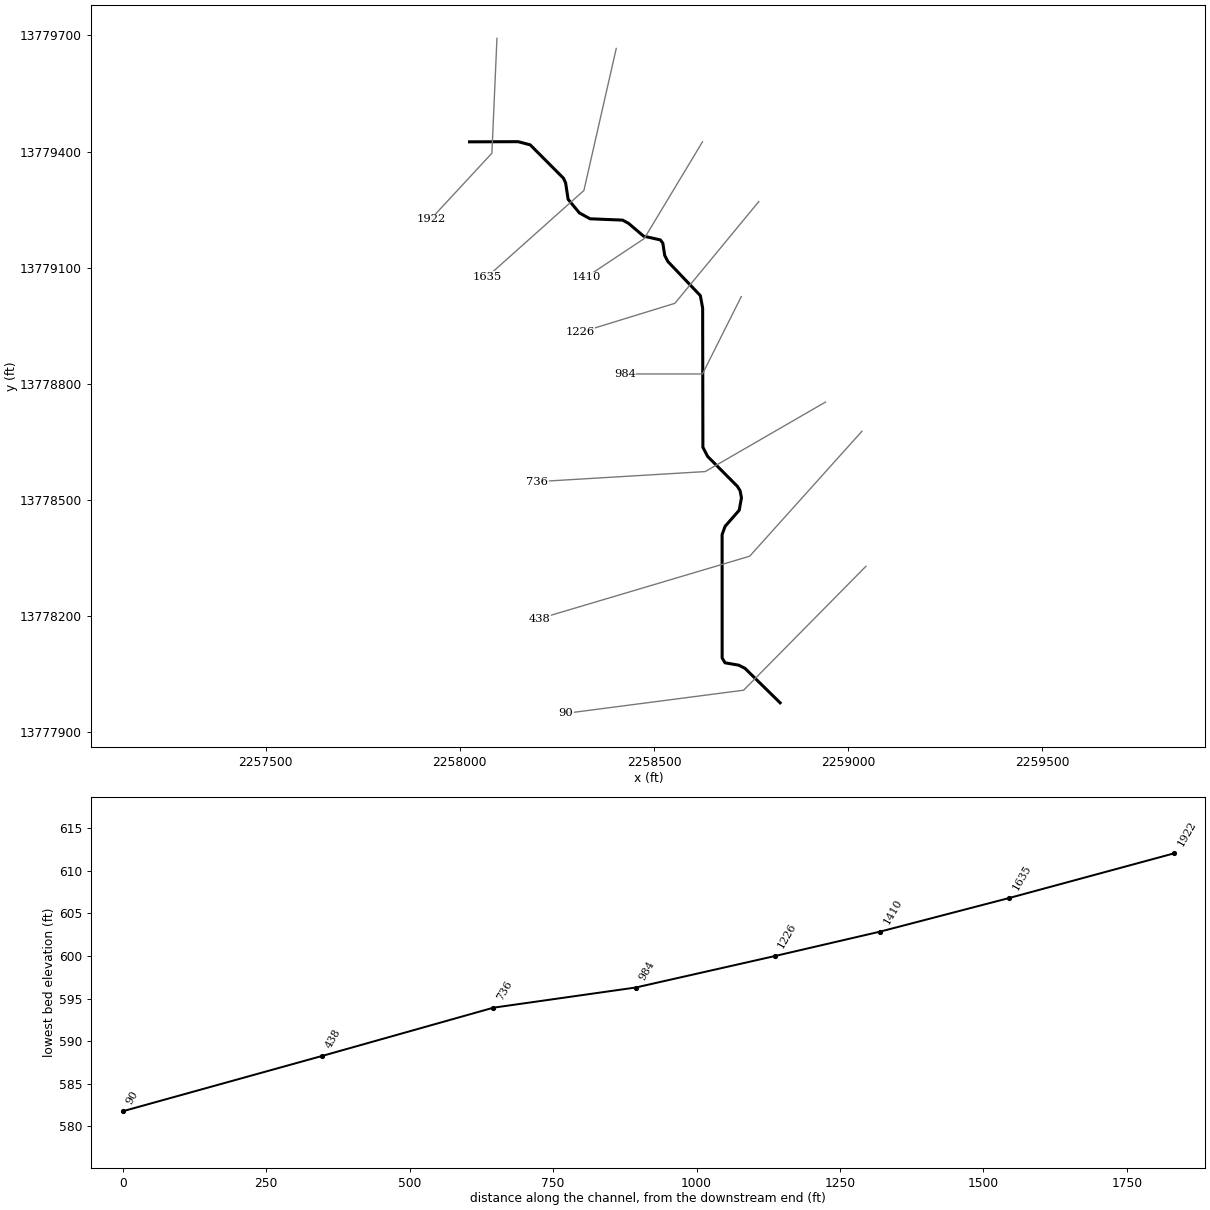
--- LONG TRIBUTARY 7.prj (project) ---

Proj Title=LONG TRIBUTARY 7 Base Level Engineering
Current Plan=p01
Default Exp/Contr=0.3,0.1
English Units
Geom File=g01
Flow File=f01
Plan File=p01
BEGIN DESCRIPTION:
LONG TRIBUTARY 7
END DESCRIPTION:

--- LONG TRIBUTARY 7.p01 (plan) ---

Plan Title=Multiple Run
Short Identifier=Multiple
Geom File=g01
Flow File=f01
Subcritical Flow
K Sum by GR= 0
Std Step Tol= 0.01
Critical Tol= 0.01
Num of Std Step Trials= 20
Max Error Tol= 0.3
Flow Tol Ratio= 0.001
Split Flow NTrial= 30
Split Flow Tol= 0.02
Split Flow Ratio= 0.02
Log Output Level= 0
Friction Slope Method= 1
Unsteady Friction Slope Method= 2
Unsteady Bridges Friction Slope Method= 1
Parabolic Critical Depth
Global Vel Dist=  1 , 1 , 1
Global Log Level= 0
CheckData=True
Encroach Param= -1, 0, 0, 0
BEGIN DESCRIPTION:
Multiple Run
END DESCRIPTION:

--- LONG TRIBUTARY 7.f01 (steady flow) ---

Flow Title=Multiple
Number of Profiles=7
Profile Names=10-year,25-year,50-year,1pct_min,100-year,1pct_plu,500-year
River Rch & RM= LONG TRIBUTARY 7,Reach-1,1922
     468     745     993     643    1284    2562    2117
Boundary for River Rch & Prof#=LONG TRIBUTARY 7,Reach-1,1
Up Type=0
Dn Type=3
Dn Slope=0.005
Boundary for River Rch & Prof#=LONG TRIBUTARY 7,Reach-1,2
Up Type=0
Dn Type=3
Dn Slope=0.005
Boundary for River Rch & Prof#=LONG TRIBUTARY 7,Reach-1,3
Up Type=0
Dn Type=3
Dn Slope=0.005
Boundary for River Rch & Prof#=LONG TRIBUTARY 7,Reach-1,4
Up Type=0
Dn Type=3
Dn Slope=0.005
Boundary for River Rch & Prof#=LONG TRIBUTARY 7,Reach-1,5
Up Type=0
Dn Type=3
Dn Slope=0.005
Boundary for River Rch & Prof#=LONG TRIBUTARY 7,Reach-1,6
Up Type=0
Dn Type=3
Dn Slope=0.005
Boundary for River Rch & Prof#=LONG TRIBUTARY 7,Reach-1,7
Up Type=0
Dn Type=3
Dn Slope=0.005

--- LONG TRIBUTARY 7.g01 (geometry) ---

Geom Title=Existing Conditions

River Reach=LONG TRIBUTARY 7,Reach-1
Reach XY= 30
      2258025.00     13779425.00      2258150.16     13779425.38
      2258181.22     13779417.22      2258266.84     13779331.05
      2258272.45     13779318.92      2258278.88     13779276.41
      2258307.87     13779241.30      2258335.33     13779226.10
      2258419.05     13779222.67      2258434.71     13779214.19
      2258473.16     13779181.28      2258516.52     13779171.49
      2258522.89     13779162.99      2258527.70     13779131.44
      2258535.91     13779115.60      2258619.53     13779027.45
      2258625.43     13778995.18      2258626.06     13778635.44
      2258638.40     13778611.69      2258714.79     13778534.67
      2258721.86     13778523.36      2258725.39     13778504.87
      2258719.65     13778472.83      2258683.19     13778431.08
      2258675.54     13778409.79      2258675.66     13778090.83
      2258683.09     13778078.37      2258718.45     13778072.27
      2258734.38     13778064.15      2258825.00     13777975.00

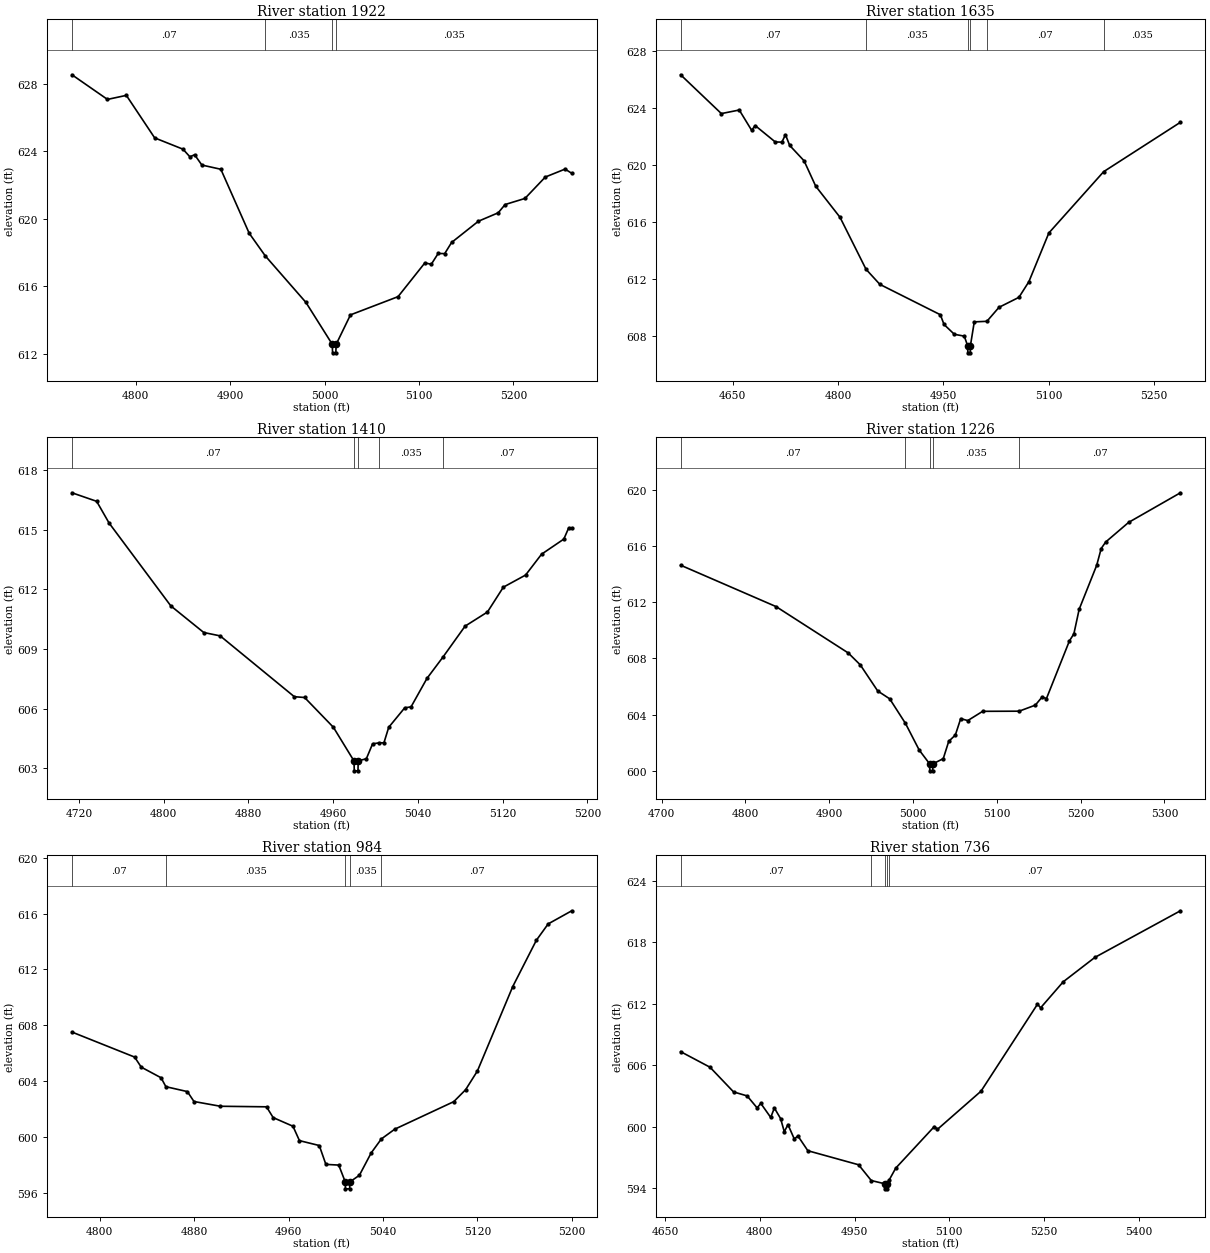
Type RM Length L Ch R = 1,1922,287,287,287
BEGIN DESCRIPTION:
LONG TRIBUTARY 7 4.0
END DESCRIPTION:
XS GIS Cut Line= 3
      2258095.57     13779692.52      2258082.55     13779395.61
      2257925.01     13779225.02
#Sta/Elev= 30
  4732.4  628.54  4770.0  627.08  4790.0  627.32  4820.0  624.80  4850.0  624.13
  4857.3  623.68  4862.3  623.80  4870.0  623.19  4890.1  622.94  4920.1  619.15
  4937.1  617.81  4980.2  615.05  5008.2  612.56  5008.4  612.06  5011.9  612.06
  5012.2  612.56  5027.4  614.31  5077.8  615.39  5106.2  617.39  5113.0  617.31
  5120.3  617.95  5127.2  617.94  5134.5  618.60  5162.9  619.86  5183.9  620.36
  5191.2  620.85  5212.2  621.21  5233.8  622.48  5254.7  622.95  5261.8  622.70
#Mann=4,-1,0
  4732.4    0.07       0  4937.1   0.035       0  5008.2   0.035       0
  5012.2   0.035       0
Bank Sta=5008.2,5012.2
Exp/Cntr=0.3,0.1

Type RM Length L Ch R = 1,1635,225,225,225
BEGIN DESCRIPTION:
A19869
END DESCRIPTION:
XS GIS Cut Line= 3
      2258402.86     13779666.41      2258319.53     13779299.25
      2258069.78     13779075.52
#Sta/Elev= 30
  4575.7  626.31  4633.7  623.59  4659.2  623.84  4676.8  622.42  4681.9  622.75
  4710.5  621.60  4719.9  621.59  4725.0  622.11  4731.0  621.36  4751.5  620.28
  4768.1  618.50  4802.7  616.32  4839.7  612.68  4859.4  611.62  4945.6  609.49
  4950.8  608.81  4965.5  608.12  4979.7  607.99  4984.4  607.32  4984.7  606.82
  4988.2  606.82  4988.4  607.32  4993.9  608.99  5011.9  609.03  5029.1  610.01
  5057.5  610.71  5071.7  611.81  5100.1  615.22  5178.2  619.52  5287.5  622.98
#Mann=6,-1,0
  4575.7    0.07       0  4839.7   0.035       0  4984.4   0.035       0
  4988.4   0.035       0  5011.9    0.07       0  5178.2   0.035       0
Bank Sta=4984.4,4988.4
Exp/Cntr=0.3,0.1

Type RM Length L Ch R = 1,1410,184,184,184
BEGIN DESCRIPTION:
LONG TRIBUTARY 7 3.0
END DESCRIPTION:
XS GIS Cut Line= 3
      2258624.99     13779424.98      2258475.00     13779175.00
      2258325.00     13779075.00
#Sta/Elev= 30
  4713.4  616.86  4736.7  616.43  4748.4  615.34  4806.7  611.17  4837.8  609.83
  4853.3  609.66  4923.3  606.60  4933.0  606.56  4960.2  605.06  4979.6  603.37
  4979.9  602.87  4983.4  602.87  4983.6  603.37  4991.3  603.48  4997.2  604.23
  5003.7  604.28  5007.9  604.28  5012.4  605.06  5027.5  606.04  5033.5  606.09
  5048.5  607.52  5063.7  608.60  5084.5  610.15  5105.6  610.86  5120.6  612.11
  5141.6  612.72  5156.7  613.77  5177.7  614.53  5182.2  615.08  5185.2  615.08
#Mann=5,-1,0
  4713.4    0.07       0  4979.6    0.05       0  4983.6    0.07       0
  5003.7   0.035       0  5063.7    0.07       0
Bank Sta=4979.6,4983.6
Exp/Cntr=0.3,0.1

Type RM Length L Ch R = 1,1226,242,242,242
BEGIN DESCRIPTION:
A19868
END DESCRIPTION:
XS GIS Cut Line= 3
      2258770.08     13779270.64      2258553.91     13779007.59
      2258309.56     13778932.20
#Sta/Elev= 30
  4722.8  614.64  4836.7  611.69  4922.7  608.39  4937.1  607.54  4957.9  605.68
  4972.2  605.12  4991.0  603.37  5007.4  601.47  5019.8  600.49  5020.0  599.99
  5023.5  599.99  5023.8  600.49  5036.1  600.86  5042.6  602.09  5050.5  602.54
  5056.9  603.71  5065.3  603.57  5083.1  604.23  5126.6  604.24  5145.9  604.67
  5154.0  605.25  5159.2  605.14  5186.6  609.25  5191.9  609.75  5198.2  611.50
  5219.1  614.63  5224.5  615.83  5229.8  616.29  5257.2  617.69  5319.0  619.80
#Mann=5,-1,0
  4722.8    0.07       0  4991.0   0.035       0  5019.8   0.035       0
  5023.8   0.035       0  5126.6    0.07       0
Bank Sta=5019.8,5023.8
Exp/Cntr=0.3,0.1

Type RM Length L Ch R = 1,984,248,248,248
BEGIN DESCRIPTION:
LONG TRIBUTARY 7 2.0
END DESCRIPTION:
XS GIS Cut Line= 3
      2258724.99     13779024.99      2258625.00     13778825.00
      2258424.99     13778825.00
#Sta/Elev= 30
  4776.4  607.52  4829.5  605.73  4835.1  605.01  4851.9  604.25  4856.0  603.61
  4874.2  603.26  4879.8  602.55  4902.2  602.21  4941.3  602.17  4946.9  601.40
  4963.7  600.78  4969.2  599.75  4986.0  599.40  4991.6  598.05  5002.5  598.00
  5008.0  596.80  5008.2  596.30  5011.7  596.30  5012.0  596.80  5020.0  597.27
  5030.0  598.87  5038.6  599.87  5050.0  600.57  5100.0  602.54  5110.0  603.39
  5120.0  604.73  5150.0  610.78  5170.0  614.09  5180.0  615.26  5200.0  616.20
#Mann=5,-1,0
  4776.4    0.07       0  4856.0   0.035       0  5008.0   0.035       0
  5012.0   0.035       0  5038.6    0.07       0
Bank Sta=5008,5012
Exp/Cntr=0.3,0.1

Type RM Length L Ch R = 1,736,298,298,298
BEGIN DESCRIPTION:
A19867
END DESCRIPTION:
XS GIS Cut Line= 3
      2258941.92     13778752.37      2258632.03     13778572.69
      2258199.82     13778546.65
#Sta/Elev= 30
  4674.6  607.32  4721.1  605.80  4758.4  603.39  4779.9  603.00  4795.7  601.83
  4801.5  602.27  4817.2  600.90  4823.0  601.82  4832.9  600.78  4838.7  599.50
  4844.5  600.20  4854.5  598.80  4860.3  599.09  4876.0  597.65  4956.3  596.28
  4976.4  594.74  4997.4  594.43  4997.6  593.93  5001.1  593.93  5001.4  594.43
  5004.7  594.79  5015.1  595.95  5076.2  600.01  5081.2  599.74  5150.1  603.46
  5239.5  611.95  5244.5  611.60  5280.3  614.14  5330.4  616.52  5465.8  621.07
#Mann=5,-1,0
  4674.6    0.07       0  4976.4   0.035       0  4997.4   0.035       0
  5001.4   0.035       0  5004.7    0.07       0
Bank Sta=4997.4,5001.4
Exp/Cntr=0.3,0.1

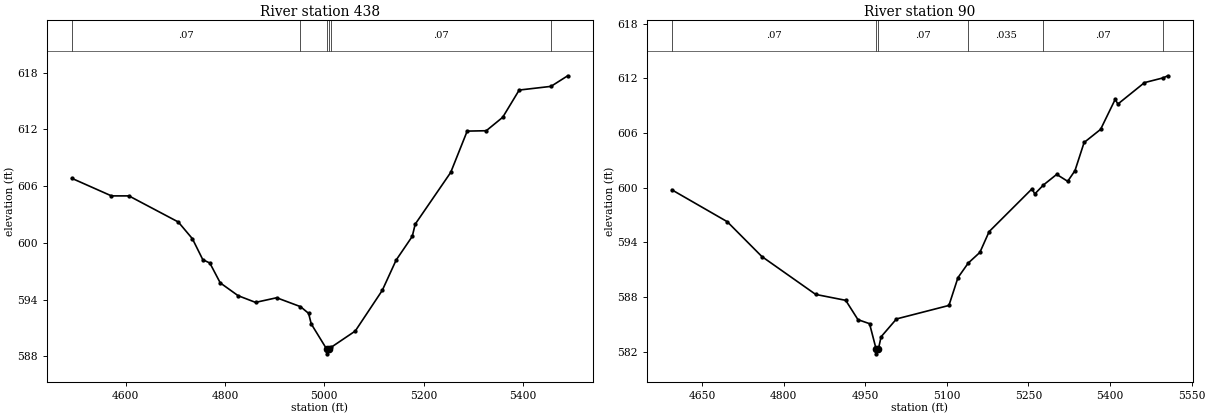
Type RM Length L Ch R = 1,438,348,348,348
BEGIN DESCRIPTION:
LONG TRIBUTARY 7 1.0
END DESCRIPTION:
XS GIS Cut Line= 3
      2259035.70     13778676.88      2258746.61     13778353.94
      2258204.99     13778192.50
#Sta/Elev= 30
  4491.7  606.83  4571.6  604.97  4606.8  604.97  4706.2  602.21  4734.6  600.44
  4755.5  598.23  4769.7  597.87  4790.7  595.77  4826.6  594.42  4861.7  593.71
  4904.3  594.20  4952.2  593.26  4968.6  592.55  4973.9  591.43  5005.0  588.77
  5005.3  588.27  5009.0  588.77  5014.2  588.97  5062.5  590.68  5116.9  594.98
  5144.8  598.18  5177.3  600.69  5183.2  601.98  5254.7  607.45  5287.9  611.82
  5326.3  611.86  5359.4  613.28  5392.6  616.16  5456.6  616.55  5490.3  617.67
#Mann=6,-1,0
  4491.7    0.07       0  4952.2   0.035       0  5005.0   0.035       0
  5009.0   0.035       0  5014.2    0.07       0  5456.6   0.035       0
Bank Sta=5005,5009
Exp/Cntr=0.3,0.1

Type RM Length L Ch R = 1,90,0,0,0
BEGIN DESCRIPTION:
A19866
END DESCRIPTION:
XS GIS Cut Line= 3
      2259046.12     13778327.92      2258730.99     13778007.59
      2258272.64     13777947.69
#Sta/Elev= 30
  4594.4  599.76  4696.3  596.26  4759.9  592.44  4858.9  588.28  4914.1  587.63
  4936.6  585.51  4957.9  585.07  4970.1  582.26  4970.3  581.76  4974.1  582.26
  4979.1  583.63  5007.4  585.59  5103.8  587.07  5120.4  590.12  5139.3  591.72
  5160.7  592.89  5177.7  595.17  5256.6  599.87  5261.6  599.30  5277.4  600.28
  5301.9  601.45  5322.1  600.69  5335.5  601.86  5352.3  604.95  5382.6  606.39
  5409.4  609.68  5414.4  609.17  5463.3  611.52  5497.5  612.04  5506.0  612.27
#Mann=6,-1,0
  4594.4    0.07       0  4970.1    0.05       0  4974.1    0.07       0
  5139.3   0.035       0  5277.4    0.07       0  5497.5   0.035       0
Bank Sta=4970.1,4974.1
Exp/Cntr=0.3,0.1

Chan Stop Cuts=-1