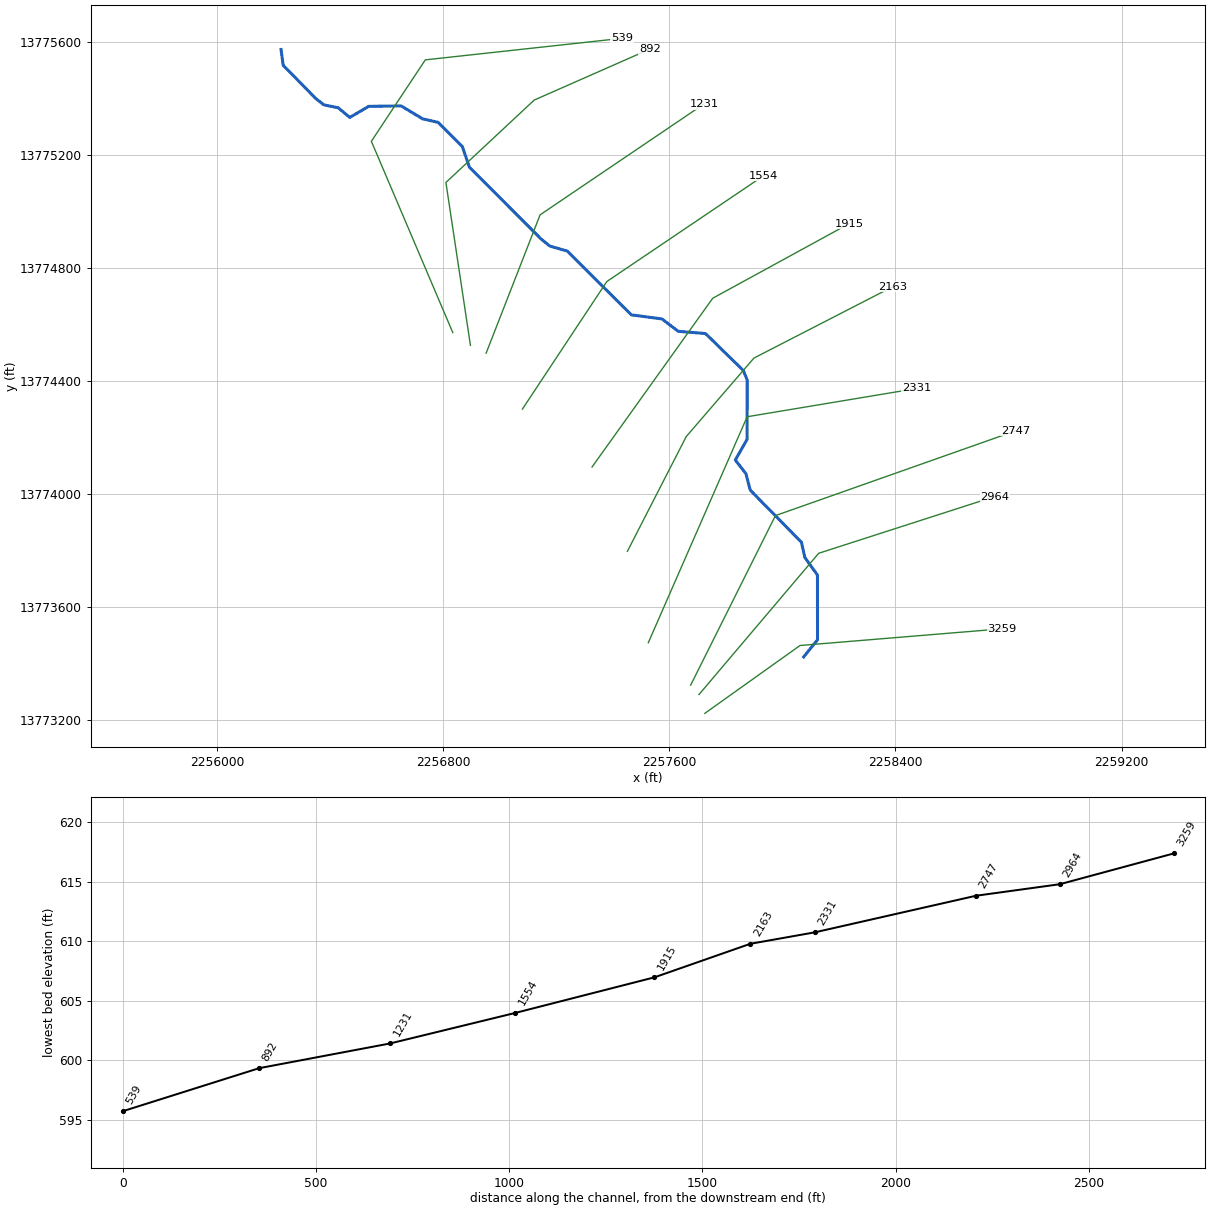
--- LONG TRIBUTARY 8.prj (project) ---

Proj Title=LONG TRIBUTARY 8 Base Level Engineering
Current Plan=p01
Default Exp/Contr=0.3,0.1
English Units
Geom File=g01
Flow File=f01
Plan File=p01
BEGIN DESCRIPTION:
LONG TRIBUTARY 8
END DESCRIPTION:

--- LONG TRIBUTARY 8.p01 (plan) ---

Plan Title=Multiple Run
Short Identifier=Multiple
Geom File=g01
Flow File=f01
Subcritical Flow
K Sum by GR= 0
Std Step Tol= 0.01
Critical Tol= 0.01
Num of Std Step Trials= 20
Max Error Tol= 0.3
Flow Tol Ratio= 0.001
Split Flow NTrial= 30
Split Flow Tol= 0.02
Split Flow Ratio= 0.02
Log Output Level= 0
Friction Slope Method= 1
Unsteady Friction Slope Method= 2
Unsteady Bridges Friction Slope Method= 1
Parabolic Critical Depth
Global Vel Dist=  1 , 1 , 1
Global Log Level= 0
CheckData=True
Encroach Param= -1, 0, 0, 0
BEGIN DESCRIPTION:
Multiple Run
END DESCRIPTION:

--- LONG TRIBUTARY 8.f01 (steady flow) ---

Flow Title=Multiple
Number of Profiles=7
Profile Names=10-year,25-year,50-year,1pct_min,100-year,1pct_plu,500-year
River Rch & RM= LONG TRIBUTARY 8,Reach-1,3259
     346     539     708     452     901    1798    1442
Boundary for River Rch & Prof#=LONG TRIBUTARY 8,Reach-1,1
Up Type=0
Dn Type=3
Dn Slope=0.005
Boundary for River Rch & Prof#=LONG TRIBUTARY 8,Reach-1,2
Up Type=0
Dn Type=3
Dn Slope=0.005
Boundary for River Rch & Prof#=LONG TRIBUTARY 8,Reach-1,3
Up Type=0
Dn Type=3
Dn Slope=0.005
Boundary for River Rch & Prof#=LONG TRIBUTARY 8,Reach-1,4
Up Type=0
Dn Type=3
Dn Slope=0.005
Boundary for River Rch & Prof#=LONG TRIBUTARY 8,Reach-1,5
Up Type=0
Dn Type=3
Dn Slope=0.005
Boundary for River Rch & Prof#=LONG TRIBUTARY 8,Reach-1,6
Up Type=0
Dn Type=3
Dn Slope=0.005
Boundary for River Rch & Prof#=LONG TRIBUTARY 8,Reach-1,7
Up Type=0
Dn Type=3
Dn Slope=0.005

--- LONG TRIBUTARY 8.g01 (geometry) ---

Geom Title=Existing Conditions

River Reach=LONG TRIBUTARY 8,Reach-1
Reach XY= 30
      2258075.00     13773425.00      2258124.04     13773485.40
      2258123.80     13773714.50      2258079.22     13773776.75
      2258066.86     13773831.06      2257885.75     13774015.32
      2257870.55     13774073.35      2257833.04     13774121.68
      2257874.82     13774194.98      2257875.04     13774405.02
      2257861.63     13774438.32      2257727.43     13774569.48
      2257630.98     13774577.36      2257573.40     13774621.14
      2257465.21     13774635.52      2257238.21     13774861.37
      2257176.65     13774878.98      2257144.84     13774904.62
      2256891.65     13775158.33      2256866.85     13775231.07
      2256781.07     13775316.87      2256726.75     13775329.22
      2256650.08     13775375.24      2256535.44     13775373.63
      2256468.38     13775334.41      2256427.28     13775368.59
      2256376.65     13775378.91      2256348.18     13775401.28
      2256232.76     13775518.79      2256225.00     13775575.00

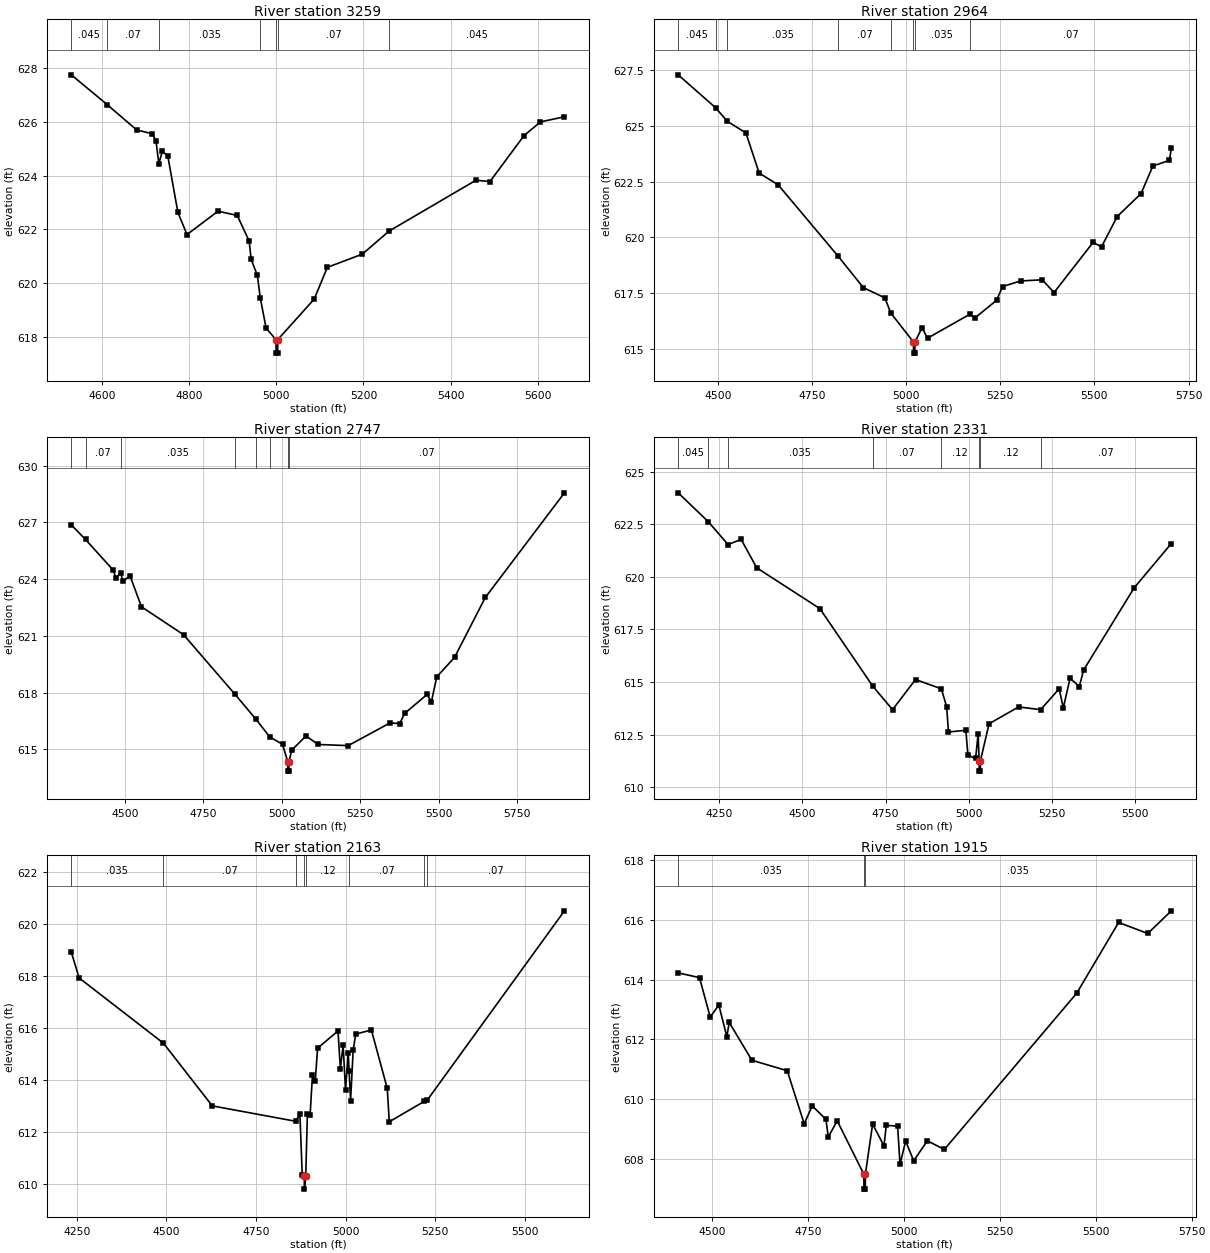
Type RM Length L Ch R = 1,3259,295,295,295
BEGIN DESCRIPTION:
LONG TRIBUTARY 8 3.0
END DESCRIPTION:
XS GIS Cut Line= 3
      2257725.00     13773225.00      2258062.13     13773465.28
      2258777.40     13773524.31
#Sta/Elev= 30
  4529.6  627.75  4612.0  626.64  4679.6  625.70  4715.2  625.56  4723.8  625.30
  4730.5  624.45  4738.4  624.90  4750.9  624.74  4774.2  622.63  4795.1  621.81
  4866.4  622.68  4910.3  622.52  4937.7  621.57  4942.3  620.89  4956.5  620.29
  4963.3  619.45  4976.6  618.33  4999.3  617.90  4999.6  617.40  5003.1  617.40
  5003.3  617.90  5087.0  619.41  5117.1  620.59  5197.3  621.08  5259.0  621.94
  5458.2  623.83  5490.3  623.78  5568.6  625.49  5606.3  626.00  5661.3  626.19
#Mann=7,-1,0
  4529.6   0.045       0  4612.0    0.07       0  4730.5   0.035       0
  4963.3    0.07       0  4999.3    0.05       0  5003.3    0.07       0
  5259.0   0.045       0
Bank Sta=4999.3,5003.3
Exp/Cntr=0.3,0.1

Type RM Length L Ch R = 1,2964,217,217,217
BEGIN DESCRIPTION:
A19876
END DESCRIPTION:
XS GIS Cut Line= 3
      2257704.47     13773291.64      2258128.10     13773791.67
      2258751.58     13773992.57
#Sta/Elev= 30
  4393.9  627.30  4493.5  625.82  4524.1  625.22  4573.9  624.69  4609.1  622.89
  4659.7  622.36  4818.4  619.17  4885.9  617.75  4943.1  617.29  4958.9  616.61
  5019.0  615.31  5019.3  614.81  5022.8  614.81  5023.0  615.31  5041.9  615.95
  5056.5  615.48  5168.3  616.55  5182.6  616.39  5239.9  617.18  5256.1  617.80
  5304.0  618.05  5361.2  618.10  5392.7  617.53  5496.4  619.78  5518.8  619.58
  5560.5  620.94  5623.8  621.97  5655.4  623.21  5699.3  623.46  5704.3  624.01
#Mann=8,-1,0
  4393.9   0.045       0  4493.5    0.07       0  4524.1   0.035       0
  4818.4    0.07       0  4958.9   0.035       0  5019.0   0.035       0
  5023.0   0.035       0  5168.3    0.07       0
Bank Sta=5019,5023
Exp/Cntr=0.3,0.1

Type RM Length L Ch R = 1,2747,416,416,416
BEGIN DESCRIPTION:
LONG TRIBUTARY 8 2.0
END DESCRIPTION:
XS GIS Cut Line= 3
      2257675.01     13773325.01      2257975.00     13773925.00
      2258825.01     13774225.00
#Sta/Elev= 30
  4329.2  626.87  4374.4  626.10  4463.3  624.47  4471.7  624.04  4486.1  624.34
  4494.1  623.90  4516.5  624.17  4552.8  622.54  4687.0  621.06  4850.3  617.92
  4918.1  616.58  4961.9  615.65  5002.7  615.26  5019.2  614.34  5019.5  613.84
  5023.0  613.84  5023.2  614.34  5031.8  614.95  5077.3  615.70  5116.7  615.25
  5212.1  615.19  5345.1  616.39  5376.0  616.36  5392.4  616.90  5463.5  617.90
  5477.2  617.51  5494.4  618.83  5551.0  619.86  5649.1  623.03  5901.4  628.57
#Mann=8,-1,0
  4329.2   0.045       0  4374.4    0.07       0  4486.1   0.035       0
  4850.3    0.07       0  4918.1   0.035       0  4961.9    0.07       0
  5019.2    0.05       0  5023.2    0.07       0
Bank Sta=5019.2,5023.2
Exp/Cntr=0.3,0.1

Type RM Length L Ch R = 1,2331,168,168,168
BEGIN DESCRIPTION:
LONG TRIBUTARY 8 1.0
END DESCRIPTION:
XS GIS Cut Line= 3
      2257525.01     13773475.01      2257875.00     13774275.00
      2258475.02     13774375.00
#Sta/Elev= 30
  4126.7  623.99  4217.6  622.61  4276.5  621.53  4315.8  621.78  4362.5  620.43
  4552.4  618.49  4711.1  614.81  4770.7  613.69  4839.7  615.12  4917.4  614.68
  4933.2  613.83  4938.7  612.63  4990.9  612.71  4997.2  611.53  5020.2  611.37
  5027.8  612.54  5030.8  611.27  5031.1  610.77  5034.6  610.77  5034.8  611.27
  5060.7  613.02  5149.4  613.82  5215.8  613.69  5271.1  614.68  5283.8  613.78
  5304.0  615.18  5331.9  614.79  5344.6  615.57  5496.7  619.48  5608.2  621.58
#Mann=8,-1,0
  4126.7   0.045       0  4217.6    0.07       0  4276.5   0.035       0
  4711.1    0.07       0  4917.4    0.12       0  5030.8    0.05       0
  5034.8    0.12       0  5215.8    0.07       0
Bank Sta=5030.8,5034.8
Exp/Cntr=0.3,0.1

Type RM Length L Ch R = 1,2163,248,248,248
BEGIN DESCRIPTION:
A19875
END DESCRIPTION:
XS GIS Cut Line= 4
      2257451.04     13773798.65      2257659.35     13774204.86
      2257898.94     13774482.64      2258390.99     13774735.60
#Sta/Elev= 30
  4234.5  618.91  4256.3  617.92  4491.7  615.41  4628.0  613.00  4860.4  612.41
  4872.6  612.67  4879.2  610.33  4884.9  610.30  4885.1  609.80  4888.9  610.30
  4893.5  612.68  4901.1  612.65  4907.7  614.19  4915.4  613.94  4922.0  615.22
  4979.0  615.88  4985.6  614.43  4993.3  615.34  4999.9  613.61  5007.5  615.03
  5010.0  614.34  5014.1  613.20  5021.3  615.14  5028.4  615.76  5072.1  615.92
  5116.5  613.67  5122.1  612.39  5220.4  613.18  5227.5  613.21  5611.1  620.50
#Mann=8,-1,0
  4234.5   0.035       0  4491.7    0.07       0  4860.4    0.12       0
  4884.9    0.05       0  4888.9    0.12       0  5010.0    0.07       0
  5220.4   0.035       0  5227.5    0.07       0
Bank Sta=4884.9,4888.9
Exp/Cntr=0.3,0.1

Type RM Length L Ch R = 1,1915,361,361,361
BEGIN DESCRIPTION:
A19874
END DESCRIPTION:
XS GIS Cut Line= 3
      2257326.03     13774097.24      2257753.10     13774694.44
      2258235.78     13774958.35
#Sta/Elev= 30
  4412.7  614.23  4468.2  614.07  4496.0  612.75  4518.6  613.15  4539.4  612.09
  4545.6  612.57  4604.6  611.30  4696.7  610.95  4740.9  609.17  4761.8  609.77
  4797.5  609.32  4803.6  608.73  4826.9  609.27  4896.2  607.48  4896.5  606.98
  4900.0  606.98  4900.2  607.48  4919.1  609.16  4948.6  608.43  4954.7  609.12
  4984.2  609.09  4990.4  607.81  5005.1  608.59  5026.0  607.93  5061.6  608.60
  5105.9  608.31  5450.7  613.55  5559.8  615.92  5635.7  615.55  5697.0  616.31
#Mann=3,-1,0
  4412.7   0.035       0  4896.2   0.035       0  4900.2   0.035       0
Bank Sta=4896.2,4900.2
Exp/Cntr=0.3,0.1

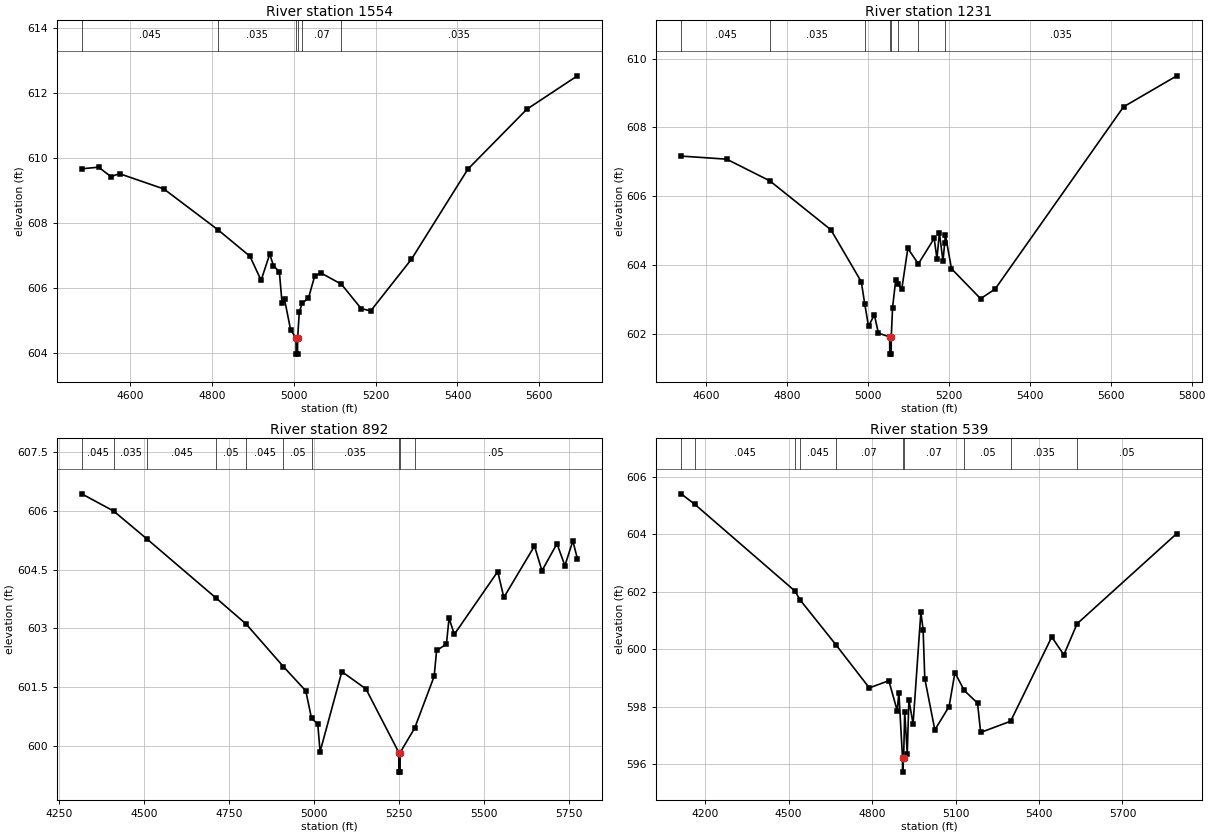
Type RM Length L Ch R = 1,1554,323,323,323
BEGIN DESCRIPTION:
A19873
END DESCRIPTION:
XS GIS Cut Line= 3
      2257079.49     13774302.09      2257378.10     13774753.47
      2257933.67     13775128.48
#Sta/Elev= 30
  4481.6  609.68  4522.9  609.73  4553.0  609.44  4574.1  609.53  4682.4  609.06
  4815.1  607.80  4892.8  606.99  4920.1  606.25  4941.2  607.06  4950.2  606.70
  4964.7  606.51  4971.3  605.55  4977.3  605.67  4992.3  604.72  5005.4  604.48
  5005.6  603.98  5009.1  603.98  5009.4  604.48  5013.4  605.27  5020.5  605.55
  5035.8  605.70  5050.8  606.37  5065.8  606.48  5116.4  606.13  5164.7  605.38
  5188.0  605.31  5287.6  606.90  5425.5  609.67  5569.4  611.51  5693.1  612.54
#Mann=6,-1,0
  4481.6   0.045       0  4815.1   0.035       0  5005.4   0.035       0
  5009.4   0.035       0  5020.5    0.07       0  5116.4   0.035       0
Bank Sta=5005.4,5009.4
Exp/Cntr=0.3,0.1

Type RM Length L Ch R = 1,1231,339,339,339
BEGIN DESCRIPTION:
A19872
END DESCRIPTION:
XS GIS Cut Line= 3
      2256951.02     13774500.00      2257141.99     13774989.58
      2257721.82     13775381.92
#Sta/Elev= 30
  4537.7  607.17  4650.4  607.08  4757.1  606.45  4908.0  605.03  4983.2  603.52
  4991.8  602.87  5001.0  602.23  5015.4  602.56  5025.5  602.03  5053.3  601.92
  5053.6  601.42  5057.1  601.42  5057.3  601.92  5060.5  602.77  5068.4  603.58
  5072.8  603.46  5083.4  603.32  5098.3  604.49  5124.2  604.04  5163.4  604.78
  5170.2  604.19  5176.3  604.94  5185.2  604.12  5189.3  604.64  5191.2  604.88
  5206.2  603.90  5278.1  603.03  5314.1  603.31  5631.6  608.60  5763.3  609.50
#Mann=8,-1,0
  4537.7   0.045       0  4757.1   0.035       0  4991.8    0.07       0
  5053.3    0.05       0  5057.3    0.07       0  5072.8   0.035       0
  5124.2    0.05       0  5189.3   0.035       0
Bank Sta=5053.3,5057.3
Exp/Cntr=0.3,0.1

Type RM Length L Ch R = 1,892,353,353,353
BEGIN DESCRIPTION:
A19871
END DESCRIPTION:
XS GIS Cut Line= 4
      2256895.47     13774527.74      2256808.66     13775104.17
      2257121.16     13775395.83      2257530.40     13775576.18
#Sta/Elev= 30
  4317.7  606.43  4411.8  605.99  4510.9  605.27  4713.5  603.77  4801.5  603.11
  4910.6  602.03  4976.7  601.41  4993.5  600.71  5011.8  600.57  5018.7  599.86
  5082.7  601.90  5153.5  601.46  5250.2  599.84  5250.4  599.34  5253.9  599.34
  5254.2  599.84  5296.8  600.46  5354.1  601.78  5361.4  602.44  5390.2  602.60
  5397.9  603.26  5413.5  602.85  5541.1  604.45  5559.0  603.79  5649.2  605.10
  5671.1  604.47  5715.3  605.16  5738.6  604.60  5762.0  605.23  5775.3  604.78
#Mann=10,-1,0
  4317.7   0.045       0  4411.8   0.035       0  4510.9   0.045       0
  4713.5    0.05       0  4801.5   0.045       0  4910.6    0.05       0
  4993.5   0.035       0  5250.2   0.035       0  5254.2   0.035       0
  5296.8    0.05       0
Bank Sta=5250.2,5254.2
Exp/Cntr=0.3,0.1

Type RM Length L Ch R = 1,539,0,0,0
BEGIN DESCRIPTION:
A19870
END DESCRIPTION:
XS GIS Cut Line= 4
      2256832.97     13774572.91      2256544.77     13775250.00
      2256735.74     13775538.19      2257431.79     13775614.38
#Sta/Elev= 30
  4113.6  605.40  4163.4  605.03  4522.6  602.02  4542.1  601.70  4670.0  600.15
  4790.1  598.65  4860.2  598.90  4890.3  597.86  4896.3  598.48  4909.4  596.22
  4909.6  595.72  4913.4  596.22  4917.3  597.82  4926.4  596.36  4932.4  598.23
  4947.4  597.40  4975.4  601.28  4983.5  600.67  4989.5  598.97  5025.6  597.19
  5076.8  598.00  5097.8  599.18  5131.4  598.56  5179.1  598.12  5190.3  597.10
  5298.0  597.49  5445.9  600.42  5489.4  599.80  5536.9  600.88  5895.4  604.02
#Mann=10,-1,0
  4113.6   0.035       0  4163.4   0.045       0  4522.6    0.05       0
  4542.1   0.045       0  4670.0    0.07       0  4909.4    0.05       0
  4913.4    0.07       0  5131.4    0.05       0  5298.0   0.035       0
  5536.9    0.05       0
Bank Sta=4909.4,4913.4
Exp/Cntr=0.3,0.1

Chan Stop Cuts=-1