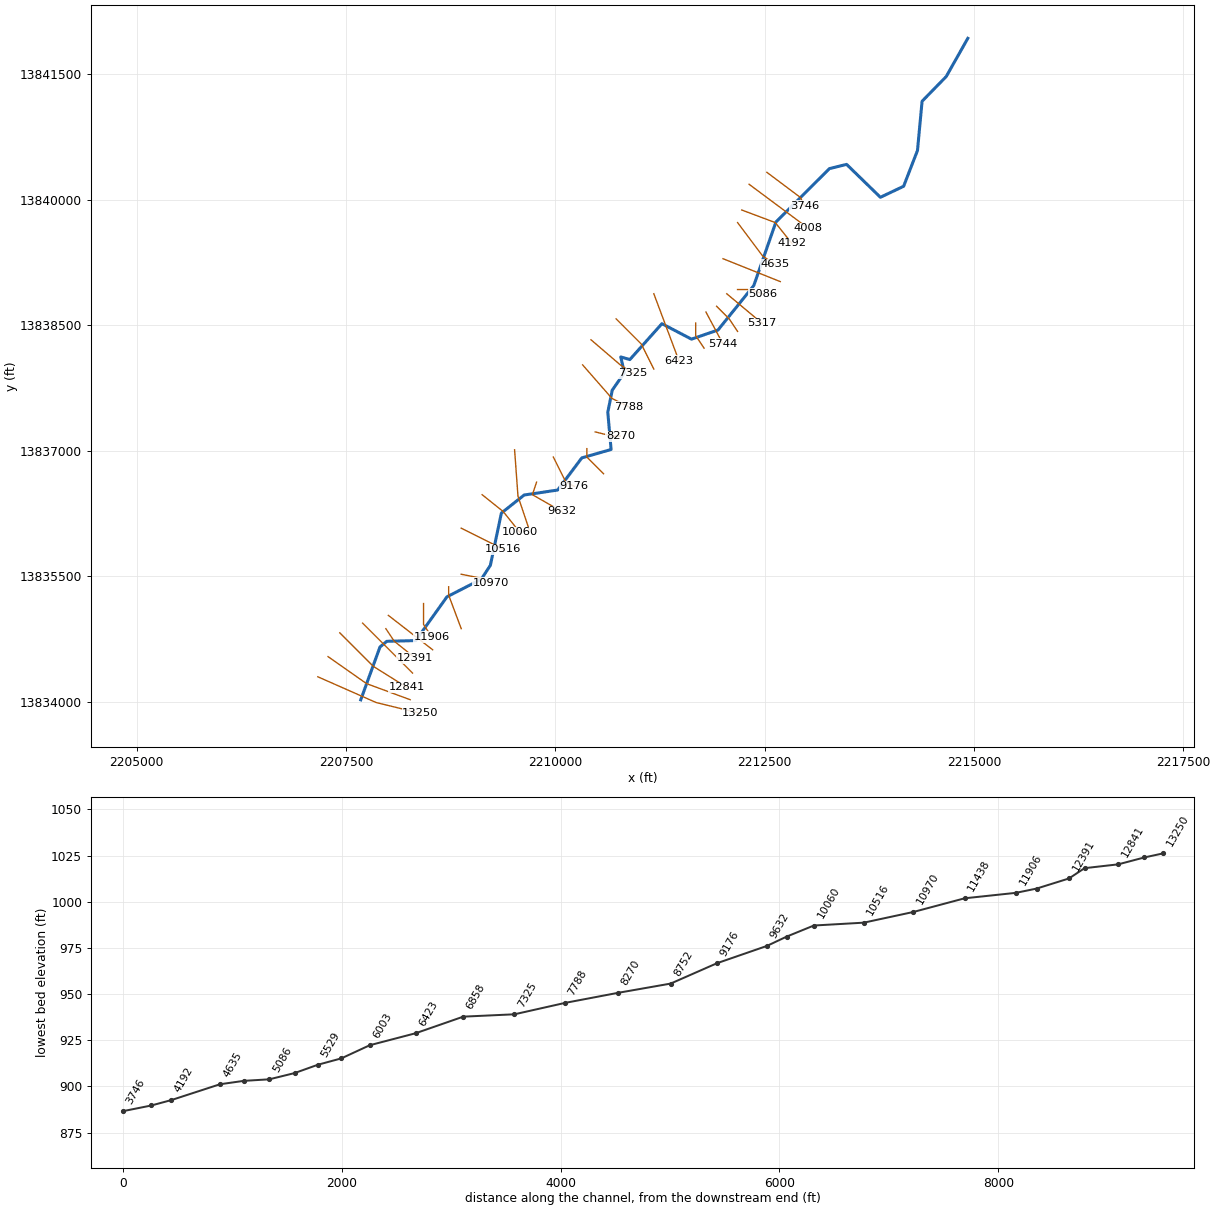
--- Little Bear Creek.prj (project) ---

Proj Title=Little Bear Creek Base Level Engineering
Current Plan=p01
Default Exp/Contr=0.3,0.1
English Units
Geom File=g01
Flow File=f01
Plan File=p01
Y Axis Title=Elevation
X Axis Title(PF)=Main Channel Distance
X Axis Title(XS)=Station
BEGIN DESCRIPTION:
Little Bear Creek
END DESCRIPTION:
DSS Export Rating Curves= 0
DSS Export Rating Curve Sorted= 0
DSS Export Volume Flow Curves= 0
DXF OffsetX= 0
DXF OffsetY= 0
DXF ScaleX= 1
DXF ScaleY= 10

--- Little Bear Creek.p01 (plan) ---

Plan Title=Multiple Run
Short Identifier=Multiple
Geom File=g01
Flow File=f01
Subcritical Flow
K Sum by GR= 0
Std Step Tol= 0.01
Critical Tol= 0.01
Num of Std Step Trials= 20
Max Error Tol= 0.3
Flow Tol Ratio= 0.001
Split Flow NTrial= 30
Split Flow Tol= 0.02
Split Flow Ratio= 0.02
Log Output Level= 0
Friction Slope Method= 1
Unsteady Friction Slope Method= 2
Unsteady Bridges Friction Slope Method= 1
Parabolic Critical Depth
Global Vel Dist=  1 , 1 , 1
Global Log Level= 0
CheckData=True
Encroach Param= -1, 0, 0, 0
BEGIN DESCRIPTION:
Multiple Run
END DESCRIPTION:

--- Little Bear Creek.f01 (steady flow) ---

Flow Title=Multiple
Number of Profiles=7
Profile Names=10-year,25-year,50-year,1pct_min,100-year,1pct_plu,500-year
River Rch & RM= Little Bear Cree,Reach-1,13250
    1157    1964    2732    1841    3674    7331    6573
River Rch & RM= Little Bear Cree,Reach-1,11438
    1391    2381    3329    2253    4496    8970    8113
River Rch & RM= Little Bear Cree,Reach-1,9176
    1656    2857    4016    2730    5448   10869    9925
River Rch & RM= Little Bear Cree,Reach-1,7325
    1932    3343    4710    3208    6400   12770   11696
River Rch & RM= Little Bear Cree,Reach-1,2400
    2455    4299    6107    4189    8359   16678   15505
Boundary for River Rch & Prof#=Little Bear Cree,Reach-1,1
Up Type=0
Dn Type=3
Dn Slope=0.005
Boundary for River Rch & Prof#=Little Bear Cree,Reach-1,2
Up Type=0
Dn Type=3
Dn Slope=0.005
Boundary for River Rch & Prof#=Little Bear Cree,Reach-1,3
Up Type=0
Dn Type=3
Dn Slope=0.005
Boundary for River Rch & Prof#=Little Bear Cree,Reach-1,4
Up Type=0
Dn Type=3
Dn Slope=0.005
Boundary for River Rch & Prof#=Little Bear Cree,Reach-1,5
Up Type=0
Dn Type=3
Dn Slope=0.005
Boundary for River Rch & Prof#=Little Bear Cree,Reach-1,6
Up Type=0
Dn Type=3
Dn Slope=0.005
Boundary for River Rch & Prof#=Little Bear Cree,Reach-1,7
Up Type=0
Dn Type=3
Dn Slope=0.005

--- Little Bear Creek.g01 (geometry) ---

Geom Title=Existing Conditions
Program Version=4.10

River Reach=Little Bear Cree,Reach-1
Reach XY= 30
        2207675.       13834025.      2207904.48     13834655.28
      2207985.43     13834723.96      2208331.52     13834732.68
      2208704.84     13835255.37      2209114.23      13835465.3
      2209222.93     13835630.86      2209354.61     13836255.16
      2209626.58     13836471.18      2210027.47     13836530.45
       2210315.2     13836914.52      2210664.66     13837014.88
      2210625.51     13837459.78      2210678.55     13837723.53
       2210823.2     13837931.11      2210780.11     13838120.34
      2210888.72      13838088.4      2211271.77     13838517.17
        2211625.     13838332.56      2211941.68     13838441.64
      2212369.16     13838972.71      2212633.14     13839731.06
      2213272.45     13840369.27      2213477.44     13840419.61
      2213881.08     13840026.64      2214158.37     13840158.29
      2214323.78      13840585.5      2214378.75     13841173.45
      2214667.14     13841468.83        2214925.       13841925.

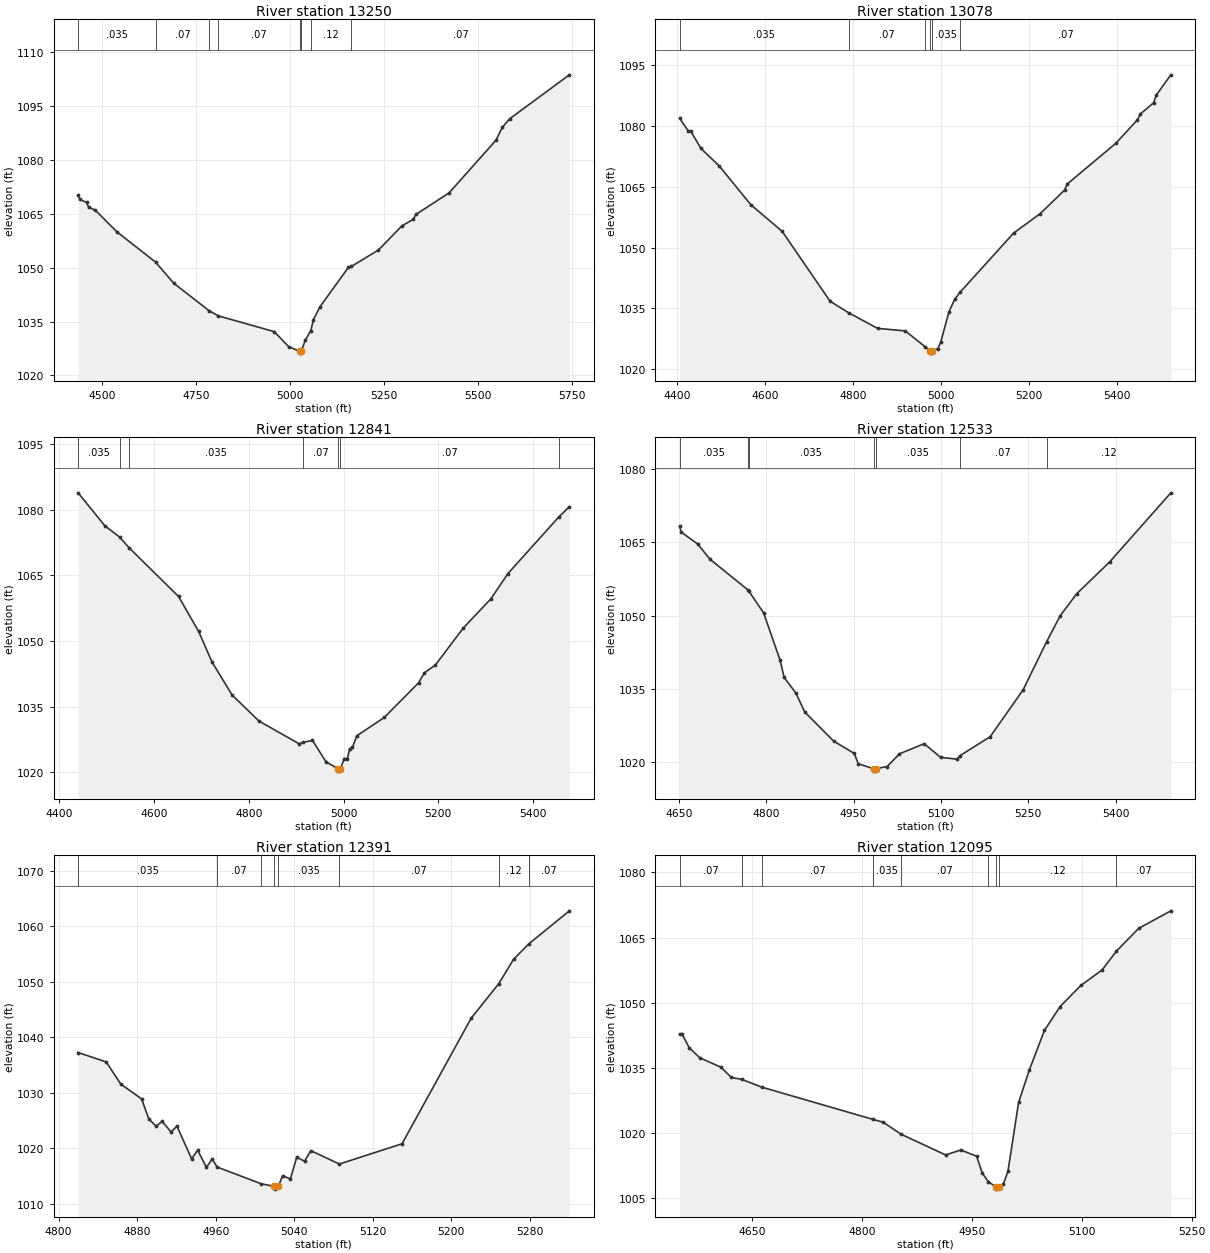
Type RM Length L Ch R = 1 ,13250   ,172,172,172
BEGIN DESCRIPTION:
A19644
END DESCRIPTION:
XS GIS Cut Line= 3
      2207162.42     13834300.41      2207858.75     13833992.99
      2208388.44     13833863.35
#Sta/Elev= 30
  4436.4 1070.23  4441.1 1068.97  4458.9 1068.14  4464.4  1066.8  4482.2 1065.99
  4539.8 1059.94  4642.6 1051.52  4690.6 1045.66  4785.4 1037.96  4809.7 1036.56
  4957.9 1032.18  4996.7 1027.97  5025.9  1026.7  5026.1  1026.2  5029.9  1026.7
  5040.4 1029.75  5055.3 1032.49  5062.3 1035.54  5079.9 1039.13  5155.3 1050.09
  5163.3 1050.34  5234.9 1054.88    5298 1061.67  5327.6 1063.43  5334.5 1064.79
  5422.9  1070.8  5547.8 1085.48  5564.3 1089.01  5584.3 1091.45  5742.9 1103.67
#Mann= 8 ,-1 , 0
  4436.4    .035       0  4642.6     .07       0  4785.4    .035       0
  4809.7     .07       0  5025.9     .05       0  5029.9     .07       0
  5055.3     .12       0  5163.3     .07       0
Bank Sta=5025.9,5029.9
XS Rating Curve= 0 ,0
Exp/Cntr=0.3,0.1

Type RM Length L Ch R = 1 ,13078   ,237,237,237
BEGIN DESCRIPTION:
A19643
END DESCRIPTION:
XS GIS Cut Line= 3
      2207284.67     13834541.15      2207743.93     13834218.93
      2208266.23     13834026.31
#Sta/Elev= 30
  4405.4 1081.92  4424.5 1078.84  4430.6 1078.75  4454.1 1074.44  4495.9  1070.1
  4567.4 1060.58  4638.9    1054  4747.8 1036.79  4789.8 1033.95  4855.9 1030.09
  4918.9 1029.47  4964.8  1025.5  4976.2 1024.49  4976.5 1023.99  4980.3 1024.49
  4993.2 1025.13  4999.5 1026.67  5018.3  1034.2  5031.5 1037.27  5044.2 1039.07
  5165.2 1053.56  5226.1 1058.39  5281.6 1064.21  5287.3 1065.66    5398 1075.72
  5447.2 1081.51  5453.6 1082.92    5484 1085.71  5489.8 1087.56  5523.1 1092.59
#Mann= 6 ,-1 , 0
  4405.4    .035       0  4789.8     .07       0  4964.8    .035       0
  4976.2    .035       0  4980.3    .035       0  5044.2     .07       0
Bank Sta=4976.2,4980.3
XS Rating Curve= 0 ,0
Exp/Cntr=0.3,0.1

Type RM Length L Ch R = 1 ,12841   ,308,308,308
BEGIN DESCRIPTION:
Little Bear Creek 28.0
END DESCRIPTION:
XS GIS Cut Line= 3
      2207425.03     13834824.97        2207825.       13834425.
      2208224.96     13834175.02
#Sta/Elev= 30
  4439.4 1083.84  4495.9 1076.31    4527 1073.74  4546.9 1071.31  4651.5 1060.17
  4693.9 1052.19  4722.2 1045.19  4764.6 1037.66  4821.2 1031.73  4906.1 1026.52
    4914 1026.83  4934.3 1027.31  4962.6 1022.42  4988.9 1020.78  4989.1 1020.28
    4993 1020.78  5001.5 1023.16    5008 1023.16  5012.7 1025.41  5018.6 1025.69
    5028 1028.36  5085.8 1032.53  5158.3 1040.45  5170.7 1042.75  5193.7  1044.5
  5252.7 1052.97  5311.1 1059.65    5347 1065.41  5453.8 1078.26  5476.7 1080.68
#Mann= 7 ,-1 , 0
  4439.4    .035       0    4527     .07       0  4546.9    .035       0
    4914     .07       0  4988.9     .05       0    4993     .07       0
  5453.8     .12       0
Bank Sta=4988.9,4993
XS Rating Curve= 0 ,0
Exp/Cntr=0.3,0.1

Type RM Length L Ch R = 1 ,12533   ,142,142,142
BEGIN DESCRIPTION:
A19642
END DESCRIPTION:
XS GIS Cut Line= 2
      2207697.28     13834941.19      2208293.58     13834344.89
#Sta/Elev= 30
  4651.3 1068.25  4654.1 1067.09  4682.4 1064.64  4703.6 1061.52  4768.6 1055.27
    4770 1055.05  4795.5 1050.58  4823.8 1040.91  4830.8 1037.37    4851 1034.15
  4866.2 1030.29  4915.7 1024.35  4951.1 1021.82  4958.1 1019.71  4984.4  1018.7
  4984.6  1018.2  4988.5  1018.7  5007.6 1019.14  5028.8 1021.74  5071.3 1023.81
  5099.5 1021.01  5127.8 1020.65  5132.1 1021.32  5184.4 1025.23    5241 1034.82
  5281.3 1044.65  5304.6 1049.96  5332.9 1054.46  5389.5 1060.97  5494.6 1075.11
#Mann= 7 ,-1 , 0
  4651.3    .035       0  4768.6     .12       0    4770    .035       0
  4984.4    .035       0  4988.5    .035       0  5132.1     .07       0
  5281.3     .12       0
Bank Sta=4984.4,4988.5
XS Rating Curve= 0 ,0
Exp/Cntr=0.3,0.1

Type RM Length L Ch R = 1 ,12391   ,296,296,296
BEGIN DESCRIPTION:
Little Bear Creek 27.0
END DESCRIPTION:
XS GIS Cut Line= 3
      2207974.99     13834875.01        2208075.       13834725.
      2208325.04     13834524.97
#Sta/Elev= 30
  4819.8 1037.24  4848.4 1035.55  4863.4 1031.53  4884.4  1028.9  4891.9 1025.24
  4899.4 1023.96  4905.4 1024.85  4914.5 1022.92  4920.5 1023.98  4935.5 1018.07
  4941.5 1019.65  4950.5 1016.57  4956.5 1018.05  4961.4 1016.61  5006.4 1013.59
  5019.7 1013.13  5019.9 1012.63  5023.8 1013.13  5028.1 1015.03  5036.1 1014.47
  5042.5 1018.36  5050.5 1017.67  5056.9 1019.56    5086 1017.15  5149.8  1020.8
  5220.2 1043.41  5248.4 1049.66  5263.4 1054.03  5279.1 1056.83  5320.3 1062.77
#Mann= 8 ,-1 , 0
  4819.8    .035       0  4961.4     .07       0  5006.4    .035       0
  5019.7     .05       0  5023.8    .035       0    5086     .07       0
  5248.4     .12       0  5279.1     .07       0
Bank Sta=5019.7,5023.8
XS Rating Curve= 0 ,0
Exp/Cntr=0.3,0.1

Type RM Length L Ch R = 1 ,12095   ,189,189,189
BEGIN DESCRIPTION:
A19641
END DESCRIPTION:
XS GIS Cut Line= 2
      2208004.68     13835033.82      2208534.34     13834622.69
#Sta/Elev= 30
    4551 1042.88  4554.1 1042.88  4564.1  1039.7  4578.3 1037.38  4607.3 1035.19
  4621.7 1032.84  4636.3 1032.36  4663.2  1030.6  4814.8 1023.19    4829 1022.52
  4853.4 1019.77  4914.1 1015.01  4934.9 1016.15  4956.5  1014.7  4963.9 1010.93
  4972.1  1008.9  4982.6 1007.65  4982.9 1007.15  4986.8 1007.65  4992.9 1008.29
  4999.2 1011.25  5013.7 1027.07  5028.2 1034.47    5049 1043.65  5070.4 1049.14
  5098.7 1053.98  5127.7 1057.55  5147.1 1061.85  5177.5 1067.09  5221.5 1071.14
#Mann= 9 ,-1 , 0
    4551     .07       0  4636.3    .035       0  4663.2     .07       0
  4814.8    .035       0  4853.4     .07       0  4972.1     .12       0
  4982.6     .05       0  4986.8     .12       0  5147.1     .07       0
Bank Sta=4982.6,4986.8
XS Rating Curve= 0 ,0
Exp/Cntr=0.3,0.1

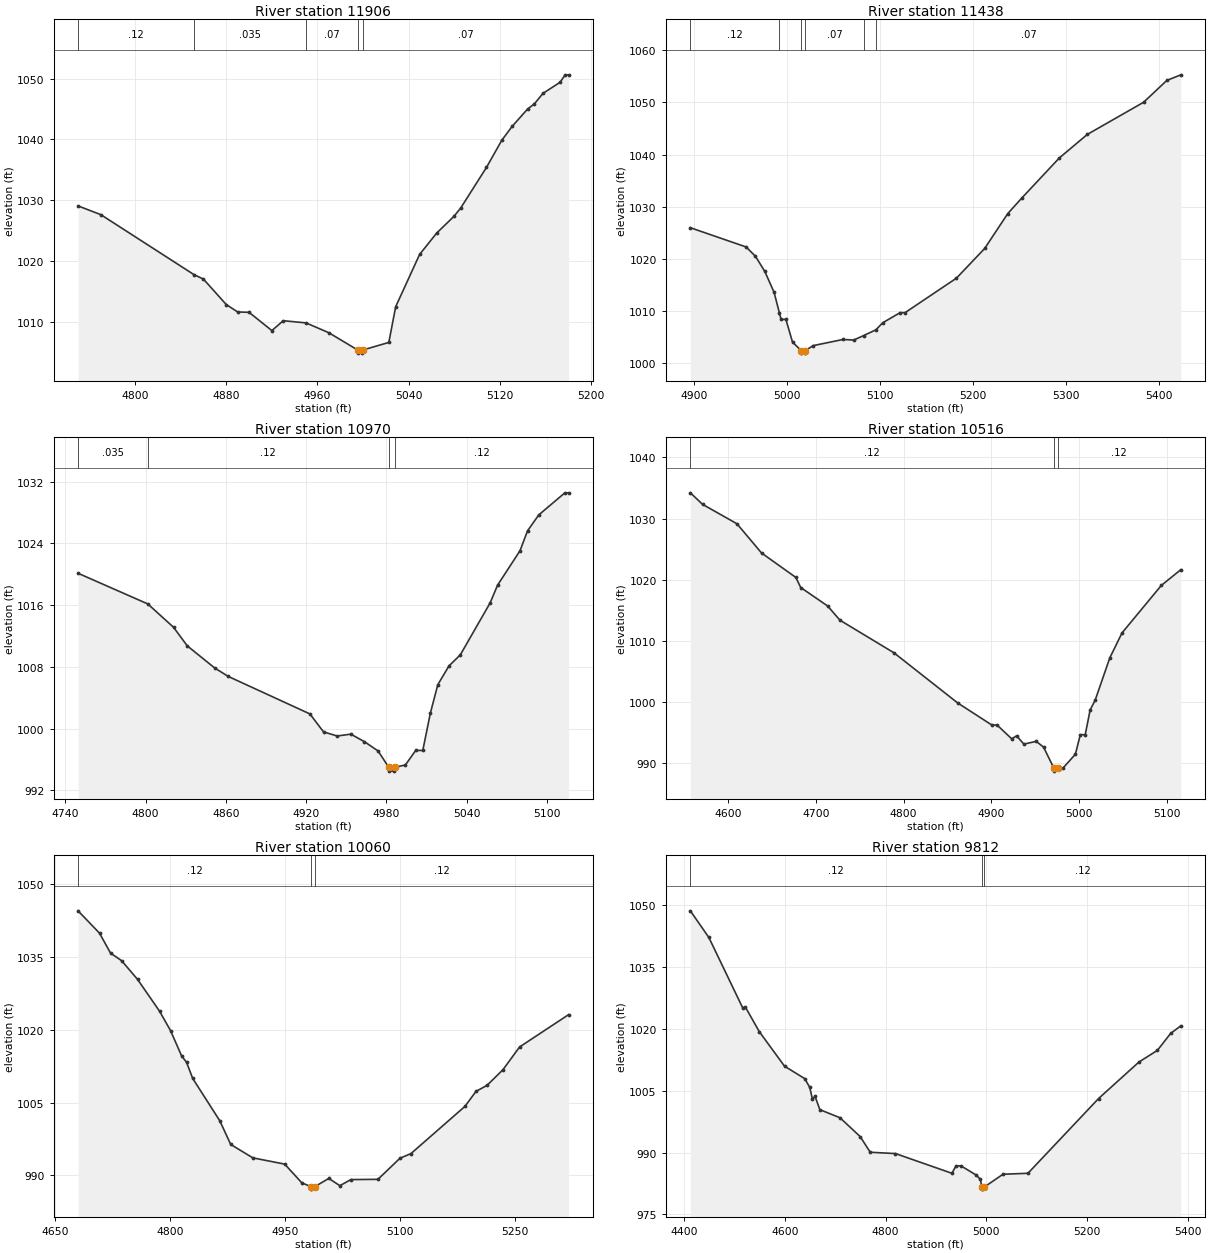
Type RM Length L Ch R = 1 ,11906   ,468,468,468
BEGIN DESCRIPTION:
Little Bear Creek 26.0
END DESCRIPTION:
XS GIS Cut Line= 3
        2208425.     13835175.03        2208425.       13834925.
      2208524.99     13834775.01
#Sta/Elev= 30
    4750 1029.05    4770 1027.61  4851.6 1017.76    4860 1017.01    4880 1012.83
    4890 1011.61    4900 1011.55    4920 1008.55    4930 1010.17    4950 1009.81
    4970 1008.19  4995.4 1005.34  4995.7 1004.84  4999.3 1004.84  4999.6 1005.34
  5022.6  1006.6  5028.6 1012.47  5049.6 1021.07  5064.6 1024.59  5079.7 1027.33
  5085.7 1028.72  5108.2 1035.37  5121.7 1039.85  5130.7 1042.12  5144.3 1044.98
  5150.3 1045.84  5157.8 1047.56  5172.8 1049.38  5177.3 1050.61  5180.3 1050.61
#Mann= 5 ,-1 , 0
    4750     .12       0  4851.6    .035       0    4950     .07       0
  4995.4     .05       0  4999.6     .07       0
Bank Sta=4995.4,4999.6
XS Rating Curve= 0 ,0
Exp/Cntr=0.3,0.1

Type RM Length L Ch R = 1 ,11438   ,468,468,468
BEGIN DESCRIPTION:
Little Bear Creek 25.0
END DESCRIPTION:
XS GIS Cut Line= 3
        2208725.     13835374.98        2208725.       13835275.
      2208875.01     13834874.98
#Sta/Elev= 30
  4896.1 1025.96  4956.1 1022.26  4966.1 1020.47  4976.1 1017.58  4986.1 1013.56
  4991.9 1009.54  4993.6 1008.36  4998.8 1008.36  5005.9 1004.01  5015.2 1002.39
  5015.5 1001.89  5019.4 1001.89  5019.7 1002.39  5028.1 1003.33  5060.2 1004.51
  5071.7  1004.4  5082.4 1005.26  5095.5 1006.36  5102.9 1007.72  5121.6 1009.66
  5126.9 1009.66  5182.1 1016.28  5212.4 1021.97  5237.3 1028.68  5252.4 1031.67
  5292.5 1039.32  5322.7 1043.86  5383.2 1050.03  5408.2 1054.23  5423.3  1055.3
#Mann= 6 ,-1 , 0
  4896.1     .12       0  4991.9     .07       0  5015.2     .05       0
  5019.7     .07       0  5082.4    .035       0  5095.5     .07       0
Bank Sta=5015.2,5019.7
XS Rating Curve= 0 ,0
Exp/Cntr=0.3,0.1

Type RM Length L Ch R = 1 ,10970   ,454,454,454
BEGIN DESCRIPTION:
Little Bear Creek 24.0
END DESCRIPTION:
XS GIS Cut Line= 3
      2208875.03     13835524.99        2209125.       13835475.
      2209224.98     13835425.01
#Sta/Elev= 30
  4749.5 1020.12  4801.6 1016.15  4820.9 1013.12  4831.1 1010.72  4851.5 1007.87
  4861.6 1006.77  4922.8  1001.9    4933  999.57  4943.2  999.04  4953.4  999.28
  4963.6   998.3  4973.8   997.1  4981.7  994.99  4982.1  994.49    4986  994.49
  4986.3  994.99  4994.2  995.29  5001.9  997.17  5007.2  997.17  5012.8 1001.96
  5018.4 1005.68  5026.8 1008.13  5035.2 1009.54  5057.5 1016.27  5063.1 1018.58
  5079.9 1023.05  5085.5 1025.62  5093.9 1027.68  5113.4 1030.54  5116.2 1030.54
#Mann= 4 ,-1 , 0
  4749.5    .035       0  4801.6     .12       0  4981.7     .05       0
  4986.3     .12       0
Bank Sta=4981.7,4986.3
XS Rating Curve= 0 ,0
Exp/Cntr=0.3,0.1

Type RM Length L Ch R = 1 ,10516   ,456,456,456
BEGIN DESCRIPTION:
Little Bear Creek 23.0
END DESCRIPTION:
XS GIS Cut Line= 3
      2208874.99     13836075.01        2209275.       13835875.
      2209374.97     13835825.01
#Sta/Elev= 30
  4556.9 1034.22  4570.9 1032.33    4610 1029.16    4638 1024.38  4677.1 1020.38
  4682.7 1018.73  4713.4  1015.7  4727.4 1013.38  4788.9 1008.05  4861.6  999.84
  4900.7  996.21  4906.3  996.25  4923.1  993.98  4928.7  994.46    4937  993.11
    4951  993.56  4959.4  992.62  4971.1  989.19  4971.4  988.69  4975.7  989.19
  4981.8  989.23  4995.7  991.46  5001.3  994.65  5006.9  994.65  5012.5  998.72
  5018.1 1000.25  5034.9 1007.22  5048.8  1011.3  5093.6 1019.07  5115.9 1021.66
#Mann= 3 ,-1 , 0
  4556.9     .12       0  4971.1     .05       0  4975.7     .12       0
Bank Sta=4971.1,4975.7
XS Rating Curve= 0 ,0
Exp/Cntr=0.3,0.1

Type RM Length L Ch R = 1 ,10060   ,248,248,248
BEGIN DESCRIPTION:
Little Bear Creek 22.0
END DESCRIPTION:
XS GIS Cut Line= 3
      2209125.02     13836474.98        2209375.       13836275.
      2209575.01     13836024.99
#Sta/Elev= 30
  4680.1 1044.54  4708.1 1039.93  4722.5 1035.82  4736.9 1034.26  4757.7 1030.41
  4786.5 1023.83  4800.9  1019.8  4815.3  1014.6  4821.7  1013.3  4829.7 1009.98
    4865 1001.26  4879.4  996.35  4908.2  993.59  4949.8   992.3  4972.2  988.43
  4984.3  987.64  4984.6  987.14    4989  987.64  5007.4  989.35  5021.8  987.85
  5036.2  989.11  5071.5  989.16  5100.3  993.51  5114.7  994.48  5185.1 1004.21
  5199.5  1007.3  5213.9 1008.54  5234.7 1011.77  5256.4 1016.46  5320.4 1023.13
#Mann= 3 ,-1 , 0
  4680.1     .12       0  4984.3     .05       0    4989     .12       0
Bank Sta=4984.3,4989
XS Rating Curve= 0 ,0
Exp/Cntr=0.3,0.1

Type RM Length L Ch R = 1 ,9812    ,180,180,180
BEGIN DESCRIPTION:
A19640
END DESCRIPTION:
XS GIS Cut Line= 3
      2209512.21     13837011.69      2209552.96     13836456.14
      2209686.27     13836059.91
#Sta/Elev= 30
  4411.7 1048.61  4448.5 1042.15  4515.9 1025.05  4520.9 1025.32  4548.8 1019.31
  4598.9 1010.95    4639 1007.93    4649 1005.82  4654.5 1002.91  4659.5 1003.67
  4669.1 1000.41  4709.2  998.44  4749.3  993.88  4769.3  990.08  4819.5  989.76
  4931.6  984.98  4939.8  986.76  4949.8  986.77  4980.5  984.51  4988.3  983.49
  4991.2  981.64  4991.5  981.14  4995.9  981.64  5033.2  984.75  5082.8  984.98
  5223.2 1003.11  5303.4 1011.95  5340.1 1014.78  5366.4 1018.89  5386.8 1020.73
#Mann= 3 ,-1 , 0
  4411.7     .12       0  4991.2     .05       0  4995.9     .12       0
Bank Sta=4991.2,4995.9
XS Rating Curve= 0 ,0
Exp/Cntr=0.3,0.1

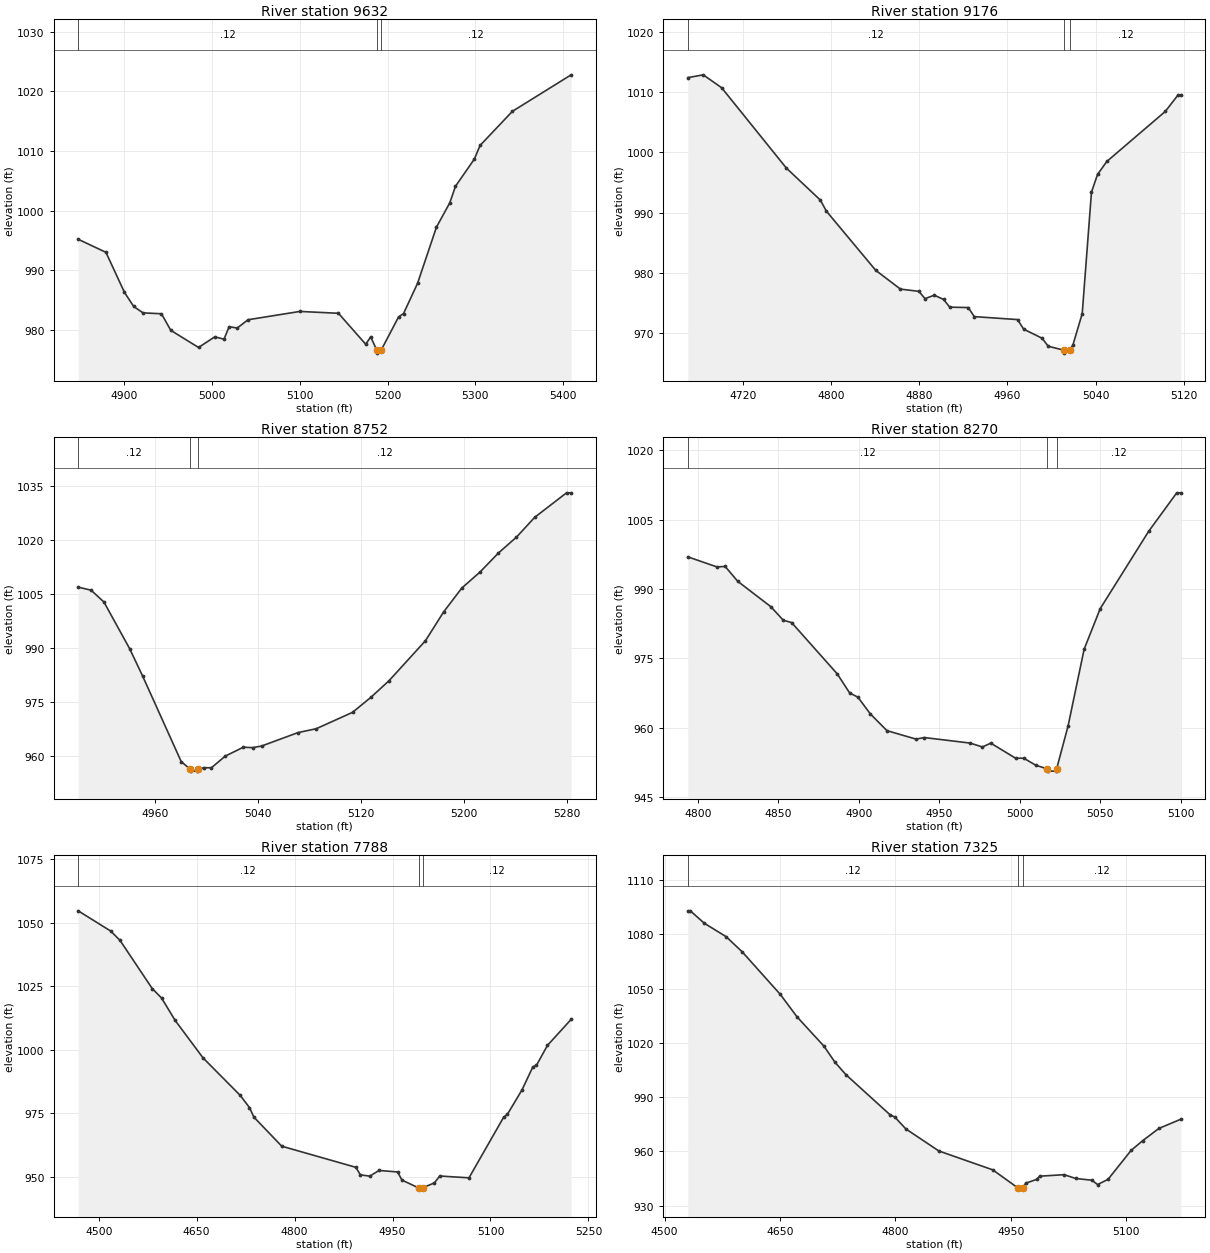
Type RM Length L Ch R = 1 ,9632    ,456,456,456
BEGIN DESCRIPTION:
Little Bear Creek 21.0
END DESCRIPTION:
XS GIS Cut Line= 3
      2209774.99     13836624.98        2209725.       13836475.
        2210075.       13836275.
#Sta/Elev= 30
  4847.8  995.19  4879.4     993  4900.5  986.28    4911  983.92  4921.6  982.85
  4942.6   982.7  4953.2  979.92  4984.8  977.05  5003.3  978.83  5013.8  978.44
  5019.6  980.53  5028.9  980.31  5041.2   981.7  5100.2  983.09  5144.1  982.78
  5175.1  977.59  5180.8  978.83  5187.7   976.6  5188.1   976.1  5192.7   976.6
  5212.5  982.16  5218.2  982.74  5234.1  987.79  5255.7  997.24  5270.8 1001.29
  5277.3 1004.07  5298.9 1008.66  5305.3 1010.92  5342.1 1016.64    5409 1022.76
#Mann= 3 ,-1 , 0
  4847.8     .12       0  5187.7     .05       0  5192.7     .12       0
Bank Sta=5187.7,5192.7
XS Rating Curve= 0 ,0
Exp/Cntr=0.3,0.1

Type RM Length L Ch R = 1 ,9176    ,424,424,424
BEGIN DESCRIPTION:
Little Bear Creek 20.0
END DESCRIPTION:
XS GIS Cut Line= 3
        2209975.       13836925.        2210125.       13836625.
      2210224.99     13836575.01
#Sta/Elev= 30
  4670.1 1012.39  4684.1 1012.86  4700.8 1010.72  4759.5  997.41  4790.3  992.11
  4795.9  990.25  4840.6  980.46    4863  977.35  4879.7  976.98  4885.3  975.77
  4893.7  976.34  4902.1  975.64  4907.7  974.36  4924.5  974.29    4930  972.79
  4969.2   972.3  4974.8  970.71  4991.5  969.21  4997.1  967.88    5011  967.24
  5011.5  966.74  5016.8  967.24  5019.5  968.11  5027.9  973.29  5036.3  993.42
  5041.8  996.35  5050.2   998.5  5103.3  1006.8  5114.5 1009.44  5117.3 1009.44
#Mann= 3 ,-1 , 0
  4670.1     .12       0    5011     .05       0  5016.8     .12       0
Bank Sta=5011,5016.8
XS Rating Curve= 0 ,0
Exp/Cntr=0.3,0.1

Type RM Length L Ch R = 1 ,8752    ,482,482,482
BEGIN DESCRIPTION:
Little Bear Creek 19.0
END DESCRIPTION:
XS GIS Cut Line= 3
        2210375.     13837025.01        2210375.       13836925.
      2210575.03     13836724.97
#Sta/Elev= 30
  4900.4 1006.85  4910.4 1006.01  4920.4 1002.72  4940.4  989.72  4950.4  982.17
  4980.4  958.36  4987.5  956.19    4988  955.69  4992.9  955.69  4993.3  956.19
  4997.9  956.63  5003.9  956.63  5014.6  959.86  5028.7  962.34  5035.8  962.22
  5042.8  962.66  5071.1   966.4  5085.3  967.48  5113.5  972.04  5127.7   976.2
  5141.8  980.82  5170.1  991.94  5184.3  999.99  5198.4 1006.61  5212.5 1011.05
  5226.7 1016.31  5240.8 1020.75    5255 1026.27  5279.7 1033.08  5283.3 1033.08
#Mann= 3 ,-1 , 0
  4900.4     .12       0  4987.5     .05       0  4993.3     .12       0
Bank Sta=4987.5,4993.3
XS Rating Curve= 0 ,0
Exp/Cntr=0.3,0.1

Type RM Length L Ch R = 1 ,8270    ,482,482,482
BEGIN DESCRIPTION:
Little Bear Creek 18.0
END DESCRIPTION:
XS GIS Cut Line= 3
      2210474.96     13837225.01        2210675.       13837175.
        2210775.       13837175.
#Sta/Elev= 30
  4793.7  996.94  4811.8  994.76  4816.9  994.87  4824.7  991.66  4845.3  986.17
    4853  983.25  4858.2  982.74  4886.5  971.68  4894.2  967.57  4899.4  966.62
  4907.1  963.02  4917.4  959.41  4935.5  957.58  4940.6  957.92    4969  956.73
  4976.7  955.89  4981.9  956.71  4997.3  953.46  5002.4  953.46  5009.9  951.93
  5016.9  951.17  5017.4  950.67  5022.3  950.67  5022.8  951.17  5029.9  960.42
  5039.9  977.02  5049.9  985.78  5079.9 1002.42  5097.4 1010.76  5099.9 1010.76
#Mann= 3 ,-1 , 0
  4793.7     .12       0  5016.9     .05       0  5022.8     .12       0
Bank Sta=5016.9,5022.8
XS Rating Curve= 0 ,0
Exp/Cntr=0.3,0.1

Type RM Length L Ch R = 1 ,7788    ,463,463,463
BEGIN DESCRIPTION:
Little Bear Creek 17.0
END DESCRIPTION:
XS GIS Cut Line= 3
      2210324.99     13838025.01        2210675.       13837625.
      2210874.97     13837525.01
#Sta/Elev= 30
  4468.5  1054.6  4518.3 1046.65  4532.6 1042.98  4581.9 1024.06  4596.2 1020.33
  4617.1 1011.51  4659.8  996.79  4716.7  982.08  4730.9  977.28  4737.6  973.55
  4780.3  962.11  4893.7  953.82  4900.8  950.86  4915.1  950.34  4929.3  952.58
  4957.8  951.99  4964.4  948.79  4989.8  945.74  4990.3  945.24    4996  945.74
    5014  947.68  5022.4  950.39  5067.1  949.68  5120.2   973.5  5125.8  974.58
  5148.2  984.18  5164.9  993.25  5170.5  993.91  5187.3 1001.72  5223.6 1011.96
#Mann= 3 ,-1 , 0
  4468.5     .12       0  4989.8     .05       0    4996     .12       0
Bank Sta=4989.8,4996
XS Rating Curve= 0 ,0
Exp/Cntr=0.3,0.1

Type RM Length L Ch R = 1 ,7325    ,467,467,467
BEGIN DESCRIPTION:
Little Bear Creek 16.0
END DESCRIPTION:
XS GIS Cut Line= 3
      2210425.03     13838324.98        2210775.       13838025.
      2210924.98     13837925.01
#Sta/Elev= 30
  4530.1 1093.02  4533.4 1093.02  4551.5 1086.17    4580 1078.71  4600.9 1070.32
  4650.3 1046.85  4672.2 1034.36  4707.3 1018.11  4721.6  1009.2  4735.9 1002.33
  4792.9  980.29  4799.5  978.86  4813.8  972.35  4856.6  960.18  4926.8  949.72
    4960  939.56  4960.5  939.06  4966.2  939.56  4969.6  942.35  4983.9  944.45
  4987.8  946.22  5019.6  947.05  5034.6  944.95  5055.6  943.99  5063.2   941.6
  5076.7  944.47  5106.7  960.48  5121.7  965.84  5142.8  972.63  5171.3  977.72
#Mann= 3 ,-1 , 0
  4530.1     .12       0    4960     .05       0  4966.2     .12       0
Bank Sta=4960,4966.2
XS Rating Curve= 0 ,0
Exp/Cntr=0.3,0.1

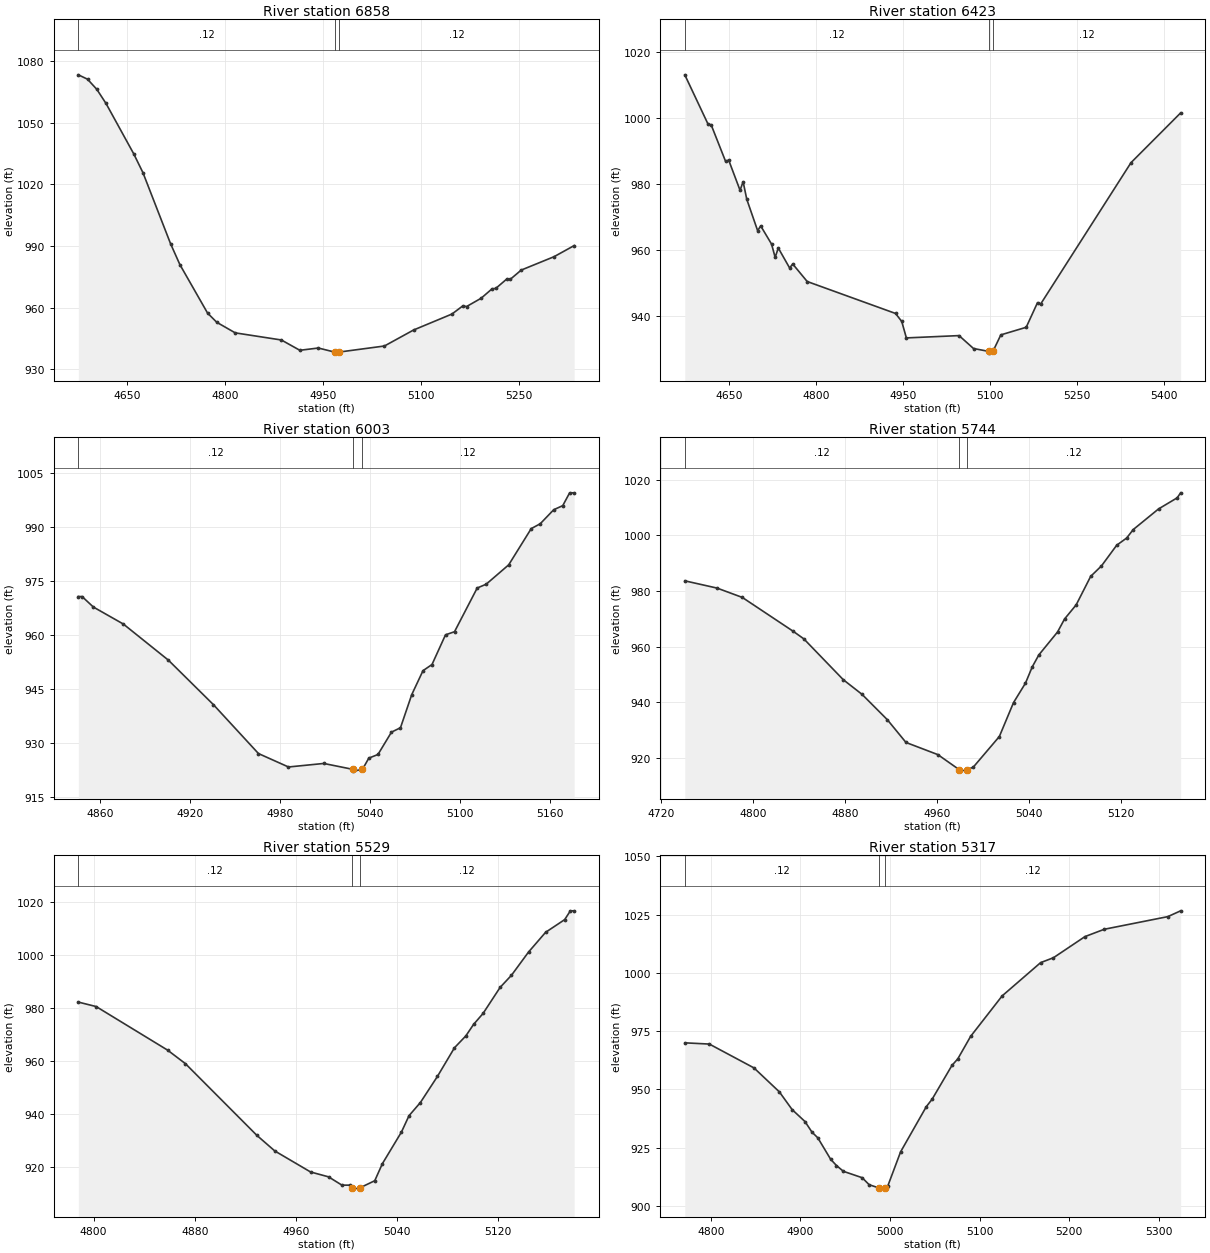
Type RM Length L Ch R = 1 ,6858    ,435,435,435
BEGIN DESCRIPTION:
Little Bear Creek 15.0
END DESCRIPTION:
XS GIS Cut Line= 3
        2210725.       13838575.        2211025.       13838275.
      2211175.01     13837974.97
#Sta/Elev= 30
  4575.5 1073.34  4589.6 1071.21  4603.8 1066.28  4617.9  1059.4  4660.4 1034.85
  4674.5 1025.68  4716.9  991.02  4731.1   980.9  4773.5   957.3  4787.6  952.81
  4815.9  947.66  4886.6  944.19  4914.9  939.17  4943.2  940.28  4968.3  938.29
  4968.8  937.79  4974.6  938.29  5044.5  941.26  5089.2  949.06  5147.9  956.82
  5164.7  960.82  5170.3  960.47  5192.6  964.51  5209.4  969.11    5215  969.29
  5231.8  973.84  5237.3  973.73  5254.1  978.24  5304.4  984.76  5335.2  990.17
#Mann= 3 ,-1 , 0
  4575.5     .12       0  4968.3     .05       0  4974.6     .12       0
Bank Sta=4968.3,4974.6
XS Rating Curve= 0 ,0
Exp/Cntr=0.3,0.1

Type RM Length L Ch R = 1 ,6423    ,420,420,420
BEGIN DESCRIPTION:
Little Bear Creek 14.0
END DESCRIPTION:
XS GIS Cut Line= 3
      2211175.01     13838874.97        2211325.       13838475.
      2211475.01     13838074.97
#Sta/Elev= 30
  4573.7 1013.13  4613.7  998.21  4619.1  997.99    4644   986.9  4649.3   987.3
  4668.9  978.15  4674.2  980.75  4680.5  975.42  4699.2  965.92  4704.5  967.35
  4723.2  961.85  4729.4  957.82  4734.8  960.66  4754.3  954.62  4759.7  955.81
  4784.6  950.51  4936.8  940.83  4947.5  938.42  4955.5  933.42  5046.3  934.12
  5071.2  930.21  5098.2  929.31  5098.7  928.81  5104.6  929.31  5118.3  934.34
    5162  936.64  5181.5  944.11  5186.9  943.68  5342.6  986.52  5428.1 1001.59
#Mann= 3 ,-1 , 0
  4573.7     .12       0  5098.2     .05       0  5104.6     .12       0
Bank Sta=5098.2,5104.6
XS Rating Curve= 0 ,0
Exp/Cntr=0.3,0.1

Type RM Length L Ch R = 1 ,6003    ,259,259,259
BEGIN DESCRIPTION:
Little Bear Creek 13.0
END DESCRIPTION:
XS GIS Cut Line= 3
        2211675.     13838524.98        2211675.       13838375.
      2211775.02     13838224.97
#Sta/Elev= 30
  4845.6  970.79  4848.1  970.79  4855.6  967.88  4875.6  963.15  4905.6  953.12
  4935.6  940.76  4965.6  927.18  4985.6  923.45  5009.1  924.43  5028.4   922.8
  5028.9   922.3  5034.9   922.8  5039.1  925.91  5045.2  926.92  5054.2  933.13
  5060.2  934.35  5067.7  943.54  5075.2   950.2  5081.2  951.91  5090.2  960.16
  5096.2  961.02  5111.3  973.16  5117.3  974.22  5132.3   979.6  5147.3  989.66
  5153.3  991.01  5162.3  994.91  5168.3  996.04  5172.9   999.6  5175.9   999.6
#Mann= 3 ,-1 , 0
  4845.6     .12       0  5028.4     .05       0  5034.9     .12       0
Bank Sta=5028.4,5034.9
XS Rating Curve= 0 ,0
Exp/Cntr=0.3,0.1

Type RM Length L Ch R = 1 ,5744    ,215,215,215
BEGIN DESCRIPTION:
A19639
END DESCRIPTION:
XS GIS Cut Line= 2
      2211797.58     13838656.27      2212000.65     13838275.99
#Sta/Elev= 30
  4740.9  983.62    4769     981  4790.9  977.65  4834.8  965.57  4844.4  962.75
  4878.7  948.06    4895   942.8    4917  933.68  4933.2   925.5  4960.9  921.13
  4979.6  915.69  4980.1  915.19  4986.1  915.69  4991.7  916.61  5014.4  927.64
  5026.7  939.82  5037.1  946.83    5043  952.68  5048.7  956.96    5065  965.23
  5071.1   969.9  5081.2  974.99  5093.8  985.22  5103.2  988.99  5116.4  996.41
  5125.1  999.02  5130.8 1002.05  5152.8 1009.47    5169 1013.46    5172 1015.26
#Mann= 3 ,-1 , 0
  4740.9     .12       0  4979.6     .05       0  4986.1     .12       0
Bank Sta=4979.6,4986.1
XS Rating Curve= 0 ,0
Exp/Cntr=0.3,0.1

Type RM Length L Ch R = 1 ,5529    ,212,212,212
BEGIN DESCRIPTION:
Little Bear Creek 12.0
END DESCRIPTION:
XS GIS Cut Line= 3
      2211925.02     13838724.98        2212075.       13838575.
      2212175.01     13838424.98
#Sta/Elev= 30
  4787.9  982.17    4802  980.49  4858.6  964.06  4872.7  958.96  4929.3  931.93
  4943.4   926.1  4971.7  918.19  4985.9  916.36  4996.5  913.23    5003  913.23
  5004.3  912.23  5004.8  911.73  5010.8  912.23  5022.5   914.9  5028.5  921.29
  5043.6  933.21  5049.6  939.38  5058.6  944.34  5072.1  954.18  5085.6  964.98
  5094.6  969.45  5100.7  973.77  5108.2  977.89  5121.7   987.7  5130.7  992.28
  5144.2 1001.02  5157.7 1008.45  5172.8 1013.23  5177.3 1016.54  5180.3 1016.54
#Mann= 3 ,-1 , 0
  4787.9     .12       0  5004.3     .05       0  5010.8     .12       0
Bank Sta=5004.3,5010.8
XS Rating Curve= 0 ,0
Exp/Cntr=0.3,0.1

Type RM Length L Ch R = 1 ,5317    ,231,231,231
BEGIN DESCRIPTION:
A19638
END DESCRIPTION:
XS GIS Cut Line= 2
      2212045.73     13838874.84      2212470.41     13838520.32
#Sta/Elev= 30
    4771  969.98  4798.4  969.45  4848.2  959.22  4876.5  948.95  4890.8  941.32
  4905.1  936.22  4912.9  931.67  4919.4  929.24  4933.7  920.06  4940.2  917.36
    4948  914.86  4968.9  912.13  4976.7  909.12  4987.7  907.73  4988.2  907.23
  4994.3  907.73  4997.5   908.6  5011.8  923.24  5040.5  942.63    5047  945.83
  5069.1  960.31  5075.6  963.11  5089.9  972.75  5125.1  990.12    5168 1004.38
  5182.3 1006.48  5217.5 1015.55    5239 1018.69  5309.9 1024.11  5324.2  1026.6
#Mann= 3 ,-1 , 0
    4771     .12       0  4987.7     .05       0  4994.3     .12       0
Bank Sta=4987.7,4994.3
XS Rating Curve= 0 ,0
Exp/Cntr=0.3,0.1

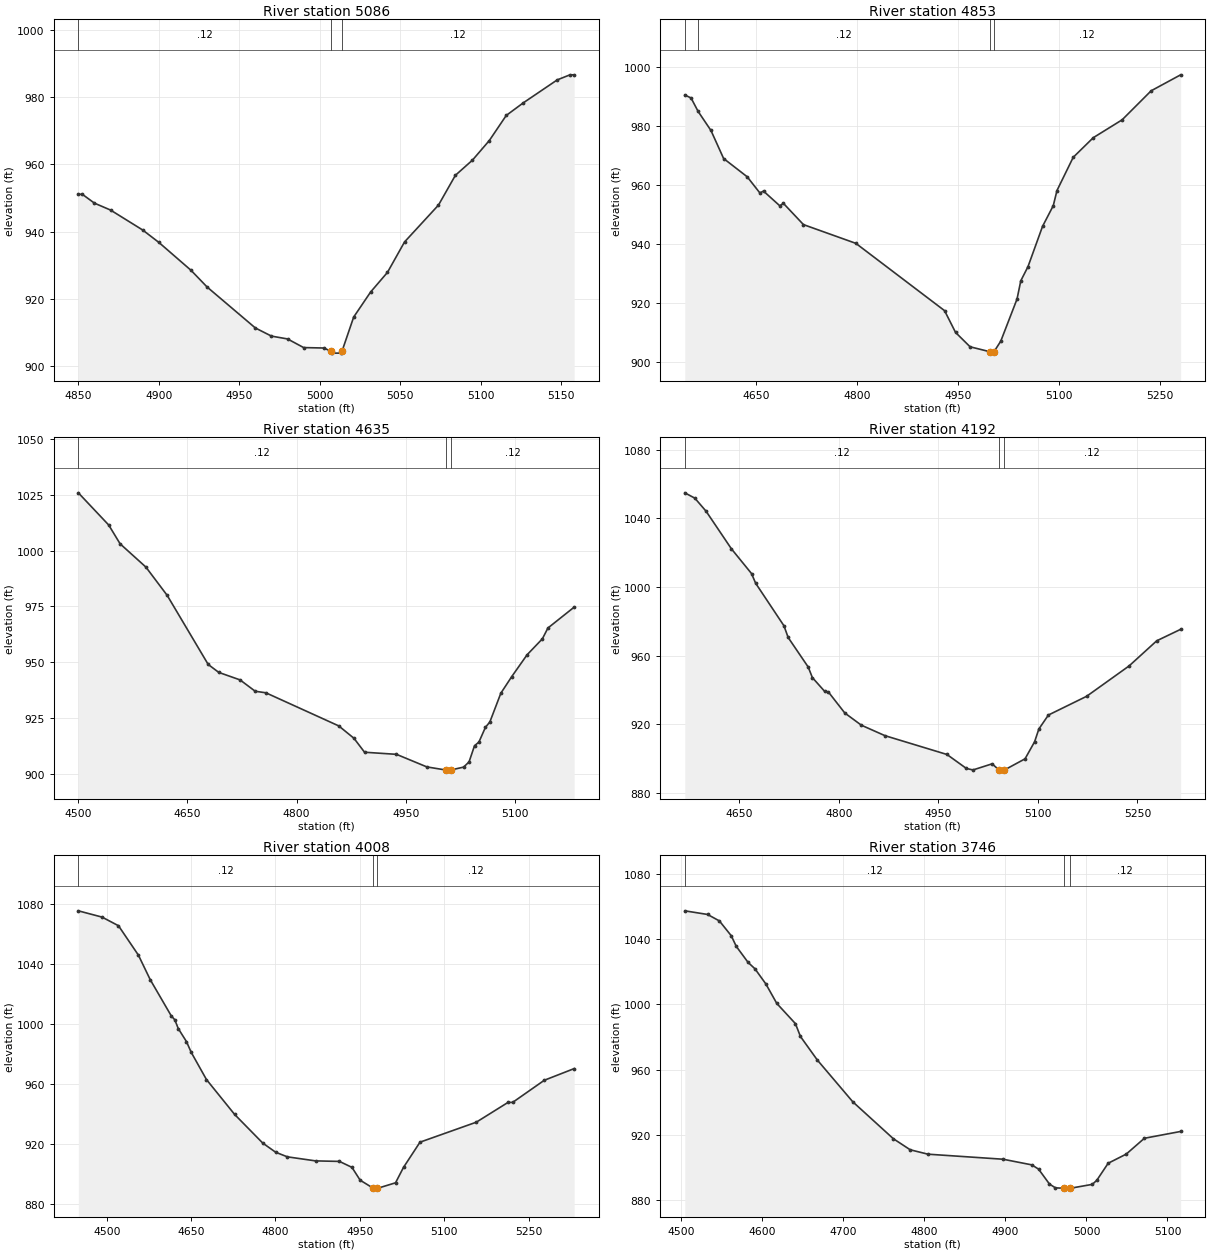
Type RM Length L Ch R = 1 ,5086    ,233,233,233
BEGIN DESCRIPTION:
Little Bear Creek 11.0
END DESCRIPTION:
XS GIS Cut Line= 3
      2212175.02       13838925.        2212325.       13838925.
        2212475.       13838875.
#Sta/Elev= 30
    4850  951.08  4852.5  951.08    4860  948.45    4870   946.4    4890  940.46
    4900  936.79    4920  928.49    4930  923.52    4960  911.33    4970  908.91
    4980  908.07    4990   905.5  5002.6  905.37  5007.2  904.35  5007.7  903.85
  5013.3  903.85  5013.8  904.35  5021.1  914.58  5031.6  922.01  5042.1  927.87
  5052.7  936.91  5073.8  947.88  5084.3  956.73  5094.9  961.24  5105.4  967.08
  5115.9  974.53  5126.5  978.28  5147.6  985.11  5155.5  986.61  5158.1  986.61
#Mann= 3 ,-1 , 0
    4850     .12       0  5007.2     .05       0  5013.8     .12       0
Bank Sta=5007.2,5013.8
XS Rating Curve= 0 ,0
Exp/Cntr=0.3,0.1

Type RM Length L Ch R = 1 ,4853    ,218,218,218
BEGIN DESCRIPTION:
A19637
END DESCRIPTION:
XS GIS Cut Line= 2
      2212001.26      13839293.4      2212685.64     13839019.64
#Sta/Elev= 30
  4543.6  990.65  4552.9  989.63  4563.4  985.07  4582.5  978.59  4601.3  969.08
  4636.4  962.87  4655.2  957.39  4660.6  958.02  4684.8  953.03  4690.2  953.86
    4720  946.64  4797.9  940.28  4929.8  917.42  4946.1  910.04  4967.7  905.16
  4996.7  903.51  4997.2  903.01  5003.3  903.51  5013.3  907.06  5037.5  921.37
  5043.1  927.57  5053.8  932.37  5075.4  946.03  5091.4  953.09  5096.9  958.22
    5121  969.48  5150.8  976.14  5193.7  982.21  5236.9  992.07  5280.7  997.49
#Mann= 4 ,-1 , 0
  4543.6     .07       0  4563.4     .12       0  4996.7     .05       0
  5003.3     .12       0
Bank Sta=4996.7,5003.3
XS Rating Curve= 0 ,0
Exp/Cntr=0.3,0.1

Type RM Length L Ch R = 1 ,4635    ,443,443,443
BEGIN DESCRIPTION:
Little Bear Creek 10.0
END DESCRIPTION:
XS GIS Cut Line= 3
      2212174.98     13839725.03        2212475.       13839325.
      2212624.99     13839225.01
#Sta/Elev= 30
  4500.5 1025.94  4542.2  1011.5  4557.8 1003.09  4593.2  992.65  4622.4  979.97
  4678.7  948.99  4693.2  945.43  4722.4  942.07  4743.2  936.98  4757.8  936.29
  4857.8  921.45  4878.7  915.89  4893.2  909.64    4937   908.7  4978.7  903.06
  5004.7  901.67  5005.2  901.17  5011.4  901.67  5029.1  902.97  5036.6  905.31
  5044.1  912.57  5050.1  914.17  5059.1  920.84  5065.1  923.18  5080.2   936.1
  5095.2  943.57  5116.2  953.32  5137.2  960.49  5144.8  965.33  5180.8  974.69
#Mann= 3 ,-1 , 0
  4500.5     .12       0  5004.7     .05       0  5011.4     .12       0
Bank Sta=5004.7,5011.4
XS Rating Curve= 0 ,0
Exp/Cntr=0.3,0.1

Type RM Length L Ch R = 1 ,4192    ,184,184,184
BEGIN DESCRIPTION:
Little Bear Creek 9.0
END DESCRIPTION:
XS GIS Cut Line= 3
      2212224.98     13839875.01        2212625.       13839725.
      2212825.02     13839474.98
#Sta/Elev= 30
  4567.7 1054.94  4582.8 1051.84  4599.8  1044.2    4638 1022.26  4668.3 1007.84
  4674.5  1002.2  4717.2  977.37  4723.5  970.56  4753.7  953.35    4760  947.18
  4778.6  939.11    4784  938.86  4808.9  926.52  4833.8  919.42  4869.4  913.31
  4962.9  902.33  4992.2  894.17  5002.1  893.31  5030.9  896.87  5041.9  893.12
  5042.4  892.62  5048.7  893.12  5080.6   899.8    5095  909.76  5101.4  917.19
  5115.8  925.34  5173.4  936.26  5237.4  953.97  5279.1  968.64  5315.1  975.32
#Mann= 3 ,-1 , 0
  4567.7     .12       0  5041.9     .05       0  5048.7     .12       0
Bank Sta=5041.9,5048.7
XS Rating Curve= 0 ,0
Exp/Cntr=0.3,0.1

Type RM Length L Ch R = 1 ,4008    ,262,262,262
BEGIN DESCRIPTION:
A19636
END DESCRIPTION:
XS GIS Cut Line= 2
      2212312.41     13840182.35       2213019.9     13839656.36
#Sta/Elev= 30
  4449.5 1075.32  4491.7 1071.13  4520.9 1065.37  4556.3 1045.77  4577.3 1029.42
  4614.7 1005.27    4621 1002.64  4627.2  996.78  4641.8  988.07  4650.2  980.93
  4677.3  962.78  4727.4   939.5  4777.4  920.39  4800.4  914.27  4821.2  911.21
  4871.3  908.51  4913.8  908.16    4936  904.19  4950.6  895.63  4974.3  890.17
  4974.8  889.67  4981.1  890.17  5013.5  893.89  5027.7   904.2    5057  920.99
  5157.1  934.32  5213.4   947.5  5221.8  947.54    5278  962.29  5331.1  970.07
#Mann= 3 ,-1 , 0
  4449.5     .12       0  4974.3     .05       0  4981.1     .12       0
Bank Sta=4974.3,4981.1
XS Rating Curve= 0 ,0
Exp/Cntr=0.3,0.1

Type RM Length L Ch R = 1 ,3746    ,322,322,322
BEGIN DESCRIPTION:
Little Bear Creek 8.0
END DESCRIPTION:
XS GIS Cut Line= 3
        2212525.       13840325.        2212925.       13840025.
        2212975.     13839925.01
#Sta/Elev= 30
  4504.4 1057.54  4532.5 1055.31  4547.1 1051.33  4561.7 1042.25  4567.9 1035.72
  4582.5 1025.85  4590.9 1021.97  4604.4 1012.64  4617.9 1000.66  4640.9  988.23
  4647.1  980.34  4667.9  965.89  4711.7   940.2  4761.7  917.54  4782.5  910.74
  4804.4  908.03  4897.1  904.93  4932.5  901.47  4940.9  898.86  4954.4  889.66
  4961.7  887.36  4972.9  887.06  4973.4  886.56  4979.7  887.06  5007.2  889.48
  5012.8  892.01  5026.8  902.46  5049.1  908.08  5071.5  917.81  5116.2  921.99
#Mann= 3 ,-1 , 0
  4504.4     .12       0  4972.9     .05       0  4979.7     .12       0
Bank Sta=4972.9,4979.7
XS Rating Curve= 0 ,0
Exp/Cntr=0.3,0.1