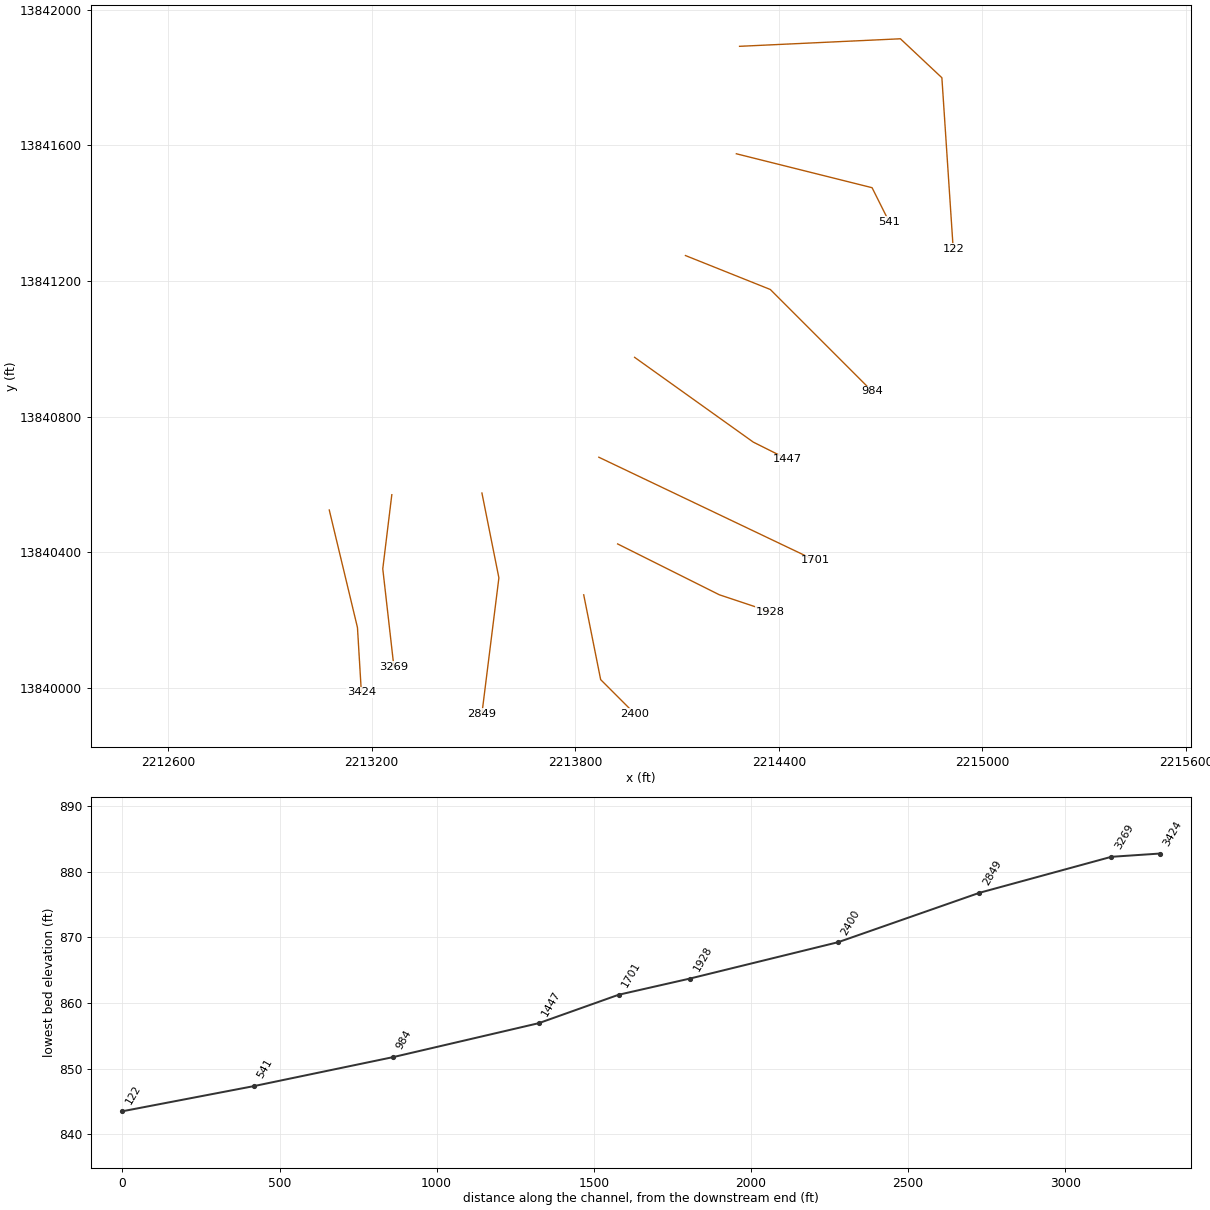
HEC-RAS study Little Bear Creek.prj: Little Bear Creek Base Level Engineering

--- Little Bear Creek.g01 (geometry) --- (continued)

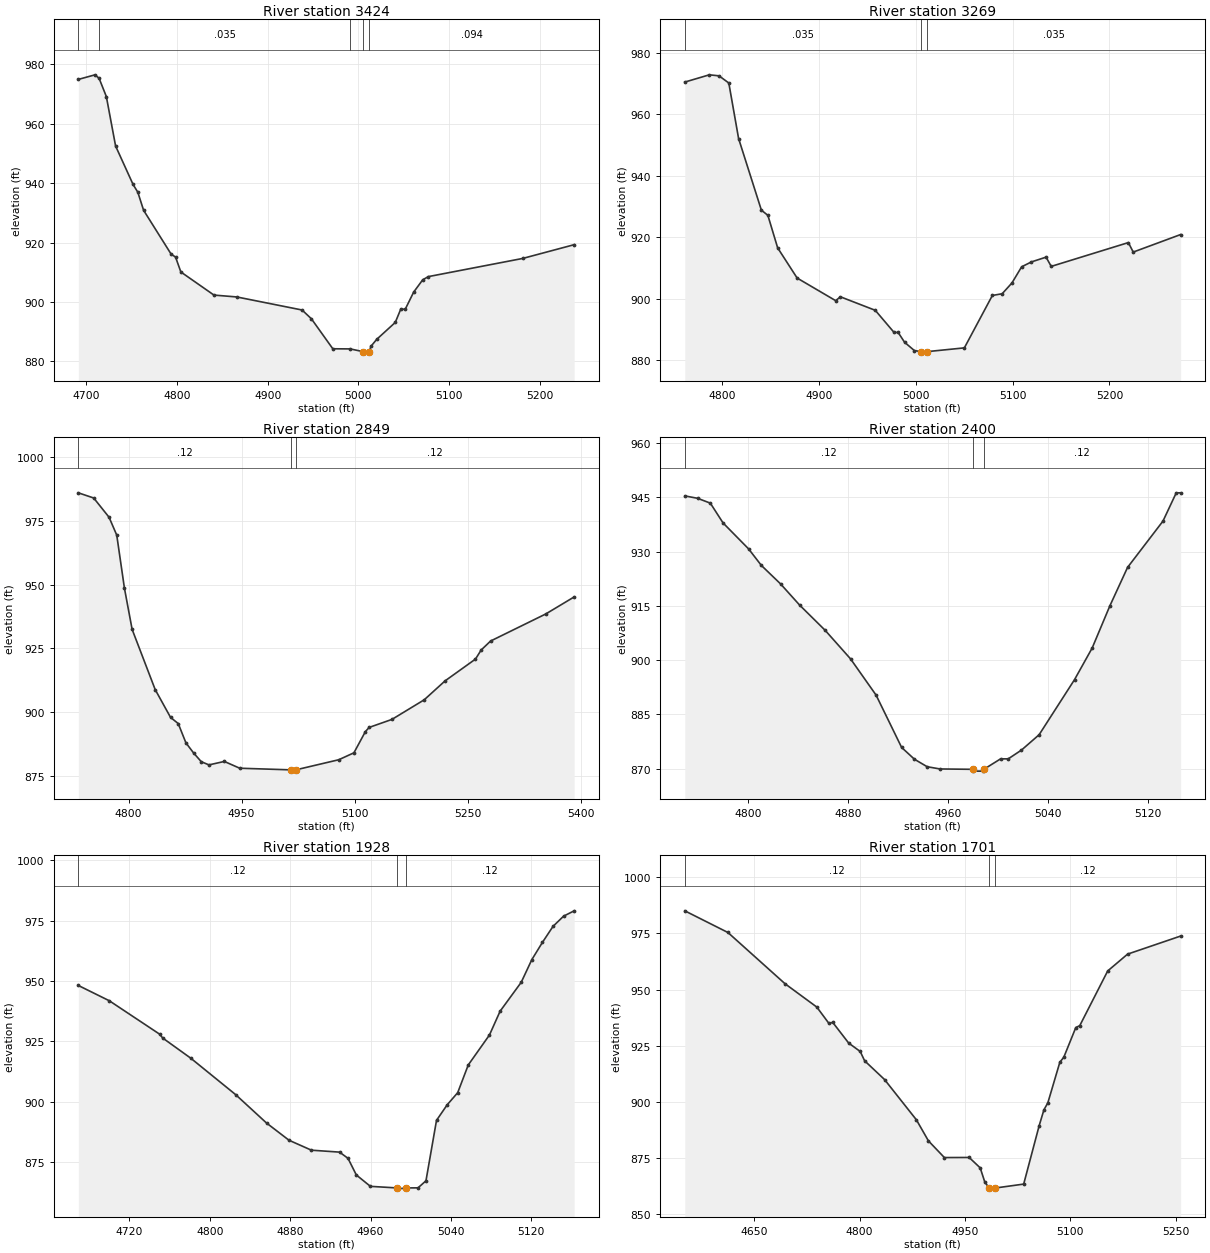
Type RM Length L Ch R = 1 ,3424    ,155,155,155
BEGIN DESCRIPTION:
Little Bear Creek 7.5
END DESCRIPTION:
XS GIS Cut Line= 3
        2213075.       13840525.      2213158.13     13840178.45
      2213169.57     13839988.28
#Sta/Elev= 30
  4691.2  974.85  4709.6  976.39  4714.1  975.22  4722.1  969.08  4732.3  952.45
  4751.6  939.51  4756.8  936.92  4763.2  930.83  4793.6  916.07  4798.4  915.12
  4804.3  910.09  4840.8  902.32    4866  901.69    4938   897.3  4948.3  894.34
  4971.9  884.26  4991.1  884.22  5005.3   883.3  5005.8   882.8  5012.2   883.3
  5013.9  885.07  5020.3  887.43  5040.8  893.13  5046.8  897.57  5051.8  897.57
  5061.1  903.33  5071.1  907.48  5077.4  908.54  5181.3  914.64  5238.1  919.27
#Mann= 5 ,-1 , 0
  4691.2    .063       0  4714.1    .035       0  4991.1    .094       0
  5005.3     .05       0  5012.2    .094       0
Bank Sta=5005.3,5012.2
XS Rating Curve= 0 ,0
Exp/Cntr=0.3,0.1

Type RM Length L Ch R = 1 ,3269    ,420,420,420
BEGIN DESCRIPTION:
Little Bear Creek 7.0
END DESCRIPTION:
XS GIS Cut Line= 3
      2213259.37     13840570.09      2213232.73     13840351.62
      2213265.59     13840062.06
#Sta/Elev= 30
  4761.9  970.55  4787.2  972.91  4797.2  972.58  4807.3  970.25  4817.4  952.17
  4840.9  928.85  4847.6  927.16  4857.7  916.57  4877.8  906.74  4917.5  899.39
  4922.5  900.63  4958.4  896.24  4977.8  889.03    4982  889.03  4988.6  885.85
  4998.7  883.14  5005.3   882.8  5005.8   882.3  5012.2   882.8  5050.3  884.01
  5079.2  901.08  5089.3  901.63  5099.4  905.15  5109.4  910.41  5119.5     912
  5134.6  913.55  5139.9  910.54  5219.5  918.29  5224.5   915.2  5273.4  920.91
#Mann= 3 ,-1 , 0
  4761.9    .035       0  5005.3    .035       0  5012.2    .035       0
Bank Sta=5005.3,5012.2
XS Rating Curve= 0 ,0
Exp/Cntr=0.3,0.1

Type RM Length L Ch R = 1 ,2849    ,449,449,449
BEGIN DESCRIPTION:
Little Bear Creek 6.0
END DESCRIPTION:
XS GIS Cut Line= 3
      2213524.99     13840575.04        2213575.       13840325.
        2213525.     13839925.01
#Sta/Elev= 30
  4733.4  986.01  4753.8  983.98  4774.2  976.42  4784.4   969.4  4794.6  948.57
  4804.8  932.43  4835.4  908.81  4855.8   897.9    4866  895.47  4876.2  887.91
  4886.4  883.93  4896.6   880.5  4906.8  879.26  4927.2  880.61  4947.6  877.95
  5015.2  877.31  5015.7  876.81  5022.1  877.31  5079.1  881.28  5099.2     884
  5114.4  892.32  5119.4  893.96  5149.6   897.1  5192.5   904.8  5220.2  912.23
  5260.5  920.77  5268.1  924.34  5280.6  927.86  5353.7  938.46  5391.5  945.16
#Mann= 3 ,-1 , 0
  4733.4     .12       0  5015.2     .05       0  5022.1     .12       0
Bank Sta=5015.2,5022.1
XS Rating Curve= 0 ,0
Exp/Cntr=0.3,0.1

Type RM Length L Ch R = 1 ,2400    ,472,472,472
BEGIN DESCRIPTION:
Little Bear Creek 5.0
END DESCRIPTION:
XS GIS Cut Line= 3
      2213825.01     13840274.97        2213875.       13840025.
      2213974.97     13839925.03
#Sta/Elev= 30
  4749.6  945.37  4759.8  944.71    4770  943.37  4780.2  937.89  4800.6  930.72
  4810.8  926.15  4826.1  921.06  4841.4  915.18  4861.8  908.21  4882.1  900.31
  4902.5   890.3  4922.9  875.84  4933.1  872.59  4943.3  870.51  4953.5  869.89
  4979.7  869.79  4980.2  869.29  4988.1  869.29  4988.6  869.79    5002  872.68
  5008.1  872.68  5018.7  875.11  5032.8  879.35  5061.1  894.58  5075.2  903.32
  5089.4  915.02  5103.5  925.61  5131.8  938.41  5142.4  946.22  5145.9  946.22
#Mann= 3 ,-1 , 0
  4749.6     .12       0  4979.7     .05       0  4988.6     .12       0
Bank Sta=4979.7,4988.6
XS Rating Curve= 0 ,0
Exp/Cntr=0.3,0.1

Type RM Length L Ch R = 1 ,1928    ,227,227,227
BEGIN DESCRIPTION:
Little Bear Creek 4.0
END DESCRIPTION:
XS GIS Cut Line= 3
      2213924.98     13840425.01        2214225.       13840275.
      2214374.96     13840225.01
#Sta/Elev= 30
  4669.1  948.16  4699.9  941.83  4750.2  927.92    4753   926.4  4780.9  918.05
  4825.6  902.94  4856.4  891.15  4878.8     884  4901.1  879.88  4929.1  879.08
  4937.5  876.51  4945.8  869.61  4959.8  864.89  4986.1  864.24  4986.6  863.74
    4995  864.24  5007.2  864.27  5015.1  867.19  5025.6  892.24  5036.2  898.68
  5046.7  903.73  5057.2  915.21  5078.3  927.63  5088.9   937.5  5109.9  949.47
  5120.5  958.89    5131  966.01  5141.6  972.68  5152.1  976.89  5162.6   979.1
#Mann= 3 ,-1 , 0
  4669.1     .12       0  4986.1     .05       0    4995     .12       0
Bank Sta=4986.1,4995
XS Rating Curve= 0 ,0
Exp/Cntr=0.3,0.1

Type RM Length L Ch R = 1 ,1701    ,254,254,254
BEGIN DESCRIPTION:
A19635
END DESCRIPTION:
XS GIS Cut Line= 2
      2213869.59     13840680.52      2214506.69     13840376.78
#Sta/Elev= 30
  4551.3  985.06  4612.7  975.42  4693.9  952.65  4739.2  942.25  4756.4  935.01
  4761.9  935.43  4784.6  926.23    4801   922.5  4807.3  918.35  4835.6  910.03
    4881  892.09  4898.1  882.74  4920.8  875.31  4956.1  875.35  4971.8  870.73
  4978.3  864.46  4984.5  861.77    4985  861.27  4993.4  861.77  5033.7  863.51
  5055.8  889.56  5062.5  896.54  5068.1  899.67  5085.2  917.74  5090.8  919.93
  5107.9  933.16  5113.5  933.97  5153.3  958.32  5181.6   965.8  5257.1  973.84
#Mann= 3 ,-1 , 0
  4551.3     .12       0  4984.5     .05       0  4993.4     .12       0
Bank Sta=4984.5,4993.4
XS Rating Curve= 0 ,0
Exp/Cntr=0.3,0.1

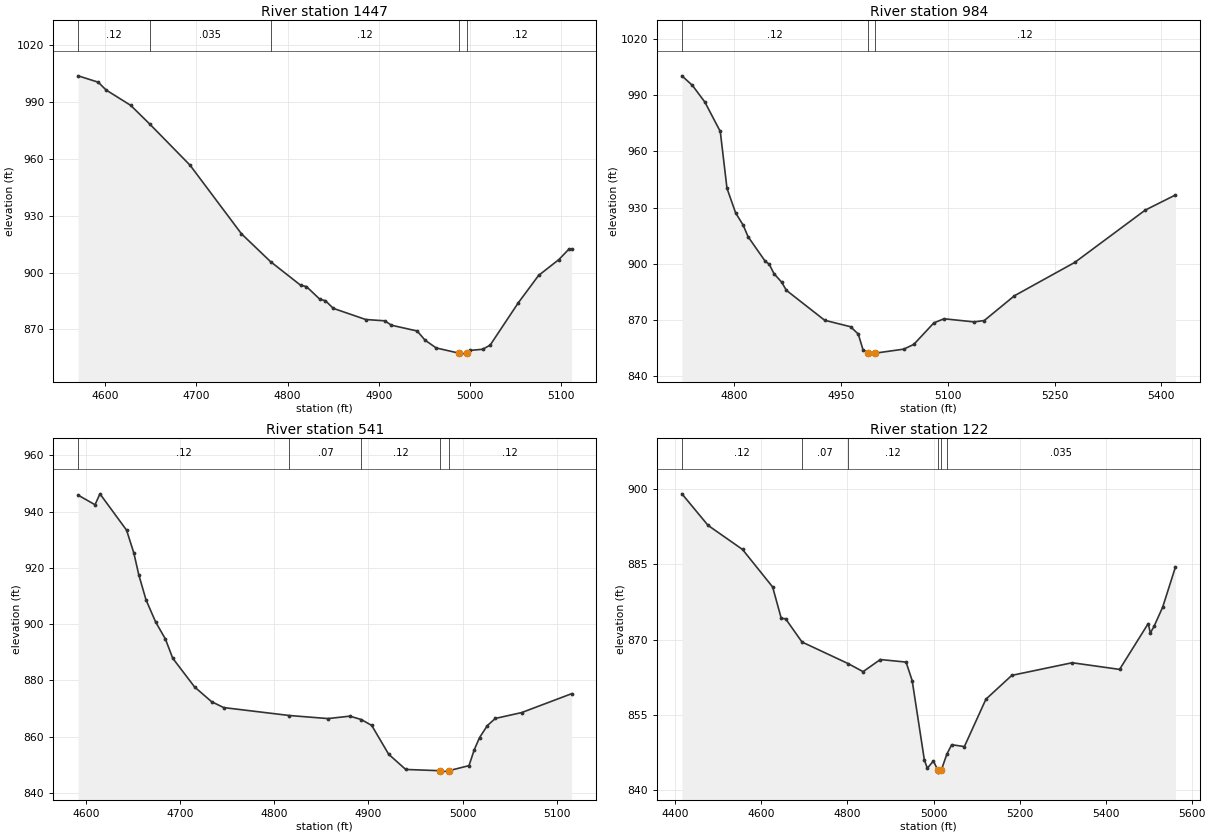
Type RM Length L Ch R = 1 ,1447    ,463,463,463
BEGIN DESCRIPTION:
Little Bear Creek 3.0
END DESCRIPTION:
XS GIS Cut Line= 3
      2213975.02     13840974.98        2214325.       13840725.
      2214425.01       13840675.
#Sta/Elev= 30
    4570 1003.89  4592.1 1000.53  4600.7  996.43  4627.7  988.32  4648.9  978.32
  4692.9  956.71  4749.4  920.46  4781.3  905.78  4814.5  893.25  4820.7  892.63
  4835.4  885.93  4841.6  885.13  4850.2  881.11  4885.8  875.22  4906.7  874.53
  4914.1   872.2  4942.3  869.15  4950.9  864.33  4963.2   860.2  4988.3  857.44
  4988.8  856.94  4997.2  857.44  5000.1  858.89  5014.1   859.5  5022.4  861.67
  5053.2  883.96  5075.6  898.49  5097.9  906.88  5109.1  912.48  5111.9  912.48
#Mann= 5 ,-1 , 0
    4570     .12       0  4648.9    .035       0  4781.3     .12       0
  4988.3     .05       0  4997.2     .12       0
Bank Sta=4988.3,4997.2
XS Rating Curve= 0 ,0
Exp/Cntr=0.3,0.1

Type RM Length L Ch R = 1 ,984     ,443,443,443
BEGIN DESCRIPTION:
Little Bear Creek 2.0
END DESCRIPTION:
XS GIS Cut Line= 3
      2214124.96     13841275.01        2214375.       13841175.
      2214675.03     13840874.97
#Sta/Elev= 30
  4726.2 1000.41    4741  995.28  4758.5  986.35  4780.1  970.68  4789.5  940.37
  4801.6  927.26  4812.4  920.55  4819.1  914.52  4843.4  901.29  4848.8  899.86
  4855.5  894.78  4866.3  890.23    4873  885.85  4926.8  869.86  4963.2   866.4
    4974  862.49  4980.7   854.1  4988.3  852.27  4988.8  851.77  4997.4  852.27
  5037.9  854.43  5052.1  856.98  5080.3  868.47  5094.5  870.65  5136.9  868.98
  5151.1  869.72  5193.5  882.95  5278.3  900.76  5377.3  928.69  5419.8  936.78
#Mann= 3 ,-1 , 0
  4726.2     .12       0  4988.3     .05       0  4997.4     .12       0
Bank Sta=4988.3,4997.4
XS Rating Curve= 0 ,0
Exp/Cntr=0.3,0.1

Type RM Length L Ch R = 1 ,541     ,419,419,419
BEGIN DESCRIPTION:
Little Bear Creek 1.0
END DESCRIPTION:
XS GIS Cut Line= 3
      2214275.02     13841574.99        2214675.       13841475.
        2214725.     13841374.99
#Sta/Elev= 30
  4591.7  945.88  4609.7  942.46  4614.9  946.34  4643.2   933.4  4650.9  925.29
  4656.1   917.6  4663.8  908.66  4674.1  900.71  4684.4  894.71  4692.2  887.86
  4715.4  877.65  4733.4  872.42  4746.3  870.31  4816.1  867.49  4857.1   866.4
  4880.3  867.26  4892.4  866.06  4903.5  863.96  4921.5  853.71  4939.6   848.3
  4976.2  847.85  4976.7  847.35  4985.3  847.85  5006.8  849.66  5012.4  855.32
    5018  859.63  5026.3  863.91  5034.7  866.44  5062.7  868.53  5115.8  875.25
#Mann= 5 ,-1 , 0
  4591.7     .12       0  4816.1     .07       0  4892.4     .12       0
  4976.2     .05       0  4985.3     .12       0
Bank Sta=4976.2,4985.3
XS Rating Curve= 0 ,0
Exp/Cntr=0.3,0.1

Type RM Length L Ch R = 1 ,122     ,0,0,0
BEGIN DESCRIPTION:
A19634
END DESCRIPTION:
XS GIS Cut Line= 4
       2214284.4     13841891.73      2214758.53     13841913.95
      2214880.76     13841799.13       2214914.1     13841295.38
#Sta/Elev= 30
  4415.2   899.1  4475.9   892.8    4556  887.99    4626   880.5  4646.1  874.22
  4656.1  874.15  4694.3   869.5  4801.3   865.2  4836.3  863.58  4876.3     866
  4936.2  865.49  4950.4  861.79  4978.7  845.95  4985.6  844.29  4999.7  845.73
  5009.4  844.01  5009.9  843.51  5018.5  844.01    5031   847.1  5042.2  848.99
  5071.7  848.61  5121.8  858.08    5182  862.84  5322.3  865.36  5432.5  864.03
    5499  873.18    5504   871.3  5512.7  872.65  5532.7  876.48  5562.4   884.5
#Mann= 6 ,-1 , 0
  4415.2     .12       0  4694.3     .07       0  4801.3     .12       0
  5009.4     .05       0  5018.5     .12       0    5031    .035       0
Bank Sta=5009.4,5018.5
XS Rating Curve= 0 ,0
Exp/Cntr=0.3,0.1

Chan Stop Cuts=-1
Use User Specified Reach Order=0
Composite Channel Slope=5