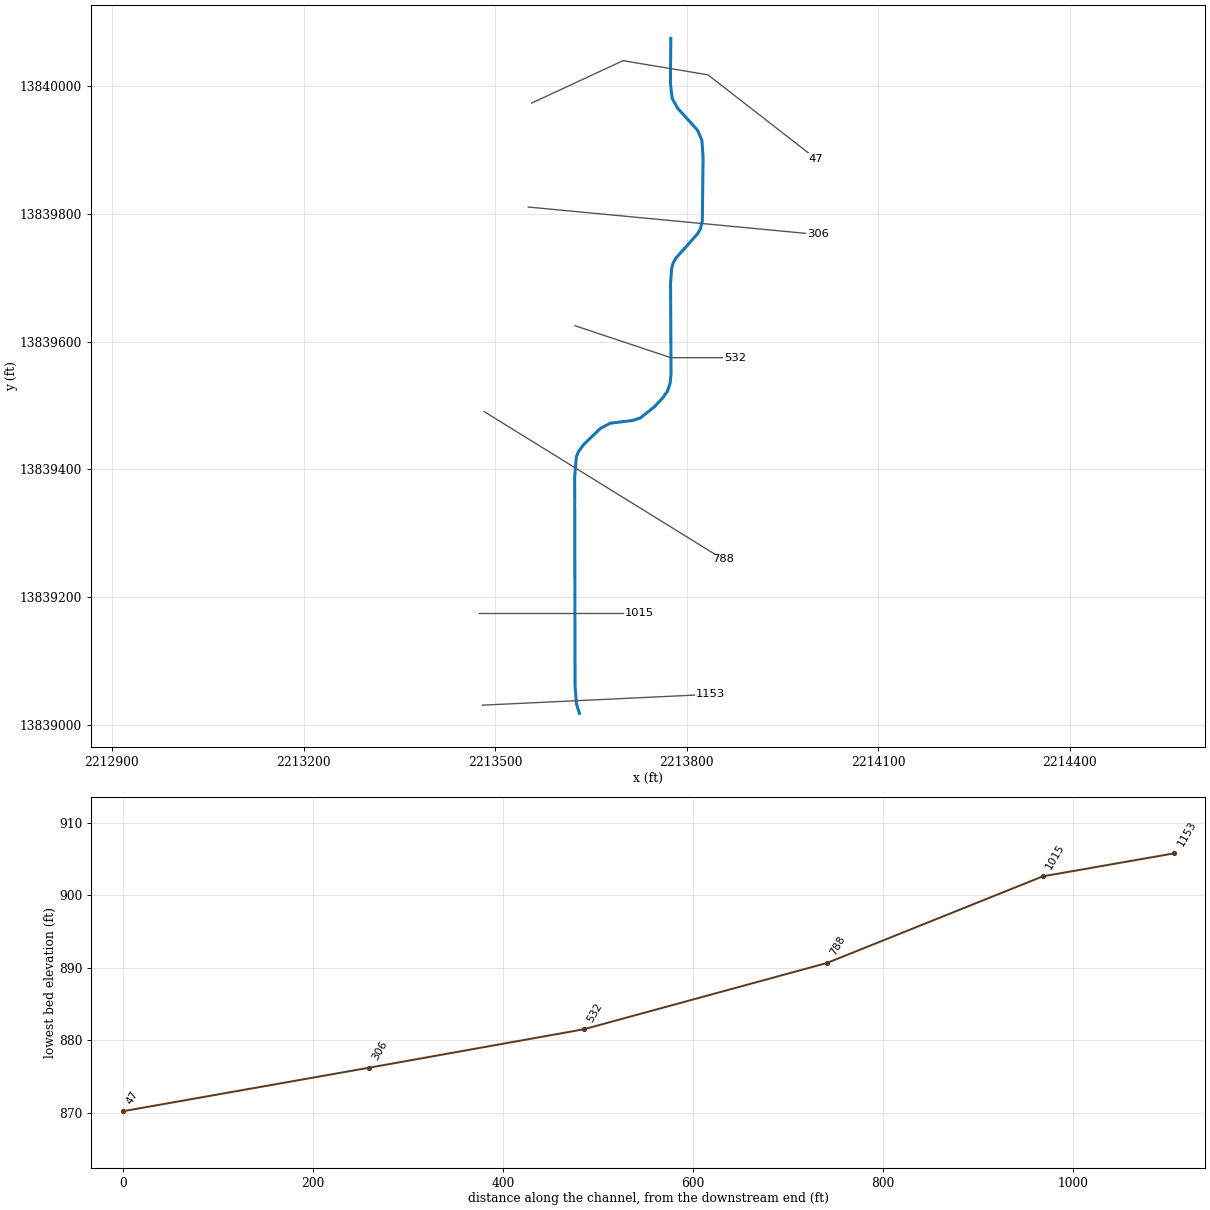
--- Little Bear Tributary 1.prj (project) ---

Proj Title=Little Bear Tributary 1 Base Level Engineering
Current Plan=p01
Default Exp/Contr=0.3,0.1
English Units
Geom File=g01
Flow File=f01
Plan File=p01
BEGIN DESCRIPTION:
Little Bear Tributary 1
END DESCRIPTION:

--- Little Bear Tributary 1.p01 (plan) ---

Plan Title=Multiple Run
Short Identifier=Multiple
Geom File=g01
Flow File=f01
Subcritical Flow
K Sum by GR= 0
Std Step Tol= 0.01
Critical Tol= 0.01
Num of Std Step Trials= 20
Max Error Tol= 0.3
Flow Tol Ratio= 0.001
Split Flow NTrial= 30
Split Flow Tol= 0.02
Split Flow Ratio= 0.02
Log Output Level= 0
Friction Slope Method= 1
Unsteady Friction Slope Method= 2
Unsteady Bridges Friction Slope Method= 1
Parabolic Critical Depth
Global Vel Dist=  1 , 1 , 1
Global Log Level= 0
CheckData=True
Encroach Param= -1, 0, 0, 0
BEGIN DESCRIPTION:
Multiple Run
END DESCRIPTION:

--- Little Bear Tributary 1.f01 (steady flow) ---

Flow Title=Multiple
Number of Profiles=7
Profile Names=10-year,25-year,50-year,1pct_min,100-year,1pct_plu,500-year
River Rch & RM= Little Bear Trib,Reach-1,1153
    1052    1788    2491    1683    3358    6701    6038
Boundary for River Rch & Prof#=Little Bear Trib,Reach-1,1
Up Type=0
Dn Type=3
Dn Slope=0.005
Boundary for River Rch & Prof#=Little Bear Trib,Reach-1,2
Up Type=0
Dn Type=3
Dn Slope=0.005
Boundary for River Rch & Prof#=Little Bear Trib,Reach-1,3
Up Type=0
Dn Type=3
Dn Slope=0.005
Boundary for River Rch & Prof#=Little Bear Trib,Reach-1,4
Up Type=0
Dn Type=3
Dn Slope=0.005
Boundary for River Rch & Prof#=Little Bear Trib,Reach-1,5
Up Type=0
Dn Type=3
Dn Slope=0.005
Boundary for River Rch & Prof#=Little Bear Trib,Reach-1,6
Up Type=0
Dn Type=3
Dn Slope=0.005
Boundary for River Rch & Prof#=Little Bear Trib,Reach-1,7
Up Type=0
Dn Type=3
Dn Slope=0.005

--- Little Bear Tributary 1.g01 (geometry) ---

Geom Title=Existing Conditions

River Reach=Little Bear Trib,Reach-1
Reach XY= 30
      2213631.96     13839018.04      2213627.23     13839032.95
      2213625.03     13839061.11      2213624.48     13839388.90
      2213627.09     13839419.74      2213630.36     13839427.70
      2213638.23     13839438.67      2213664.96     13839464.37
      2213680.47     13839472.43      2213715.33     13839476.65
      2213727.55     13839480.75      2213748.96     13839497.81
      2213761.77     13839511.33      2213769.64     13839522.30
      2213774.01     13839535.28      2213775.33     13839549.79
      2213774.57     13839690.18      2213776.22     13839714.49
      2213778.78     13839723.43      2213783.14     13839731.06
      2213816.86     13839768.95      2213821.23     13839776.57
      2213824.33     13839788.93      2213825.48     13839888.80
      2213823.65     13839915.34      2213816.91     13839931.07
      2213785.86     13839965.35      2213777.10     13839980.87
      2213774.37     13840004.74      2213775.00     13840075.00

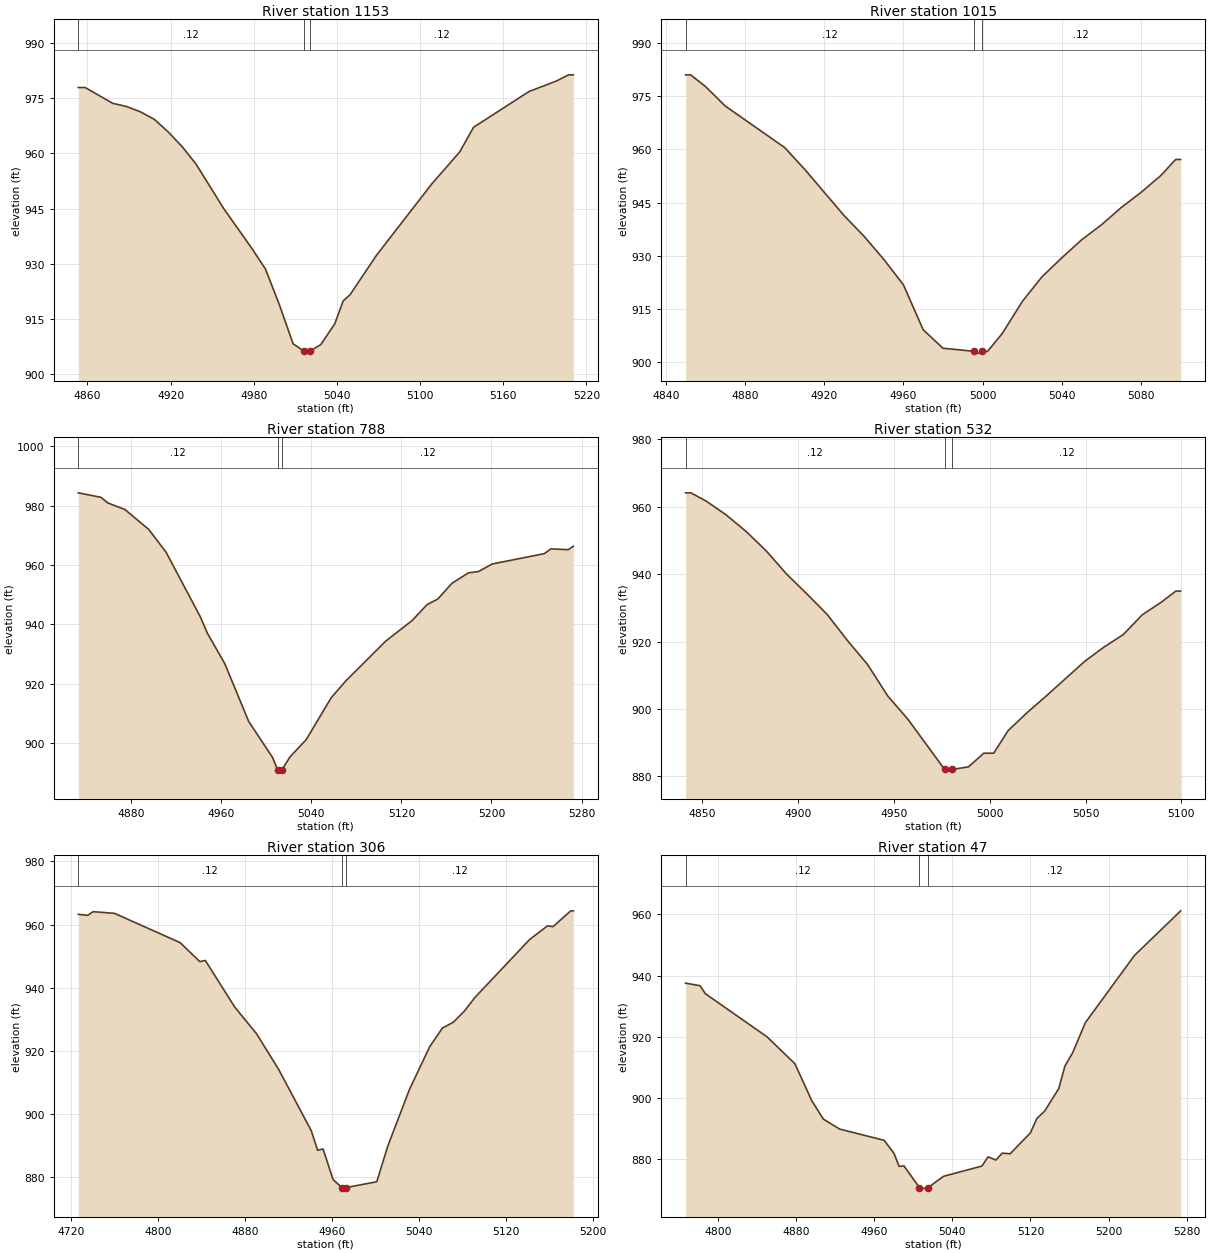
Type RM Length L Ch R = 1,1153,138,138,138
BEGIN DESCRIPTION:
A19648
END DESCRIPTION:
XS GIS Cut Line= 2
      2213480.15     13839030.89      2213836.95     13839047.82
#Sta/Elev= 30
  4853.4  977.85  4858.3  977.85  4878.3  973.55  4888.3  972.69  4898.3  971.24
  4908.3  969.21  4918.3  965.79  4928.3  961.82  4938.3  957.11  4958.4  944.96
  4978.4  934.33  4988.4  928.63  4998.4  919.00  5008.4  908.33  5016.4  906.29
  5016.7  905.79  5020.2  905.79  5020.4  906.29  5028.4  908.12  5038.5  913.78
  5044.5  919.96  5049.5  921.64  5068.5  932.31  5108.5  951.72  5128.6  960.37
  5138.6  967.06  5178.6  976.76  5198.6  979.65  5207.1  981.29  5210.6  981.29
#Mann=3,-1,0
  4853.4    0.12       0  5016.4    0.05       0  5020.4    0.12       0
Bank Sta=5016.4,5020.4
Exp/Cntr=0.3,0.1

Type RM Length L Ch R = 1,1015,227,227,227
BEGIN DESCRIPTION:
Little Bear Tributary 1 2.0
END DESCRIPTION:
XS GIS Cut Line= 3
      2213474.97     13839175.00      2213625.00     13839175.00
      2213724.97     13839175.00
#Sta/Elev= 30
  4850.0  981.00  4852.5  981.00  4860.0  977.74  4870.0  972.23  4900.0  960.53
  4910.0  954.49  4930.0  941.38  4940.0  935.61  4950.0  929.09  4960.0  921.86
  4970.0  909.19  4980.0  903.99  4990.0  903.45  4995.5  903.12  4995.8  902.62
  4999.3  902.62  4999.5  903.12  5000.0  903.12  5002.5  903.12  5010.0  908.22
  5020.0  917.14  5030.0  924.14  5040.0  929.47  5050.0  934.54  5060.0  938.76
  5070.0  943.62  5080.0  947.90  5090.0  952.65  5097.5  957.17  5100.0  957.17
#Mann=3,-1,0
  4850.0    0.12       0  4995.5    0.05       0  4999.5    0.12       0
Bank Sta=4995.5,4999.5
Exp/Cntr=0.3,0.1

Type RM Length L Ch R = 1,788,256,256,256
BEGIN DESCRIPTION:
A19647
END DESCRIPTION:
XS GIS Cut Line= 2
      2213482.81     13839490.52      2213856.75     13839259.40
#Sta/Elev= 30
  4833.1  984.30  4853.2  982.80  4859.2  980.92  4874.5  978.69  4895.7  971.97
  4911.1  964.28  4941.5  942.55  4947.8  937.02  4963.2  926.80  4984.4  907.39
  5005.7  895.19  5010.0  891.16  5010.3  890.66  5014.0  891.16  5021.1  895.46
  5035.5  901.27  5057.7  915.37  5070.8  921.09  5106.2  934.44  5129.6  941.35
  5142.8  946.69  5152.3  948.55  5164.8  953.84  5179.5  957.37  5188.3  957.80
  5200.7  960.36  5246.9  963.84  5252.8  965.45  5268.2  965.17  5272.7  966.33
#Mann=3,-1,0
  4833.1    0.12       0  5010.0    0.05       0  5014.0    0.12       0
Bank Sta=5010,5014
Exp/Cntr=0.3,0.1

Type RM Length L Ch R = 1,532,226,226,226
BEGIN DESCRIPTION:
Little Bear Tributary 1 1.0
END DESCRIPTION:
XS GIS Cut Line= 3
      2213624.96     13839625.01      2213775.00     13839575.00
      2213875.04     13839575.00
#Sta/Elev= 30
  4841.4  964.16  4844.1  964.16  4852.0  961.76  4862.5  957.64  4873.1  952.62
  4883.6  946.83  4894.1  940.01  4904.7  934.13  4915.2  928.07  4925.8  920.31
  4936.3  913.18  4946.9  903.78  4957.4  896.87  4976.5  882.00  4976.7  881.50
  4980.2  881.50  4980.5  882.00  4989.0  882.78  4996.9  886.82  5002.1  886.82
  5009.6  893.52  5019.6  898.92  5029.6  903.88  5049.6  914.13  5059.6  918.34
  5069.6  922.03  5079.6  927.93  5089.6  931.72  5097.1  934.98  5099.6  934.98
#Mann=3,-1,0
  4841.4    0.12       0  4976.5    0.05       0  4980.5    0.12       0
Bank Sta=4976.5,4980.5
Exp/Cntr=0.3,0.1

Type RM Length L Ch R = 1,306,259,259,259
BEGIN DESCRIPTION:
A19646
END DESCRIPTION:
XS GIS Cut Line= 2
      2213551.82     13839810.84      2214004.88     13839767.88
#Sta/Elev= 30
  4726.9  963.26  4735.5  962.93  4740.5  964.09  4760.2  963.56  4820.5  954.29
  4838.6  948.28  4843.7  948.62  4870.7  933.88  4890.8  925.39  4910.9  914.23
  4941.0  894.75  4946.9  888.49  4951.9  888.92  4961.1  879.23  4969.2  876.69
  4969.4  876.19  4973.2  876.69  5001.3  878.53  5011.4  889.82  5031.4  907.83
  5050.0  921.35  5061.6  927.21  5071.6  929.06  5081.7  932.54  5091.7  936.99
  5141.9  955.31  5158.3  959.61  5163.3  959.35  5179.6  964.36  5182.0  964.36
#Mann=3,-1,0
  4726.9    0.12       0  4969.2    0.05       0  4973.2    0.12       0
Bank Sta=4969.2,4973.2
Exp/Cntr=0.3,0.1

Type RM Length L Ch R = 1,47,0,0,0
BEGIN DESCRIPTION:
A19645
END DESCRIPTION:
XS GIS Cut Line= 4
      2213556.98     13839973.59      2213700.24     13840040.01
      2213833.06     13840017.87      2214002.32     13839886.37
#Sta/Elev= 30
  4766.9  937.53  4781.7  936.70  4787.2  934.07  4850.4  919.96  4878.8  911.19
  4896.2  899.05  4908.0  893.07  4924.7  889.81  4970.2  886.14  4980.3  881.88
  4985.5  877.63  4990.6  877.75  5006.3  870.68  5006.8  870.18  5015.2  870.68
  5031.0  874.37  5070.3  877.72  5076.6  880.72  5084.7  879.70  5091.1  881.95
  5099.2  881.73  5120.0  888.59  5126.4  893.21  5134.5  895.67  5149.0  903.06
  5155.3  910.43  5163.2  914.75  5176.2  924.60  5226.5  946.59  5273.8  961.18
#Mann=3,-1,0
  4766.9    0.12       0  5006.3    0.05       0  5015.2    0.12       0
Bank Sta=5006.3,5015.2
Exp/Cntr=0.3,0.1

Chan Stop Cuts=-1