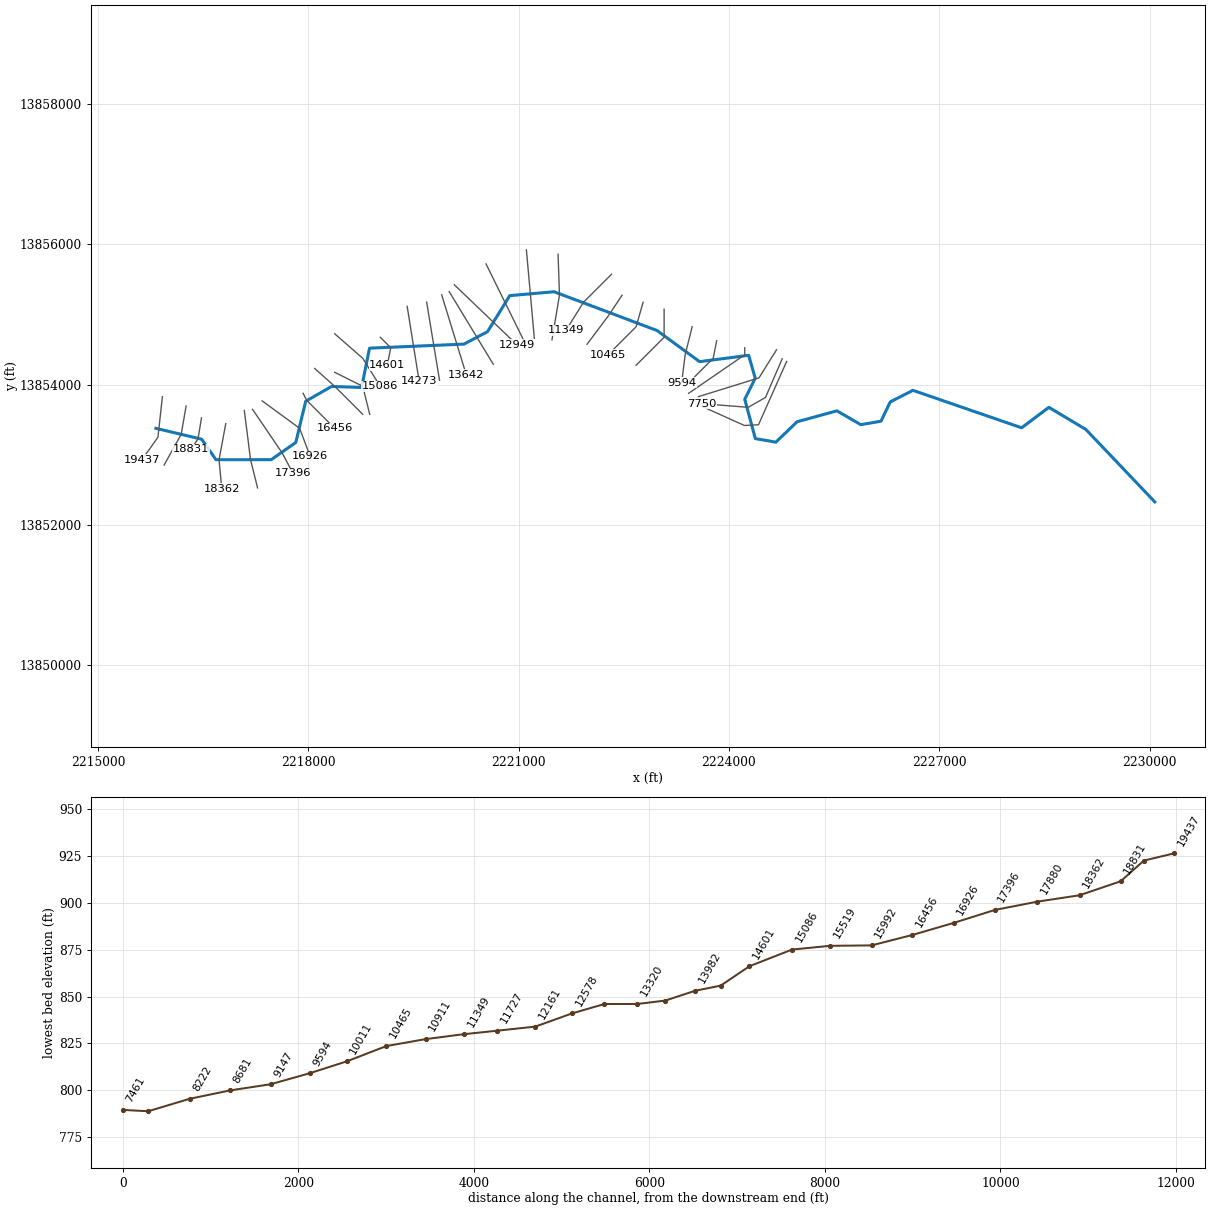
--- Mountain Creek.prj (project) ---

Proj Title=Mountain Creek Base Level Engineering
Current Plan=p01
Default Exp/Contr=0.3,0.1
English Units
Geom File=g01
Flow File=f01
Plan File=p01
Y Axis Title=Elevation
X Axis Title(PF)=Main Channel Distance
X Axis Title(XS)=Station
BEGIN DESCRIPTION:
Mountain Creek
END DESCRIPTION:
DSS Export Rating Curves= 0
DSS Export Rating Curve Sorted= 0
DSS Export Volume Flow Curves= 0
DXF OffsetX= 0
DXF OffsetY= 0
DXF ScaleX= 1
DXF ScaleY= 10

--- Mountain Creek.p01 (plan) ---

Plan Title=Multiple Run
Short Identifier=Multiple
Geom File=g01
Flow File=f01
Subcritical Flow
K Sum by GR= 0
Std Step Tol= 0.01
Critical Tol= 0.01
Num of Std Step Trials= 20
Max Error Tol= 0.3
Flow Tol Ratio= 0.001
Split Flow NTrial= 30
Split Flow Tol= 0.02
Split Flow Ratio= 0.02
Log Output Level= 0
Friction Slope Method= 1
Unsteady Friction Slope Method= 2
Unsteady Bridges Friction Slope Method= 1
Parabolic Critical Depth
Global Vel Dist=  1 , 1 , 1
Global Log Level= 0
CheckData=True
Encroach Param= -1, 0, 0, 0
BEGIN DESCRIPTION:
Multiple Run
END DESCRIPTION:

--- Mountain Creek.f01 (steady flow) ---

Flow Title=Multiple
Number of Profiles=7
Profile Names=10-year,25-year,50-year,1pct_min,100-year,1pct_plu,500-year
River Rch & RM= Mountain Creek,Reach-1,19437
    1360    2322    3245    2196    4381    8741    7898
River Rch & RM= Mountain Creek,Reach-1,18362
    1624    2801    3939    2681    5349   10672    9759
River Rch & RM= Mountain Creek,Reach-1,16456
    1902    3296    4649    3170    6325   12620   11589
River Rch & RM= Mountain Creek,Reach-1,12949
    2169    3774    5337    3646    7274   14513   13379
River Rch & RM= Mountain Creek,Reach-1,7220
    3344    5929    8492    5867   11706   23356   22029
Boundary for River Rch & Prof#=Mountain Creek,Reach-1,1
Up Type=0
Dn Type=3
Dn Slope=0.005
Boundary for River Rch & Prof#=Mountain Creek,Reach-1,2
Up Type=0
Dn Type=3
Dn Slope=0.005
Boundary for River Rch & Prof#=Mountain Creek,Reach-1,3
Up Type=0
Dn Type=3
Dn Slope=0.005
Boundary for River Rch & Prof#=Mountain Creek,Reach-1,4
Up Type=0
Dn Type=3
Dn Slope=0.005
Boundary for River Rch & Prof#=Mountain Creek,Reach-1,5
Up Type=0
Dn Type=3
Dn Slope=0.005
Boundary for River Rch & Prof#=Mountain Creek,Reach-1,6
Up Type=0
Dn Type=3
Dn Slope=0.005
Boundary for River Rch & Prof#=Mountain Creek,Reach-1,7
Up Type=0
Dn Type=3
Dn Slope=0.005

--- Mountain Creek.g01 (geometry) ---

Geom Title=Existing Conditions
Program Version=4.10

River Reach=Mountain Creek  ,Reach-1
Reach XY= 30
        2215825.       13853375.      2216477.68     13853219.58
      2216680.84     13852927.05      2217469.07     13852927.24
      2217819.48     13853172.56      2217961.44     13853761.51
      2218330.97     13853972.86      2218758.76     13853957.78
      2218872.53     13854519.55      2220219.06     13854577.26
      2220555.41      13854754.8      2220872.58     13855269.46
      2221504.97     13855324.93       2222973.5     13854771.39
      2223581.11      13854326.8      2224281.23     13854417.19
      2224374.63     13854090.17      2224225.09     13853790.39
       2224376.4     13853228.39      2224669.07     13853177.23
       2224972.7     13853469.17      2225540.28     13853624.62
      2225880.97     13853427.17      2226169.35     13853476.98
      2226301.16     13853752.15      2226624.99     13853917.47
        2228175.     13853382.56      2228564.36     13853674.45
      2229092.13      13853358.7        2230075.       13852325.

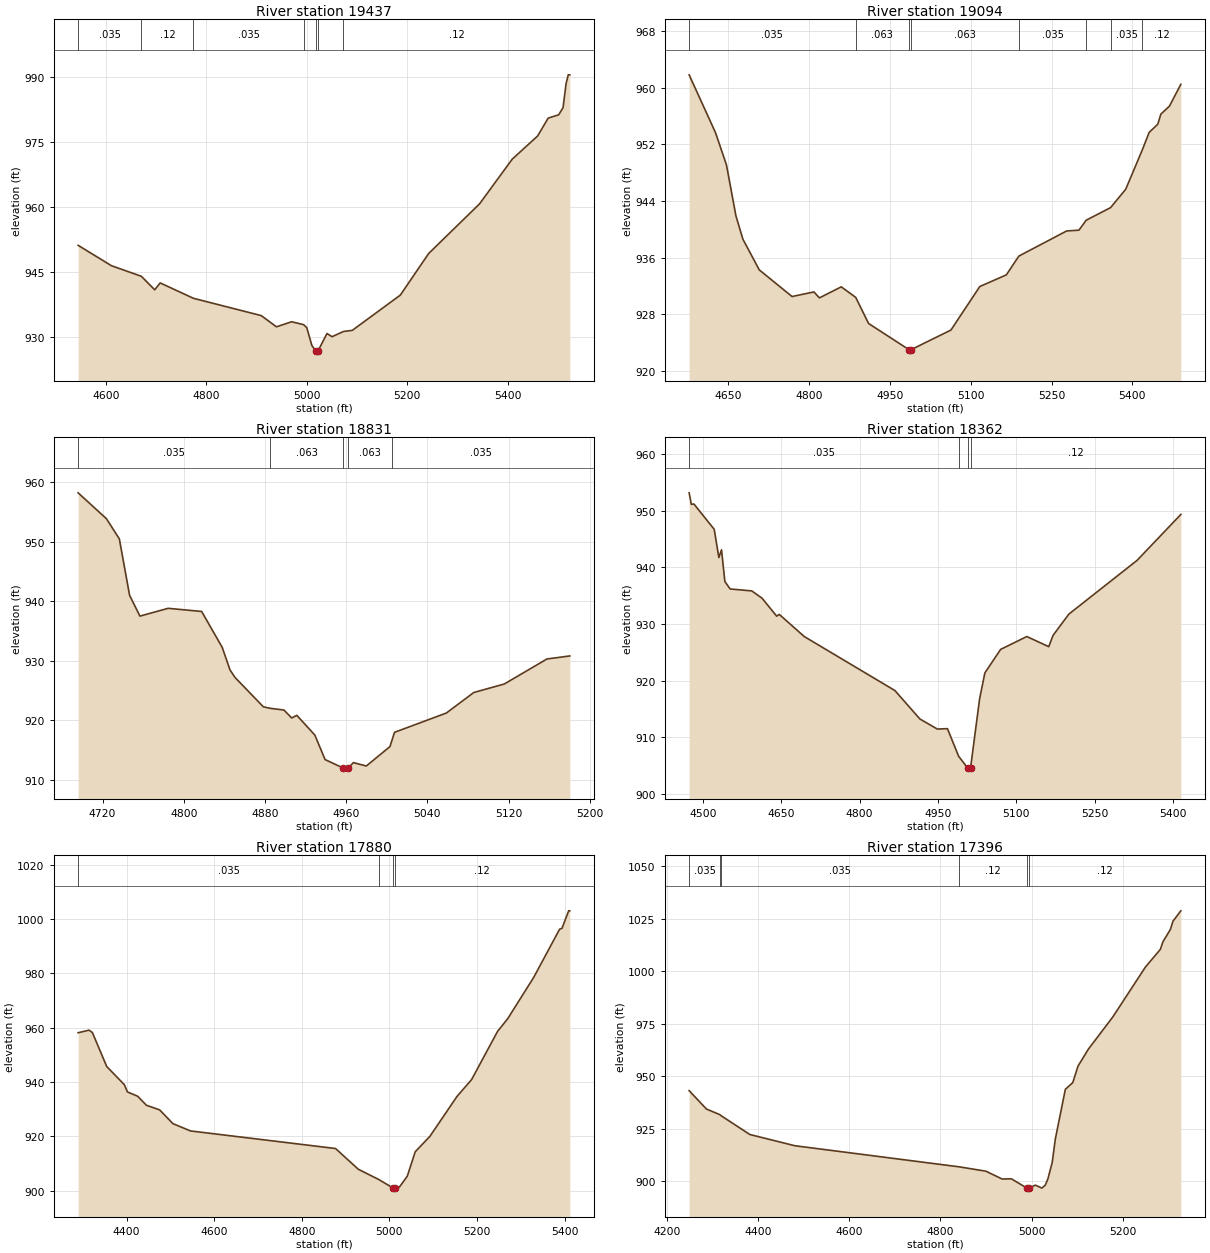
Type RM Length L Ch R = 1 ,19437   ,343,343,343
BEGIN DESCRIPTION:
Mountain Creek 41.0
END DESCRIPTION:
XS GIS Cut Line= 3
      2215917.11     13853827.28      2215853.49     13853248.07
        2215625.       13852925.
#Sta/Elev= 30
  4545.1  951.18  4611.5  946.48  4670.9  944.05  4697.5  940.94  4708.4  942.52
  4774.5  938.98  4909.6  934.99  4939.7  932.41  4969.9  933.57  4993.8  932.91
  5000.1  932.22  5010.2  928.12    5018  926.85  5018.3  926.35  5022.4  926.85
  5040.3  930.87  5050.4  930.13    5073  931.33  5090.6  931.59  5186.2  939.71
  5242.8  949.32  5343.8  960.72    5409  971.04  5459.5  976.37  5480.4  980.48
  5501.3  981.24    5510  982.87  5516.1  988.44  5520.4  990.45  5523.5  990.45
#Mann= 7 ,-1 , 0
  4545.1    .035       0  4670.9     .12       0  4774.5    .035       0
  4993.8    .063       0    5018    .063       0  5022.4    .063       0
    5073     .12       0
Bank Sta=5018,5022.4
XS Rating Curve= 0 ,0
Exp/Cntr=0.3,0.1

Type RM Length L Ch R = 1 ,19094   ,263,263,263
BEGIN DESCRIPTION:
B19681
END DESCRIPTION:
XS GIS Cut Line= 3
      2216255.26     13853693.33      2216184.95     13853288.24
      2215940.66     13852849.85
#Sta/Elev= 30
    4577  961.84    4626  953.66  4646.3  949.11  4663.9   941.9  4676.8  938.61
  4707.2  934.27  4768.1   930.5  4808.7  931.15  4818.9  930.31  4859.5  931.87
  4886.3  930.38  4910.2  926.69    4985     923  4985.3   922.5  4989.4     923
  5063.1  925.76  5116.8  931.92    5166  933.56  5189.3  936.22    5278  939.77
  5300.8  939.88  5314.3  941.29  5359.6  943.07  5387.7  945.67  5418.4  951.22
  5431.2   953.7  5447.2  954.86  5452.9  956.28  5468.9  957.42    5490   960.5
#Mann= 8 ,-1 , 0
    4577    .035       0  4886.3    .063       0    4985    .063       0
  4989.4    .063       0  5189.3    .035       0  5314.3    .063       0
  5359.6    .035       0  5418.4     .12       0
Bank Sta=4985,4989.4
XS Rating Curve= 0 ,0
Exp/Cntr=0.3,0.1

Type RM Length L Ch R = 1 ,18831   ,469,469,469
BEGIN DESCRIPTION:
Mountain Creek 40.0
END DESCRIPTION:
XS GIS Cut Line= 3
        2216475.     13853525.03        2216425.       13853225.
      2216325.02     13853075.04
#Sta/Elev= 30
  4695.9  958.24  4723.8  953.89  4736.5  950.51  4746.6  941.03  4756.8  937.53
  4784.6  938.84  4817.6  938.31  4837.9  932.27  4845.5   928.5  4850.5  927.22
  4878.4  922.29  4884.9  922.05  4898.7  921.75  4906.3  920.42  4911.4  920.86
  4929.1  917.55  4939.2  913.43  4957.3  911.99  4957.6  911.49  4961.8  911.99
  4967.1  912.92  4979.8  912.35  5003.1  915.61  5004.9  916.57  5007.6  918.01
  5058.7  921.25  5085.7   924.7  5115.7  926.12  5157.8  930.33  5180.3  930.84
#Mann= 5 ,-1 , 0
  4695.9    .035       0  4884.9    .063       0  4957.3    .063       0
  4961.8    .063       0  5004.9    .035       0
Bank Sta=4957.3,4961.8
XS Rating Curve= 0 ,0
Exp/Cntr=0.3,0.1

Type RM Length L Ch R = 1 ,18362   ,482,482,482
BEGIN DESCRIPTION:
Mountain Creek 39.0
END DESCRIPTION:
XS GIS Cut Line= 3
      2216821.08     13853442.21        2216725.       13852925.
      2216764.16     13852511.51
#Sta/Elev= 30
  4473.5  953.17  4477.6  951.15  4482.7  951.19  4521.5  946.73  4530.4  941.74
  4535.5  943.11  4541.9  937.51    4552  936.19  4593.4  935.85  4613.1  934.56
  4641.1  931.39  4646.2  931.69  4693.9  927.79  4867.5  918.25  4915.3  913.23
  4948.7  911.45  4968.1  911.52  4989.4  906.66  5007.1  904.52  5007.5  904.02
  5012.2  904.52  5029.7  916.82  5039.7  921.36  5069.9  925.52  5120.1  927.79
    5162     926  5170.3     928  5200.5  931.75    5331  941.23  5414.9  949.35
#Mann= 4 ,-1 , 0
  4473.5    .035       0  4989.4     .12       0  5007.1     .05       0
  5012.2     .12       0
Bank Sta=5007.1,5012.2
XS Rating Curve= 0 ,0
Exp/Cntr=0.3,0.1

Type RM Length L Ch R = 1 ,17880   ,484,484,484
BEGIN DESCRIPTION:
Mountain Creek 38.0
END DESCRIPTION:
XS GIS Cut Line= 3
      2217085.58     13853629.75        2217175.       13852925.
        2217275.     13852525.01
#Sta/Elev= 30
  4289.2  958.12  4314.2  959.08  4321.8  958.18  4354.5  945.71  4394.8  939.01
  4401.8  936.35    4425  934.78  4445.2  931.45  4475.4  929.75  4505.7  924.68
    4546     922    4877  915.54    4929  907.91  4976.1   904.1  5007.4   901.1
  5007.8   900.6  5012.5   901.1  5022.8  901.35  5040.8  905.36  5058.9  914.33
  5092.4  920.01  5154.2  934.67  5187.7  940.91    5247  958.64  5270.2  963.31
  5329.5   978.5  5388.7  996.24  5393.9  996.49  5409.3 1002.97  5411.9 1002.97
#Mann= 4 ,-1 , 0
  4289.2    .035       0  4976.1     .12       0  5007.4     .05       0
  5012.5     .12       0
Bank Sta=5007.4,5012.5
XS Rating Curve= 0 ,0
Exp/Cntr=0.3,0.1

Type RM Length L Ch R = 1 ,17396   ,470,470,470
BEGIN DESCRIPTION:
Mountain Creek 37.0
END DESCRIPTION:
XS GIS Cut Line= 3
      2217202.74     13853646.52        2217625.       13853025.
      2217778.65     13852735.78
#Sta/Elev= 30
  4248.6  943.06  4286.7  934.29  4316.1  931.62  4318.7  931.14  4381.7  922.19
  4480.6  916.83  4841.6  906.77  4899.7  904.71  4935.6  900.97  4955.5  901.09
  4989.9  896.67  4990.3  896.17  4995.1  896.67  5008.2  898.07  5022.6  896.67
  5030.1  898.08  5035.8  901.05  5045.3  908.89  5052.1  920.02  5074.1   943.7
  5090.4  946.89  5101.9  954.74  5124.6  962.81  5178.3  978.17  5249.9 1001.94
  5282.6 1010.33  5288.2 1013.94  5304.6 1019.82  5310.2 1023.71  5327.5 1028.68
#Mann= 6 ,-1 , 0
  4248.6    .035       0  4316.1     .12       0  4318.7    .035       0
  4841.6     .12       0  4989.9     .05       0  4995.1     .12       0
Bank Sta=4989.9,4995.1
XS Rating Curve= 0 ,0
Exp/Cntr=0.3,0.1

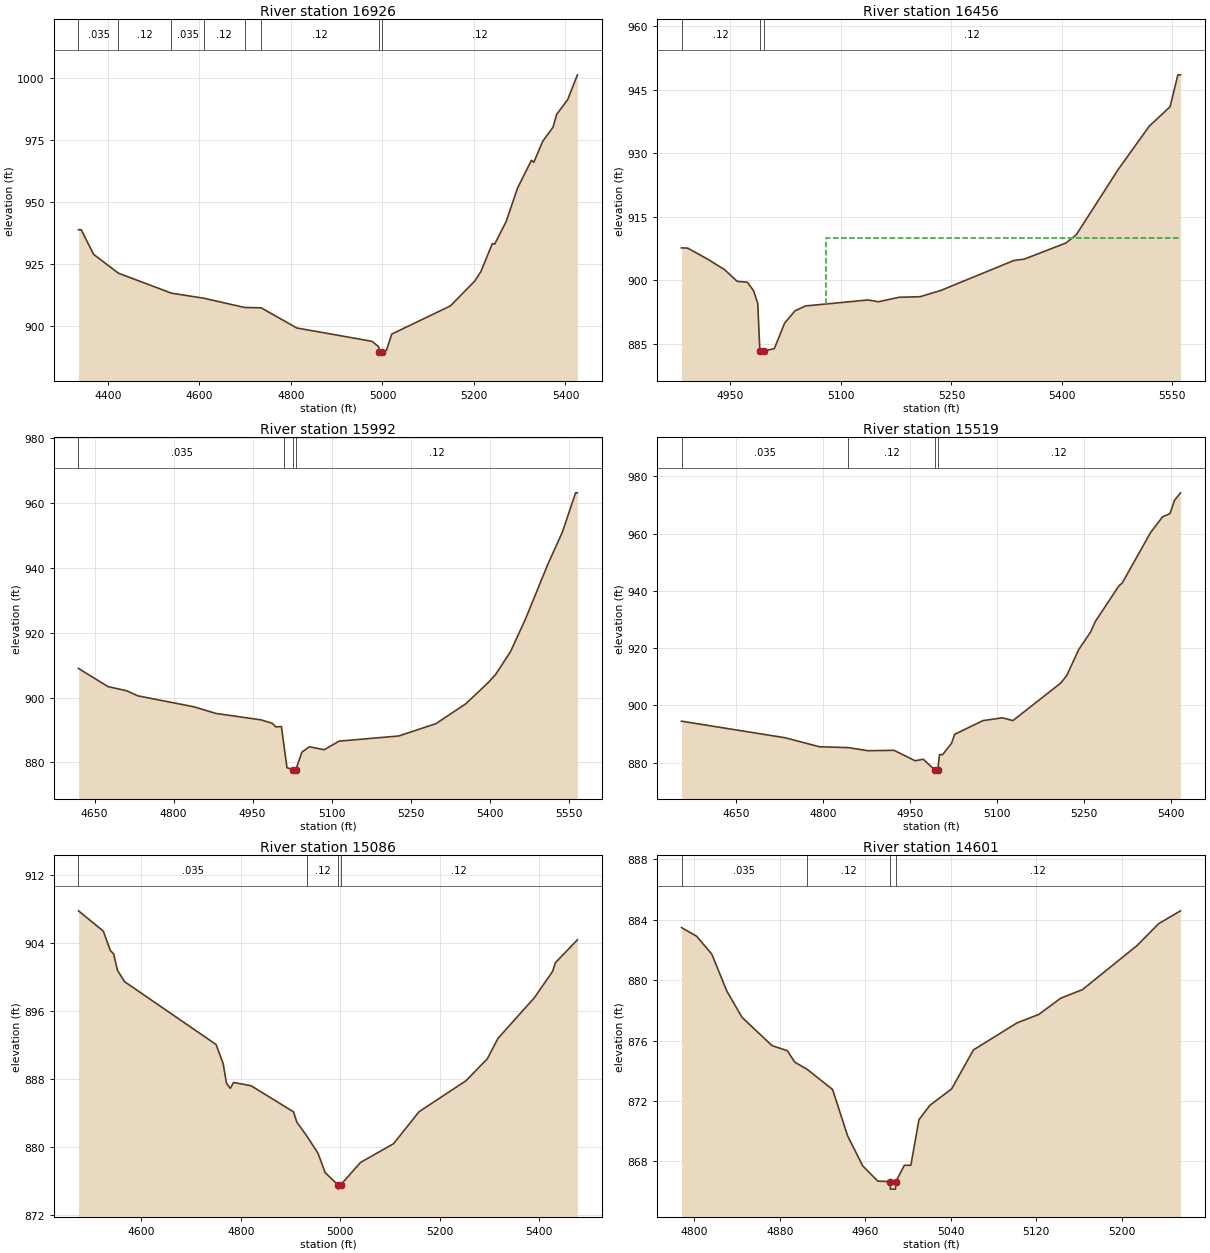
Type RM Length L Ch R = 1 ,16926   ,470,470,470
BEGIN DESCRIPTION:
Mountain Creek 36.0
END DESCRIPTION:
XS GIS Cut Line= 3
        2217340.     13853767.04        2217875.       13853375.
      2218025.01     13852974.97
#Sta/Elev= 30
  4335.6  938.95  4341.6  938.95  4368.6  929.06  4422.8  921.46  4538.7  913.41
  4610.1  911.35  4698.6  907.64    4735  907.49  4812.9  899.37  4976.9  894.02
  4991.5  891.87  4993.2  889.75  4993.6  889.25  4998.4  889.75  5008.7  890.38
  5020.2  896.91  5148.4  908.27  5201.8   918.3  5215.1  922.09  5240.1   933.4
  5245.4  933.19  5270.3  942.26  5295.2  955.75  5325.5  966.92  5330.8  966.15
  5350.4  974.65  5372.7  980.25  5380.7  985.44  5404.7  991.35  5426.1 1001.36
#Mann= 8 ,-1 , 0
  4335.6    .035       0  4422.8     .12       0  4538.7    .035       0
  4610.1     .12       0  4698.6    .035       0    4735     .12       0
  4993.2     .05       0  4998.4     .12       0
Bank Sta=4993.2,4998.4
XS Rating Curve= 0 ,0
Exp/Cntr=0.3,0.1

Type RM Length L Ch R = 1 ,16456   ,464,464,464
BEGIN DESCRIPTION:
Mountain Creek 35.0
END DESCRIPTION:
XS GIS Cut Line= 3
      2217924.98     13853875.04        2217975.       13853775.
      2218374.98     13853375.02
#Sta/Elev= 30
  4883.5  907.67  4891.9  907.62  4919.9  904.92  4942.2  902.51    4959  899.78
    4973  899.56  4981.4  897.54    4987  894.59  4989.9  883.33  4990.3  882.83
  4994.9  882.83  4995.3  883.33  5009.5  883.89  5023.6  889.94  5037.8  892.84
  5051.9  893.97  5136.8  895.38  5150.9  894.96  5179.2  896.02  5207.5  896.15
  5235.8  897.64  5334.8   904.7  5348.9  905.02  5405.5  908.83  5419.6  910.79
  5476.2  926.12  5518.6   936.4  5546.9     941  5557.5  948.53    5561  948.53
#Mann= 3 ,-1 , 0
  4883.5     .12       0  4989.9     .05       0  4995.3     .12       0
#XS Ineff= 2 , 0
       0                    5080       0     910
Permanent Ineff=
       F       F
Bank Sta=4989.9,4995.3
XS Rating Curve= 0 ,0
Exp/Cntr=0.3,0.1

Type RM Length L Ch R = 1 ,15992   ,473,473,473
BEGIN DESCRIPTION:
Mountain Creek 34.0
END DESCRIPTION:
XS GIS Cut Line= 3
      2218090.04     13854229.02        2218375.       13853975.
      2218774.98     13853575.02
#Sta/Elev= 30
  4619.5     909  4675.6  903.38  4710.7  902.11  4732.4  900.52  4838.6  897.15
  4880.7  895.09  4965.7  893.12  4987.4  892.05  4994.1  890.95  5004.8  891.04
  5010.5  884.21  5015.4  878.33  5026.8  877.78  5027.2  877.28  5032.3  877.78
  5043.7  883.14  5057.8   884.8  5086.1  883.89  5114.4  886.54  5227.5  888.13
  5298.2  891.94  5354.8  898.06  5397.2  904.58  5411.4  907.09  5439.7  914.14
  5467.9  924.14  5510.4  941.03  5538.6  951.22  5563.4  963.22  5566.9  963.22
#Mann= 4 ,-1 , 0
  4619.5    .035       0  5010.5     .12       0  5026.8    .035       0
  5032.3     .12       0
Bank Sta=5026.8,5032.3
XS Rating Curve= 0 ,0
Exp/Cntr=0.3,0.1

Type RM Length L Ch R = 1 ,15519   ,433,433,433
BEGIN DESCRIPTION:
Mountain Creek 33.0
END DESCRIPTION:
XS GIS Cut Line= 3
      2218375.03     13854174.98        2218775.       13853975.
        2218875.     13853574.99
#Sta/Elev= 30
  4556.5  894.49  4735.3  888.69    4794  885.56  4843.8  885.26  4877.9  884.17
  4922.6  884.32    4959  880.66  4972.9  881.21  4992.5  877.55    4993  877.05
    4998  877.55  5000.9  882.82  5006.3  882.82  5021.7  886.77  5026.9  889.89
  5075.8  894.69  5109.3  895.66  5127.4   894.7  5209.8   907.8  5220.1  910.43
  5240.8  919.51  5261.4  925.69  5269.1  929.22  5310.3  941.84  5315.5  942.66
  5364.4  960.32  5385.1  965.83  5397.9  966.96  5405.7  971.58    5416  974.22
#Mann= 4 ,-1 , 0
  4556.5    .035       0  4843.8     .12       0  4992.5     .05       0
    4998     .12       0
Bank Sta=4992.5,4998
XS Rating Curve= 0 ,0
Exp/Cntr=0.3,0.1

Type RM Length L Ch R = 1 ,15086   ,485,485,485
BEGIN DESCRIPTION:
Mountain Creek 32.0
END DESCRIPTION:
XS GIS Cut Line= 3
      2218374.98     13854725.02        2218775.       13854375.
      2219024.98     13853975.03
#Sta/Elev= 30
  4473.4  907.75  4523.3  905.37  4537.5  903.08  4544.1  902.69  4551.7  900.77
    4566  899.43  4750.1  892.04  4764.3  889.79    4771  887.48  4778.6   886.9
  4785.2  887.58  4820.3   887.2  4905.8  884.13  4912.4  882.92  4932.9  881.26
  4955.1  879.25  4969.3  876.99  4995.1  875.55  4995.5  875.05  5000.6  875.55
  5040.3  878.18  5106.9  880.39  5158.2  884.15  5252.6  887.79  5295.6  890.38
  5316.8  892.76    5390  897.54  5426.5  900.62  5432.4  901.66  5476.6  904.35
#Mann= 4 ,-1 , 0
  4473.4    .035       0  4932.9     .12       0  4995.1     .05       0
  5000.6     .12       0
Bank Sta=4995.1,5000.6
XS Rating Curve= 0 ,0
Exp/Cntr=0.3,0.1

Type RM Length L Ch R = 1 ,14601   ,328,328,328
BEGIN DESCRIPTION:
Mountain Creek 31.0
END DESCRIPTION:
XS GIS Cut Line= 3
      2219025.01     13854674.99        2219175.       13854525.
      2219124.99     13854274.97
#Sta/Elev= 30
  4787.9  883.49    4802  882.92  4816.2  881.74  4830.3  879.29  4844.5  877.55
  4872.7  875.67  4886.9  875.34  4893.9  874.58  4905.6   874.1  4929.3  872.77
  4943.4   869.7  4957.6   867.7  4971.7   866.7  4983.1  866.67  4983.5  866.17
  4988.2  866.17  4988.6  866.67  4996.5  867.75  5002.6  867.75  5010.2  870.77
  5020.4  871.72  5040.8  872.81  5061.2  875.39    5102  877.18  5122.4  877.74
  5142.8  878.81  5163.2  879.38  5214.2  882.29  5234.6  883.75    5255   884.6
#Mann= 4 ,-1 , 0
  4787.9    .035       0  4905.6     .12       0  4983.1     .05       0
  4988.6     .12       0
Bank Sta=4983.1,4988.6
XS Rating Curve= 0 ,0
Exp/Cntr=0.3,0.1

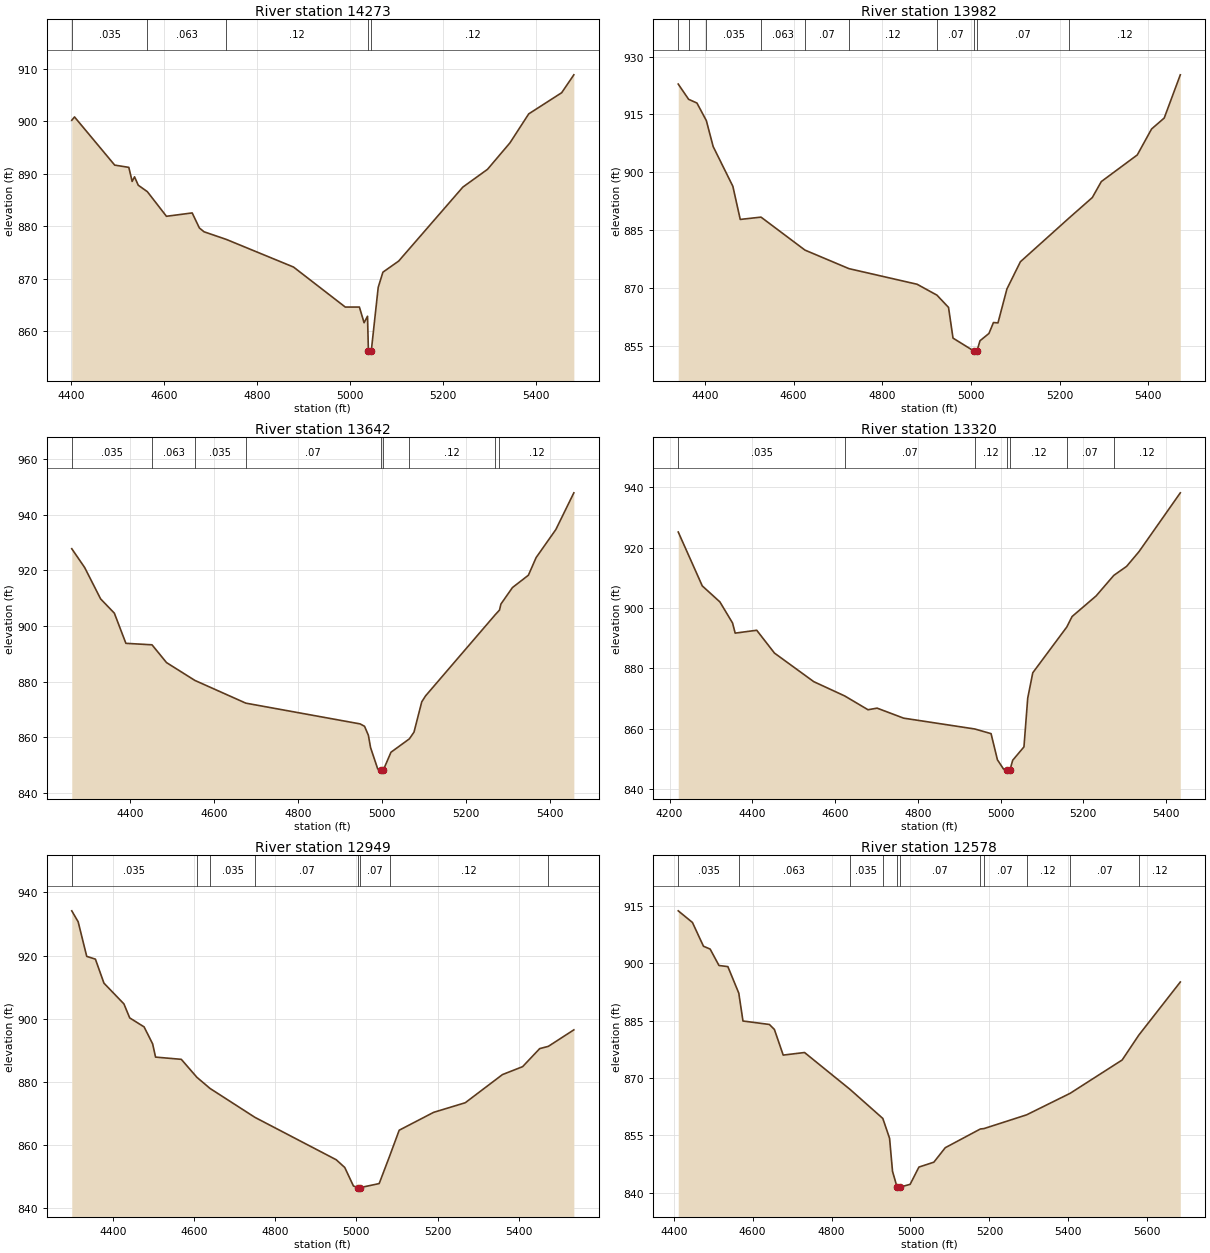
Type RM Length L Ch R = 1 ,14273   ,291,291,291
BEGIN DESCRIPTION:
B19680
END DESCRIPTION:
XS GIS Cut Line= 2
      2219409.13     13855116.29      2219579.74     13854049.14
#Sta/Elev= 30
  4401.2  900.17  4407.1  900.81  4493.6  891.63    4524   891.2  4531.2  888.52
  4536.3   889.4  4544.3   887.8  4563.9  886.57    4605  881.88  4660.4  882.52
  4675.9  879.65  4686.1  878.92  4733.7  877.48  4878.5  872.21  4989.9  864.59
  5020.3  864.59  5030.4   861.6  5037.8  862.84  5039.7  856.31  5040.2  855.81
    5046  856.31  5060.8  868.34  5070.9  871.23  5104.9  873.35    5243  887.44
  5296.1  890.83  5344.3  895.86  5384.8  901.39  5455.7  905.42  5481.9  908.83
#Mann= 5 ,-1 , 0
  4401.2    .035       0  4563.9    .063       0  4733.7     .12       0
  5039.7     .05       0    5046     .12       0
Bank Sta=5039.7,5046
XS Rating Curve= 0 ,0
Exp/Cntr=0.3,0.1

Type RM Length L Ch R = 1 ,13982   ,340,340,340
BEGIN DESCRIPTION:
B19679
END DESCRIPTION:
XS GIS Cut Line= 2
      2219687.02     13855176.59      2219871.03     13854059.14
#Sta/Elev= 30
  4339.6  922.89    4363  918.94  4381.8  917.97    4403  913.42  4418.4  906.68
  4462.8  896.37  4479.5  887.77  4526.3  888.37  4625.5  879.81  4724.7     875
  4878.4  870.95  4923.2  868.12  4949.3  864.94  4959.4  856.98    5007  853.58
  5007.5  853.08  5013.3  853.58  5020.2  856.28  5040.5  858.19  5050.6  861.02
  5060.8  860.92    5081  869.73  5111.4  876.79  5220.8   888.1  5273.6  893.45
  5293.9  897.59    5375   904.5  5407.3  911.24  5435.8  914.08  5472.1  925.29
#Mann= 10 ,-1 , 0
  4339.6    .035       0    4363    .063       0    4403    .035       0
  4526.3    .063       0  4625.5     .07       0  4724.7     .12       0
  4923.2     .07       0    5007     .05       0  5013.3     .07       0
  5220.8     .12       0
Bank Sta=5007,5013.3
XS Rating Curve= 0 ,0
Exp/Cntr=0.3,0.1

Type RM Length L Ch R = 1 ,13642   ,322,322,322
BEGIN DESCRIPTION:
B19678
END DESCRIPTION:
XS GIS Cut Line= 2
       2219901.3     13855280.35      2220252.64     13854139.32
#Sta/Elev= 30
  4261.9  927.76  4292.6  920.99  4330.5  909.73  4363.2  904.59  4390.6  893.76
  4452.7  893.23  4487.2  886.84  4554.7  880.43  4675.7  872.27  4947.6  864.81
  4958.1  863.95  4967.2  860.75  4972.4  856.32  4989.5   848.6  4996.7  848.34
  4997.2  847.84  5003.1  848.34  5020.9  854.62  5064.7  859.44  5075.7  861.86
  5094.1  872.73  5103.2  874.88  5268.8  904.03    5279  905.71  5282.4  907.88
  5309.8   913.8  5347.7  918.23  5366.1  924.57    5413  934.65  5455.8  947.84
#Mann= 9 ,-1 , 0
  4261.9    .035       0  4452.7    .063       0  4554.7    .035       0
  4675.7     .07       0  4996.7     .05       0  5003.1     .07       0
  5064.7     .12       0  5268.8     .07       0    5279     .12       0
Bank Sta=4996.7,5003.1
XS Rating Curve= 0 ,0
Exp/Cntr=0.3,0.1

Type RM Length L Ch R = 1 ,13320   ,371,371,371
BEGIN DESCRIPTION:
B19677
END DESCRIPTION:
XS GIS Cut Line= 2
      2220008.42     13855327.24      2220637.68     13854289.64
#Sta/Elev= 30
  4221.1  925.13  4279.2   907.3  4321.8     902  4352.4  895.02  4358.7  891.67
  4410.8  892.62  4453.7  885.07  4548.7  875.61  4623.7  870.87  4679.8  866.32
  4701.8  866.85  4765.8  863.54    4938  859.95  4977.2  858.41  4992.6  849.76
  5007.3   846.7  5016.6  846.51  5017.1  846.01  5023.1  846.51  5029.5  849.61
  5056.7  854.03  5065.8  870.16    5078  878.55  5160.2  893.69    5173  897.16
  5231.2  903.99  5273.8  910.77  5304.8  913.76  5334.8  918.64  5434.6  938.09
#Mann= 7 ,-1 , 0
  4221.1    .035       0  4623.7     .07       0    4938     .12       0
  5016.6     .05       0  5023.1     .12       0  5160.2     .07       0
  5273.8     .12       0
Bank Sta=5016.6,5023.1
XS Rating Curve= 0 ,0
Exp/Cntr=0.3,0.1

Type RM Length L Ch R = 1 ,12949   ,371,371,371
BEGIN DESCRIPTION:
B19676
END DESCRIPTION:
XS GIS Cut Line= 2
      2220082.09     13855424.31      2220976.06     13854567.17
#Sta/Elev= 30
  4297.8  934.16  4313.6  930.67  4334.7  919.73  4356.1  918.86  4377.2  911.25
  4426.5  904.67  4440.7  900.25  4476.2   897.4  4497.3  892.01  4504.5  887.83
    4568  887.12  4606.6  881.41  4639.1  877.88  4749.8  868.73  4950.1  855.32
  4971.2  852.87  4992.6  847.01  5003.5  846.51    5004  846.01    5010  846.51
  5056.1  847.77  5081.8  856.44  5105.5  864.67  5190.4  870.33  5268.4  873.37
  5360.2  882.29  5409.9   884.8  5452.1  890.52  5473.3  891.23  5536.3  896.46
#Mann= 8 ,-1 , 0
  4297.8    .035       0  4606.6    .063       0  4639.1    .035       0
  4749.8     .07       0  5003.5     .05       0    5010     .07       0
  5081.8     .12       0  5473.3     .07       0
Bank Sta=5003.5,5010
XS Rating Curve= 0 ,0
Exp/Cntr=0.3,0.1

Type RM Length L Ch R = 1 ,12578   ,417,417,417
BEGIN DESCRIPTION:
B19675
END DESCRIPTION:
XS GIS Cut Line= 2
       2220534.1     13855722.25      2221096.56     13854580.58
#Sta/Elev= 30
  4411.3  913.67  4447.3  910.63  4475.3  904.42  4492.2  903.68  4514.6  899.39
  4537.1   899.1  4564.8  892.17  4575.4  884.89  4642.3  883.99    4655   882.7
  4677.4  875.99  4731.5  876.66  4846.7  867.04  4929.9  859.44    4947  854.26
  4954.5  845.63  4966.1  841.48  4966.6  840.98  4972.7  841.48  4999.1  842.23
  5021.4  846.74  5059.3  848.02  5088.2   851.8  5177.2  856.69  5186.2  856.79
  5294.3  860.38  5404.8  866.01  5536.6  874.71  5578.9  881.22    5684  895.08
#Mann= 11 ,-1 , 0
  4411.3    .035       0  4564.8    .063       0  4846.7    .035       0
  4929.9     .07       0  4966.1     .05       0  4972.7     .07       0
  5177.2     .12       0  5186.2     .07       0  5294.3     .12       0
  5404.8     .07       0  5578.9     .12       0
Bank Sta=4966.1,4972.7
XS Rating Curve= 0 ,0
Exp/Cntr=0.3,0.1

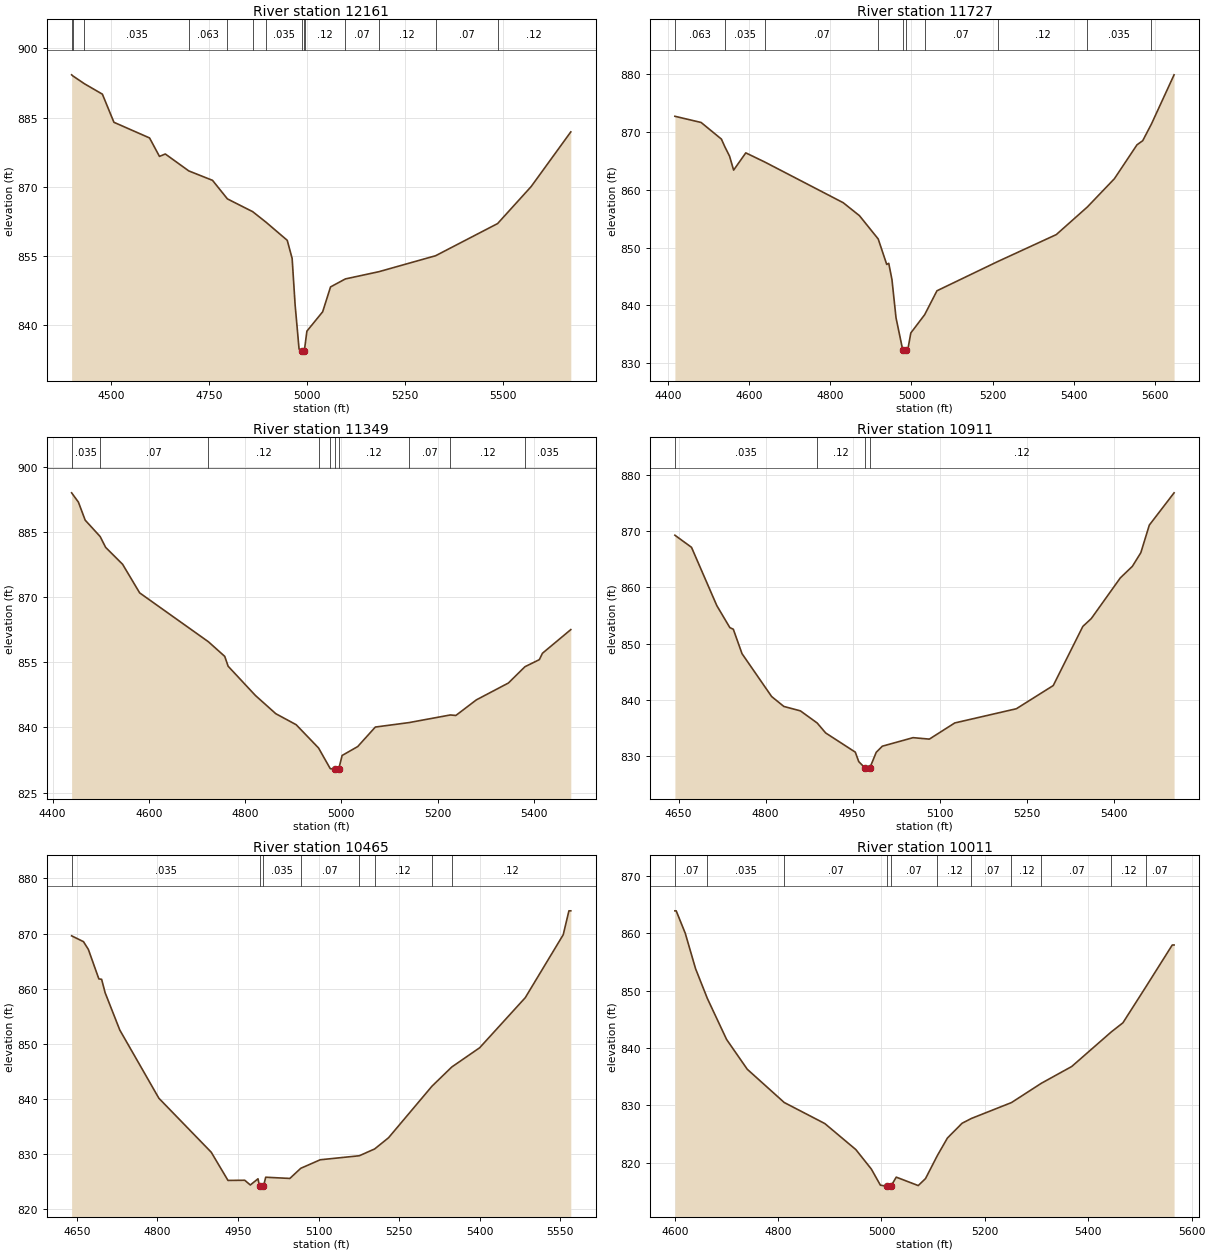
Type RM Length L Ch R = 1 ,12161   ,434,434,434
BEGIN DESCRIPTION:
B19674
END DESCRIPTION:
XS GIS Cut Line= 2
      2221109.95     13855923.14      2221223.79     13854654.24
#Sta/Elev= 30
  4399.5  894.28  4402.5  894.05  4432.3  892.34    4478  890.09  4507.5  883.99
  4598.4   880.6  4623.7   876.6  4638.6  877.12  4698.6  873.45  4759.1  871.41
  4797.1  867.39  4861.8  864.61  4895.6  862.34  4949.8  858.41  4962.3  854.48
  4969.9  844.43    4980  834.84  4986.7  834.46  4987.2  833.96  4993.4  834.46
  4994.1  834.91    5000  838.73  5040.2  842.92  5060.3  848.31  5098.1  850.04
  5183.7  851.61  5328.5  855.07  5486.7  862.04  5572.3  870.06  5673.5  881.91
#Mann= 14 ,-1 , 0
  4399.5    .035       0  4402.5    .063       0  4432.3    .035       0
  4698.6    .063       0  4797.1    .035       0  4861.8    .094       0
  4895.6    .035       0  4986.7     .05       0  4993.4    .035       0
  4994.1     .12       0  5098.1     .07       0  5183.7     .12       0
  5328.5     .07       0  5486.7     .12       0
Bank Sta=4986.7,4993.4
XS Rating Curve= 0 ,0
Exp/Cntr=0.3,0.1

Type RM Length L Ch R = 1 ,11727   ,378,378,378
BEGIN DESCRIPTION:
B19673
END DESCRIPTION:
XS GIS Cut Line= 3
      2221561.94     13855859.58      2221582.03     13855276.99
      2221475.09     13854638.72
#Sta/Elev= 30
  4417.1  872.68  4481.7  871.61  4531.7  868.74  4540.2  867.41  4551.8  865.79
  4561.8  863.38  4591.8  866.36  4638.6  864.78  4831.9  857.75  4871.9  855.51
  4918.1  851.49  4939.1  847.09  4944.1  847.28    4952  844.47    4962  837.87
  4978.7  832.27  4979.2  831.77  4985.4  832.27    4992  832.75  4998.5  835.26
  5032.6  838.41  5062.9  842.54  5212.4  847.58  5356.9  852.24  5433.6  857.02
  5500.2   861.9  5555.8  867.75  5569.9  868.46  5591.3  871.33  5647.2  879.84
#Mann= 10 ,-1 , 0
  4417.1    .063       0  4540.2    .035       0  4638.6     .07       0
  4918.1    .035       0  4978.7    .035       0  4985.4    .035       0
  5032.6     .07       0  5212.4     .12       0  5433.6    .035       0
  5591.3     .07       0
Bank Sta=4978.7,4985.4
XS Rating Curve= 0 ,0
Exp/Cntr=0.3,0.1

Type RM Length L Ch R = 1 ,11349   ,438,438,438
BEGIN DESCRIPTION:
Mountain Creek 24.0
END DESCRIPTION:
XS GIS Cut Line= 3
      2222324.97     13855574.97        2221925.       13855175.
      2221675.02     13854775.03
#Sta/Elev= 30
  4439.4  893.96  4453.5  891.82  4467.6  887.67  4498.7   883.9  4510.1  881.41
  4545.4  877.51  4580.8  870.94  4723.6   859.7  4757.6  856.33  4764.6  854.07
  4821.2  847.35  4863.6  843.15    4906  840.61  4952.5  835.26  4976.9  830.49
  4987.2  830.43  4987.7  829.93  4994.5  830.43  5001.5  833.53  5033.9  835.58
  5070.5  840.07  5140.7   841.1  5226.3  842.85  5237.9  842.74  5280.4  846.32
    5347   850.2  5381.4  853.95  5411.3  855.58  5417.8  857.05  5476.7  862.49
#Mann= 10 ,-1 , 0
  4439.4    .035       0  4498.7     .07       0  4723.6     .12       0
  4952.5     .07       0  4976.9     .12       0  4987.2     .05       0
  4994.5     .12       0  5140.7     .07       0  5226.3     .12       0
  5381.4    .035       0
Bank Sta=4987.2,4994.5
XS Rating Curve= 0 ,0
Exp/Cntr=0.3,0.1

Type RM Length L Ch R = 1 ,10911   ,446,446,446
BEGIN DESCRIPTION:
Mountain Creek 23.0
END DESCRIPTION:
XS GIS Cut Line= 3
      2222475.02     13855275.04        2222275.       13854975.
        2221975.       13854575.
#Sta/Elev= 30
  4643.7  869.29  4672.3  867.14  4715.9  856.77  4738.4  852.84  4744.4  852.55
  4759.4   848.2  4810.5  840.56  4831.5   838.8  4860.1  838.01    4889  835.85
  4903.6  834.08  4954.7  830.66  4960.7  828.97  4972.1  827.78  4972.6  827.28
  4979.5  827.78  4990.8  830.63  5001.3  831.72  5054.3  833.24  5082.4  832.98
  5126.2  835.86  5232.4  838.39    5296  842.52    5347  853.05  5361.6  854.45
  5411.6  861.69  5432.4  863.75    5447  866.18  5461.6  871.09  5504.3  876.84
#Mann= 4 ,-1 , 0
  4643.7    .035       0    4889     .12       0  4972.1     .05       0
  4979.5     .12       0
Bank Sta=4972.1,4979.5
XS Rating Curve= 0 ,0
Exp/Cntr=0.3,0.1

Type RM Length L Ch R = 1 ,10465   ,454,454,454
BEGIN DESCRIPTION:
Mountain Creek 22.0
END DESCRIPTION:
XS GIS Cut Line= 3
      2222774.99     13855174.96        2222675.       13854825.
      2222275.03     13854425.03
#Sta/Elev= 30
  4640.2  869.59  4662.3  868.53  4671.4  867.12  4690.9  861.78  4696.1  861.69
  4702.6  859.26  4729.9  852.49  4802.7   840.1  4900.2   830.3  4931.4  825.18
  4962.6  825.21    4973  824.35  4987.3  825.48  4990.1   824.1  4990.6   823.6
  4997.5   824.1  5001.6  825.76  5046.6  825.54  5066.9  827.38  5103.2  828.93
    5176  829.66  5204.6   830.9  5230.4  832.93  5311.2  842.28  5348.1  845.77
  5400.1  849.27    5485  858.36  5555.7  869.79  5566.3  874.13  5569.8  874.13
#Mann= 8 ,-1 , 0
  4640.2    .035       0  4990.1    .035       0  4997.5    .035       0
  5066.9     .07       0    5176    .035       0  5204.6     .12       0
  5311.2    .035       0  5348.1     .12       0
Bank Sta=4990.1,4997.5
XS Rating Curve= 0 ,0
Exp/Cntr=0.3,0.1

Type RM Length L Ch R = 1 ,10011   ,417,417,417
BEGIN DESCRIPTION:
Mountain Creek 21.0
END DESCRIPTION:
XS GIS Cut Line= 3
        2223075.     13855074.95        2223075.       13854675.
      2222675.03     13854275.03
#Sta/Elev= 30
  4600.4  863.94  4602.9  863.94  4620.4  860.04  4640.4  853.84  4663.3  848.63
  4700.4   841.5  4740.4   836.3  4811.9   830.5  4890.4  826.83  4950.4  822.29
  4980.4  818.89  4997.9  816.08  5010.7  815.89  5011.2  815.39  5018.2  815.89
  5028.6  817.48  5071.1  816.01  5085.2  817.23  5108.1  821.25  5127.6  824.31
  5155.9  826.88    5174  827.72  5251.5  830.49  5309.3  833.86    5368  836.78
  5444.6  842.82    5467   844.4  5512.1  850.77  5562.5  857.98    5566  857.98
#Mann= 11 ,-1 , 0
  4600.4     .07       0  4663.3    .035       0  4811.9     .07       0
  5010.7     .05       0  5018.2     .07       0  5108.1     .12       0
    5174     .07       0  5251.5     .12       0  5309.3     .07       0
  5444.6     .12       0  5512.1     .07       0
Bank Sta=5010.7,5018.2
XS Rating Curve= 0 ,0
Exp/Cntr=0.3,0.1

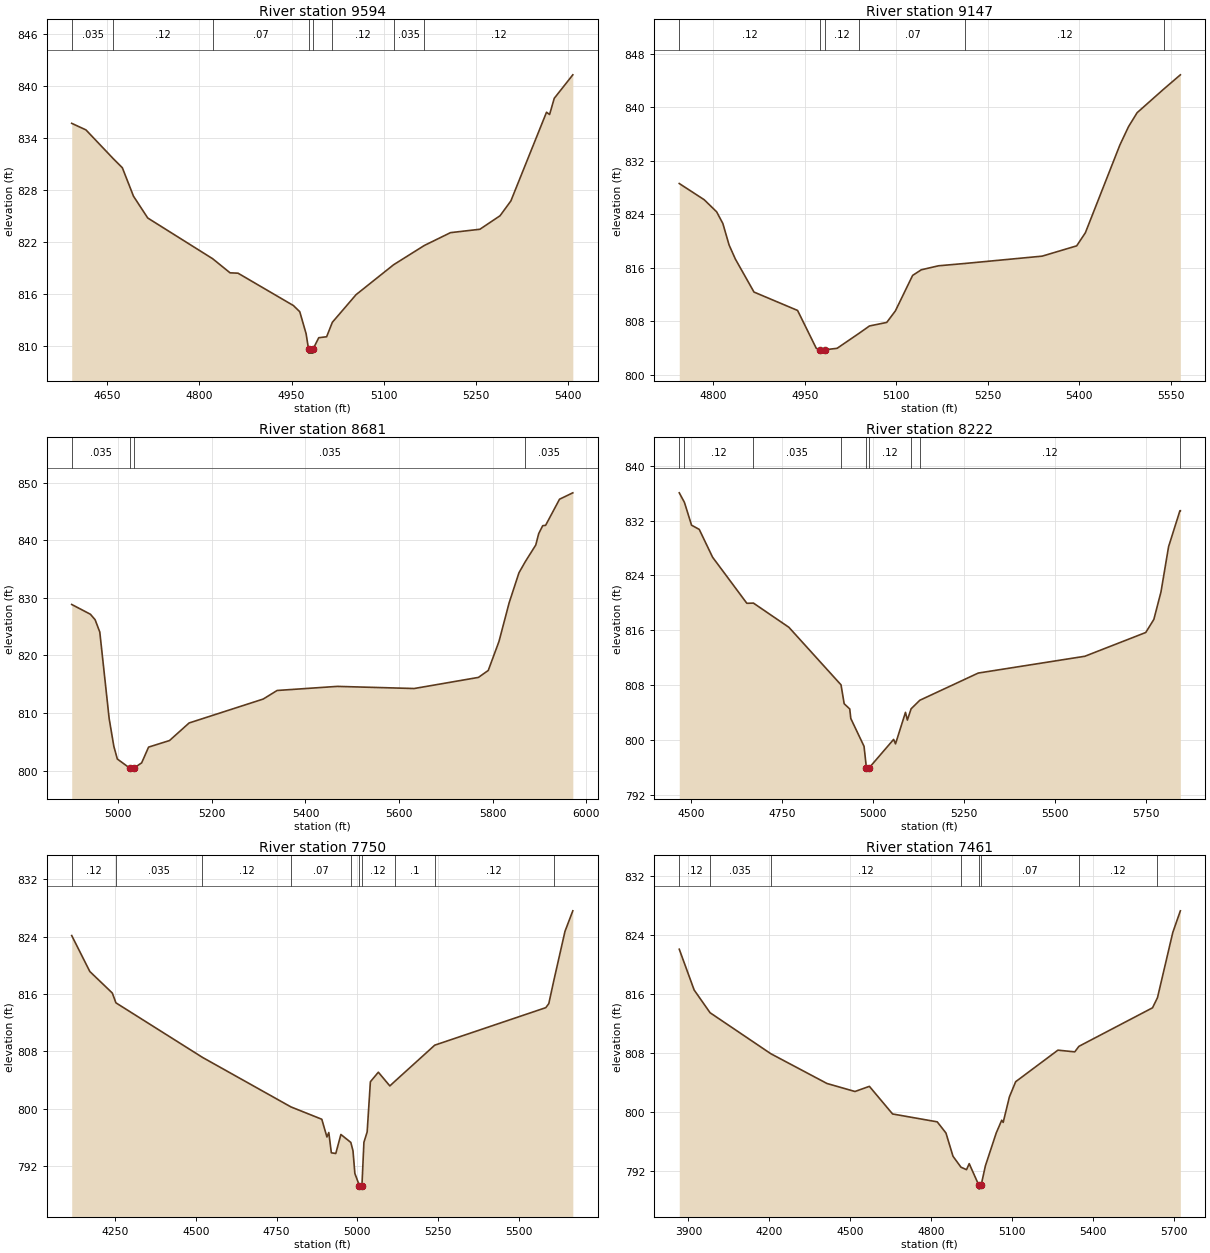
Type RM Length L Ch R = 1 ,9594    ,447,447,447
BEGIN DESCRIPTION:
Mountain Creek 20.0
END DESCRIPTION:
XS GIS Cut Line= 3
        2223475.     13854824.99        2223375.       13854425.
        2223325.     13854025.01
#Sta/Elev= 30
  4592.3  835.66  4615.5   834.9  4659.9  831.58  4674.7  830.53  4692.8  827.25
    4716  824.73  4821.6  820.03    4850   818.4  4862.9  818.36  4953.1  814.62
  4963.4  813.91  4973.7  811.37  4977.6  809.63  4978.1  809.13  4984.7  809.13
  4985.2  809.63  4994.3  810.91  5007.1  811.02  5016.4  812.69    5055  815.88
    5116  819.33  5166.1  821.56  5208.7  823.04  5256.5  823.43  5289.3  824.99
  5306.9   826.7  5364.9  836.94  5369.9  836.68  5377.5  838.55  5407.7  841.26
#Mann= 8 ,-1 , 0
  4592.3    .035       0  4659.9     .12       0  4821.6     .07       0
  4977.6     .05       0  4985.2     .07       0  5016.4     .12       0
    5116    .035       0  5166.1     .12       0
Bank Sta=4977.6,4985.2
XS Rating Curve= 0 ,0
Exp/Cntr=0.3,0.1

Type RM Length L Ch R = 1 ,9147    ,466,466,466
BEGIN DESCRIPTION:
Mountain Creek 19.0
END DESCRIPTION:
XS GIS Cut Line= 3
        2223825.     13854625.01        2223775.       13854375.
      2223374.96     13853974.96
#Sta/Elev= 30
  4744.6  828.59  4785.4  826.17  4805.8  824.36    4816  822.61  4826.2   819.4
  4836.4  817.31    4867  812.36  4938.4  809.61    4969  803.95  4975.4  803.73
  4975.9  803.23  4982.5  803.23    4983  803.73  5003.1  803.95  5039.7  806.23
  5056.1  807.29  5084.4  807.82  5098.6  809.55  5126.8  814.85    5141  815.69
  5169.3  816.29  5213.1  816.64    5339  817.73  5395.5  819.27  5409.7  821.22
  5466.3  834.36  5480.4  837.09  5494.5  839.18  5538.1  842.71  5565.3  844.84
#Mann= 6 ,-1 , 0
  4744.6     .12       0  4975.4     .05       0    4983     .12       0
  5039.7     .07       0  5213.1     .12       0  5538.1    .035       0
Bank Sta=4975.4,4983
XS Rating Curve= 0 ,0
Exp/Cntr=0.3,0.1

Type RM Length L Ch R = 1 ,8681    ,459,459,459
BEGIN DESCRIPTION:
Mountain Creek 18.0
END DESCRIPTION:
XS GIS Cut Line= 3
        2224225.     13854525.03        2224225.       13854425.
      2223424.97     13853874.98
#Sta/Elev= 30
  4900.4  828.83  4940.4  827.13  4950.4  826.18  4960.4  824.04  4980.4  809.03
  4990.4  804.21  4997.9     802  5024.9   800.4  5025.4   799.9  5032.8   800.4
  5049.8  801.33  5064.7  804.07  5109.4  805.21  5151.3  808.26  5309.6  812.41
  5339.4   813.9  5467.9  814.61  5632.3  814.24  5769.6  816.17  5790.6  817.38
  5813.5  822.41  5835.3  829.14  5856.2  834.33  5869.8  836.27  5892.1  839.15
  5898.4  841.13    5907  842.51  5913.1  842.56  5942.9   847.1  5971.3  848.21
#Mann= 4 ,-1 , 0
  4900.4    .035       0  5024.9    .035       0  5032.8    .035       0
  5869.8    .035       0
Bank Sta=5024.9,5032.8
XS Rating Curve= 0 ,0
Exp/Cntr=0.3,0.1

Type RM Length L Ch R = 1 ,8222    ,472,472,472
BEGIN DESCRIPTION:
Mountain Creek 17.0
END DESCRIPTION:
XS GIS Cut Line= 3
      2224678.99      13854496.9      2224427.88     13854095.13
      2223564.04     13853827.27
#Sta/Elev= 30
  4467.6  836.05  4481.8  834.66  4501.4  831.33  4522.6  830.71  4559.2  826.66
  4653.5  819.93  4671.6  819.96  4769.1  816.43  4912.5  808.03  4921.2  805.27
  4936.5  804.51  4939.4  803.12  4975.8  799.06  4982.3  795.94  4982.8  795.44
  4990.2  795.94  5057.2  800.07  5062.4  799.42  5089.8  804.02    5095  802.89
  5105.2  804.53  5129.2  805.78  5289.9  809.75  5583.1   812.2  5750.6  815.67
  5772.9  817.58  5792.5  821.59  5813.4  828.19  5844.6  833.44  5845.8  833.44
#Mann= 9 ,-1 , 0
  4467.6    .035       0  4481.8     .12       0  4671.6    .035       0
  4912.5     .12       0  4982.3     .05       0  4990.2     .12       0
  5105.2    .035       0  5129.2     .12       0  5844.6    .035       0
Bank Sta=4982.3,4990.2
XS Rating Curve= 0 ,0
Exp/Cntr=0.3,0.1

Type RM Length L Ch R = 1 ,7750    ,289,289,289
BEGIN DESCRIPTION:
Mountain Creek 16.0
END DESCRIPTION:
XS GIS Cut Line= 4
      2224759.35     13854366.35      2224521.11     13853815.63
        2224275.       13853675.      2223610.92     13853726.84
#Sta/Elev= 30
  4116.5  824.16  4172.5  819.15    4242  816.15  4253.3  814.78  4520.8  807.18
  4794.5  800.27  4889.9  798.55  4905.7  796.08  4911.5   796.7  4919.4  793.87
  4933.1  793.78  4948.9  796.43  4979.6  795.32  4986.3  794.15  4992.1     791
    5006  789.31  5006.5  788.81    5014  789.31  5020.1  795.34  5030.1  796.78
  5040.1  803.78  5064.7  805.11  5100.3   803.2  5114.7   803.8  5239.1  808.88
  5582.5  814.11  5591.8  814.67  5607.3  817.88  5641.9  824.75  5666.1  827.61
#Mann= 10 ,-1 , 0
  4116.5     .12       0  4253.3    .035       0  4520.8     .12       0
  4794.5     .07       0  4979.6     .12       0    5006     .05       0
    5014     .12       0  5114.7      .1       0  5239.1     .12       0
  5607.3    .035       0
Bank Sta=5006,5014
XS Rating Curve= 0 ,0
Exp/Cntr=0.3,0.1

Type RM Length L Ch R = 1 ,7461    ,241,241,241
BEGIN DESCRIPTION:
B19672
END DESCRIPTION:
XS GIS Cut Line= 4
      2224822.93     13854329.46      2224421.18     13853425.52
       2224220.3     13853415.47      2223610.93     13853690.02
#Sta/Elev= 30
  3866.1  822.08  3921.4  816.54  3980.4  813.46  4205.6   807.9  4413.8  803.86
  4517.8  802.77  4571.3  803.47  4657.3  799.72    4823  798.65  4855.3  797.14
  4881.5  793.98    4911   792.5  4931.6  792.16  4941.6  792.98  4977.6  790.02
  4978.1  789.52  4985.6  790.02  5001.7  792.69  5041.7  797.13  5062.1  798.87
  5067.6  798.58  5090.7  802.04  5113.9   804.1  5270.6  808.38  5333.1  808.15
  5348.5   808.9  5621.6  814.13    5640  815.51  5696.7  824.35  5724.8  827.29
#Mann= 8 ,-1 , 0
  3866.1     .12       0  3980.4    .035       0  4205.6     .12       0
    4911     .07       0  4977.6     .05       0  4985.6     .07       0
  5348.5     .12       0    5640    .035       0
Bank Sta=4977.6,4985.6
XS Rating Curve= 0 ,0
Exp/Cntr=0.3,0.1