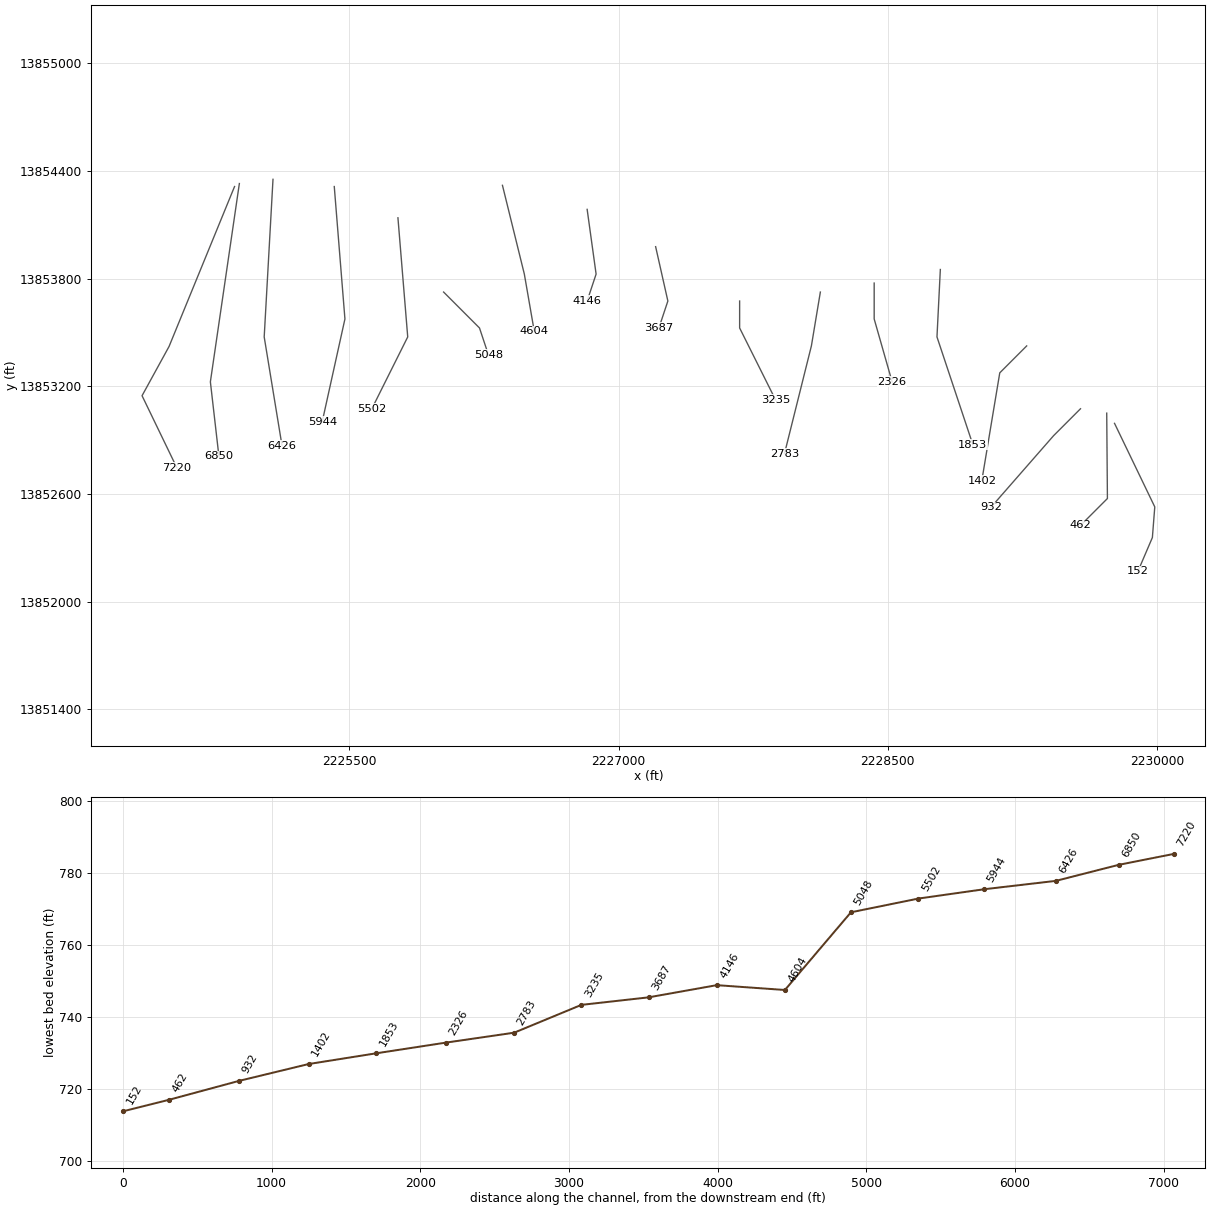
HEC-RAS study Mountain Creek.prj: Mountain Creek Base Level Engineering

--- Mountain Creek.g01 (geometry) --- (continued)

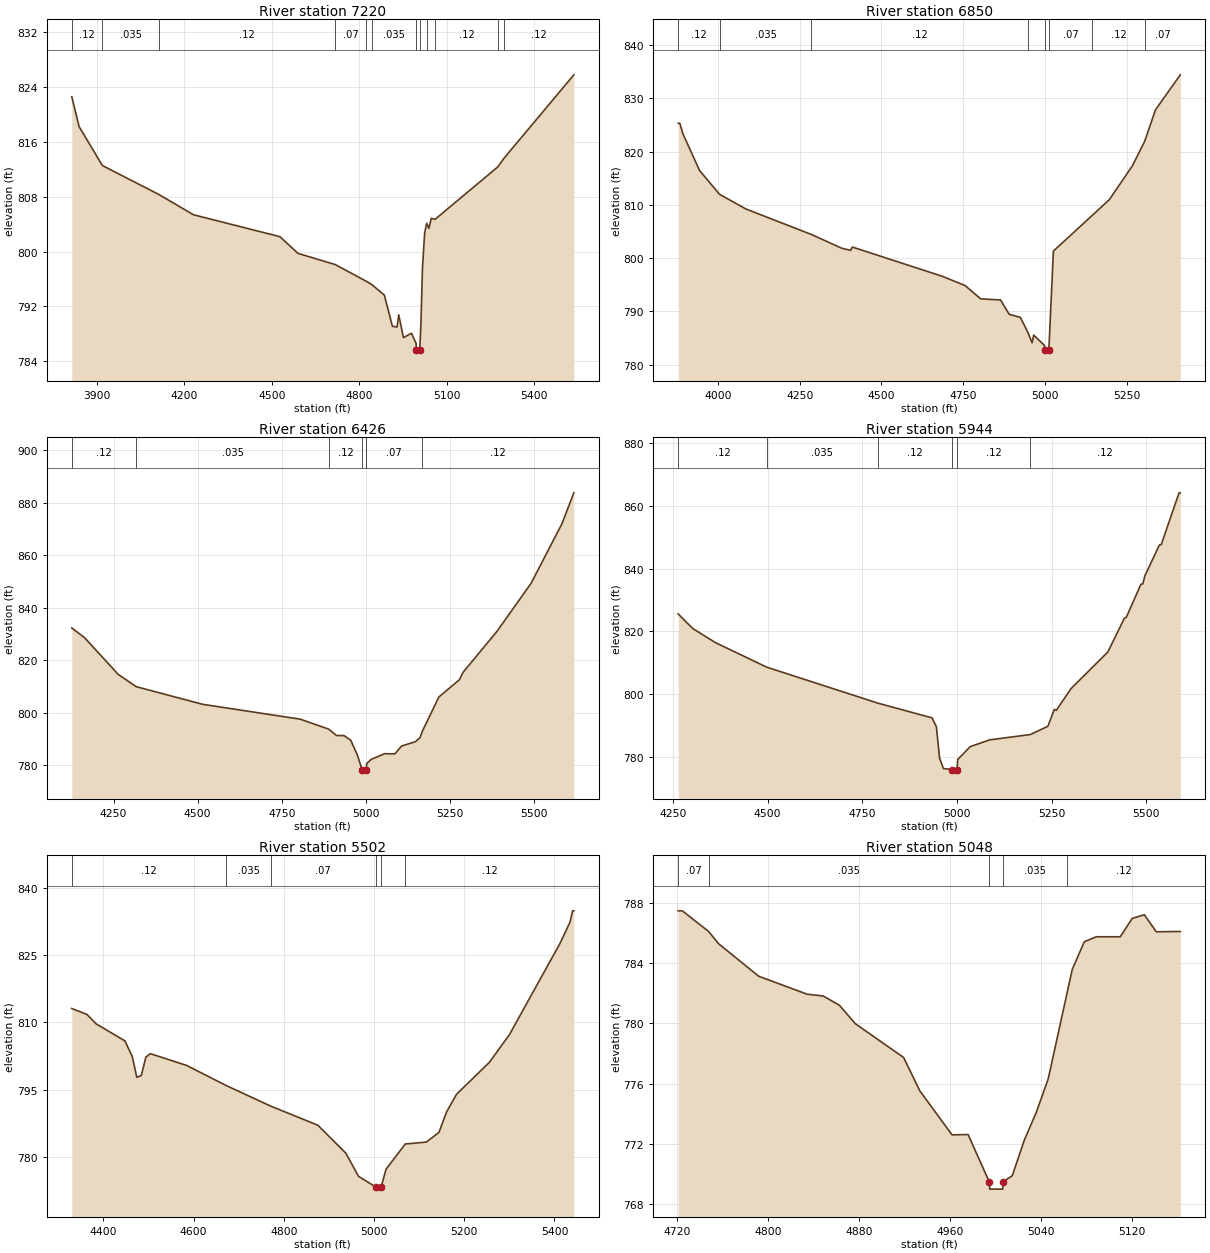
Type RM Length L Ch R = 1 ,7220    ,370,370,370
BEGIN DESCRIPTION:
B19671
END DESCRIPTION:
XS GIS Cut Line= 4
      2224859.77     13854312.72      2224494.84     13853422.17
      2224344.18     13853147.63      2224538.35     13852745.88
#Sta/Elev= 30
  3813.7  822.55  3838.9  818.18  3918.8  812.52  4112.5   808.3  4231.2  805.35
  4527.5  802.16  4589.3  799.73  4716.9   798.1  4824.4  795.65  4842.9  795.17
  4885.7  793.65  4913.2  789.11  4929.3  789.01    4935  790.78  4951.1  787.46
  4978.6   788.1  4994.7   786.6    4995   785.7  4995.5   785.2    5007   785.7
  5010.8  789.16  5016.5  797.65  5023.8  802.68  5030.9  804.11  5038.3  803.37
  5046.7  804.83  5059.7  804.69    5275  812.33  5295.6  813.56  5535.5  825.73
#Mann= 12 ,-1 , 0
  3813.7     .12       0  3918.8    .035       0  4112.5     .12       0
  4716.9     .07       0  4824.4     .12       0  4842.9    .035       0
    4995    .035       0    5007    .035       0  5030.9     .07       0
  5059.7     .12       0    5275     .07       0  5295.6     .12       0
Bank Sta=4995,5007
XS Rating Curve= 0 ,0
Exp/Cntr=0.3,0.1

Type RM Length L Ch R = 1 ,6850    ,424,424,424
BEGIN DESCRIPTION:
Mountain Creek 15.0
END DESCRIPTION:
XS GIS Cut Line= 3
      2224886.56     13854329.48        2224725.       13853225.
      2224772.69     13852809.77
#Sta/Elev= 30
  3878.9  825.31  3883.7  825.31  3893.5   823.3  3944.1  816.44    4005  811.99
  4085.6  809.23    4286  804.44  4378.6  801.86  4405.9  801.46  4410.9  802.09
  4685.6   796.6  4755.5  794.86  4803.1  792.36  4863.8  792.16  4890.3  789.46
  4924.4  788.89  4946.3  786.21  4960.2  784.13  4965.2  785.57  4997.7  783.65
  4999.1  782.68  4999.6  782.18  5011.3  782.68  5025.3  801.33  5144.3  808.04
  5196.5     811  5266.9  817.35  5303.8  821.87  5337.4  827.85  5413.1   834.4
#Mann= 8 ,-1 , 0
  3878.9     .12       0    4005    .035       0    4286     .12       0
  4946.3     .07       0  4999.1     .05       0  5011.3     .07       0
  5144.3     .12       0  5303.8     .07       0
Bank Sta=4999.1,5011.3
XS Rating Curve= 0 ,0
Exp/Cntr=0.3,0.1

Type RM Length L Ch R = 1 ,6426    ,482,482,482
BEGIN DESCRIPTION:
Mountain Creek 14.0
END DESCRIPTION:
XS GIS Cut Line= 3
      2225074.06     13854352.96        2225025.       13853475.
      2225124.25     13852869.91
#Sta/Elev= 30
  4125.9  832.29  4163.9  828.58  4264.1  814.57  4317.5  809.91  4514.5  803.19
  4804.9  797.52  4889.7  793.72  4912.8  791.29  4935.1  791.26  4955.2  789.49
  4975.2  783.75  4989.1  778.22  4989.6  777.72  5001.3  778.22  5001.4  778.39
  5002.7  780.58  5015.4  782.16  5055.9  784.36  5086.3  784.29  5106.6  787.31
  5147.1  788.92    5161  790.44  5167.9  792.89  5217.2  805.97  5278.5  812.58
    5289  815.36  5390.3  831.04  5491.6  849.36  5582.8  871.93  5618.4  883.77
#Mann= 7 ,-1 , 0
  4125.9     .12       0  4317.5    .035       0  4889.7     .12       0
  4989.1     .05       0  5001.3     .12       0  5001.4     .07       0
  5167.9     .12       0
Bank Sta=4989.1,5001.3
XS Rating Curve= 0 ,0
Exp/Cntr=0.3,0.1

Type RM Length L Ch R = 1 ,5944    ,442,442,442
BEGIN DESCRIPTION:
Mountain Creek 13.0
END DESCRIPTION:
XS GIS Cut Line= 3
      2225415.56     13854312.72        2225475.       13853575.
      2225348.59     13853003.63
#Sta/Elev= 30
  4264.3  825.58  4302.1  820.97  4362.3  816.44  4498.1  808.58  4791.7  797.09
  4934.2   792.4  4945.7   789.6  4954.2  779.52  4964.3  776.23  4988.2   775.9
  4988.7   775.4  5000.5   775.9  5001.9  779.09  5035.1  783.22  5086.3  785.38
  5193.9  787.08    5240  789.72  5257.2  795.13  5262.3  794.79  5300.8   801.7
  5398.3  813.44  5441.9  824.19  5447.1  824.51  5485.6  835.06  5490.7  835.19
    5496  837.74  5534.3  847.58  5539.4  847.75  5586.3  864.25  5589.6  864.25
#Mann= 6 ,-1 , 0
  4264.3     .12       0  4498.1    .035       0  4791.7     .12       0
  4988.2     .05       0  5000.5     .12       0  5193.9     .12       0
Bank Sta=4988.2,5000.5
XS Rating Curve= 0 ,0
Exp/Cntr=0.3,0.1

Type RM Length L Ch R = 1 ,5502    ,454,454,454
BEGIN DESCRIPTION:
Mountain Creek 12.0
END DESCRIPTION:
XS GIS Cut Line= 3
      2225770.45      13854138.7        2225825.       13853475.
      2225624.98     13853074.96
#Sta/Elev= 30
  4329.8  813.11  4363.6  811.77  4383.7  809.69  4447.7  805.88    4464  802.37
    4474  797.76    4484  798.16  4494.1  802.27  4504.1  803.03  4584.4  800.41
  4672.5  795.91    4771  791.33  4875.3  787.08  4937.6  780.83  4965.6  775.67
  5003.6  773.32  5004.1  772.82  5015.9  773.32  5026.5  777.25  5069.3  782.89
  5115.9  783.31  5143.9  785.47  5160.6  789.99    5183  793.99  5255.7  801.09
  5300.4  807.31  5412.2   827.6  5434.6   832.4  5440.2  834.89    5443  834.89
#Mann= 6 ,-1 , 0
  4329.8     .12       0  4672.5    .035       0    4771     .07       0
  5003.6     .05       0  5015.9     .07       0  5069.3     .12       0
Bank Sta=5003.6,5015.9
XS Rating Curve= 0 ,0
Exp/Cntr=0.3,0.1

Type RM Length L Ch R = 1 ,5048    ,444,444,444
BEGIN DESCRIPTION:
Mountain Creek 11.0
END DESCRIPTION:
XS GIS Cut Line= 3
      2226024.97     13853725.03        2226225.       13853525.
        2226275.     13853374.99
#Sta/Elev= 30
  4721.3  787.47  4724.9  787.47    4748   786.1  4756.7  785.29    4792  783.13
  4834.5  781.94  4848.6  781.82  4862.8  781.21  4876.9  779.98  4919.3  777.74
  4933.5  775.53  4961.8  772.61  4975.9  772.63  4994.4  769.51  4994.9  769.01
  5006.3  769.01  5006.8  769.51  5014.7   769.9  5025.3  772.26  5035.8   774.1
  5046.3  776.33  5062.4  781.87  5067.4  783.59    5078  785.42  5088.5  785.75
  5109.6  785.75  5120.1  786.97  5130.7  787.21  5141.2  786.08  5162.3   786.1
#Mann= 5 ,-1 , 0
  4721.3     .07       0    4748    .035       0  4994.4    .035       0
  5006.8    .035       0  5062.4     .12       0
Bank Sta=4994.4,5006.8
XS Rating Curve= 0 ,0
Exp/Cntr=0.3,0.1

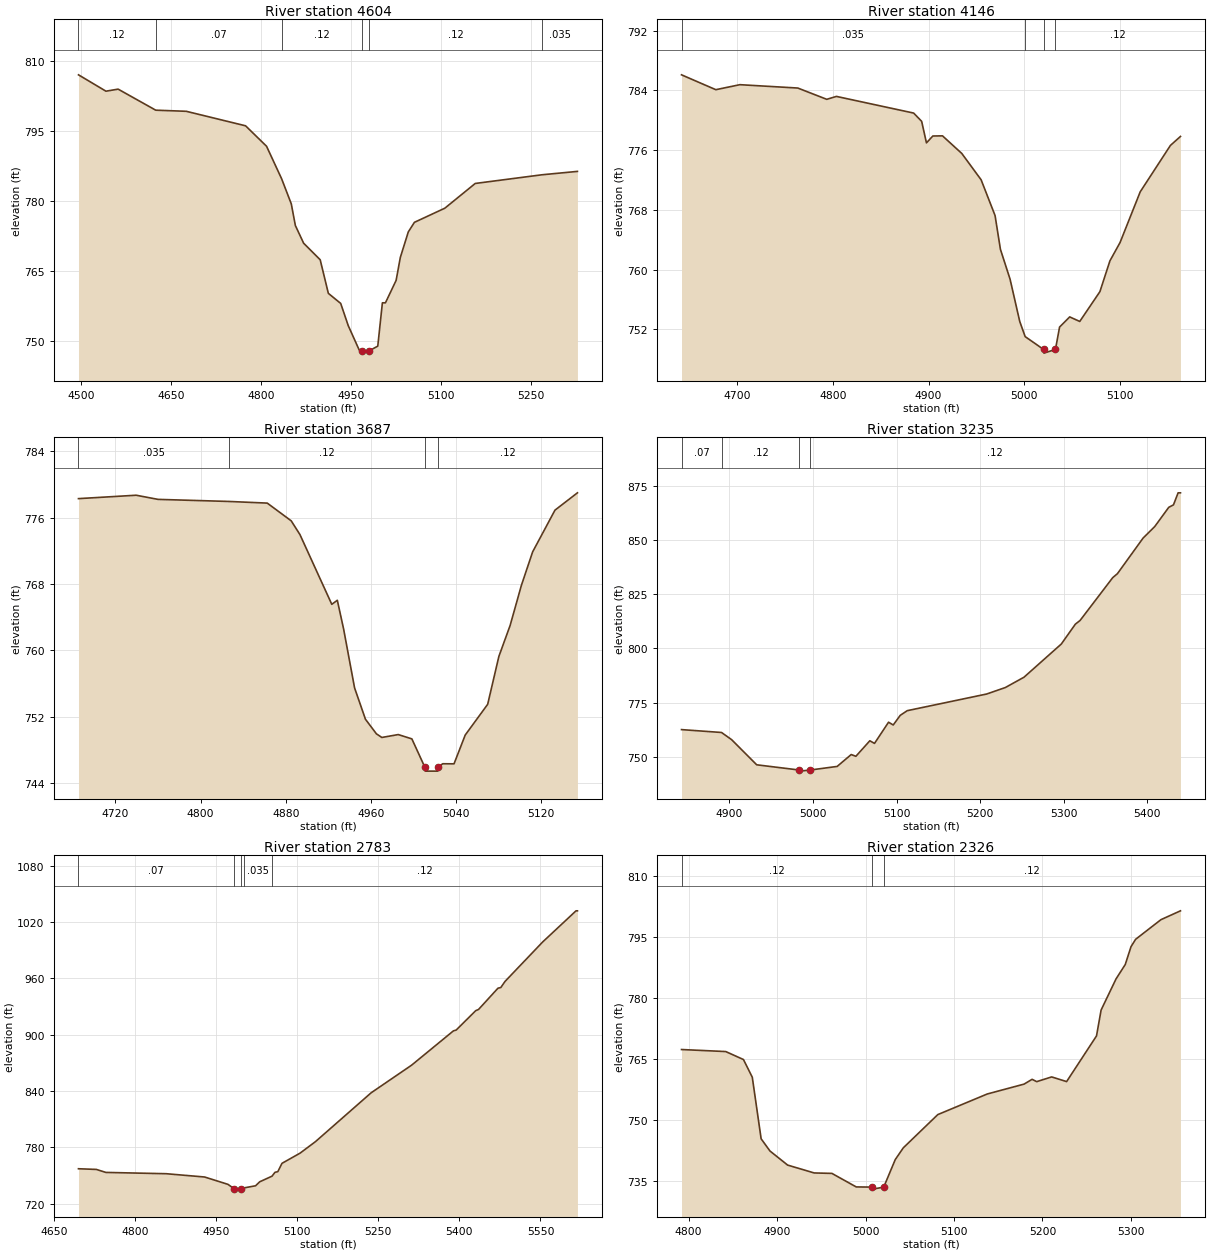
Type RM Length L Ch R = 1 ,4604    ,458,458,458
BEGIN DESCRIPTION:
Mountain Creek 10.0
END DESCRIPTION:
XS GIS Cut Line= 3
      2226353.01     13854319.47        2226475.       13853825.
      2226530.24     13853507.16
#Sta/Elev= 30
  4495.3  806.98  4541.1  803.48  4561.4  803.92  4624.1  799.42    4675  799.18
  4773.9  796.08  4808.9   791.7    4834  784.75  4850.1  779.39  4856.9  774.76
  4870.7  770.97  4898.3  767.43  4911.9  760.25  4932.5   758.1    4945  753.37
  4963.4  748.12  4967.5  747.97    4968  747.47    4980  747.97  4994.3  748.96
    5002  758.23  5007.1  758.23  5024.9  763.03  5031.9  767.93  5045.2  773.39
  5055.4  775.44  5106.1  778.46  5156.8  783.75  5268.3  785.61  5327.2  786.33
#Mann= 6 ,-1 , 0
  4495.3     .12       0  4624.1     .07       0    4834     .12       0
  4967.5     .05       0    4980     .12       0  5268.3    .035       0
Bank Sta=4967.5,4980
XS Rating Curve= 0 ,0
Exp/Cntr=0.3,0.1

Type RM Length L Ch R = 1 ,4146    ,459,459,459
BEGIN DESCRIPTION:
Mountain Creek 9.0
END DESCRIPTION:
XS GIS Cut Line= 3
      2226825.09     13854185.56        2226875.       13853825.
        2226825.     13853675.01
#Sta/Elev= 30
  4641.5  786.07  4677.4  784.08  4702.6  784.75  4763.2   784.3  4793.5  782.79
  4803.6  783.18  4884.4  780.95  4892.8  779.84  4897.8  776.96  4904.5  777.88
  4914.6   777.9  4934.8  775.54    4955  772.02  4969.6  767.23  4975.2  762.71
  4985.3  758.71  4995.4  753.06  5001.1  751.02  5020.3  749.31  5020.8  748.81
  5032.8  749.31  5037.1   752.3  5047.7  753.66  5058.2  753.05  5079.3  757.04
  5089.8  761.17  5100.4  763.62  5121.5  770.41  5153.1  776.62  5163.6  777.82
#Mann= 4 ,-1 , 0
  4641.5    .035       0  5001.1     .12       0  5020.3    .035       0
  5032.8     .12       0
Bank Sta=5020.3,5032.8
XS Rating Curve= 0 ,0
Exp/Cntr=0.3,0.1

Type RM Length L Ch R = 1 ,3687    ,452,452,452
BEGIN DESCRIPTION:
Mountain Creek 8.0
END DESCRIPTION:
XS GIS Cut Line= 3
      2227206.77     13853977.92        2227275.       13853675.
      2227225.01     13853525.02
#Sta/Elev= 30
  4685.4   778.3  4739.6  778.71  4760.1  778.21  4826.5  777.96  4862.7  777.76
  4885.2  775.62  4893.4  773.96  4923.3  765.55  4928.5  766.04  4934.4  762.57
  4944.7  755.47  4954.9  751.69  4965.2  749.93  4970.3  749.49  4985.7  749.84
  4998.5  749.32  5010.6  745.93  5011.1  745.43  5022.8  745.43  5023.3  745.93
  5027.5  746.32  5038.1  746.31  5048.6  749.78  5069.7  753.49  5080.2  759.26
  5090.8  763.01  5101.3  767.81  5111.9  771.87  5132.9  776.91    5154     779
#Mann= 4 ,-1 , 0
  4685.4    .035       0  4826.5     .12       0  5010.6     .05       0
  5023.3     .12       0
Bank Sta=5010.6,5023.3
XS Rating Curve= 0 ,0
Exp/Cntr=0.3,0.1

Type RM Length L Ch R = 1 ,3235    ,452,452,452
BEGIN DESCRIPTION:
Mountain Creek 7.0
END DESCRIPTION:
XS GIS Cut Line= 3
        2227675.     13853674.97        2227675.       13853525.
      2227875.01     13853124.99
#Sta/Elev= 30
  4842.6  762.52  4890.5  761.19  4902.6  757.87  4932.6  746.26  4983.7  743.84
  4984.2  743.34  4996.4  743.84  5028.9  745.51  5045.7     751  5051.3  750.19
    5068  757.36  5073.6  756.15  5090.4  765.94    5096  764.66  5104.4  769.11
  5112.8  771.27  5207.8  778.96  5230.2  781.96  5252.5  786.72  5297.2  802.07
    5314  811.24  5319.6  812.92  5358.7  832.72  5364.3  834.54  5395.1  851.02
    5409  856.32  5425.8  865.22  5431.4  866.34    5437  871.91  5439.8  871.91
#Mann= 4 ,-1 , 0
  4842.6     .07       0  4890.5     .12       0  4983.7     .05       0
  4996.4     .12       0
Bank Sta=4983.7,4996.4
XS Rating Curve= 0 ,0
Exp/Cntr=0.3,0.1

Type RM Length L Ch R = 1 ,2783    ,457,457,457
BEGIN DESCRIPTION:
Mountain Creek 6.0
END DESCRIPTION:
XS GIS Cut Line= 3
        2228125.     13853725.02        2228075.       13853425.
      2227925.01     13852825.03
#Sta/Elev= 30
  4695.8  757.32  4728.8  756.61  4746.5  753.42    4858  752.04    4929  748.54
  4972.1  740.73  4983.4  736.13  4983.9  735.63  4996.2  736.13    5001  736.86
  5023.2  739.19  5030.9  743.44  5053.6   749.4  5059.2  753.55  5064.4  754.23
  5072.1   763.1  5105.6  773.97    5134   786.2    5237  838.23  5311.8  867.63
  5389.1  904.14  5394.2  905.02  5430.3  925.64  5435.5  926.93  5471.5  949.59
  5476.7  950.28  5484.4  956.72    5554  998.73  5615.8 1031.96  5618.4 1031.96
#Mann= 5 ,-1 , 0
  4695.8     .07       0  4983.4     .05       0  4996.2     .07       0
    5001    .035       0  5053.6     .12       0
Bank Sta=4983.4,4996.2
XS Rating Curve= 0 ,0
Exp/Cntr=0.3,0.1

Type RM Length L Ch R = 1 ,2326    ,473,473,473
BEGIN DESCRIPTION:
Mountain Creek 5.0
END DESCRIPTION:
XS GIS Cut Line= 3
        2228425.     13853775.04        2228425.       13853575.
      2228524.99     13853225.05
#Sta/Elev= 30
    4792  767.24    4842  766.74    4862  764.78    4872  760.42    4882  745.27
    4892  742.27    4912   738.8    4942  736.87    4962  736.76  4989.5  733.43
  5007.7  733.39  5008.2  732.89  5020.6  733.39  5033.6  740.16  5042.7  743.05
  5081.7  751.23  5137.6   756.3  5179.2  758.73  5188.3  759.91  5193.5  759.34
  5210.4   760.5  5227.3  759.35  5261.1  770.59  5266.3  776.96  5283.2  784.63
  5293.6  788.16  5300.1  792.55  5305.3  794.36  5333.9  799.19    5356  801.37
#Mann= 3 ,-1 , 0
    4792     .12       0  5007.7     .05       0  5020.6     .12       0
Bank Sta=5007.7,5020.6
XS Rating Curve= 0 ,0
Exp/Cntr=0.3,0.1

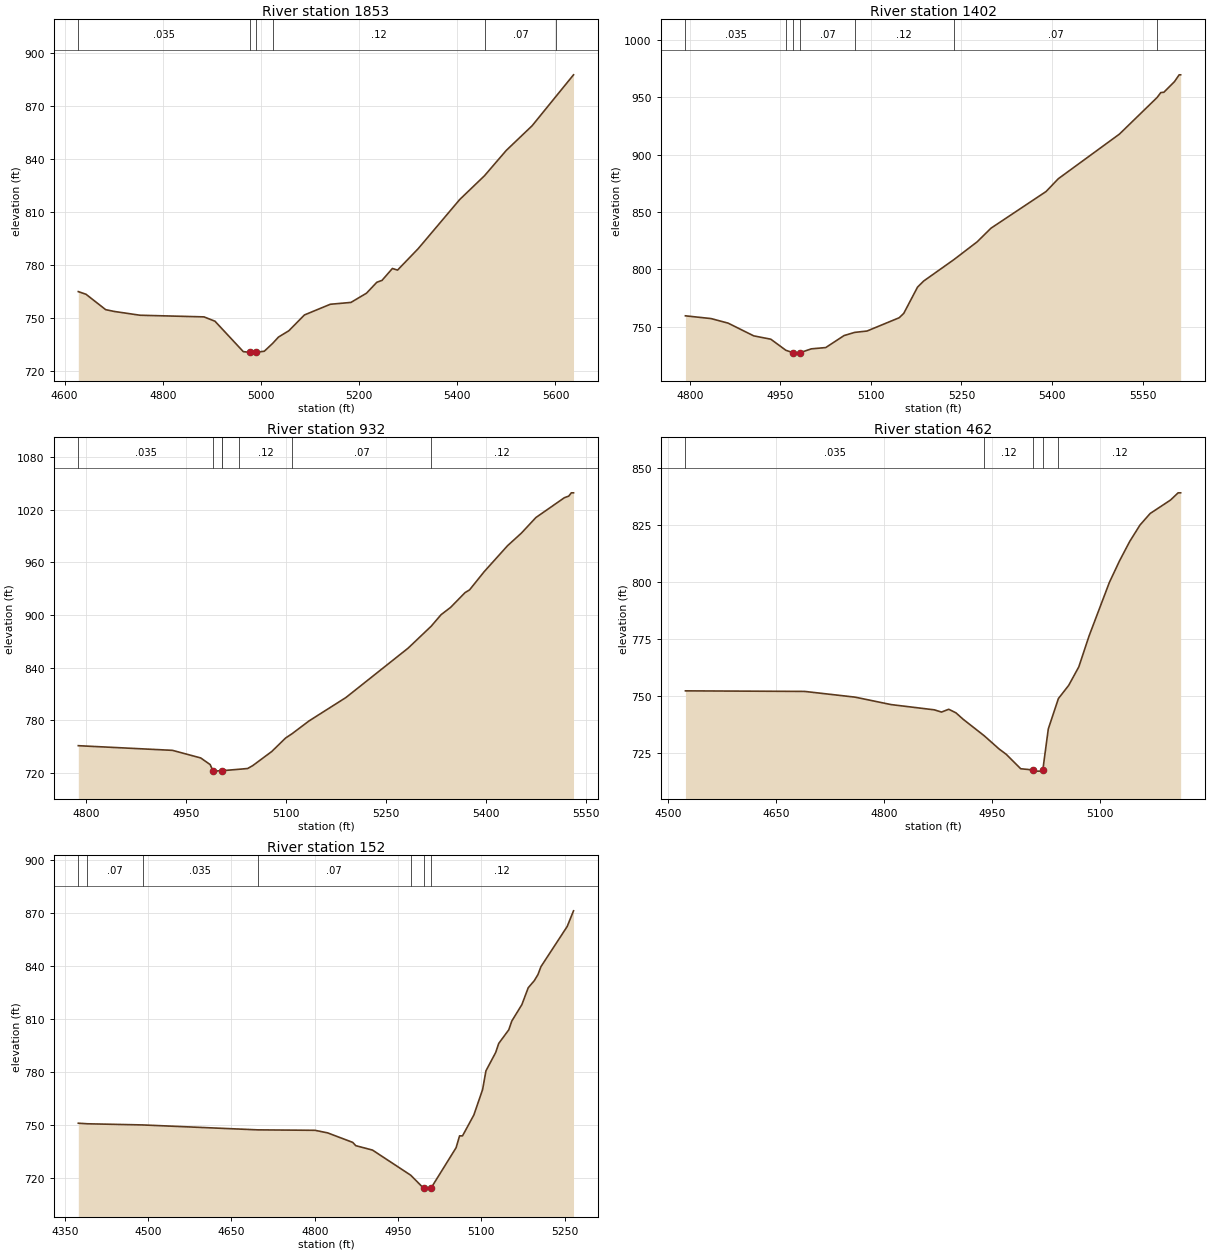
Type RM Length L Ch R = 1 ,1853    ,451,451,451
BEGIN DESCRIPTION:
Mountain Creek 4.0
END DESCRIPTION:
XS GIS Cut Line= 3
      2228793.75     13853850.68        2228775.       13853475.
        2228975.       13852875.
#Sta/Elev= 30
  4628.1  764.78  4643.8  763.27  4683.8  754.56  4701.1  753.54  4753.9  751.38
  4884.1  750.45  4906.5  747.98  4964.2  730.73  4977.7   730.4  4978.2   729.9
  4990.7   730.4  5006.9  730.97  5023.7  735.36  5035.9  739.02    5057   742.6
  5088.6  751.54  5141.3   757.6  5183.4  758.65  5215.1  763.89  5236.1  770.07
  5246.7  771.16  5267.8  777.89  5278.3  776.98  5320.5  789.17  5404.8  816.95
  5455.4  830.48  5499.7  844.82  5552.4  858.82  5601.9  875.79  5636.7  887.69
#Mann= 6 ,-1 , 0
  4628.1    .035       0  4977.7    .035       0  4990.7    .035       0
  5023.7     .12       0  5455.4     .07       0  5601.9     .12       0
Bank Sta=4977.7,4990.7
XS Rating Curve= 0 ,0
Exp/Cntr=0.3,0.1

Type RM Length L Ch R = 1 ,1402    ,470,470,470
BEGIN DESCRIPTION:
Mountain Creek 3.0
END DESCRIPTION:
XS GIS Cut Line= 3
        2229275.       13853425.        2229125.       13853275.
        2229025.     13852675.01
#Sta/Elev= 30
  4792.7  759.49  4835.1  757.09  4863.4  753.11  4905.8  742.01  4934.1   739.1
    4959  729.47  4970.1  727.45  4970.6  726.95  4983.1  727.45  5001.3  730.68
  5025.1   731.8  5055.5  742.27  5073.1  745.05  5093.5  746.22  5146.8  757.81
  5154.4  761.64  5177.2  784.53  5187.3  789.81  5237.3  808.45    5276  824.04
  5298.8  835.89  5390.1  867.89  5410.4  879.06  5511.7  918.01  5574.3  950.04
  5580.2  954.24  5585.2  954.46    5603  963.84  5610.6   969.7  5613.1   969.7
#Mann= 7 ,-1 , 0
  4792.7    .035       0    4959     .07       0  4970.1     .05       0
  4983.1     .07       0  5073.1     .12       0  5237.3     .07       0
  5574.3     .12       0
Bank Sta=4970.1,4983.1
XS Rating Curve= 0 ,0
Exp/Cntr=0.3,0.1

Type RM Length L Ch R = 1 ,932     ,470,470,470
BEGIN DESCRIPTION:
Mountain Creek 2.0
END DESCRIPTION:
XS GIS Cut Line= 3
      2229574.97     13853074.97        2229425.       13852925.
        2229075.       13852525.
#Sta/Elev= 30
  4787.9  751.24  4929.3  745.93  4971.7  737.28  4985.9  729.72    4990  722.76
  4990.5  722.26    5003  722.76  5004.3  722.77  5028.5  724.33  5042.2  725.26
  5049.8  728.52  5078.3  744.56  5099.2  759.99  5109.3   765.1  5134.3  779.41
  5189.8  806.13  5283.3  862.46  5317.8  887.36  5332.7  900.52  5346.9  908.77
  5368.7  925.67  5375.4  928.74  5397.2  949.33  5432.3  978.95  5453.2  993.38
    5475 1011.14  5517.7  1033.7  5524.4  1035.6  5528.2  1039.3  5531.5  1039.3
#Mann= 7 ,-1 , 0
  4787.9    .035       0    4990    .035       0    5003    .035       0
  5004.3     .07       0  5028.5     .12       0  5109.3     .07       0
  5317.8     .12       0
Bank Sta=4990,5003
XS Rating Curve= 0 ,0
Exp/Cntr=0.3,0.1

Type RM Length L Ch R = 1 ,462     ,310,310,310
BEGIN DESCRIPTION:
Mountain Creek 1.0
END DESCRIPTION:
XS GIS Cut Line= 3
      2229721.16     13853050.58        2229725.       13852575.
      2229575.02     13852425.02
#Sta/Elev= 30
  4524.2  752.22  4689.8  751.97  4759.8  749.46  4809.8   746.2  4869.8   743.9
  4879.8  742.92  4889.8  744.15  4899.8   742.6  4909.8  739.78  4939.1  732.54
  4959.8  726.73  4969.8  724.37  4989.8  718.07  5007.4  717.53  5007.9  717.03
    5020  717.03  5020.5  717.53  5028.1  735.52  5042.1  748.83  5056.4  754.62
  5070.5  762.76  5084.6  776.19  5112.9  799.74  5127.1  809.27  5141.2  817.73
  5155.4  824.89  5169.5  829.96  5197.8  835.86  5208.4  839.03  5211.9  839.03
#Mann= 5 ,-1 , 0
  4524.2    .035       0  4939.1     .12       0  5007.4     .05       0
  5020.5     .12       0  5042.1     .12       0
Bank Sta=5007.4,5020.5
XS Rating Curve= 0 ,0
Exp/Cntr=0.3,0.1

Type RM Length L Ch R = 1 ,152     ,0,0,0
BEGIN DESCRIPTION:
B19670
END DESCRIPTION:
XS GIS Cut Line= 4
      2229764.67     13852993.65      2229989.01     13852528.23
      2229975.62     13852357.48      2229895.27     13852170.01
#Sta/Elev= 30
  4374.2  751.16  4390.5  750.84  4490.4  750.18  4697.2   747.4  4800.6  747.14
  4823.2  745.69  4868.4  740.31    4874  738.44  4904.1  735.94  4972.8  721.74
  4996.2  714.33  4996.7  713.83  5009.3  714.33  5054.6  737.28  5060.9     744
  5066.2     744  5086.6  755.82  5102.3  770.16  5108.4  780.83  5125.9  791.21
  5131.4  796.34  5149.5  804.06  5154.9  809.01  5173.1  818.34  5184.5  827.87
  5195.4  831.87  5202.1  835.37  5207.5  839.86  5254.7  862.58  5266.1  871.45
#Mann= 7 ,-1 , 0
  4374.2    .035       0  4390.5     .07       0  4490.4    .035       0
  4697.2     .07       0  4972.8     .12       0  4996.2     .05       0
  5009.3     .12       0
Bank Sta=4996.2,5009.3
XS Rating Curve= 0 ,0
Exp/Cntr=0.3,0.1

Chan Stop Cuts=-1
Use User Specified Reach Order=0
Composite Channel Slope=5