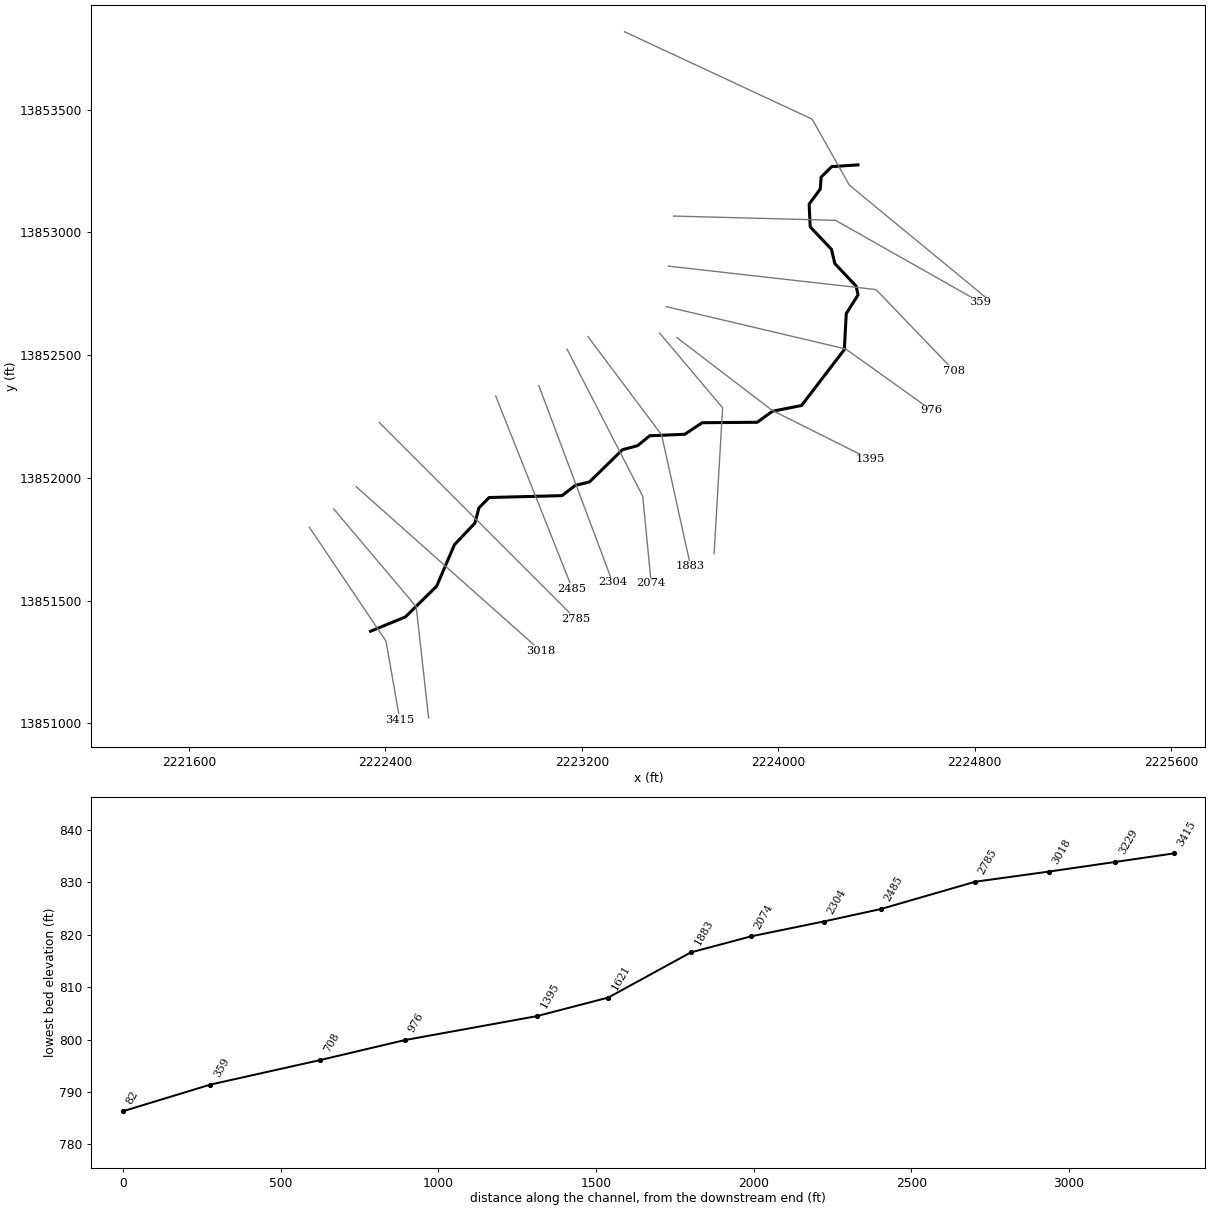
--- Mountain Tributary 2.prj (project) ---

Proj Title=Mountain Tributary 2 Base Level Engineering
Current Plan=p01
Default Exp/Contr=0.3,0.1
English Units
Geom File=g01
Flow File=f01
Plan File=p01
BEGIN DESCRIPTION:
Mountain Tributary 2
END DESCRIPTION:

--- Mountain Tributary 2.p01 (plan) ---

Plan Title=Multiple Run
Short Identifier=Multiple
Geom File=g01
Flow File=f01
Subcritical Flow
K Sum by GR= 0
Std Step Tol= 0.01
Critical Tol= 0.01
Num of Std Step Trials= 20
Max Error Tol= 0.3
Flow Tol Ratio= 0.001
Split Flow NTrial= 30
Split Flow Tol= 0.02
Split Flow Ratio= 0.02
Log Output Level= 0
Friction Slope Method= 1
Unsteady Friction Slope Method= 2
Unsteady Bridges Friction Slope Method= 1
Parabolic Critical Depth
Global Vel Dist=  1 , 1 , 1
Global Log Level= 0
CheckData=True
Encroach Param= -1, 0, 0, 0
BEGIN DESCRIPTION:
Multiple Run
END DESCRIPTION:

--- Mountain Tributary 2.f01 (steady flow) ---

Flow Title=Multiple
Number of Profiles=7
Profile Names=10-year,25-year,50-year,1pct_min,100-year,1pct_plu,500-year
River Rch & RM= Mountain Tributa,Reach-1,3415
    1376    2350    3285    2223    4435    8849    7999
River Rch & RM= Mountain Tributa,Reach-1,82
    1754    3039    4287    2926    5838   11649   10714
Boundary for River Rch & Prof#=Mountain Tributa,Reach-1,1
Up Type=0
Dn Type=3
Dn Slope=0.005
Boundary for River Rch & Prof#=Mountain Tributa,Reach-1,2
Up Type=0
Dn Type=3
Dn Slope=0.005
Boundary for River Rch & Prof#=Mountain Tributa,Reach-1,3
Up Type=0
Dn Type=3
Dn Slope=0.005
Boundary for River Rch & Prof#=Mountain Tributa,Reach-1,4
Up Type=0
Dn Type=3
Dn Slope=0.005
Boundary for River Rch & Prof#=Mountain Tributa,Reach-1,5
Up Type=0
Dn Type=3
Dn Slope=0.005
Boundary for River Rch & Prof#=Mountain Tributa,Reach-1,6
Up Type=0
Dn Type=3
Dn Slope=0.005
Boundary for River Rch & Prof#=Mountain Tributa,Reach-1,7
Up Type=0
Dn Type=3
Dn Slope=0.005

--- Mountain Tributary 2.g01 (geometry) ---

Geom Title=Existing Conditions

River Reach=Mountain Tributa,Reach-1
Reach XY= 30
      2222339.46     13851375.00      2222481.07     13851433.12
      2222608.36     13851558.32      2222680.85     13851727.29
      2222764.19     13851815.35      2222780.74     13851877.58
      2222822.30     13851919.64      2223119.48     13851927.35
      2223172.83     13851968.86      2223231.06     13851983.14
      2223365.32     13852114.24      2223427.17     13852131.14
      2223476.56     13852171.24      2223619.47     13852177.39
      2223690.22     13852224.48      2223914.50     13852226.22
      2223976.60     13852271.14      2224095.20     13852294.61
      2224269.52     13852522.56      2224277.30     13852669.07
      2224325.36     13852745.21      2224317.50     13852781.05
      2224230.87     13852872.72      2224216.82     13852931.04
      2224130.41     13853022.58      2224126.15     13853115.33
      2224171.35     13853176.51      2224175.00     13853225.00
      2224217.90     13853267.76      2224325.00     13853275.00

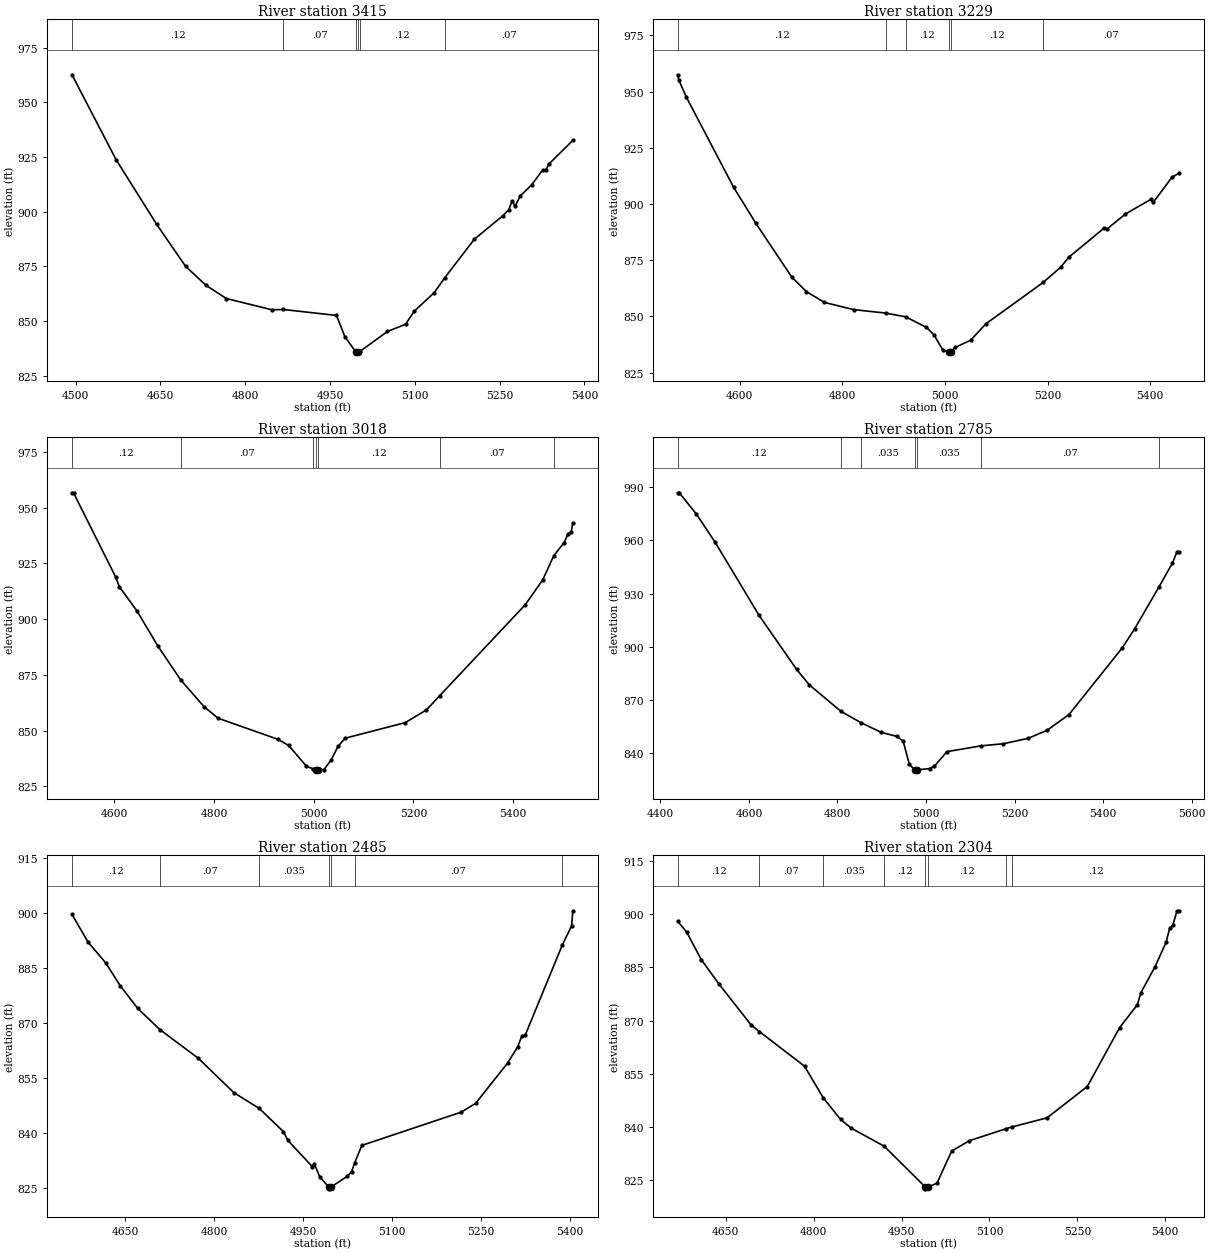
Type RM Length L Ch R = 1,3415,186,186,186
BEGIN DESCRIPTION:
B19687
END DESCRIPTION:
XS GIS Cut Line= 3
      2222089.49     13851799.08      2222402.01     13851334.64
      2222458.43     13851013.46
#Sta/Elev= 30
  4493.6  962.54  4571.5  923.77  4643.5  894.12  4694.5  875.00  4730.5  866.34
  4766.5  860.29  4847.4  855.14  4867.2  855.28  4961.4  852.56  4976.4  842.76
  4995.4  835.97  4995.6  835.47  4999.4  835.97  5003.2  836.19  5051.6  845.24
  5083.5  848.51  5099.2  854.56  5134.3  862.97  5152.8  869.74  5205.3  887.39
  5256.1  898.22  5266.3  900.94  5272.2  904.93  5277.2  902.44  5286.6  907.21
  5306.9  912.31  5326.4  919.14  5331.5  918.83  5337.3  921.82  5379.5  932.53
#Mann=6,-1,0
  4493.6    0.12       0  4867.2    0.07       0  4995.4    0.05       0
  4999.4    0.07       0  5003.2    0.12       0  5152.8    0.07       0
Bank Sta=4995.4,4999.4
Exp/Cntr=0.3,0.1

Type RM Length L Ch R = 1,3229,211,211,211
BEGIN DESCRIPTION:
Mountain Tributary 2 7.0
END DESCRIPTION:
XS GIS Cut Line= 3
      2222189.37     13851872.80      2222525.00     13851475.00
      2222575.62     13851022.09
#Sta/Elev= 30
  4479.2  957.45  4481.5  955.04  4495.8  947.61  4588.1  907.47  4631.0  891.60
  4701.3  867.58  4729.9  861.08  4765.0  856.27  4822.2  853.05  4884.6  851.51
  4923.6  849.85  4963.9  845.17  4978.2  841.99  4996.4  834.93  5007.7  834.34
  5008.0  833.84  5011.7  834.34  5019.8  836.24  5050.0  839.42  5080.2  846.80
  5191.6  865.15  5225.4  871.84  5241.2  876.27  5310.7  889.38  5315.7  888.83
  5351.9  895.56  5401.0  902.01  5406.0  900.70  5442.4  911.83  5455.4  913.59
#Mann=6,-1,0
  4479.2    0.12       0  4884.6    0.07       0  4923.6    0.12       0
  5007.7    0.05       0  5011.7    0.12       0  5191.6    0.07       0
Bank Sta=5007.7,5011.7
Exp/Cntr=0.3,0.1

Type RM Length L Ch R = 1,3018,233,233,233
BEGIN DESCRIPTION:
B19686
END DESCRIPTION:
XS GIS Cut Line= 2
      2222280.45     13851964.00      2223030.67     13851296.18
#Sta/Elev= 30
  4515.5  956.63  4518.5  956.63  4602.7  919.03  4610.2  914.60  4645.3  903.82
  4687.9  887.87  4733.2  872.83  4779.9  860.83  4808.4  855.59  4928.8  846.10
  4950.0  843.37  4985.6  834.07  4999.7  832.81  5004.5  832.50  5004.7  832.00
  5008.6  832.50  5020.7  832.57  5035.0  836.80  5049.2  843.07  5063.4  846.63
  5183.8  853.61  5226.4  859.33  5252.7  865.64  5424.6  906.48  5459.7  917.68
  5481.6  928.39  5502.4  934.29  5509.9  938.00  5516.6  939.06  5519.9  943.14
#Mann=7,-1,0
  4515.5    0.12       0  4733.2    0.07       0  4999.7    0.12       0
  5004.5    0.05       0  5008.6    0.12       0  5252.7    0.07       0
  5481.6    0.12       0
Bank Sta=5004.5,5008.6
Exp/Cntr=0.3,0.1

Type RM Length L Ch R = 1,2785,300,300,300
BEGIN DESCRIPTION:
Mountain Tributary 2 6.0
END DESCRIPTION:
XS GIS Cut Line= 3
      2222375.03     13852224.97      2222775.00     13851825.00
      2223174.98     13851425.02
#Sta/Elev= 30
  4439.2  986.89  4442.7  986.89  4481.6  974.79  4524.0  958.87  4623.0  917.72
  4707.9  887.23  4736.1  878.64  4808.0  863.59  4852.9  857.26  4898.8  851.78
  4934.1  849.49  4948.3  846.86  4962.4  833.79  4974.5  830.57  4974.8  830.07
  4978.6  830.57  5008.4  831.35  5019.0  832.69  5047.3  840.89  5124.1  844.16
  5174.5  845.34  5231.1  848.42  5273.5  852.95  5323.0  861.80  5443.2  899.38
  5471.5  910.24  5526.5  933.90  5556.4  947.10  5567.0  953.53  5570.5  953.53
#Mann=7,-1,0
  4439.2    0.12       0  4808.0    0.07       0  4852.9   0.035       0
  4974.5   0.035       0  4978.6   0.035       0  5124.1    0.07       0
  5526.5    0.12       0
Bank Sta=4974.5,4978.6
Exp/Cntr=0.3,0.1

Type RM Length L Ch R = 1,2485,181,181,181
BEGIN DESCRIPTION:
B19685
END DESCRIPTION:
XS GIS Cut Line= 2
      2222849.04     13852332.94      2223161.04     13851548.62
#Sta/Elev= 30
  4560.9  899.70  4588.1  892.13  4617.7  886.50  4642.0  880.30  4671.7  874.06
  4708.9  868.31  4773.9  860.46  4833.6  851.11  4876.5  846.79  4917.2  840.47
  4924.6  838.10  4965.8  830.93  4969.3  831.65  4978.4  828.16  4993.4  825.36
  4993.7  824.86  4997.5  825.36  5025.1  828.32  5032.2  829.57  5037.3  831.97
  5049.4  836.71  5216.7  845.78  5241.0  848.15  5294.9  859.15  5312.0  863.60
  5319.2  866.63  5324.6  866.74  5386.9  891.24  5402.9  896.62  5405.0  900.71
#Mann=7,-1,0
  4560.9    0.12       0  4708.9    0.07       0  4876.5   0.035       0
  4993.4   0.035       0  4997.5   0.035       0  5037.3    0.07       0
  5386.9    0.12       0
Bank Sta=4993.4,4997.5
Exp/Cntr=0.3,0.1

Type RM Length L Ch R = 1,2304,230,230,230
BEGIN DESCRIPTION:
Mountain Tributary 2 5.0
END DESCRIPTION:
XS GIS Cut Line= 3
      2223024.99     13852375.02      2223175.00     13851975.00
      2223324.99     13851575.02
#Sta/Elev= 30
  4568.2  898.00  4583.3  895.00  4608.3  887.20  4638.5  880.32  4693.7  868.69
  4707.4  866.90  4784.5  857.11  4816.5  848.18  4845.9  842.10  4864.6  839.58
  4920.4  834.53  4990.7  822.99  4990.9  822.49  4994.8  822.99  5010.5  824.08
  5035.5  833.15  5065.7  836.07  5128.2  839.45  5139.3  840.00  5198.3  842.53
  5266.9  851.37  5322.0  867.97  5352.3  874.46  5358.5  877.88  5382.6  885.24
  5401.3  892.05  5407.5  896.11  5412.8  896.83  5419.9  900.98  5422.6  900.98
#Mann=8,-1,0
  4568.2    0.12       0  4707.4    0.07       0  4816.5   0.035       0
  4920.4    0.12       0  4990.7    0.05       0  4994.8    0.12       0
  5128.2    0.07       0  5139.3    0.12       0
Bank Sta=4990.7,4994.8
Exp/Cntr=0.3,0.1

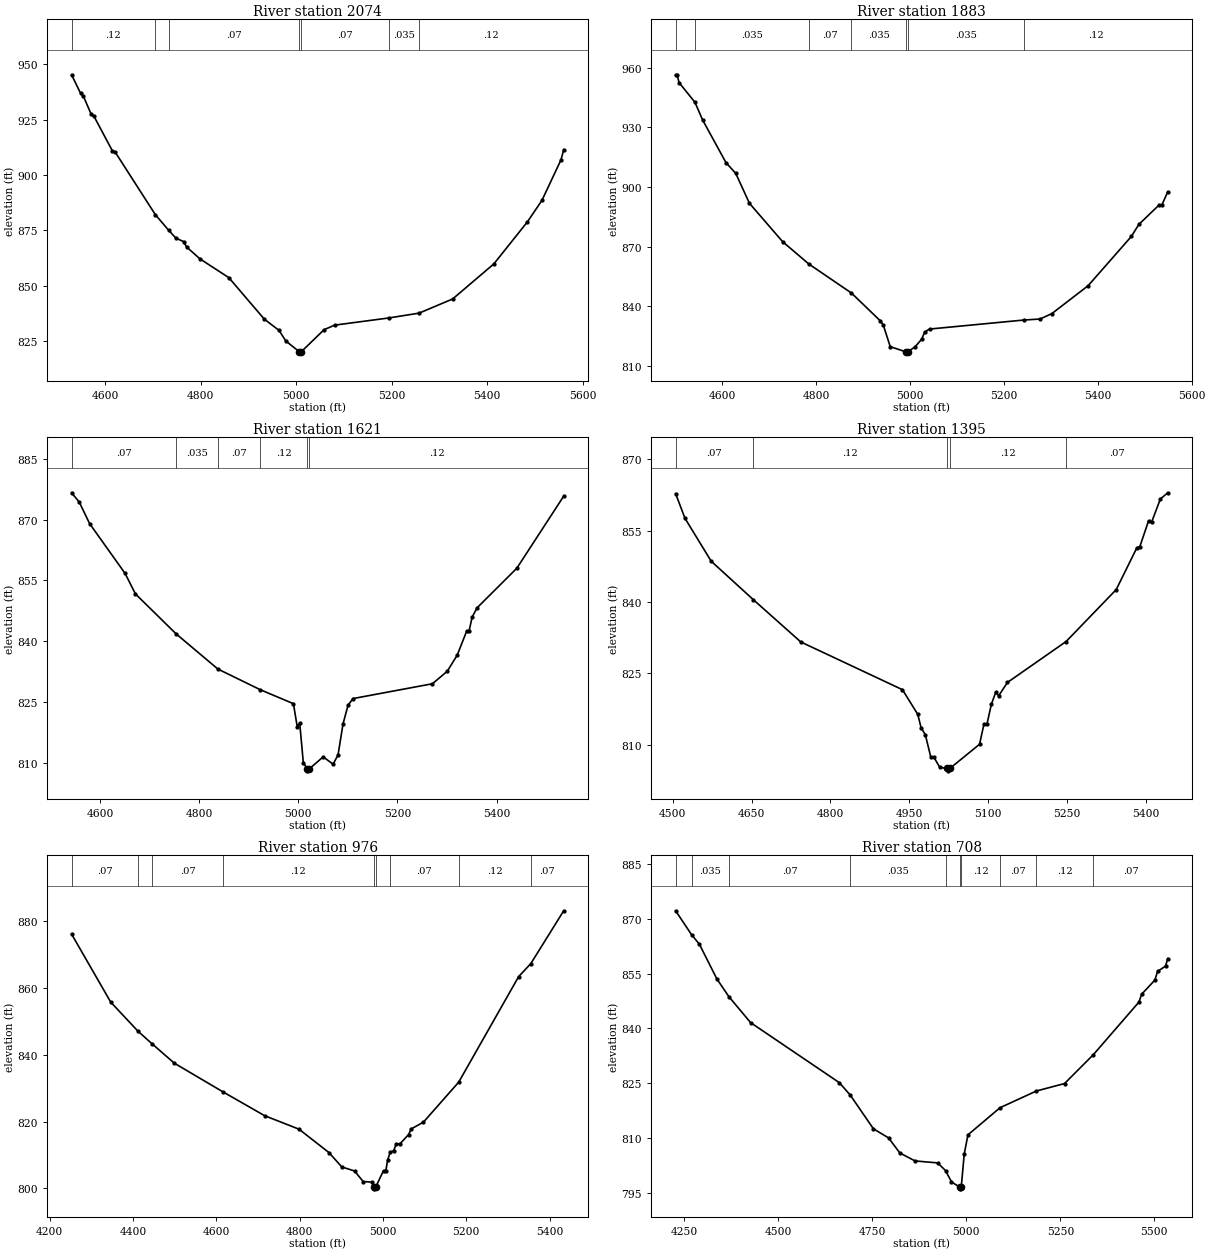
Type RM Length L Ch R = 1,2074,191,191,191
BEGIN DESCRIPTION:
B19684
END DESCRIPTION:
XS GIS Cut Line= 3
      2223139.85     13852523.89      2223448.02     13851924.92
      2223482.69     13851569.51
#Sta/Elev= 30
  4529.4  945.31  4548.3  936.92  4553.9  935.75  4570.5  927.45  4576.1  926.63
  4614.8  910.95  4620.5  910.44  4704.6  882.17  4732.9  875.00  4747.9  871.50
  4764.3  869.89  4770.1  867.54  4798.1  862.15  4858.8  853.63  4933.0  834.89
  4964.0  829.79  4978.0  825.04  5006.3  820.16  5006.6  819.66  5010.5  820.16
  5058.3  830.14  5080.5  832.18  5193.5  835.41  5257.2  837.60  5327.5  844.00
  5413.9  859.87  5484.2  878.88  5514.4  888.50  5554.6  906.96  5560.1  911.47
#Mann=7,-1,0
  4529.4    0.12       0  4704.6   0.035       0  4732.9    0.07       0
  5006.3    0.05       0  5010.5    0.07       0  5193.5   0.035       0
  5257.2    0.12       0
Bank Sta=5006.3,5010.5
Exp/Cntr=0.3,0.1

Type RM Length L Ch R = 1,1883,262,262,262
BEGIN DESCRIPTION:
Mountain Tributary 2 4.0
END DESCRIPTION:
XS GIS Cut Line= 3
      2223225.00     13852575.00      2223525.00     13852175.00
      2223643.15     13851639.27
#Sta/Elev= 30
  4500.4  956.46  4503.5  956.46  4507.7  952.55  4541.7  942.59  4557.7  933.84
  4607.7  912.28  4628.5  906.89  4657.7  891.82  4728.5  872.50  4784.4  861.26
  4875.1  846.68  4936.9  832.62  4943.1  830.44  4957.7  819.71  4991.0  817.10
  4991.3  816.60  4995.2  817.10  5010.6  819.62  5024.8  823.49  5031.1  827.10
  5041.4  828.56  5242.8  833.11  5276.9  833.60  5302.3  836.37  5379.3  850.35
  5471.5  875.15  5487.4  881.18  5531.1  891.08  5536.2  890.78  5549.0  897.57
#Mann=7,-1,0
  4500.4    0.12       0  4541.7   0.035       0  4784.4    0.07       0
  4875.1   0.035       0  4991.0   0.035       0  4995.2   0.035       0
  5242.8    0.12       0
Bank Sta=4991,4995.2
Exp/Cntr=0.3,0.1

Type RM Length L Ch R = 1,1621,226,226,226
BEGIN DESCRIPTION:
B19683
END DESCRIPTION:
XS GIS Cut Line= 3
      2223517.46     13852588.98      2223773.54     13852285.16
      2223738.81     13851690.51
#Sta/Elev= 30
  4542.5  876.64  4558.1  874.32  4578.9  869.02  4650.4  856.74  4671.3  851.68
  4753.4  841.81  4837.6  833.13  4922.7  828.05  4990.1  824.57  4997.8  818.90
  5002.8  819.79  5010.1  810.01  5018.0  808.49  5018.3  807.99  5022.2  808.49
  5050.2  811.44  5070.2  809.62  5080.2  811.94  5090.3  819.62  5100.3  824.17
  5110.3  825.83  5270.6  829.49  5300.6  832.58  5320.6  836.55  5339.6  842.45
  5344.6  842.52  5350.7  845.93  5360.7  848.24  5440.9  858.01  5535.5  875.81
#Mann=6,-1,0
  4542.5    0.07       0  4753.4   0.035       0  4837.6    0.07       0
  4922.7    0.12       0  5018.0    0.05       0  5022.2    0.12       0
Bank Sta=5018,5022.2
Exp/Cntr=0.3,0.1

Type RM Length L Ch R = 1,1395,419,419,419
BEGIN DESCRIPTION:
Mountain Tributary 2 3.0
END DESCRIPTION:
XS GIS Cut Line= 3
      2223586.92     13852571.61      2223975.00     13852275.00
      2224375.03     13852074.98
#Sta/Elev= 30
  4505.7  862.81  4523.5  857.61  4573.4  848.57  4653.2  840.51  4743.8  831.58
  4937.0  821.54  4966.1  816.35  4972.4  813.56  4980.6  812.03  4991.0  807.30
  4996.9  807.30  5008.1  805.17  5022.6  804.96  5022.9  804.46  5027.1  804.96
  5083.6  810.05  5092.0  814.30  5097.6  814.24  5106.0  818.44  5114.3  820.99
  5119.9  820.25  5136.7  823.07  5248.2  831.68  5343.5  842.61  5382.7  851.41
  5388.3  851.63  5405.0  857.09  5410.6  856.76  5427.4  861.67  5441.4  862.98
#Mann=5,-1,0
  4505.7    0.07       0  4653.2    0.12       0  5022.6    0.05       0
  5027.1    0.12       0  5248.2    0.07       0
Bank Sta=5022.6,5027.1
Exp/Cntr=0.3,0.1

Type RM Length L Ch R = 1,976,268,268,268
BEGIN DESCRIPTION:
Mountain Tributary 2 2.0
END DESCRIPTION:
XS GIS Cut Line= 3
      2223543.52     13852697.48      2224275.00     13852525.00
      2224625.04     13852274.97
#Sta/Elev= 30
  4252.4  876.07  4346.4  855.73  4411.8  847.04  4446.1  843.22  4499.1  837.47
  4615.8  828.90  4715.9  821.77  4798.5  817.73  4870.4  810.74  4901.2  806.45
  4932.0  805.22  4952.6  802.06  4973.1  801.91  4978.0  800.39  4978.3  799.89
  4982.5  800.39  5001.4  805.33  5007.0  805.33  5011.3  808.49  5017.3  810.78
  5026.1  811.35  5032.2  813.40  5040.8  813.32  5061.7  816.14  5067.8  817.80
  5097.3  819.84  5182.0  831.80  5325.9  863.36  5355.1  867.24  5434.1  883.05
#Mann=9,-1,0
  4252.4    0.07       0  4411.8   0.035       0  4446.1    0.07       0
  4615.8    0.12       0  4978.0    0.05       0  4982.5    0.12       0
  5017.3    0.07       0  5182.0    0.12       0  5355.1    0.07       0
Bank Sta=4978,4982.5
Exp/Cntr=0.3,0.1

Type RM Length L Ch R = 1,708,349,349,349
BEGIN DESCRIPTION:
B19688
END DESCRIPTION:
XS GIS Cut Line= 3
      2223552.16     13852862.42      2224398.54     13852766.93
      2224715.36     13852437.09
#Sta/Elev= 30
  4226.6  872.20  4269.0  865.66  4289.8  863.06  4336.3  853.55  4368.5  848.67
  4426.1  841.59  4662.2  825.15  4691.2  821.75  4752.8  812.52  4793.0  810.04
  4823.2  805.90  4863.5  803.73  4923.8  803.19  4944.8  801.07  4960.4  797.99
  4981.9  796.59  4982.3  796.09  4986.5  796.59  4994.3  805.61  5004.3  810.88
  5089.7  818.30  5186.3  822.87  5261.2  824.91  5337.6  832.79  5459.1  847.21
  5466.3  849.35  5501.5  853.23  5508.7  855.60  5529.8  857.05  5535.7  859.09
#Mann=10,-1,0
  4226.6    0.07       0  4269.0   0.035       0  4368.5    0.07       0
  4691.2   0.035       0  4944.8    0.12       0  4981.9    0.05       0
  4986.5    0.12       0  5089.7    0.07       0  5186.3    0.12       0
  5337.6    0.07       0
Bank Sta=4981.9,4986.5
Exp/Cntr=0.3,0.1

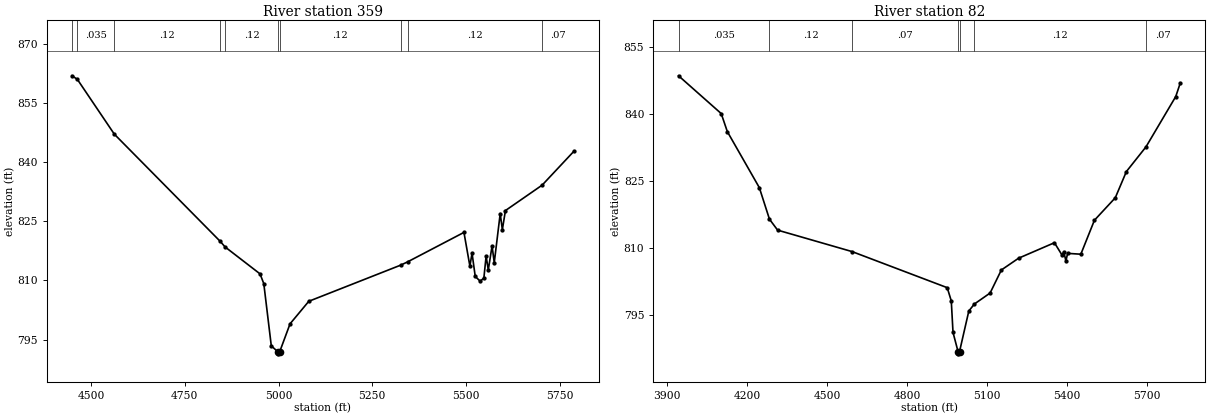
Type RM Length L Ch R = 1,359,277,277,277
BEGIN DESCRIPTION:
Mountain Tributary 2 1.0
END DESCRIPTION:
XS GIS Cut Line= 3
      2223573.92     13853066.41      2224233.61     13853049.05
      2224823.86     13852714.86
#Sta/Elev= 30
  4449.3  861.83  4463.4  860.92  4562.0  847.04  4844.7  819.86  4857.3  818.48
  4950.6  811.65  4960.6  809.18  4980.6  793.42  4998.3  791.90  4998.6  791.40
  5002.9  791.90  5030.6  799.00  5080.6  804.71  5325.5  813.86  5344.2  814.70
  5494.4  822.16  5510.2  813.63  5516.0  816.86  5524.5  811.01  5537.6  809.80
  5547.5  810.59  5553.5  816.17  5559.3  812.66  5569.4  818.74  5575.2  814.48
  5591.1  826.94  5596.8  822.86  5605.0  827.69  5702.9  834.13  5787.5  842.70
#Mann=10,-1,0
  4449.3    0.07       0  4463.4   0.035       0  4562.0    0.12       0
  4844.7   0.035       0  4857.3    0.12       0  4998.3    0.05       0
  5002.9    0.12       0  5325.5    0.07       0  5344.2    0.12       0
  5702.9    0.07       0
Bank Sta=4998.3,5002.9
Exp/Cntr=0.3,0.1

Type RM Length L Ch R = 1,82,0,0,0
BEGIN DESCRIPTION:
B19682
END DESCRIPTION:
XS GIS Cut Line= 4
      2223374.26     13853817.26      2224138.12     13853461.38
      2224290.03     13853192.28      2224852.96     13852728.94
#Sta/Elev= 30
  3943.6  848.57  4103.6  840.11  4126.5  836.07  4246.4  823.54  4284.4  816.47
  4315.0  814.02  4593.9  809.22  4950.7  801.14  4965.9  798.18  4972.4  791.12
  4991.3  786.83  4991.7  786.33  4996.8  786.83  5031.6  795.91  5052.4  797.48
  5111.4  799.94  5153.6  805.10  5218.3  807.74  5352.5  811.20  5381.2  808.42
  5387.6  809.20  5395.5  807.12  5402.0  808.82  5451.5  808.63  5502.4  816.23
  5580.6  821.26  5622.2  827.13  5695.7  832.66  5807.3  843.93  5824.4  846.98
#Mann=7,-1,0
  3943.6   0.035       0  4284.4    0.12       0  4593.9    0.07       0
  4991.3    0.05       0  4996.8    0.07       0  5052.4    0.12       0
  5695.7    0.07       0
Bank Sta=4991.3,4996.8
Exp/Cntr=0.3,0.1

Chan Stop Cuts=-1