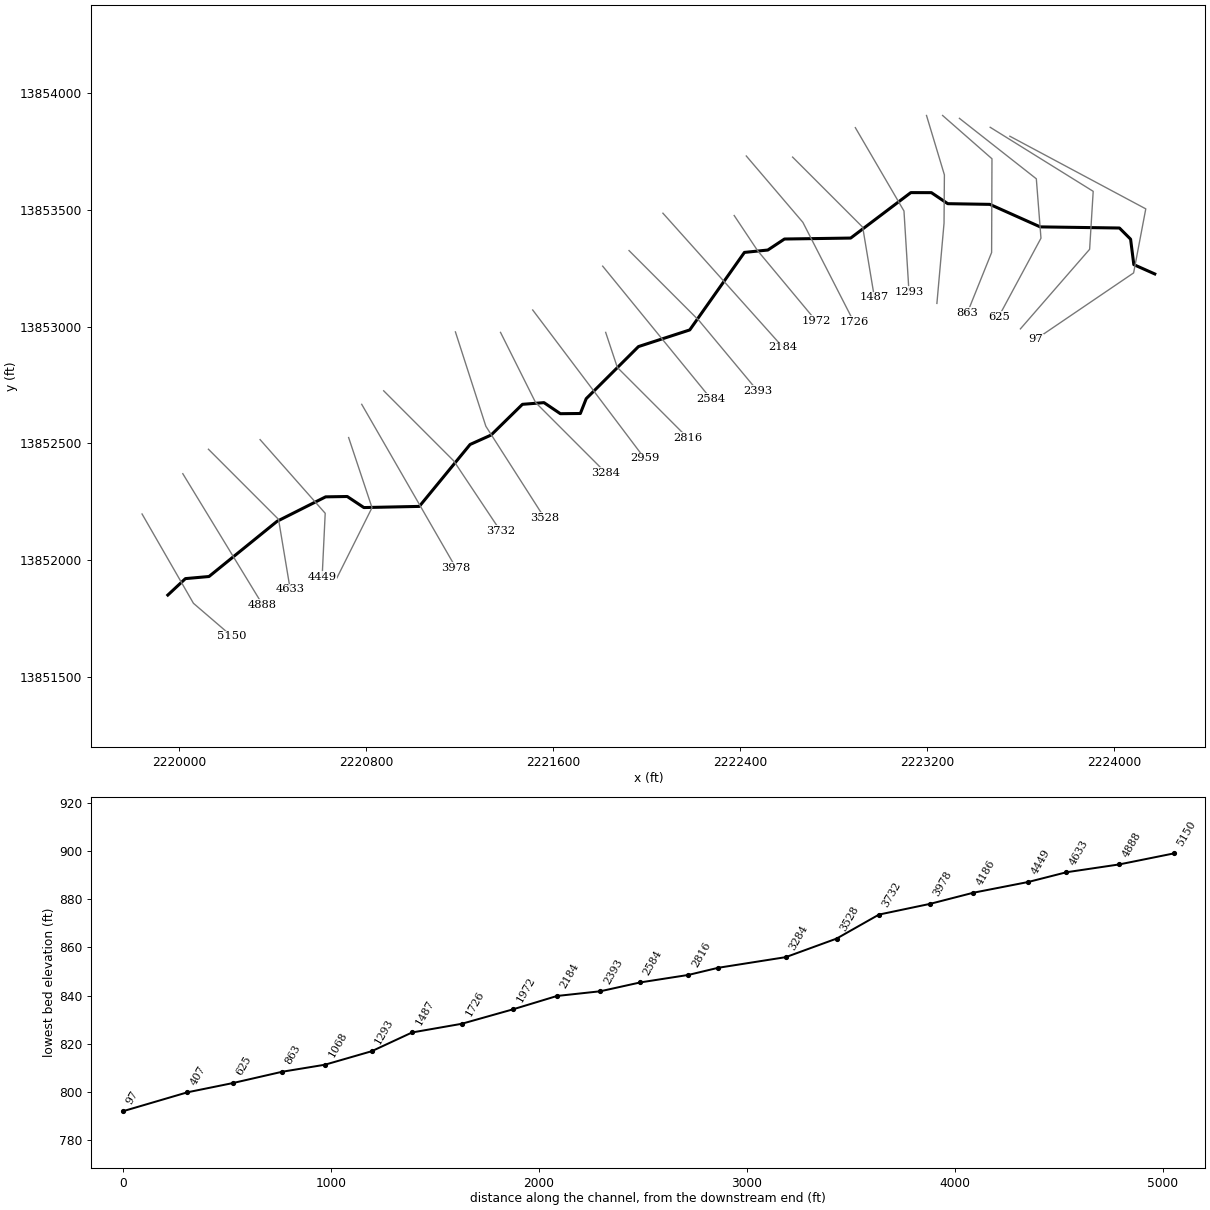
--- Mountain Tributary 3.prj (project) ---

Proj Title=Mountain Tributary 3 Base Level Engineering
Current Plan=p01
Default Exp/Contr=0.3,0.1
English Units
Geom File=g01
Flow File=f01
Plan File=p01
BEGIN DESCRIPTION:
Mountain Tributary 3
END DESCRIPTION:

--- Mountain Tributary 3.p01 (plan) ---

Plan Title=Multiple Run
Short Identifier=Multiple
Geom File=g01
Flow File=f01
Subcritical Flow
K Sum by GR= 0
Std Step Tol= 0.01
Critical Tol= 0.01
Num of Std Step Trials= 20
Max Error Tol= 0.3
Flow Tol Ratio= 0.001
Split Flow NTrial= 30
Split Flow Tol= 0.02
Split Flow Ratio= 0.02
Log Output Level= 0
Friction Slope Method= 1
Unsteady Friction Slope Method= 2
Unsteady Bridges Friction Slope Method= 1
Parabolic Critical Depth
Global Vel Dist=  1 , 1 , 1
Global Log Level= 0
CheckData=True
Encroach Param= -1, 0, 0, 0
BEGIN DESCRIPTION:
Multiple Run
END DESCRIPTION:

--- Mountain Tributary 3.f01 (steady flow) ---

Flow Title=Multiple
Number of Profiles=7
Profile Names=10-year,25-year,50-year,1pct_min,100-year,1pct_plu,500-year
River Rch & RM= Mountain Tributa,Reach-1,5150
     690    1133    1544    1021    2038    4066    3507
Boundary for River Rch & Prof#=Mountain Tributa,Reach-1,1
Up Type=0
Dn Type=3
Dn Slope=0.005
Boundary for River Rch & Prof#=Mountain Tributa,Reach-1,2
Up Type=0
Dn Type=3
Dn Slope=0.005
Boundary for River Rch & Prof#=Mountain Tributa,Reach-1,3
Up Type=0
Dn Type=3
Dn Slope=0.005
Boundary for River Rch & Prof#=Mountain Tributa,Reach-1,4
Up Type=0
Dn Type=3
Dn Slope=0.005
Boundary for River Rch & Prof#=Mountain Tributa,Reach-1,5
Up Type=0
Dn Type=3
Dn Slope=0.005
Boundary for River Rch & Prof#=Mountain Tributa,Reach-1,6
Up Type=0
Dn Type=3
Dn Slope=0.005
Boundary for River Rch & Prof#=Mountain Tributa,Reach-1,7
Up Type=0
Dn Type=3
Dn Slope=0.005

--- Mountain Tributary 3.g01 (geometry) ---

Geom Title=Existing Conditions

River Reach=Mountain Tributa,Reach-1
Reach XY= 30
      2219951.16     13851851.16      2220026.44     13851921.52
      2220127.42     13851930.53      2220418.94     13852166.86
      2220626.58     13852271.33      2220719.02     13852272.83
      2220790.22     13852225.52      2221027.45     13852230.46
      2221244.77     13852495.42      2221334.68     13852535.78
      2221468.83     13852667.24      2221561.03     13852674.45
      2221631.06     13852627.13      2221716.66     13852627.98
      2221741.74     13852691.45      2221965.32     13852914.24
      2222184.81     13852985.51      2222418.81     13853317.15
      2222519.02     13853327.36      2222590.22     13853374.48
      2222873.53     13853378.55      2223130.89     13853573.03
      2223219.02     13853572.84      2223288.92     13853525.69
      2223469.06     13853522.74      2223684.66     13853426.38
      2224023.78     13853421.56      2224071.49     13853373.75
      2224085.27     13853264.91      2224175.00     13853225.00

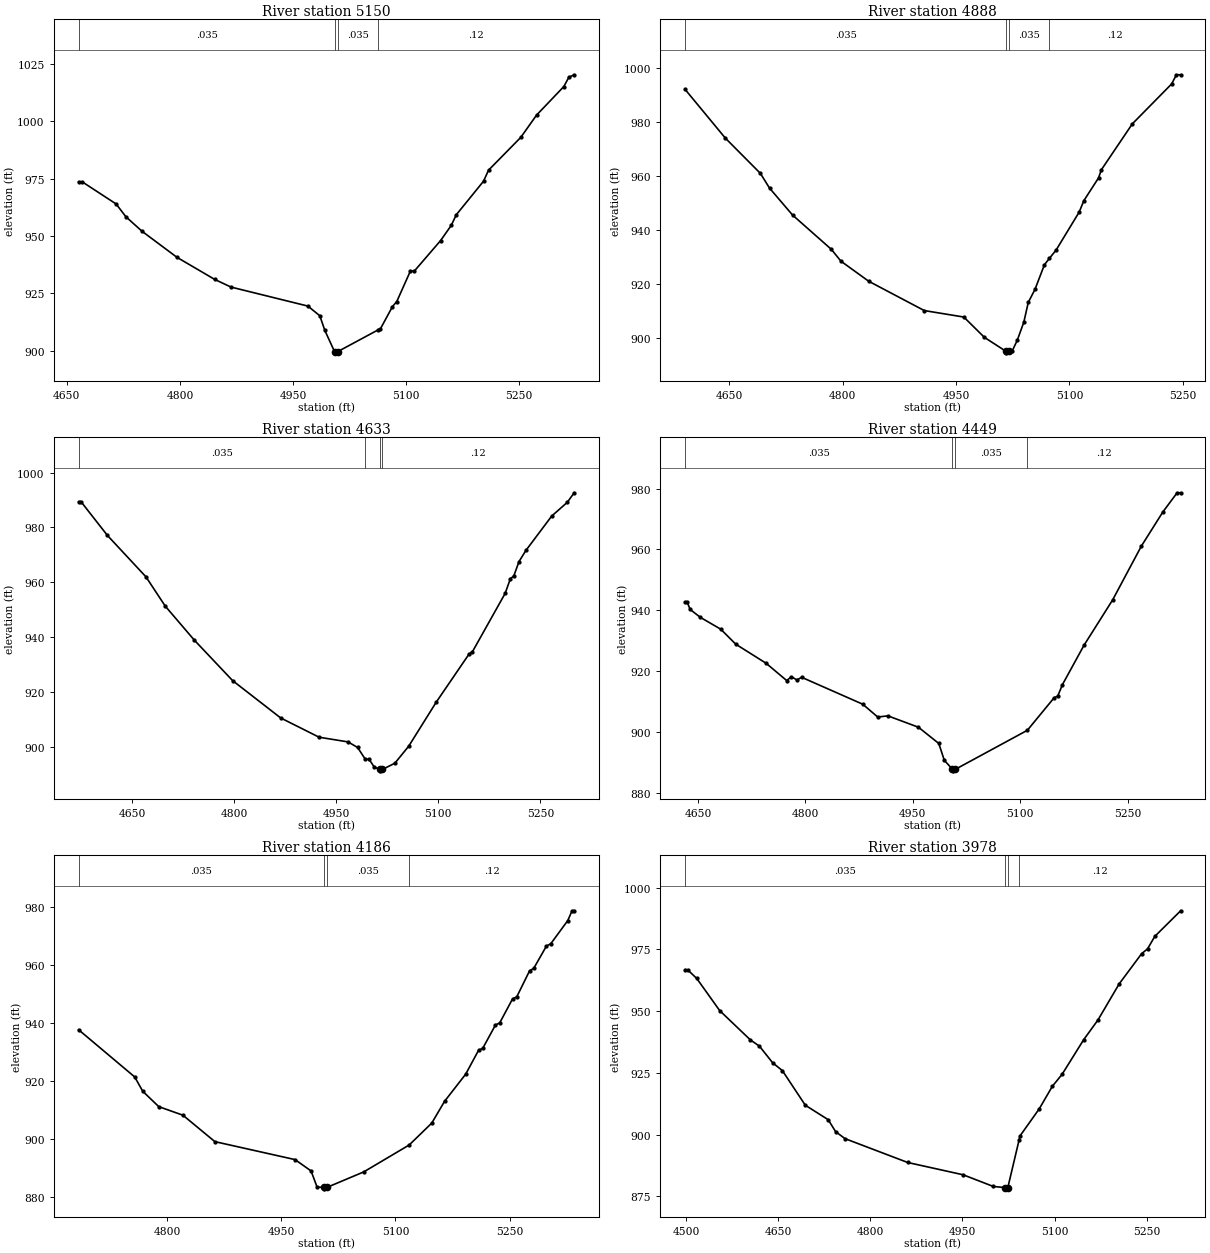
Type RM Length L Ch R = 1,5150,262,262,262
BEGIN DESCRIPTION:
Mountain Tributary 3 11.0
END DESCRIPTION:
XS GIS Cut Line= 3
      2219840.88     13852198.08      2220060.77     13851815.98
      2220225.01     13851674.99
#Sta/Elev= 30
  4665.7  973.59  4670.4  973.59  4715.4  963.94  4728.4  958.35  4750.0  951.97
  4796.2  940.65  4846.2  931.03  4867.8  927.69  4969.8  919.40  4985.6  915.18
  4992.3  908.76  5005.2  899.51  5005.4  899.01  5009.2  899.51  5063.1  909.05
  5066.1  909.54  5081.9  919.14  5087.7  921.39  5105.8  934.71  5111.1  934.71
  5145.8  947.96  5160.0  954.60  5166.6  959.21  5202.8  973.87  5209.4  978.66
  5252.2  992.98  5273.1 1002.68  5309.3 1015.14  5315.9 1019.17  5323.0 1020.27
#Mann=4,-1,0
  4665.7   0.035       0  5005.2   0.035       0  5009.2   0.035       0
  5063.1    0.12       0
Bank Sta=5005.2,5009.2
Exp/Cntr=0.3,0.1

Type RM Length L Ch R = 1,4888,255,255,255
BEGIN DESCRIPTION:
B19702
END DESCRIPTION:
XS GIS Cut Line= 2
      2220015.31     13852370.36      2220356.49     13851810.41
#Sta/Elev= 30
  4591.4  992.17  4644.6  974.12  4691.0  961.03  4703.1  955.57  4733.6  945.56
  4785.0  932.82  4797.6  928.45  4834.4  921.00  4907.9  910.13  4960.2  907.73
  4987.4  900.20  5016.3  894.95  5016.6  894.45  5020.3  894.95  5024.2  895.14
  5030.9  899.10  5039.6  905.83  5045.5  913.17  5054.4  918.01  5066.8  927.09
  5073.3  929.45  5082.3  932.57  5112.9  946.69  5119.0  950.88  5138.5  959.37
  5142.2  962.36  5183.2  979.40  5235.2  994.20  5241.5  997.60  5247.1  997.60
#Mann=4,-1,0
  4591.4   0.035       0  5016.3   0.035       0  5020.3   0.035       0
  5073.3    0.12       0
Bank Sta=5016.3,5020.3
Exp/Cntr=0.3,0.1

Type RM Length L Ch R = 1,4633,184,184,184
BEGIN DESCRIPTION:
Mountain Tributary 3 10.0
END DESCRIPTION:
XS GIS Cut Line= 3
      2220125.00     13852475.00      2220425.00     13852175.00
      2220475.00     13851875.00
#Sta/Elev= 30
  4571.3  989.41  4574.8  989.41  4613.7  977.07  4670.3  961.97  4698.6  951.30
  4741.0  938.98  4797.6  924.12  4868.3  910.48  4924.8  903.45  4967.3  901.74
  4981.4  899.70  4992.6  895.44  4998.1  895.44  5005.7  892.62  5013.8  891.68
  5014.1  891.18  5017.8  891.68  5036.1  893.96  5056.4  900.14  5096.9  916.23
  5145.1  933.77  5150.2  934.67  5198.3  955.97  5205.9  961.27  5211.0  962.33
  5218.6  967.55  5228.7  971.60  5266.7  984.17  5289.6  989.18  5299.7  992.66
#Mann=4,-1,0
  4571.3   0.035       0  4992.6    0.12       0  5013.8    0.05       0
  5017.8    0.12       0
Bank Sta=5013.8,5017.8
Exp/Cntr=0.3,0.1

Type RM Length L Ch R = 1,4449,263,263,263
BEGIN DESCRIPTION:
B19701
END DESCRIPTION:
XS GIS Cut Line= 3
      2220346.05     13852516.18      2220624.70     13852201.07
      2220611.68     13851930.22
#Sta/Elev= 30
  4632.1  942.58  4635.1  942.58  4639.2  940.22  4653.4  937.63  4681.9  933.73
  4702.8  928.81  4745.4  922.49  4773.9  916.84  4780.6  918.09  4788.1  917.04
  4794.8  917.91  4880.1  909.05  4901.0  904.84  4915.2  905.22  4957.9  901.47
  4986.3  896.13  4993.9  890.63  5005.4  887.63  5005.7  887.13  5009.4  887.63
  5109.9  900.47  5147.3  911.18  5152.3  911.72  5158.9  915.50  5189.0  928.45
  5229.0  943.38  5269.1  961.09  5299.1  972.31  5319.0  978.62  5323.9  978.62
#Mann=4,-1,0
  4632.1   0.035       0  5005.4   0.035       0  5009.4   0.035       0
  5109.9    0.12       0
Bank Sta=5005.4,5009.4
Exp/Cntr=0.3,0.1

Type RM Length L Ch R = 1,4186,208,208,208
BEGIN DESCRIPTION:
Mountain Tributary 3 9.0
END DESCRIPTION:
XS GIS Cut Line= 3
      2220724.99     13852525.02      2220825.00     13852225.00
      2220674.98     13851924.96
#Sta/Elev= 30
  4683.3  937.52  4757.1  921.25  4767.6  916.33  4788.7  911.02  4820.4  908.08
  4862.5  898.96  4967.9  892.77  4989.0  888.86  4996.9  883.28  5005.9  883.19
  5006.2  882.69  5009.9  883.19  5058.2  888.52  5118.0  897.80  5147.7  905.35
  5164.5  912.84  5192.4  922.25  5209.2  930.42  5214.8  931.15  5231.5  939.17
  5237.1  939.91  5253.9  948.13  5259.5  948.88  5276.3  957.82  5281.9  958.73
  5298.6  966.41  5304.2  967.17  5326.6  975.17  5332.2  978.54  5335.0  978.54
#Mann=4,-1,0
  4683.3   0.035       0  5005.9   0.035       0  5009.9   0.035       0
  5118.0    0.12       0
Bank Sta=5005.9,5009.9
Exp/Cntr=0.3,0.1

Type RM Length L Ch R = 1,3978,246,246,246
BEGIN DESCRIPTION:
B19700
END DESCRIPTION:
XS GIS Cut Line= 2
      2220780.96     13852667.20      2221183.66     13851968.32
#Sta/Elev= 30
  4498.7  966.76  4502.8  966.76  4517.7  963.23  4555.0  950.23  4605.1  938.33
  4619.7  935.84  4641.2  929.10  4657.0  925.95  4694.4  911.91  4731.7  906.05
  4743.6  901.25  4759.0  898.39  4861.0  888.74  4951.3  883.76  5000.4  879.03
  5020.0  878.57  5020.2  878.07  5024.0  878.57  5042.2  897.70  5043.7  899.44
  5075.1  910.44  5096.6  919.63  5112.4  924.45  5147.5  938.46  5170.6  946.38
  5205.3  961.06  5241.8  973.27  5251.4  975.22  5263.3  980.29  5305.3  990.64
#Mann=4,-1,0
  4498.7   0.035       0  5020.0   0.035       0  5024.0   0.035       0
  5042.2    0.12       0
Bank Sta=5020,5024
Exp/Cntr=0.3,0.1

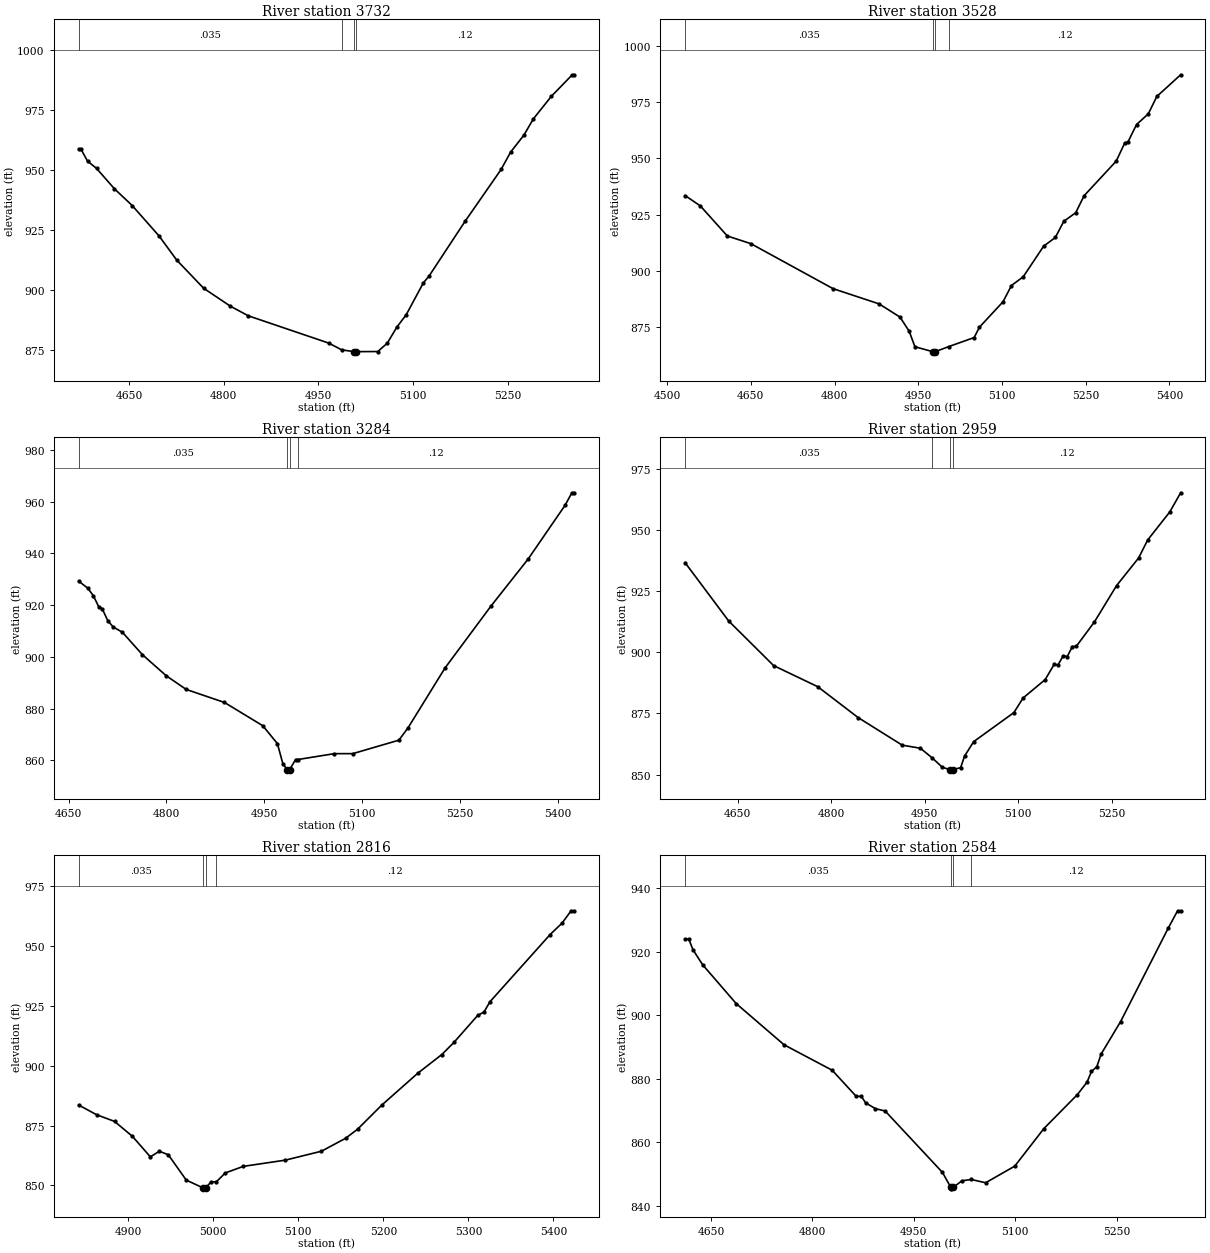
Type RM Length L Ch R = 1,3732,204,204,204
BEGIN DESCRIPTION:
Mountain Tributary 3 8.0
END DESCRIPTION:
XS GIS Cut Line= 3
      2220875.01     13852724.99      2221175.00     13852425.00
      2221375.00     13852125.00
#Sta/Elev= 30
  4570.3  958.59  4573.8  958.59  4584.4  953.51  4598.6  950.51  4626.9  942.01
  4655.1  935.02  4697.6  922.35  4725.8  912.22  4768.3  900.53  4810.7  893.04
  4839.0  889.05  4966.3  877.68  4986.9  874.86  5006.1  874.11  5006.3  873.61
  5010.1  874.11  5044.1  874.15  5059.1  877.64  5074.2  884.29  5089.2  889.54
  5116.2  902.75  5125.3  905.63  5182.3  928.43  5239.4  950.05  5254.4  957.26
  5275.5  964.35  5290.5  971.15  5319.0  980.54  5352.1  989.51  5355.1  989.51
#Mann=4,-1,0
  4570.3   0.035       0  4986.9    0.12       0  5006.1    0.05       0
  5010.1    0.12       0
Bank Sta=5006.1,5010.1
Exp/Cntr=0.3,0.1

Type RM Length L Ch R = 1,3528,244,244,244
BEGIN DESCRIPTION:
B19699
END DESCRIPTION:
XS GIS Cut Line= 3
      2221182.00     13852977.08      2221312.20     13852573.46
      2221562.22     13852182.82
#Sta/Elev= 30
  4532.2  933.46  4559.5  928.86  4607.9  915.50  4650.0  912.10  4797.1  892.15
  4879.9  885.35  4917.2  879.51  4933.7  873.22  4944.0  866.34  4976.2  864.13
  4976.5  863.63  4980.2  864.13  5005.0  866.44  5050.2  870.42  5059.5  874.99
  5101.8  886.29  5117.0  893.52  5138.1  897.41  5174.5  910.94  5195.6  914.85
  5210.8  922.05  5232.0  925.80  5247.2  933.40  5304.7  948.75  5319.9  956.76
  5325.8  957.29  5341.1  964.97  5362.2  969.74  5377.4  977.44  5420.1  987.07
#Mann=4,-1,0
  4532.2   0.035       0  4976.2   0.035       0  4980.2   0.035       0
  5005.0    0.12       0
Bank Sta=4976.2,4980.2
Exp/Cntr=0.3,0.1

Type RM Length L Ch R = 1,3284,325,325,325
BEGIN DESCRIPTION:
Mountain Tributary 3 7.0
END DESCRIPTION:
XS GIS Cut Line= 3
      2221374.99     13852975.02      2221525.00     13852675.00
      2221825.00     13852375.00
#Sta/Elev= 30
  4665.5  929.29  4679.5  926.55  4687.9  923.71  4696.3  919.39  4701.9  918.47
  4710.2  913.97  4718.6  911.54  4732.6  909.50  4763.3  900.84  4799.7  892.72
  4830.4  887.41  4889.1  882.37  4947.8  873.38  4970.2  866.48  4978.6  858.71
  4985.0  856.44  4985.2  855.94  4989.0  856.44  4998.1  860.30  5001.3  860.30
  5057.5  862.58  5085.8  862.59  5156.5  867.80  5170.6  872.60  5227.2  895.70
  5297.9  919.72  5354.5  937.77  5411.1  958.54  5421.7  963.43  5425.2  963.43
#Mann=4,-1,0
  4665.5   0.035       0  4985.0   0.035       0  4989.0   0.035       0
  5001.3    0.12       0
Bank Sta=4985,4989
Exp/Cntr=0.3,0.1

Type RM Length L Ch R = 1,2959,143,143,143
BEGIN DESCRIPTION:
B19698
END DESCRIPTION:
XS GIS Cut Line= 2
      2221512.74     13853070.83      2221990.93     13852436.72
#Sta/Elev= 30
  4566.0  936.65  4635.9  912.79  4707.9  894.56  4778.7  885.92  4843.2  873.32
  4914.0  862.02  4943.1  860.76  4962.2  856.78  4978.5  852.92  4991.1  852.02
  4991.3  851.52  4995.1  852.02  5007.6  852.82  5013.9  857.55  5028.5  863.46
  5093.0  875.35  5107.6  881.29  5143.0  888.81  5157.5  895.04  5163.8  894.88
  5172.1  898.64  5178.4  898.23  5186.7  902.36  5192.9  902.42  5222.1  912.45
  5257.5  927.27  5292.8  938.56  5307.4  945.94  5342.8  957.41  5360.2  965.24
#Mann=4,-1,0
  4566.0   0.035       0  4962.2    0.12       0  4991.1    0.05       0
  4995.1    0.12       0
Bank Sta=4991.1,4995.1
Exp/Cntr=0.3,0.1

Type RM Length L Ch R = 1,2816,232,232,232
BEGIN DESCRIPTION:
Mountain Tributary 3 6.0
END DESCRIPTION:
XS GIS Cut Line= 3
      2221825.00     13852975.00      2221875.00     13852825.00
      2222175.01     13852524.99
#Sta/Elev= 30
  4841.9  883.60  4863.0  879.54  4884.1  876.75  4905.2  870.48  4926.2  861.92
  4936.8  864.28  4947.3  862.80  4968.4  852.21  4987.5  849.06  4987.7  848.56
  4991.5  849.06  4997.4  851.43  5003.9  851.54  5014.2  855.19  5035.4  857.95
  5084.9  860.56  5127.3  864.29  5155.6  869.68  5169.7  873.47  5198.0  883.51
  5240.4  896.86  5268.7  904.69  5282.9  909.74  5311.1  921.13  5318.2  922.42
  5325.3  926.76  5396.0  954.85  5410.1  959.66  5420.7  964.80  5424.3  964.80
#Mann=4,-1,0
  4841.9   0.035       0  4987.5   0.035       0  4991.5   0.035       0
  5003.9    0.12       0
Bank Sta=4987.5,4991.5
Exp/Cntr=0.3,0.1

Type RM Length L Ch R = 1,2584,191,191,191
BEGIN DESCRIPTION:
B19697
END DESCRIPTION:
XS GIS Cut Line= 2
      2221812.20     13853258.36      2222275.74     13852690.66
#Sta/Elev= 30
  4611.7  923.96  4617.1  923.96  4623.3  920.58  4637.6  915.85  4687.2  903.66
  4758.0  890.71  4829.3  882.69  4864.5  874.55  4872.4  874.46  4878.8  872.45
  4893.2  870.63  4907.6  869.89  4992.3  850.61  5004.6  845.94  5004.9  845.44
  5008.6  845.94  5021.0  847.96  5034.9  848.38  5056.2  847.35  5099.3  852.58
  5142.3  864.36  5191.9  875.05  5206.2  878.97  5212.7  882.32  5220.6  883.80
  5227.1  887.82  5255.8  897.98  5326.1  927.29  5340.1  932.80  5344.6  932.80
#Mann=4,-1,0
  4611.7   0.035       0  5004.6   0.035       0  5008.6   0.035       0
  5034.9    0.12       0
Bank Sta=5004.6,5008.6
Exp/Cntr=0.3,0.1

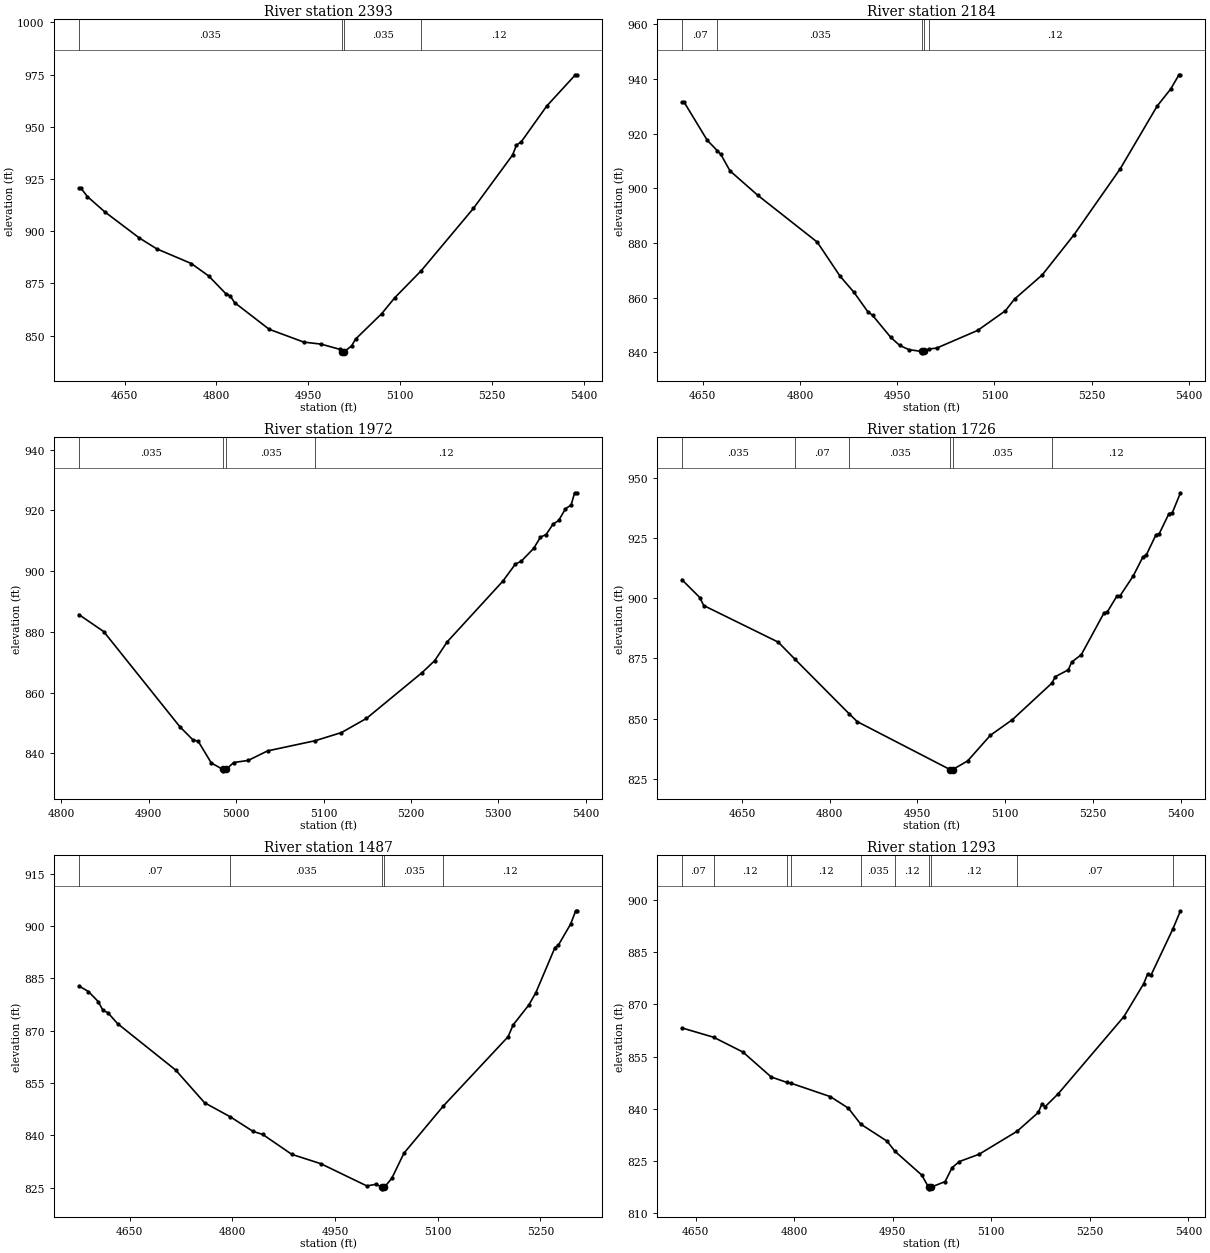
Type RM Length L Ch R = 1,2393,209,209,209
BEGIN DESCRIPTION:
Mountain Tributary 3 5.0
END DESCRIPTION:
XS GIS Cut Line= 3
      2221925.02     13853324.98      2222225.00     13853025.00
      2222475.03     13852724.96
#Sta/Elev= 30
  4575.3  920.61  4578.8  920.61  4589.4  916.62  4617.7  909.32  4674.3  896.78
  4702.6  891.60  4759.1  884.56  4787.4  878.63  4815.7  870.06  4822.8  869.03
  4829.8  865.85  4886.4  853.06  4943.0  846.92  4971.3  845.95  5002.8  843.38
  5004.7  842.28  5005.0  841.78  5008.7  842.28  5021.0  845.08  5027.5  848.35
  5070.5  860.62  5091.3  868.08  5134.6  881.05  5220.2  911.00  5284.0  936.49
  5290.5  941.25  5298.3  942.86  5339.9  959.98  5386.8  974.95  5390.1  974.95
#Mann=4,-1,0
  4575.3   0.035       0  5004.7   0.035       0  5008.7   0.035       0
  5134.6    0.12       0
Bank Sta=5004.7,5008.7
Exp/Cntr=0.3,0.1

Type RM Length L Ch R = 1,2184,212,212,212
BEGIN DESCRIPTION:
B19696
END DESCRIPTION:
XS GIS Cut Line= 2
      2222070.03     13853484.90      2222583.03     13852912.01
#Sta/Elev= 30
  4617.9  931.60  4621.2  931.60  4657.1  917.57  4672.8  913.72  4678.0  912.43
  4692.2  906.38  4734.8  897.49  4826.8  880.31  4861.9  867.87  4883.6  861.90
  4904.5  854.93  4912.0  853.55  4939.9  845.54  4953.8  842.54  4968.1  840.99
  4987.8  840.32  4988.0  839.82  4991.8  840.32  4998.8  841.24  5010.7  841.54
  5074.2  848.03  5116.8  855.19  5131.0  859.49  5173.7  868.32  5223.0  883.09
  5294.0  907.14  5350.9  930.07  5371.8  936.31  5384.6  941.52  5386.9  941.52
#Mann=5,-1,0
  4617.9    0.07       0  4672.8   0.035       0  4987.8    0.05       0
  4991.8   0.035       0  4998.8    0.12       0
Bank Sta=4987.8,4991.8
Exp/Cntr=0.3,0.1

Type RM Length L Ch R = 1,1972,246,246,246
BEGIN DESCRIPTION:
Mountain Tributary 3 4.0
END DESCRIPTION:
XS GIS Cut Line= 3
      2222375.01     13853474.99      2222475.00     13853325.00
      2222725.02     13853024.98
#Sta/Elev= 30
  4819.8  885.70  4848.3  880.10  4935.5  848.77  4950.5  844.43  4956.5  843.99
  4971.5  836.85  4984.5  834.76  4984.8  834.26  4988.5  834.76  4997.1  836.99
  5013.7  837.69  5035.9  840.82  5090.6  844.19  5120.5  846.86  5149.1  851.51
  5212.9  866.62  5227.2  870.52  5241.5  876.71  5305.3  896.71  5319.6  902.32
  5326.1  903.20  5340.5  907.46  5348.3  911.17  5354.8  912.03  5362.6  915.43
  5369.1  916.64  5376.9  920.49  5383.4  921.75  5387.3  925.76  5390.6  925.76
#Mann=4,-1,0
  4819.8   0.035       0  4984.5   0.035       0  4988.5   0.035       0
  5090.6    0.12       0
Bank Sta=4984.5,4988.5
Exp/Cntr=0.3,0.1

Type RM Length L Ch R = 1,1726,239,239,239
BEGIN DESCRIPTION:
B19695
END DESCRIPTION:
XS GIS Cut Line= 3
      2222426.79     13853729.71      2222668.97     13853445.86
      2222887.42     13853019.38
#Sta/Elev= 30
  4547.3  907.66  4578.1  900.22  4584.7  896.91  4712.1  881.71  4740.7  874.61
  4833.5  851.91  4847.1  848.71  5006.0  828.77  5006.3  828.27  5010.0  828.77
  5035.9  832.40  5074.7  843.04  5112.4  849.53  5179.8  864.69  5185.7  867.38
  5207.9  870.21  5213.5  873.38  5230.1  876.50  5268.9  893.83  5274.5  894.24
  5291.1  900.88  5296.7  901.07  5318.9  909.21  5335.5  917.15  5341.1  917.85
  5357.7  926.28  5363.3  926.74  5379.9  935.08  5385.5  935.36  5399.6  943.72
#Mann=6,-1,0
  4547.3   0.035       0  4740.7    0.07       0  4833.5   0.035       0
  5006.0   0.035       0  5010.0   0.035       0  5179.8    0.12       0
Bank Sta=5006,5010
Exp/Cntr=0.3,0.1

Type RM Length L Ch R = 1,1487,194,194,194
BEGIN DESCRIPTION:
Mountain Tributary 3 3.0
END DESCRIPTION:
XS GIS Cut Line= 3
      2222625.00     13853725.00      2222925.00     13853425.00
      2222975.00     13853125.00
#Sta/Elev= 30
  4575.7  882.84  4589.8  881.22  4604.0  878.36  4611.1  875.79  4618.1  875.18
  4632.3  872.03  4717.1  858.73  4759.5  849.33  4797.2  845.28  4830.3  841.12
  4844.4  840.25  4886.8  834.55  4929.3  831.86  4996.4  825.50  5010.1  825.97
  5018.2  825.16  5018.5  824.66  5022.2  825.16  5032.9  827.67  5050.7  834.89
  5108.3  848.43  5202.7  868.25  5210.3  871.69  5233.1  877.38  5243.3  880.88
  5271.2  893.81  5276.2  894.52  5294.0  900.51  5301.6  904.37  5304.1  904.37
#Mann=5,-1,0
  4575.7    0.07       0  4797.2   0.035       0  5018.2   0.035       0
  5022.2   0.035       0  5108.3    0.12       0
Bank Sta=5018.2,5022.2
Exp/Cntr=0.3,0.1

Type RM Length L Ch R = 1,1293,225,225,225
BEGIN DESCRIPTION:
B19694
END DESCRIPTION:
XS GIS Cut Line= 3
      2222893.47     13853850.97      2223101.65     13853494.31
      2223123.03     13853149.14
#Sta/Elev= 30
  4629.1  863.25  4677.4  860.56  4722.1  856.29  4765.1  849.11  4789.3  847.52
  4796.0  847.26  4855.2  843.44  4882.5  840.12  4901.3  835.53  4941.2  830.64
  4953.7  827.65  4994.1  820.87  5004.5  817.38  5004.8  816.88  5008.5  817.38
  5029.7  818.96  5040.4  822.99  5051.4  824.74  5081.5  826.85  5139.5  833.49
  5171.6  838.90  5176.9  841.27  5181.9  840.54  5201.7  844.24  5301.9  866.52
  5331.9  875.97  5337.9  878.76  5342.9  878.39  5376.2  891.70  5387.9  896.99
#Mann=10,-1,0
  4629.1    0.07       0  4677.4    0.12       0  4789.3   0.035       0
  4796.0    0.12       0  4901.3   0.035       0  4953.7    0.12       0
  5004.5    0.05       0  5008.5    0.12       0  5139.5    0.07       0
  5376.2    0.12       0
Bank Sta=5004.5,5008.5
Exp/Cntr=0.3,0.1

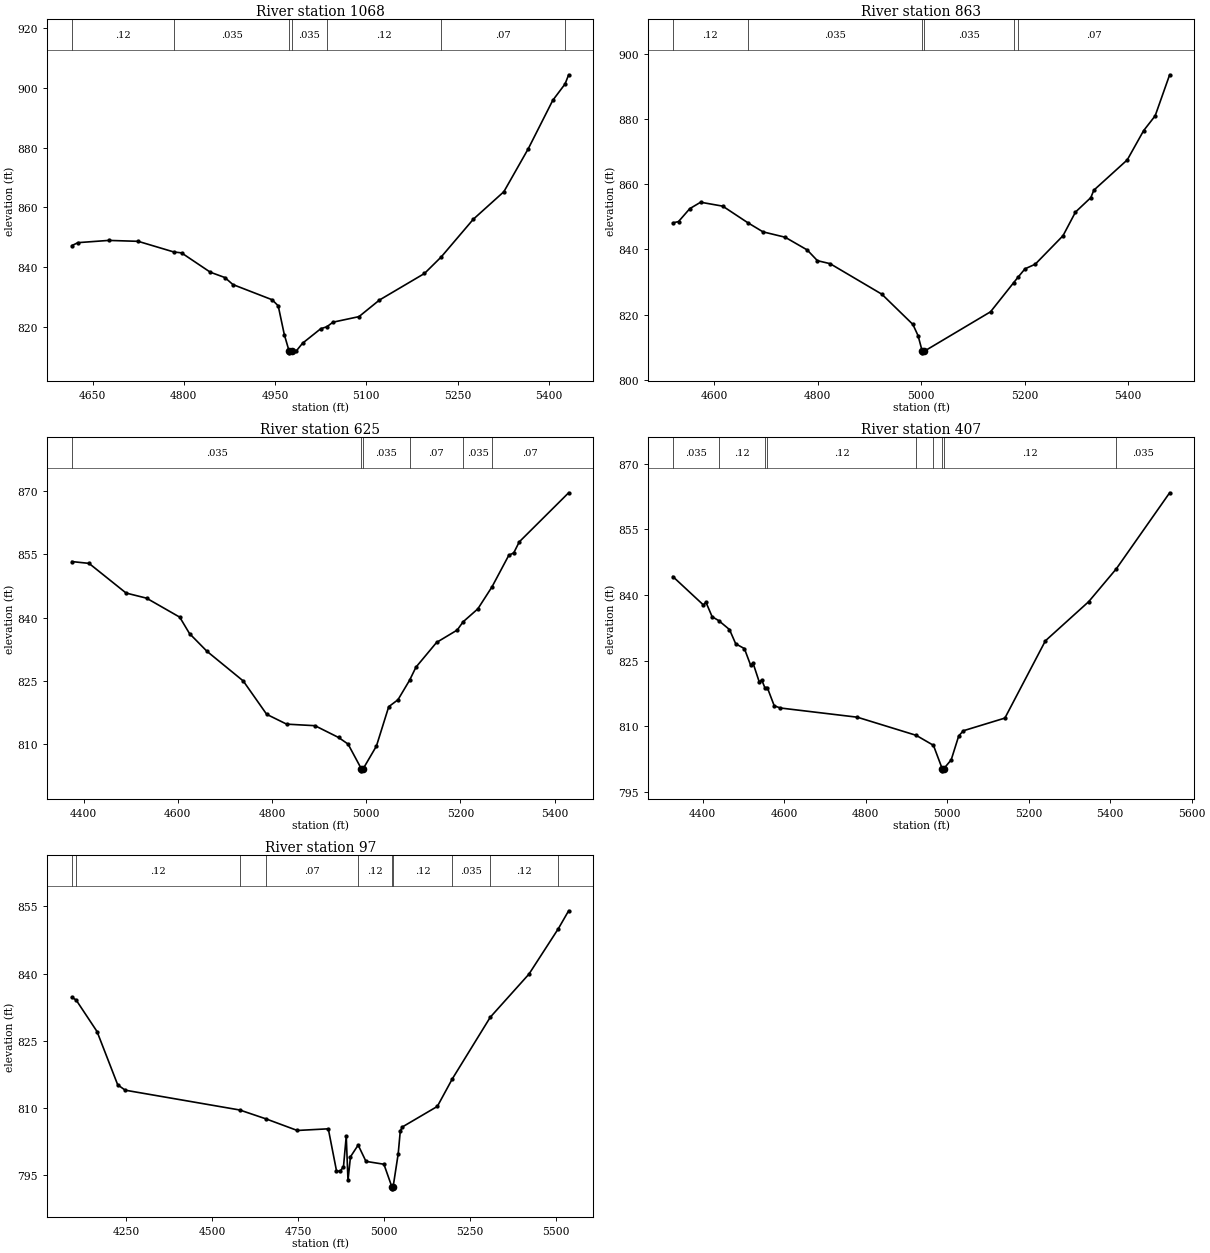
Type RM Length L Ch R = 1,1068,205,205,205
BEGIN DESCRIPTION:
B19693
END DESCRIPTION:
XS GIS Cut Line= 4
      2223198.09     13853903.02      2223274.63     13853648.93
      2223273.10     13853442.27      2223242.58     13853098.96
#Sta/Elev= 30
  4615.9  847.17  4626.0  848.16  4676.5  848.91  4725.0  848.60  4783.7  845.03
  4796.2  844.74  4843.6  838.26  4867.5  836.48  4880.7  834.13  4945.2  829.04
  4955.2  827.00  4965.2  817.37  4973.2  811.77  4973.5  811.27  4977.2  811.77
  4985.2  811.98  4995.2  814.49  5025.2  819.36  5035.0  819.99  5045.2  821.53
  5087.9  823.39  5121.6  828.95  5195.6  837.84  5223.1  843.37  5275.9  856.00
  5326.1  865.21  5366.3  879.63  5406.5  895.81  5426.7  901.28  5432.6  904.36
#Mann=7,-1,0
  4615.9    0.12       0  4783.7   0.035       0  4973.2   0.035       0
  4977.2   0.035       0  5035.0    0.12       0  5223.1    0.07       0
  5426.7    0.12       0
Bank Sta=4973.2,4977.2
Exp/Cntr=0.3,0.1

Type RM Length L Ch R = 1,863,238,238,238
BEGIN DESCRIPTION:
B19692
END DESCRIPTION:
XS GIS Cut Line= 4
      2223266.97     13853903.04      2223478.23     13853717.81
      2223476.70     13853316.74      2223373.01     13853059.05
#Sta/Elev= 30
  4520.4  848.15  4531.4  848.55  4553.2  852.51  4574.1  854.47  4616.8  853.27
  4665.0  848.22  4694.6  845.40  4737.3  843.76  4780.0  839.86  4799.7  836.58
  4824.2  835.66  4924.2  826.31  4984.2  817.05  4994.2  813.61  5002.2  808.86
  5002.4  808.36  5006.2  808.86  5134.2  820.93  5178.6  829.79  5187.4  831.54
  5200.8  834.09  5220.4  835.48  5274.2  844.22  5298.3  851.46  5327.9  855.88
  5333.7  858.15  5398.3  867.43  5430.0  876.41  5452.2  880.92  5480.2  893.49
#Mann=6,-1,0
  4520.4    0.12       0  4665.0   0.035       0  5002.2   0.035       0
  5006.2   0.035       0  5178.6    0.12       0  5187.4    0.07       0
Bank Sta=5002.2,5006.2
Exp/Cntr=0.3,0.1

Type RM Length L Ch R = 1,625,218,218,218
BEGIN DESCRIPTION:
B19691
END DESCRIPTION:
XS GIS Cut Line= 4
      2223338.96     13853890.77      2223668.05     13853632.09
      2223687.95     13853377.97      2223507.31     13853042.72
#Sta/Elev= 30
  4375.2  853.30  4411.7  852.87  4490.4  845.83  4533.7  844.62  4604.2  840.11
  4625.0  836.21  4662.0  832.01  4739.0  824.97  4788.7  817.06  4831.0  814.73
  4891.2  814.36  4941.3  811.56  4961.4  810.00  4989.5  804.15  4989.7  803.65
  4993.5  804.15  5021.6  809.53  5047.7  818.87  5067.3  820.51  5092.0  825.15
  5105.4  828.23  5149.2  834.11  5193.0  837.05  5205.6  839.01  5236.8  842.08
  5266.9  847.31  5302.5  854.79  5313.0  855.37  5324.7  857.97  5429.5  869.62
#Mann=6,-1,0
  4375.2   0.035       0  4989.5   0.035       0  4993.5   0.035       0
  5092.0    0.07       0  5205.6   0.035       0  5266.9    0.07       0
Bank Sta=4989.5,4993.5
Exp/Cntr=0.3,0.1

Type RM Length L Ch R = 1,407,310,310,310
BEGIN DESCRIPTION:
B19690
END DESCRIPTION:
XS GIS Cut Line= 4
      2223470.61     13853852.50      2223911.45     13853578.51
      2223896.14     13853330.52      2223599.93     13852990.03
#Sta/Elev= 30
  4327.2  844.20  4402.4  837.69  4408.3  838.36  4423.7  835.01  4439.7  834.14
  4466.2  832.09  4481.5  828.83  4502.8  827.74  4518.1  823.93  4524.0  824.42
  4539.4  820.07  4545.2  820.60  4553.2  818.76  4558.9  818.85  4576.0  814.67
  4591.3  814.17  4779.8  812.07  4924.2  807.93  4966.5  805.65  4988.0  800.32
  4988.3  799.82  4992.0  800.32  5010.1  802.33  5028.6  807.81  5040.1  808.98
  5141.8  811.87  5241.2  829.52  5347.5  838.47  5415.1  845.96  5546.0  863.33
#Mann=9,-1,0
  4327.2   0.035       0  4439.7    0.12       0  4553.2   0.035       0
  4558.9    0.12       0  4924.2    0.07       0  4966.5    0.12       0
  4988.0    0.05       0  4992.0    0.12       0  5415.1   0.035       0
Bank Sta=4988,4992
Exp/Cntr=0.3,0.1

Type RM Length L Ch R = 1,97,0,0,0
BEGIN DESCRIPTION:
B19689
END DESCRIPTION:
XS GIS Cut Line= 4
      2223554.81     13853814.23      2224136.47     13853503.50
      2224084.43     13853229.48      2223665.01     13852944.77
#Sta/Elev= 30
  4091.8  834.71  4104.2  834.13  4165.1  827.08  4225.3  815.18  4247.2  813.98
  4580.3  809.56  4656.6  807.58  4747.6  804.99  4837.9  805.36  4861.7  796.01
  4871.9  795.84  4882.1  796.90  4890.1  803.71  4895.2  793.86  4902.4  799.11
  4924.8  801.73  4947.5  798.09  4999.7  797.45  5022.6  792.46  5022.8  791.96
  5026.6  792.46  5041.3  799.80  5047.3  804.88  5053.7  805.79  5155.1  810.36
  5198.7  816.51  5309.1  830.27  5421.6  839.89  5507.3  850.06  5537.1  854.03
#Mann=10,-1,0
  4091.8   0.035       0  4104.2    0.12       0  4580.3     0.1       0
  4656.6    0.07       0  4924.8    0.12       0  5022.6    0.05       0
  5026.6    0.12       0  5198.7   0.035       0  5309.1    0.12       0
  5507.3   0.035       0
Bank Sta=5022.6,5026.6
Exp/Cntr=0.3,0.1

Chan Stop Cuts=-1