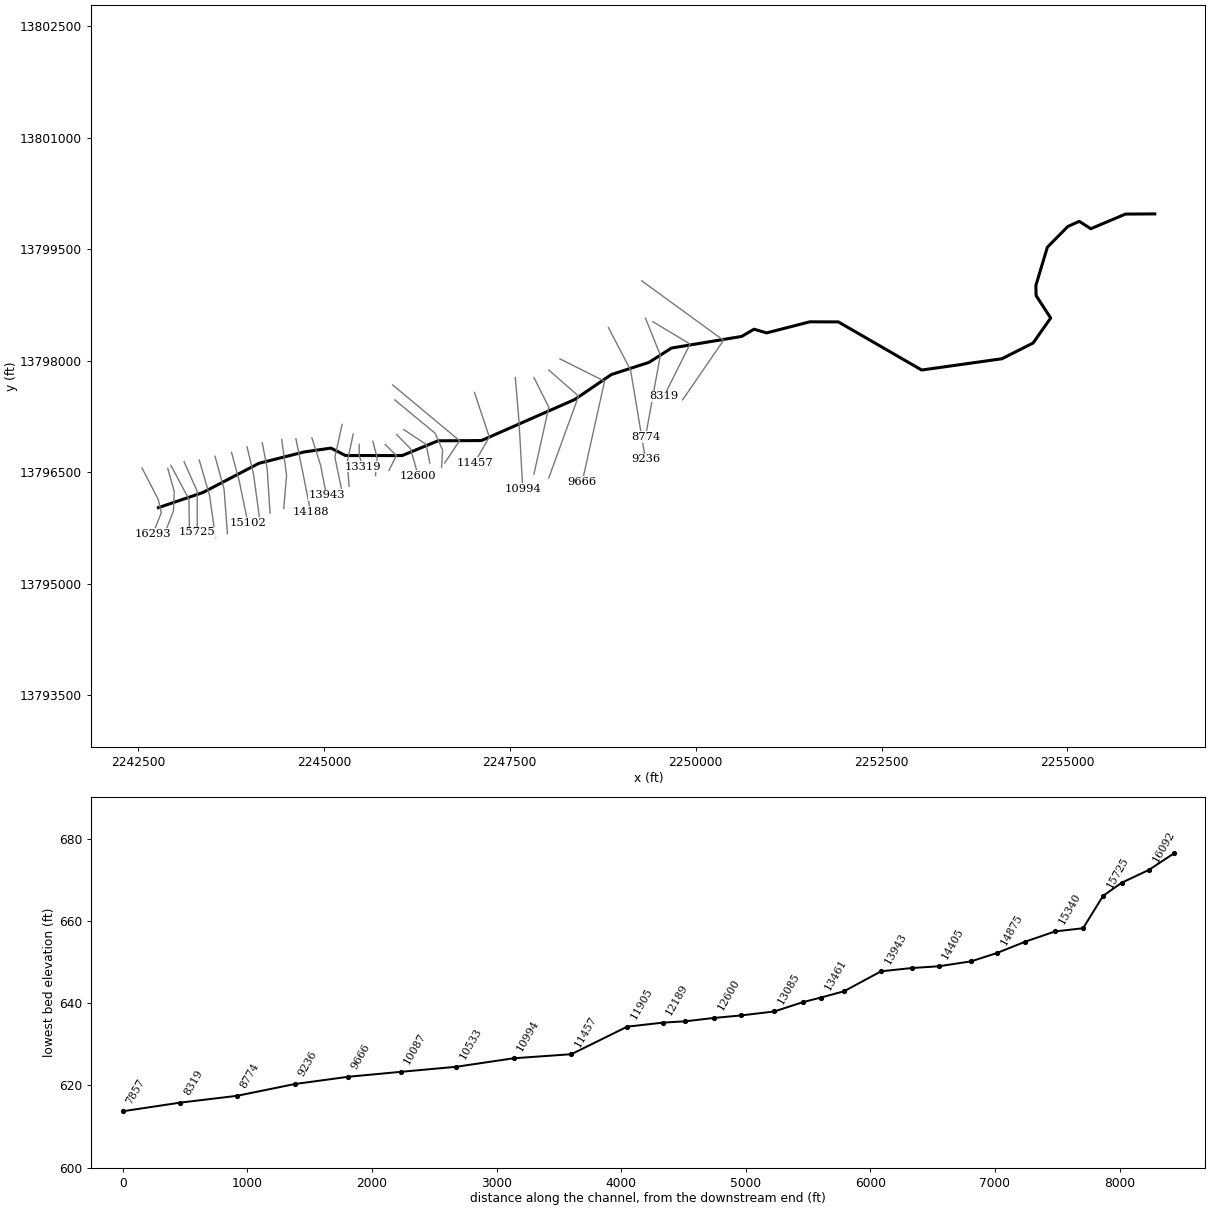
--- North Guadalupe Tributary.prj (project) ---

Proj Title=North Guadalupe Tributary Base Level Engineering
Current Plan=p01
Default Exp/Contr=0.3,0.1
English Units
Geom File=g01
Flow File=f01
Plan File=p01
Y Axis Title=Elevation
X Axis Title(PF)=Main Channel Distance
X Axis Title(XS)=Station
BEGIN DESCRIPTION:
North Guadalupe Tributary
END DESCRIPTION:
DSS Export Rating Curves= 0
DSS Export Rating Curve Sorted= 0
DSS Export Volume Flow Curves= 0
DXF OffsetX= 0
DXF OffsetY= 0
DXF ScaleX= 1
DXF ScaleY= 10

--- North Guadalupe Tributary.p01 (plan) ---

Plan Title=Multiple Run
Program Version=4.10
Short Identifier=Multiple
Geom File=g01
Flow File=f01
Subcritical Flow
K Sum by GR= 0
Std Step Tol= 0.01
Critical Tol= 0.01
Num of Std Step Trials= 20
Max Error Tol= 0.3
Flow Tol Ratio= 0.001
Split Flow NTrial= 30
Split Flow Tol= 0.02
Split Flow Ratio= 0.02
Log Output Level= 0
Friction Slope Method= 1
Unsteady Friction Slope Method= 2
Unsteady Bridges Friction Slope Method= 1
Parabolic Critical Depth
Global Vel Dist= 1 , 1 , 1
Global Log Level= 0
CheckData=True
Encroach Param=-1 ,0,0, 0
BEGIN DESCRIPTION:
Multiple Run
END DESCRIPTION:
Computation Interval=1HOUR
Output Interval=1HOUR
Run HTab= 0
Run UNet= 0
Run PostProcess= 0
Run WQNet= 0
UNET Theta= 1
UNET Theta Warmup= 1
UNET ZTol= 0.02
UNET ZSATol= 0.05
UNET MxIter= 20
UNET MaxInSteps= 0
UNET DtIC= 0
UNET DtMin= 0
UNET MaxCRTS= 20
UNET WFStab= 2
UNET SFStab= 1
UNET WFX= 1
UNET SFX= 1
UNET DSS MLevel= 4
UNET DZMax Abort= 100
UNET Convert EG Bridges= 0
UNET Use Existing IB Tables=-1
UNET Froude Reduction=False
UNET Froude Limit= 1
UNET Froude Power= 10
UNET Time Slicing=0,0, 5
UNET Junction Losses=0
Instantaneous Interval=1HOUR
Write IC File= 0
Write IC File at Sim End=0
Echo Input=False
Echo Parameters=False
Echo Output=False
Write Detailed= 0
WQ AD Non Conservative
WQ ULTIMATE=-1
WQ Max Comp Step=1HOUR
WQ Output Interval=15MIN
WQ Output Selected Increments= 0
WQ Output face flow=0
WQ Output face velocity=0
WQ Output face area=0
WQ Output face dispersion=0
WQ Output cell volume=0
WQ Output cell surface area=0
WQ Output cell continuity=0
WQ Output cumulative cell continuity=0
WQ Output face conc=0
WQ Output face dconc_dx=0
WQ Output face courant=0
WQ Output face peclet=0
WQ Output face adv mass=0
WQ Output face disp mass=0
WQ Output cell mass=0
WQ Output cell source sink temp=0
WQ Output cell source sink nsm=0
WQ Output MaxMinRange=-1
WQ Daily Max Min Mean=-1
WQ Daily Range=0
WQ Daily Time=0
WQ Create Restart=0
WQ Fixed Restart=0
WQ System Summary=0
WQ Use Fixed Temperature=0
Sorting and Armoring Iterations= 10
XS Update Threshold= 0.02
Hydraulics Update Threshold= 0.02
Energy Slope Method= 1
Volume Change Method= 0
XS Weighting Method= 0
Number of US Weighted Cross Sections= 1
Number of DS Weighted Cross Sections= 1
Upstream XS Weight=0.25
Main XS Weight=0.5
Downstream XS Weight=0.25
Number of DS XS's Weighted with US Boundary= 1
Upstream Boundary Weight= 1
Weight of XSs Associated with US Boundary= 0
Number of US XS's Weighted with DS Boundary= 1
Downstream Boundary Weight= 0.5
Weight of XSs Associated with DS Boundary= 0.5
Sediment Output Level= 4
Mass or Volume Output= 0
Output Increment Type= 1
Profile and TS Output Increment= 10
XS Output Flag= 0
XS Output Increment= 10
Disregard all LS=0
Disregard all Conn=0
Disregard all Breaches=0
Disregard all Pumps=0

--- North Guadalupe Tributary.f01 (steady flow) ---

Flow Title=Multiple
Number of Profiles=7
Profile Names=10-year,25-year,50-year,1pct_min,100-year,1pct_plu,500-year
River Rch & RM= North Guadalupe ,Reach-1,16293
     493     783    1041     671    1339    2671    2190
River Rch & RM= North Guadalupe ,Reach-1,11457
     774    1253    1687    1098    2191    4373    3660
River Rch & RM= North Guadalupe ,Reach-1,2679
    2027    3451    4804    3225    6434   12838   11433
Boundary for River Rch & Prof#=North Guadalupe ,Reach-1,1
Up Type=0
Dn Type=3
Dn Slope=0.005
Boundary for River Rch & Prof#=North Guadalupe ,Reach-1,2
Up Type=0
Dn Type=3
Dn Slope=0.005
Boundary for River Rch & Prof#=North Guadalupe ,Reach-1,3
Up Type=0
Dn Type=3
Dn Slope=0.005
Boundary for River Rch & Prof#=North Guadalupe ,Reach-1,4
Up Type=0
Dn Type=3
Dn Slope=0.005
Boundary for River Rch & Prof#=North Guadalupe ,Reach-1,5
Up Type=0
Dn Type=3
Dn Slope=0.005
Boundary for River Rch & Prof#=North Guadalupe ,Reach-1,6
Up Type=0
Dn Type=3
Dn Slope=0.005
Boundary for River Rch & Prof#=North Guadalupe ,Reach-1,7
Up Type=0
Dn Type=3
Dn Slope=0.005

--- North Guadalupe Tributary.g01 (geometry) ---

Geom Title=Existing Conditions
Program Version=4.10

River Reach=North Guadalupe ,Reach-1
Reach XY= 30
        2242775.       13796025.      2243373.53     13796228.55
      2244126.58     13796621.17      2244734.66     13796773.62
      2245095.05      13796825.6      2245290.21     13796725.51
      2246052.31      13796724.9      2246534.66     13796923.62
      2247119.03     13796927.14      2248373.42     13797478.83
      2248868.34     13797815.69      2249373.42     13797978.83
       2249676.5     13798171.38      2250619.07     13798327.24
      2250785.68     13798424.25       2250954.9     13798374.91
       2251535.5     13798523.78      2251919.07     13798522.76
      2253040.21     13797875.51      2254119.14     13798027.07
      2254538.22     13798238.62        2254775.       13798575.
      2254578.74     13798876.56      2254576.21     13799014.49
      2254730.54     13799527.37      2255004.91     13799805.22
      2255159.66     13799875.05       2255314.3      13799775.7
      2255780.93     13799972.76        2256175.       13799975.

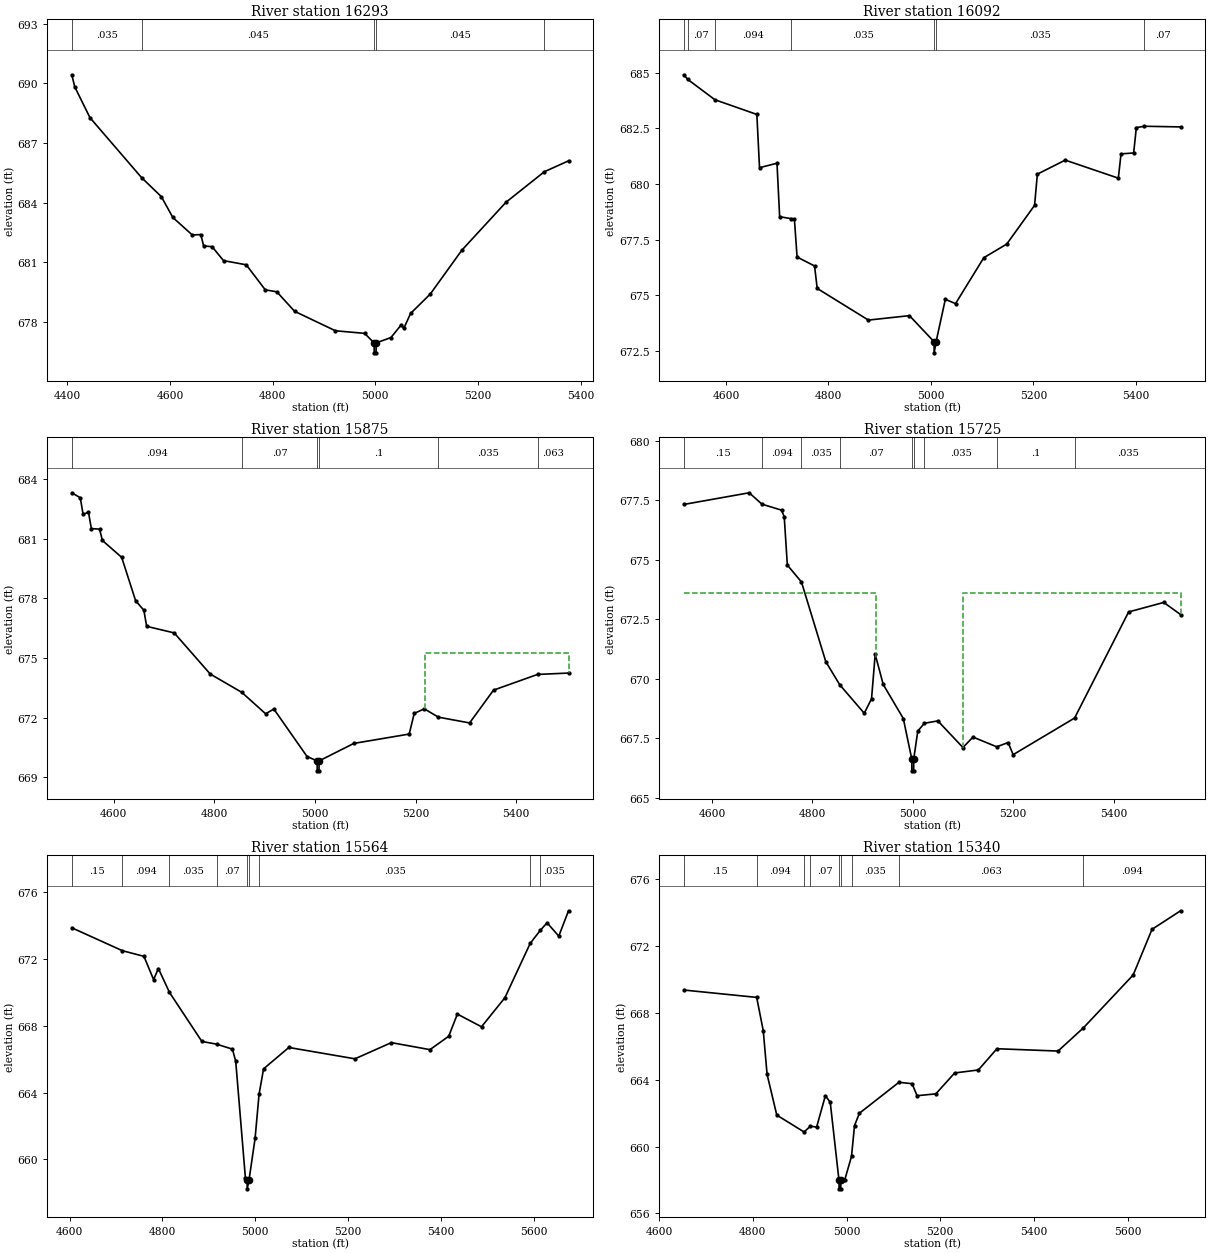
Type RM Length L Ch R = 1 ,16293   ,201,201,201
BEGIN DESCRIPTION:
B19804
END DESCRIPTION:
XS GIS Cut Line= 4
        2242553.     13796559.97      2242771.84     13796136.18
      2242813.53     13795955.53      2242699.46     13795672.08
#Sta/Elev= 30
  4408.6  690.43  4414.2  689.83    4444  688.27  4544.4  685.26    4583   684.3
  4605.5  683.25  4643.4  682.37  4659.9  682.39  4665.5  681.82    4682  681.78
  4704.2  681.08  4748.5  680.87  4785.6  679.61  4808.1  679.51  4842.7  678.53
  4922.3  677.55  4979.1  677.42  4997.7  676.94  4997.9  676.44  5001.4  676.44
  5001.7  676.94  5030.5  677.21  5050.6  677.85  5055.7  677.68  5068.7  678.42
  5107.2   679.4  5168.5   681.6  5254.8  684.02  5329.3  685.55  5376.5   686.1
#Mann= 5 ,-1 , 0
  4408.6    .035       0  4544.4    .045       0  4997.7    .045       0
  5001.7    .045       0  5329.3     .07       0
Bank Sta=4997.7,5001.7
XS Rating Curve= 0 ,0
Exp/Cntr=0.3,0.1

Type RM Length L Ch R = 1 ,16092   ,217,217,217
BEGIN DESCRIPTION:
B19805
END DESCRIPTION:
XS GIS Cut Line= 4
      2242900.37     13796553.09      2242987.23     13796243.87
       2242976.8     13795979.85      2242837.83       13795622.
#Sta/Elev= 30
  4517.9   684.9    4525   684.7  4578.4  683.78  4660.3  683.12  4665.5  680.73
  4699.6  680.93  4704.8  678.53  4727.7  678.44  4733.6  678.42  4738.8  676.72
  4772.9  676.32  4778.1  675.31    4878  673.89  4958.1  674.09  5006.1  672.92
  5006.3  672.42  5010.1  672.92  5028.1  674.82  5048.1  674.63  5103.2  676.69
  5147.9   677.3  5202.3  679.04  5207.7  680.44  5262.1  681.07  5365.7  680.26
    5371  681.35  5395.6  681.39  5400.9  682.53  5416.6  682.59  5487.2  682.56
#Mann= 7 ,-1 , 0
  4517.9    .035       0    4525     .07       0  4578.4    .094       0
  4727.7    .035       0  5006.1    .035       0  5010.1    .035       0
  5416.6     .07       0
Bank Sta=5006.1,5010.1
XS Rating Curve= 0 ,0
Exp/Cntr=0.3,0.1

Type RM Length L Ch R = 1 ,15875   ,150,150,150
BEGIN DESCRIPTION:
B19806
END DESCRIPTION:
XS GIS Cut Line= 3
      2242942.08     13796594.72      2243185.24     13796136.18
      2243192.17     13795668.56
#Sta/Elev= 30
  4517.1  683.31  4533.9  683.06  4539.5  682.23  4550.2  682.33  4555.9  681.51
  4572.2  681.48  4577.9  680.91  4616.2  680.06  4643.8  677.88  4660.2   677.4
  4665.8  676.59  4720.5  676.26  4792.1  674.19  4854.7  673.27  4902.1  672.19
  4918.4  672.43  4984.4  670.04  5004.4  669.82  5004.6  669.32  5008.1  669.32
  5008.4  669.82  5077.3   670.7  5187.3  671.17  5197.3  672.21  5217.3  672.44
  5245.4  672.02  5307.3  671.73  5354.8  673.38  5442.2  674.17  5503.8  674.24
#Mann= 6 ,-1 , 0
  4517.1    .094       0  4854.7     .07       0  5004.4     .05       0
  5008.4      .1       0  5245.4    .035       0  5442.2    .063       0
#XS Ineff= 2 , 0
       0                  5219.4       0  675.27
Permanent Ineff=
       F       F
Bank Sta=5004.4,5008.4
XS Rating Curve= 0 ,0
Exp/Cntr=0.3,0.1

Type RM Length L Ch R = 1 ,15725   ,161,161,161
BEGIN DESCRIPTION:
B19807
END DESCRIPTION:
XS GIS Cut Line= 3
      2243119.22      13796643.4      2243296.41     13796243.87
      2243296.41     13795691.53
#Sta/Elev= 30
  4544.1  677.33  4674.2  677.82  4699.7  677.34  4738.6  677.09    4744  676.81
  4750.2  674.78  4778.3  674.07  4826.8  670.72  4854.5  669.75  4903.4  668.55
  4917.9  669.16  4925.2  671.03  4941.2  669.76  4981.2  668.33    4998  666.63
  4998.3  666.13  5001.8  666.13    5002  666.63    5010   667.8  5023.2  668.13
    5050  668.23    5100  667.11    5120  667.55  5167.3  667.14    5190  667.32
    5200  666.81  5322.4  668.35    5430  672.81    5500  673.21  5533.5   672.7
#Mann= 9 ,-1 , 0
  4544.1     .15       0  4699.7    .094       0  4778.3    .035       0
  4854.5     .07       0    4998     .05       0    5002     .07       0
  5023.2    .035       0  5167.3      .1       0  5322.4    .035       0
#XS Ineff= 2 , 0
       0  4927.3  673.59    5100       0  673.59
Permanent Ineff=
       F       F
Bank Sta=4998,5002
XS Rating Curve= 0 ,0
Exp/Cntr=0.3,0.1

Type RM Length L Ch R = 1 ,15564   ,224,224,224
BEGIN DESCRIPTION:
B19808
END DESCRIPTION:
XS GIS Cut Line= 3
      2243324.19     13796664.25      2243463.16     13796184.81
      2243542.96     13795619.29
#Sta/Elev= 30
  4604.6  673.88  4713.4  672.51    4760  672.17  4780.8  670.78  4791.2  671.44
    4815  670.01  4884.9  667.07  4916.5  666.91  4950.7  666.61  4957.8  665.88
  4978.6  658.91  4982.3  658.74  4982.5  658.24  4986.3  658.74  4999.5  661.26
  5008.1  663.91  5017.8  665.43  5072.3  666.71  5214.7  666.03  5293.1     667
  5376.3  666.58  5416.7  667.38  5435.4  668.71  5487.4  667.95  5537.8  669.69
  5592.4  672.95  5614.2  673.73  5628.7  674.18  5653.9  673.38  5674.9   674.9
#Mann= 9 ,-1 , 0
  4604.6     .15       0  4713.4    .094       0    4815    .035       0
  4916.5     .07       0  4982.3     .05       0  4986.3     .07       0
  5008.1    .035       0  5592.4    .063       0  5614.2    .035       0
Bank Sta=4982.3,4986.3
XS Rating Curve= 0 ,0
Exp/Cntr=0.3,0.1

Type RM Length L Ch R = 1 ,15340   ,238,238,238
BEGIN DESCRIPTION:
B19809
END DESCRIPTION:
XS GIS Cut Line= 3
      2243536.12      13796716.3       2243657.7     13796271.66
      2243702.86     13795674.13
#Sta/Elev= 30
  4652.8  669.36  4808.2  668.92  4822.2  666.93  4830.4  664.32  4851.1  661.88
  4909.4  660.87  4922.9  661.22  4936.1  661.16  4954.8  663.04  4965.2  662.65
  4983.9  657.97  4984.1  657.47  4987.6  657.47  4987.9  657.97  4996.3  658.02
  5010.6  659.41    5017  661.25  5027.4  661.99  5111.8  663.84  5139.9  663.76
  5150.5  663.04  5190.6  663.15  5230.8   664.4  5281.4  664.58    5321  665.85
  5451.4  665.71  5505.7   667.1  5611.8  670.26    5652  672.99    5713   674.1
#Mann= 9 ,-1 , 0
  4652.8     .15       0  4808.2    .094       0  4909.4    .035       0
  4922.9     .07       0  4983.9     .05       0  4987.9     .07       0
  5010.6    .035       0  5111.8    .063       0  5505.7    .094       0
Bank Sta=4983.9,4987.9
XS Rating Curve= 0 ,0
Exp/Cntr=0.3,0.1

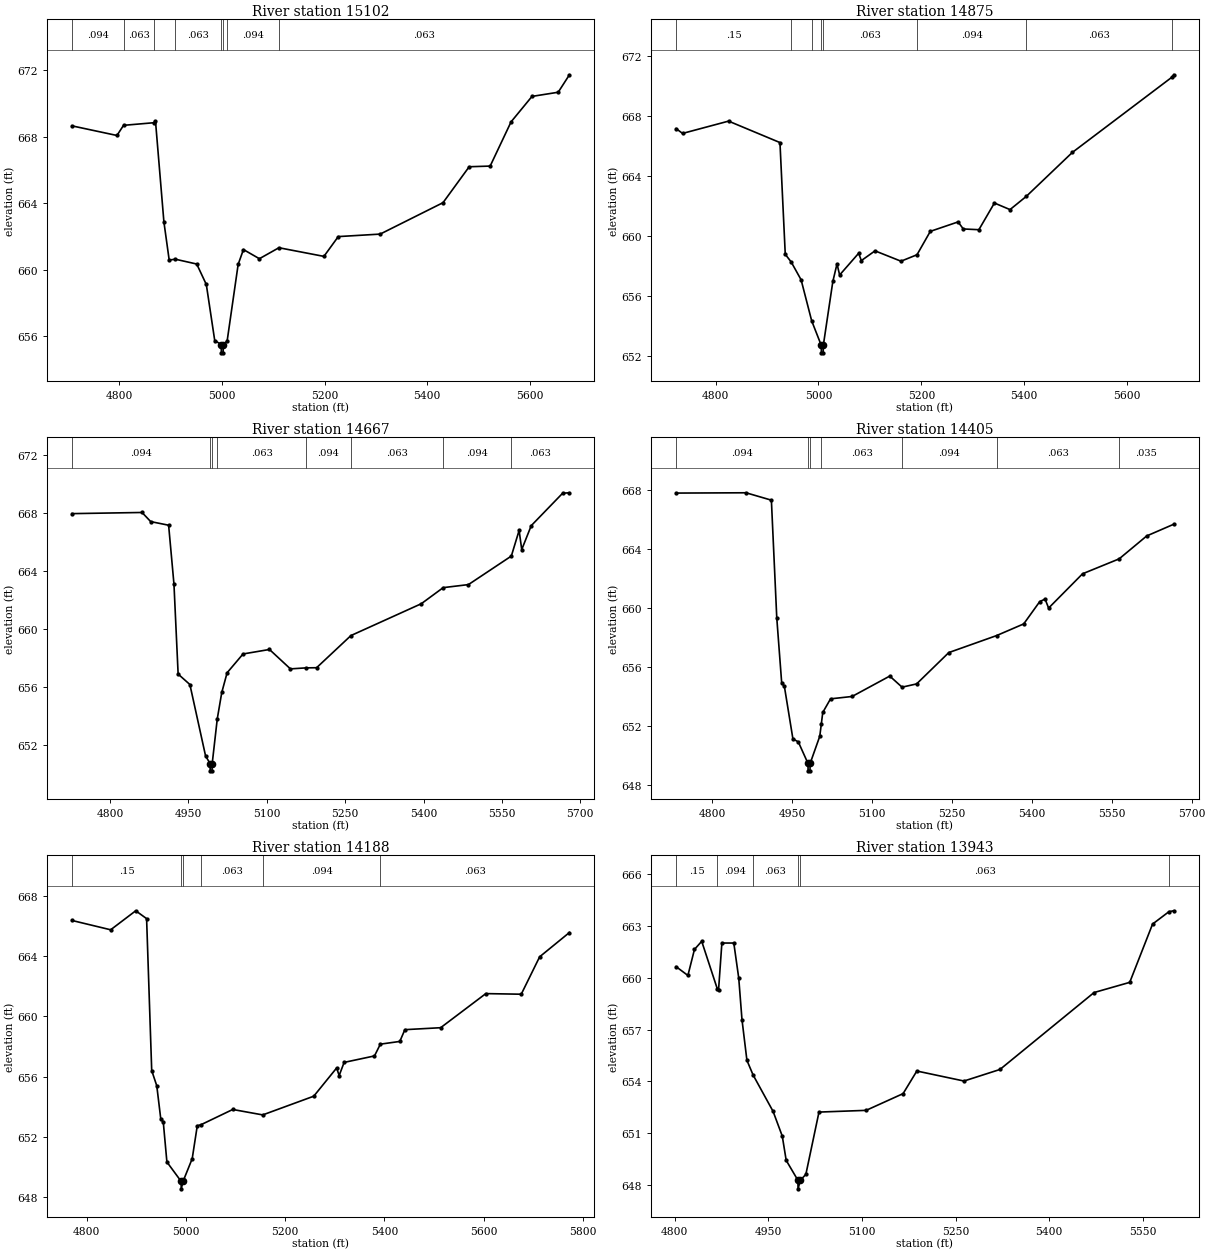
Type RM Length L Ch R = 1 ,15102   ,227,227,227
BEGIN DESCRIPTION:
B19810
END DESCRIPTION:
XS GIS Cut Line= 3
      2243758.44     13796768.47      2243866.14     13796361.99
       2243977.3     13795823.55
#Sta/Elev= 30
  4707.1  668.65    4795  668.07  4807.9  668.68  4868.1  668.84  4870.2  668.93
  4886.6  662.87  4896.9  660.58  4908.9  660.63  4950.6  660.34  4969.3  659.11
  4985.7  655.74  4998.4   655.5  4998.6     655  5002.1     655  5002.4   655.5
  5009.9  655.71  5031.4  660.32  5041.7  661.21  5072.8  660.66  5110.9  661.32
  5198.6   660.8  5226.6  661.99  5308.3  662.14  5430.9  664.03  5481.9  666.19
  5522.8  666.23  5563.6  668.89  5604.4  670.42  5655.5  670.67  5677.4  671.72
#Mann= 8 ,-1 , 0
  4707.1    .094       0  4807.9    .063       0  4868.1     .15       0
  4908.9    .063       0  4998.4     .05       0  5002.4    .063       0
  5009.9    .094       0  5110.9    .063       0
Bank Sta=4998.4,5002.4
XS Rating Curve= 0 ,0
Exp/Cntr=0.3,0.1

Type RM Length L Ch R = 1 ,14875   ,208,208,208
BEGIN DESCRIPTION:
B19811
END DESCRIPTION:
XS GIS Cut Line= 3
      2243966.88     13796841.42      2244053.73     13796476.63
      2244133.61     13795889.73
#Sta/Elev= 30
  4723.3  667.19  4735.9  666.87  4825.3  667.69  4925.2  666.26  4935.5  658.81
    4947   658.3  4966.3  657.11  4986.9  654.37  5005.5  652.74  5005.7  652.24
  5009.2  652.24  5009.5  652.74    5028     657  5036.1  658.17  5041.2  657.43
  5078.2  658.88  5083.4  658.39    5110  659.04  5160.5  658.35  5191.6  658.78
  5217.5  660.34  5271.5  660.97  5281.6   660.5  5311.9  660.45  5342.1  662.23
  5372.4  661.79    5404  662.67  5493.5   665.6    5688  670.64  5690.6  670.78
#Mann= 8 ,-1 , 0
  4723.3     .15       0    4947    .094       0  4986.9    .063       0
  5005.5     .05       0  5009.5    .063       0  5191.6    .094       0
    5404    .063       0    5688    .035       0
Bank Sta=5005.5,5009.5
XS Rating Curve= 0 ,0
Exp/Cntr=0.3,0.1

Type RM Length L Ch R = 1 ,14667   ,262,262,262
BEGIN DESCRIPTION:
B19812
END DESCRIPTION:
XS GIS Cut Line= 3
      2244171.85     13796896.99      2244237.85     13796546.11
      2244276.07     13795952.07
#Sta/Elev= 30
  4726.8  667.96  4861.1  668.04  4877.7  667.41    4912  667.16  4922.2   663.1
  4930.2  656.88  4952.7  656.16  4982.7  651.23  4991.4   650.7  4991.6   650.2
  4995.1   650.2  4995.4   650.7  5005.1  653.79  5013.7  655.61  5023.9  656.97
  5054.4  658.27    5105  658.58  5145.1  657.24    5175  657.31  5195.2  657.32
  5260.9  659.54  5395.6  661.74  5437.5  662.85  5485.8  663.06  5567.9  665.03
  5582.8   666.8  5587.8  665.48    5606  667.13  5666.1  669.37  5679.1   669.4
#Mann= 8 ,-1 , 0
  4726.8    .094       0  4991.4     .05       0  4995.4    .094       0
  5005.1    .063       0    5175    .094       0  5260.9    .063       0
  5437.5    .094       0  5567.9    .063       0
Bank Sta=4991.4,4995.4
XS Rating Curve= 0 ,0
Exp/Cntr=0.3,0.1

Type RM Length L Ch R = 1 ,14405   ,217,217,217
BEGIN DESCRIPTION:
B19813
END DESCRIPTION:
XS GIS Cut Line= 3
       2244432.4     13796942.12       2244498.4     13796462.73
      2244460.19     13796014.57
#Sta/Elev= 30
  4732.6  667.78  4863.8   667.8  4911.4   667.3  4921.5  659.34  4930.7  654.95
  4935.8   654.7  4951.8  651.15  4961.9  650.95  4980.1  649.49  4980.3  648.99
  4983.8  648.99  4984.1  649.49  5002.2  651.33  5005.1  652.16  5007.8  652.94
  5022.4  653.86  5062.8  654.02  5133.5   655.4  5156.6  654.65  5183.9  654.87
  5244.3  656.99    5334  658.14  5384.9  658.93    5415  660.44    5425  660.61
  5431.6     660  5495.3  662.32    5564  663.33  5615.7  664.88  5666.3  665.67
#Mann= 7 ,-1 , 0
  4732.6    .094       0  4980.1     .05       0  4984.1    .094       0
  5005.1    .063       0  5156.6    .094       0    5334    .063       0
    5564    .035       0
Bank Sta=4980.1,4984.1
XS Rating Curve= 0 ,0
Exp/Cntr=0.3,0.1

Type RM Length L Ch R = 1 ,14188   ,245,245,245
BEGIN DESCRIPTION:
B19814
END DESCRIPTION:
XS GIS Cut Line= 3
      2244623.46     13796952.58      2244710.31     13796528.74
      2244821.42     13795969.72
#Sta/Elev= 30
  4770.2  666.35  4848.4  665.73  4898.9  666.99  4920.8  666.47  4931.1   656.4
  4941.3  655.39  4949.3  653.21  4954.4  652.99  4961.7  650.34  4990.3  649.06
  4990.6  648.56  4994.3  649.06  5012.7  650.56  5022.9  652.74  5030.4  652.81
  5094.4  653.82  5154.8  653.46  5257.6   654.7  5303.7  656.57  5308.8  656.07
  5318.8  656.94    5380  657.37  5391.8  658.15    5431  658.33  5441.2  659.11
  5513.3  659.24  5604.3   661.5  5675.7  661.46  5712.8  663.94  5772.8  665.55
#Mann= 6 ,-1 , 0
  4770.2     .15       0  4990.3     .05       0  4994.3     .15       0
  5030.4    .063       0  5154.8    .094       0  5391.8    .063       0
Bank Sta=4990.3,4994.3
XS Rating Curve= 0 ,0
Exp/Cntr=0.3,0.1

Type RM Length L Ch R = 1 ,13943   ,297,297,297
BEGIN DESCRIPTION:
B19815
END DESCRIPTION:
XS GIS Cut Line= 3
      2244838.84     13796963.03      2244956.97     13796591.27
      2245033.39     13796191.79
#Sta/Elev= 30
  4802.5  660.65  4821.4  660.14  4831.9  661.65  4843.5  662.12  4868.7  659.34
  4870.5  659.31  4875.8  662.02  4894.9  662.02  4902.8  659.99    4908  657.58
  4915.9  655.22  4925.8  654.37  4957.8  652.26  4972.5  650.83  4978.8  649.42
  4997.5  648.27  4997.8  647.77  5001.5  648.27  5010.3  648.61  5031.3  652.22
  5106.8  652.32    5166  653.29    5188   654.6  5263.5  654.02  5321.1  654.69
  5471.8  659.15  5528.9  659.74  5565.5  663.12  5591.8  663.84  5599.3  663.89
#Mann= 6 ,-1 , 0
  4802.5     .15       0  4868.7    .094       0  4925.8    .063       0
  4997.5     .05       0  5001.5    .063       0  5591.8    .094       0
Bank Sta=4997.5,5001.5
XS Rating Curve= 0 ,0
Exp/Cntr=0.3,0.1

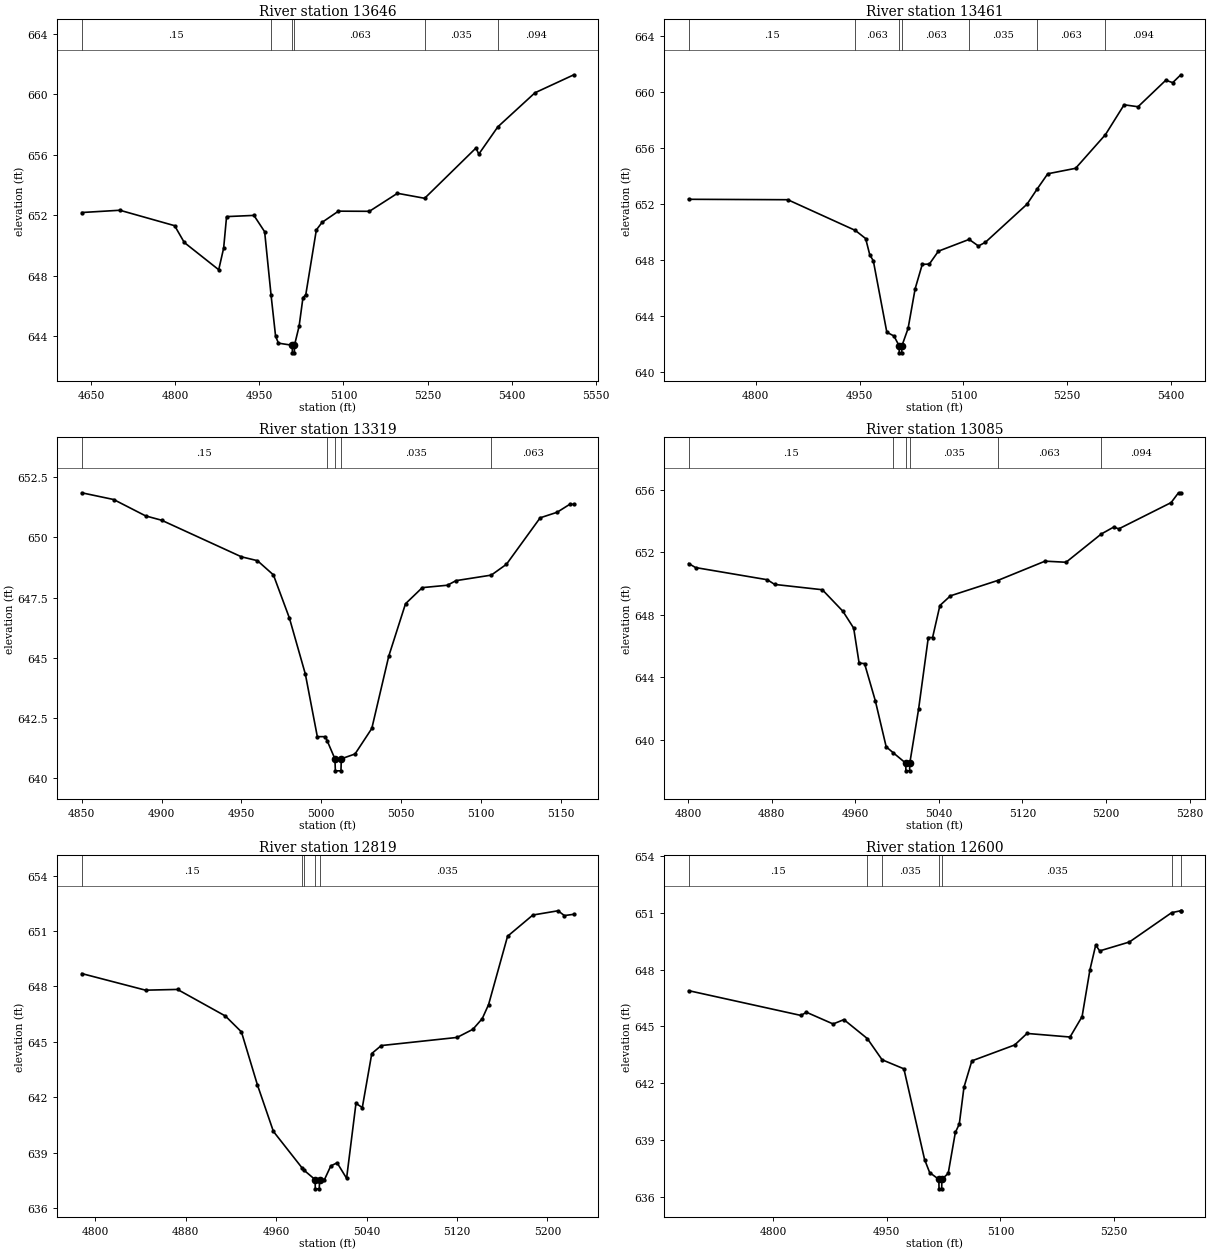
Type RM Length L Ch R = 1 ,13646   ,185,185,185
BEGIN DESCRIPTION:
B19816
END DESCRIPTION:
XS GIS Cut Line= 3
       2245245.3      13797143.6      2245148.03     13796702.43
      2245234.89     13796285.54
#Sta/Elev= 30
  4633.3  652.19  4701.4  652.34    4799  651.32  4816.2  650.21  4877.6  648.41
  4886.4  649.84  4891.6  651.92  4940.4     652  4959.5  650.92  4970.9  646.75
    4979  644.02  4984.1  643.56  5008.7  643.42    5009  642.92  5012.5  642.92
  5012.7  643.42    5021  644.69  5027.8  646.56  5032.9  646.77  5051.7  651.04
  5061.9  651.54  5091.1  652.28  5146.3  652.27  5196.3  653.46  5244.8  653.13
  5336.3  656.45  5341.4  656.05  5375.3  657.85  5441.5   660.1  5510.9  661.29
#Mann= 6 ,-1 , 0
  4633.3     .15       0  4970.9    .063       0  5008.7     .05       0
  5012.7    .063       0  5244.8    .035       0  5375.3    .094       0
Bank Sta=5008.7,5012.7
XS Rating Curve= 0 ,0
Exp/Cntr=0.3,0.1

Type RM Length L Ch R = 1 ,13461   ,142,142,142
BEGIN DESCRIPTION:
B19817
END DESCRIPTION:
XS GIS Cut Line= 3
      2245394.68     13797015.06      2245314.79      13796639.9
       2245339.1     13796313.37
#Sta/Elev= 30
  4703.1  652.34  4846.3  652.31  4943.9  650.12  4958.8  649.54  4964.7  648.39
  4969.9  647.95  4989.4  642.86  4999.7  642.59  5007.2  641.89  5007.4  641.39
  5010.9  641.39  5011.2  641.89  5020.1  643.13  5030.3  645.96  5040.6   647.7
  5050.8  647.72  5063.9  648.64  5108.3  649.48  5121.7  649.01  5131.7  649.27
  5191.9  651.99  5206.8  653.09  5221.9  654.16  5262.1  654.55  5305.2  656.95
  5332.2  659.08  5352.3  658.94  5392.4  660.83  5402.4  660.66  5414.1  661.22
#Mann= 7 ,-1 , 0
  4703.1     .15       0  4943.9    .063       0  5007.2     .05       0
  5011.2    .063       0  5108.3    .035       0  5206.8    .063       0
  5305.2    .094       0
Bank Sta=5007.2,5011.2
XS Rating Curve= 0 ,0
Exp/Cntr=0.3,0.1

Type RM Length L Ch R = 1 ,13319   ,234,234,234
BEGIN DESCRIPTION:
North Guadalupe Tributary 28.0
END DESCRIPTION:
XS GIS Cut Line= 3
        2245475.     13796874.99        2245475.       13796725.
        2245525.       13796575.
#Sta/Elev= 29
    4850  651.85    4870  651.57    4890  650.89    4900  650.71    4950  649.19
    4960  649.03    4970  648.44    4980  646.65    4990  644.32  4997.5  641.72
  5002.6  641.72  5003.6  641.56  5008.5   640.8  5008.8   640.3  5012.3   640.3
  5012.5   640.8  5021.1     641  5031.6  642.06  5042.2  645.06  5052.7  647.24
  5063.2  647.91    5079  648.01  5084.3   648.2  5106.4  648.43  5115.9  648.88
    5137  650.81  5147.6  651.04  5155.5  651.37  5158.1  651.37
#Mann= 5 ,-1 , 0
    4850     .15       0  5003.6    .035       0  5008.5     .05       0
  5012.5    .035       0  5106.4    .063       0
Bank Sta=5008.5,5012.5
XS Rating Curve= 0 ,0
Exp/Cntr=0.3,0.1

Type RM Length L Ch R = 1 ,13085   ,266,266,266
BEGIN DESCRIPTION:
B19818
END DESCRIPTION:
XS GIS Cut Line= 3
      2245658.71      13796917.8      2245717.77     13796692.01
      2245693.44     13796455.74
#Sta/Elev= 30
  4800.7  651.28  4807.3  651.02    4876  650.24    4883  649.94  4928.6   649.6
  4948.3  648.22  4958.6  647.14  4963.8   644.9    4969  644.87  4979.3  642.49
  4989.7  639.54  4996.4  639.16  5008.3   638.5  5008.6     638  5012.1     638
  5012.3   638.5  5020.7  641.95    5030  646.54  5034.1  646.54  5041.1  648.59
  5051.2  649.21  5096.3  650.19  5141.7  651.43  5161.8  651.36  5195.5  653.17
  5207.3  653.61  5212.3   653.5  5262.3  655.18  5269.4  655.81  5271.6  655.81
#Mann= 6 ,-1 , 0
  4800.7     .15       0  4996.4    .035       0  5008.3    .035       0
  5012.3    .035       0  5096.3    .063       0  5195.5    .094       0
Bank Sta=5008.3,5012.3
XS Rating Curve= 0 ,0
Exp/Cntr=0.3,0.1

Type RM Length L Ch R = 1 ,12819   ,219,219,219
BEGIN DESCRIPTION:
North Guadalupe Tributary 27.0
END DESCRIPTION:
XS GIS Cut Line= 3
      2245825.02     13796874.98        2245975.       13796725.
        2245875.       13796525.
#Sta/Elev= 30
  4787.8   648.7  4844.3   647.8  4872.6  647.84    4915   646.4  4929.2  645.54
  4943.3  642.68  4957.5  640.15  4982.8  638.18  4984.2  638.07  4994.4  637.54
  4994.6  637.04  4998.1  637.04  4998.4  637.54  5002.7  637.54  5008.3  638.28
  5013.9  638.45  5022.3  637.61  5030.6  641.67  5036.2  641.44  5044.6  644.37
    5053   644.8  5120.1  645.24  5134.1  645.68  5142.4  646.26    5148  647.02
  5164.8  650.72  5187.2  651.87  5209.5   652.1  5215.1  651.84  5223.5  651.91
#Mann= 5 ,-1 , 0
  4787.8     .15       0  4982.8    .094       0  4984.2    .035       0
  4994.4    .035       0  4998.4    .035       0
Bank Sta=4994.4,4998.4
XS Rating Curve= 0 ,0
Exp/Cntr=0.3,0.1

Type RM Length L Ch R = 1 ,12600   ,229,229,229
BEGIN DESCRIPTION:
B19819
END DESCRIPTION:
XS GIS Cut Line= 3
      2245978.35     13797008.11      2246165.91     13796817.08
       2246269.9     13796449.63
#Sta/Elev= 30
  4688.5  646.89  4836.8  645.58  4843.9  645.75  4879.2  645.13  4893.4  645.36
  4924.3  644.36  4943.8  643.24  4972.6  642.76  4999.9  637.97  5006.6  637.28
  5018.7  636.92    5019  636.42  5022.5  636.42  5022.7  636.92  5031.1  637.24
  5040.5   639.4  5045.7  639.84  5051.9  641.79  5062.3  643.18  5118.8  644.02
  5135.1  644.63  5191.9  644.44  5207.8  645.52  5218.2     648  5225.8   649.3
    5231  648.99  5270.2  649.46    5326  651.01  5337.8  651.11  5338.1  651.11
#Mann= 7 ,-1 , 0
  4688.5     .15       0  4924.3    .094       0  4943.8    .035       0
  5018.7    .035       0  5022.7    .035       0    5326    .063       0
  5337.8    .094       0
Bank Sta=5018.7,5022.7
XS Rating Curve= 0 ,0
Exp/Cntr=0.3,0.1

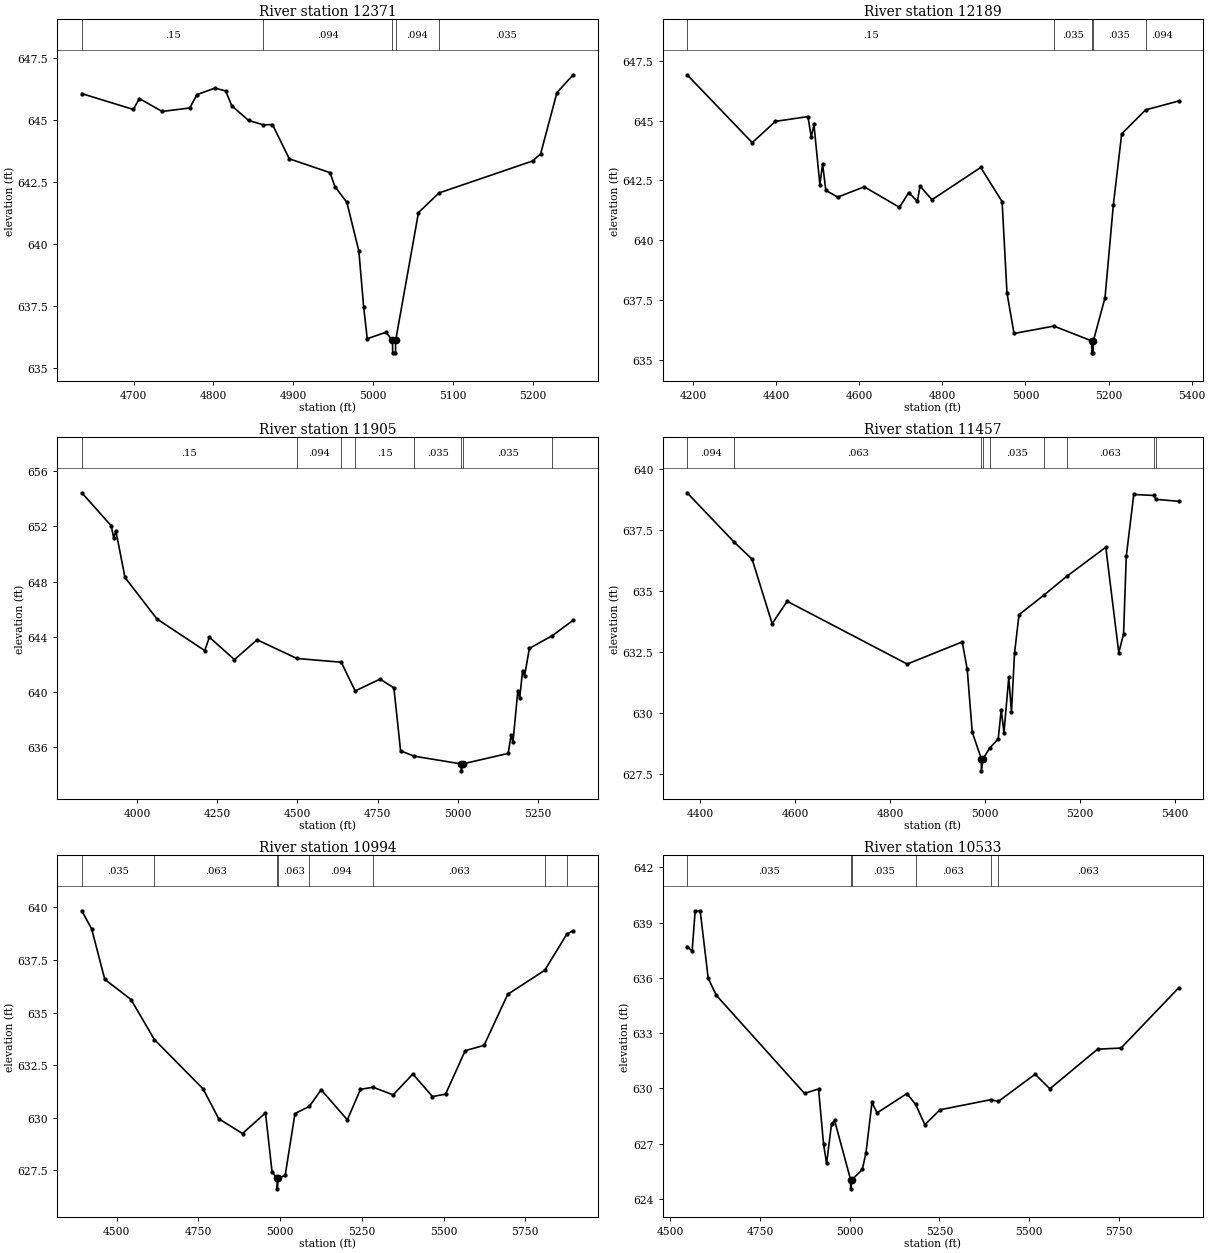
Type RM Length L Ch R = 1 ,12371   ,182,182,182
BEGIN DESCRIPTION:
North Guadalupe Tributary 26.0
END DESCRIPTION:
XS GIS Cut Line= 3
      2246075.03     13797074.98        2246375.       13796875.
      2246425.01     13796624.97
#Sta/Elev= 30
  4635.2  646.07  4699.8  645.43  4707.3  645.87  4735.8  645.35  4770.4  645.49
  4779.4  646.03  4801.9  646.29  4815.4  646.18    4823  645.58    4844  644.99
  4862.5  644.81    4874  644.82  4895.1  643.44  4946.1  642.88  4952.2  642.32
  4967.2  641.68  4982.2  639.72  4988.2  637.47  4992.7  636.18  5016.1  636.44
  5024.3  636.11  5024.6  635.61  5028.1  635.61  5028.3  636.11  5056.9  641.27
  5082.5  642.06  5199.7  643.35  5209.9  643.64  5230.3  646.11  5250.7  646.83
#Mann= 5 ,-1 , 0
  4635.2     .15       0  4862.5    .094       0  5024.3     .05       0
  5028.3    .094       0  5082.5    .035       0
Bank Sta=5024.3,5028.3
XS Rating Curve= 0 ,0
Exp/Cntr=0.3,0.1

Type RM Length L Ch R = 1 ,12189   ,284,284,284
BEGIN DESCRIPTION:
B19820
END DESCRIPTION:
XS GIS Cut Line= 4
      2245953.99     13797473.66      2246495.94     13797025.51
      2246596.68     13796799.71      2246582.88     13796568.51
#Sta/Elev= 30
  4186.2  646.92  4342.8  644.08  4398.8  644.97  4476.9  645.17  4484.8  644.31
  4491.3  644.84  4505.6  642.32  4512.1  643.18  4519.9  642.08  4548.6   641.8
  4612.4  642.23  4697.1  641.37  4719.3  641.99  4740.1  641.62  4746.6  642.26
  4775.2  641.69  4892.5  643.04  4943.9  641.61  4955.7  637.78  4972.6  636.09
  5068.5   636.4  5159.4  635.78  5159.7  635.28  5163.2  635.28  5163.4  635.78
  5191.5  637.59  5211.5  641.47  5231.6  644.45  5289.2  645.45  5368.3  645.82
#Mann= 5 ,-1 , 0
  4186.2     .15       0  5068.5    .035       0  5159.4     .05       0
  5163.4    .035       0  5289.2    .094       0
Bank Sta=5159.4,5163.4
XS Rating Curve= 0 ,0
Exp/Cntr=0.3,0.1

Type RM Length L Ch R = 1 ,11905   ,448,448,448
BEGIN DESCRIPTION:
North Guadalupe Tributary 25.0
END DESCRIPTION:
XS GIS Cut Line= 3
        2245925.       13797675.        2246825.       13796925.
      2246624.99     13796624.99
#Sta/Elev= 30
    3828  654.42  3919.8  652.03  3927.6  651.14  3934.1  651.68  3962.7  648.29
  4062.3  645.29  4211.4     643  4225.7  643.97  4303.8  642.35  4374.7  643.78
  4498.6  642.43  4636.8  642.16  4680.4  640.08  4758.1  640.94    4801   640.3
  4821.9  635.75  4864.4  635.36  5011.1   634.8  5011.3   634.3  5015.1   634.8
  5157.3  635.56  5166.3  636.87  5172.3  636.38  5187.3  640.07  5193.3  639.56
  5202.3  641.56  5208.4  641.17  5223.4  643.16  5295.5  644.09  5360.1   645.2
#Mann= 8 ,-1 , 0
    3828     .15       0  4498.6    .094       0  4636.8    .063       0
  4680.4     .15       0  4864.4    .035       0  5011.1    .035       0
  5015.1    .035       0  5295.5    .094       0
Bank Sta=5011.1,5015.1
XS Rating Curve= 0 ,0
Exp/Cntr=0.3,0.1

Type RM Length L Ch R = 1 ,11457   ,463,463,463
BEGIN DESCRIPTION:
North Guadalupe Tributary 24.0
END DESCRIPTION:
XS GIS Cut Line= 3
      2247025.01     13797574.98        2247225.       13796975.
      2247025.02     13796625.04
#Sta/Elev= 30
  4372.1  639.04  4471.4  637.01  4509.1  636.31  4551.3  633.66  4582.9  634.58
  4835.9     632  4951.8  632.91  4962.4  631.78  4972.9   629.2    4992  628.11
  4992.2  627.61    4996  628.11  5009.8  628.55  5027.6  628.92    5034  630.12
  5039.8  629.18  5049.9  631.45  5055.6  630.03  5062.1  632.46  5071.5  634.03
  5125.1  634.85  5171.7   635.6  5254.3   636.8  5281.7  632.47  5291.8  633.24
  5297.5  636.43  5313.3  638.97  5355.7  638.93  5360.4  638.77  5407.6  638.69
#Mann= 9 ,-1 , 0
  4372.1    .094       0  4471.4    .063       0    4992     .05       0
    4996    .063       0  5009.8    .035       0  5125.1    .094       0
  5171.7    .063       0  5355.7    .035       0  5360.4    .094       0
Bank Sta=4992,4996
XS Rating Curve= 0 ,0
Exp/Cntr=0.3,0.1

Type RM Length L Ch R = 1 ,10994   ,461,461,461
BEGIN DESCRIPTION:
North Guadalupe Tributary 23.0
END DESCRIPTION:
XS GIS Cut Line= 3
        2247575.     13797775.04        2247625.       13797175.
        2247675.     13796275.01
#Sta/Elev= 30
    4393  639.84  4423.1  638.98  4463.3  636.58  4543.6  635.62  4614.9  633.72
  4764.3  631.37    4812  629.95  4884.7  629.25    4955  630.23  4975.1  627.42
  4990.6  627.12  4990.9  626.62  4994.6  627.12  5015.2  627.26  5045.2   630.2
  5089.2  630.54  5125.3  631.33  5205.4   629.9  5245.5  631.35    5284  631.45
  5345.7  631.09  5405.8  632.08  5465.8  631.01  5505.9  631.12    5566  633.19
  5623.6  633.44  5696.2  635.87  5809.3  637.01  5876.5  638.72  5896.5   638.9
#Mann= 8 ,-1 , 0
    4393    .035       0  4614.9    .063       0  4990.6     .05       0
  4994.6    .063       0  5089.2    .094       0    5284    .063       0
  5809.3    .094       0  5876.5    .035       0
Bank Sta=4990.6,4994.6
XS Rating Curve= 0 ,0
Exp/Cntr=0.3,0.1

Type RM Length L Ch R = 1 ,10533   ,446,446,446
BEGIN DESCRIPTION:
North Guadalupe Tributary 22.0
END DESCRIPTION:
XS GIS Cut Line= 3
      2247824.98     13797775.03        2248025.       13797375.
        2247825.       13796475.
#Sta/Elev= 30
    4547   637.7    4561  637.45  4569.4  639.61  4583.4  639.64  4605.7  635.99
  4628.1  635.06  4874.1  629.73  4913.2  629.97  4927.2  626.97  4935.6  625.93
  4949.5  628.09  4957.9  628.26  5002.5  625.05  5002.7  624.55  5006.5  625.05
  5035.2   625.6  5045.5  626.52  5062.1  629.24  5076.2  628.67  5159.4  629.72
  5183.8  629.13  5209.4  628.03  5251.6  628.84  5393.4  629.39    5414  629.29
  5516.7  630.77  5557.7  629.98  5690.8  632.13  5756.1  632.19  5916.2  635.45
#Mann= 6 ,-1 , 0
    4547    .035       0  5002.5    .035       0  5006.5    .035       0
  5183.8    .063       0  5393.4    .094       0    5414    .063       0
Bank Sta=5002.5,5006.5
XS Rating Curve= 0 ,0
Exp/Cntr=0.3,0.1

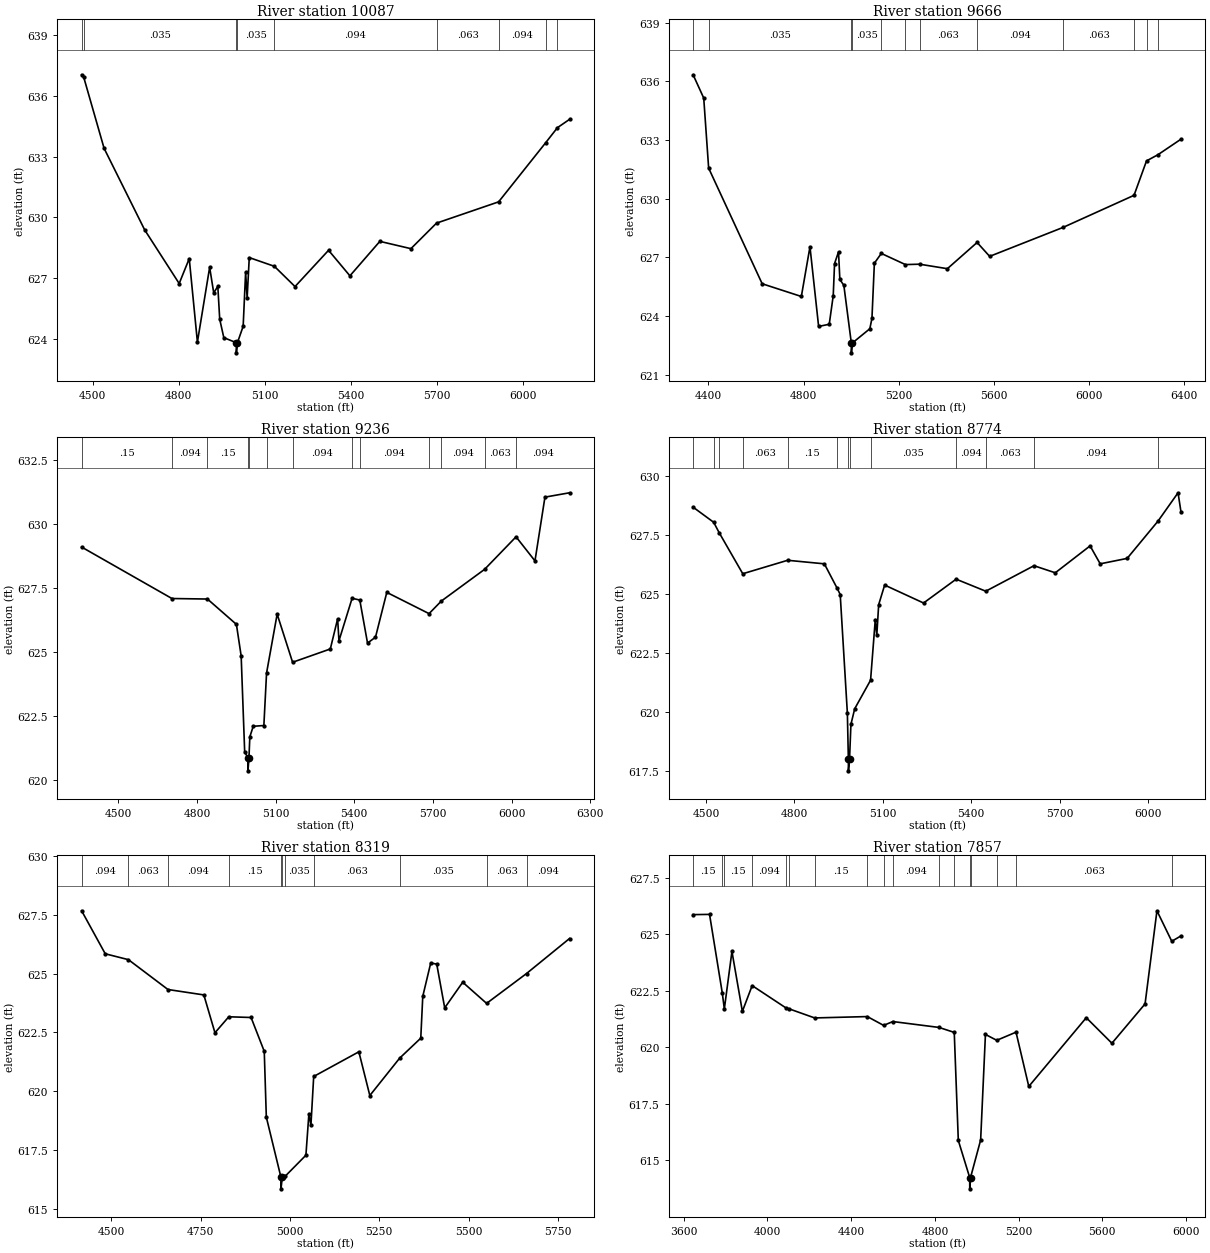
Type RM Length L Ch R = 1 ,10087   ,421,421,421
BEGIN DESCRIPTION:
North Guadalupe Tributary 21.0
END DESCRIPTION:
XS GIS Cut Line= 3
      2248024.96     13797875.03        2248425.       13797525.
      2248025.01     13796425.02
#Sta/Elev= 30
  4461.9  637.04    4469  636.93  4540.3  633.41  4681.7  629.39  4802.2  626.74
  4837.3  627.97  4865.8  623.85  4908.5  627.54  4922.7  626.28    4937   626.6
  4943.6  624.98  4957.9  624.07  5001.4  623.82  5001.7  623.32  5005.4  623.82
  5025.4  624.63    5034   627.3  5039.3  626.03  5046.7  628.02  5134.2  627.59
  5206.3  626.59  5323.3  628.38  5397.8  627.12  5502.2  628.82  5610.6  628.46
  5699.9  629.72  5916.5  630.77  6080.8  633.69  6121.7  634.43  6163.9  634.84
#Mann= 9 ,-1 , 0
  4461.9    .094       0    4469    .035       0  5001.4    .035       0
  5005.4    .035       0  5134.2    .094       0  5699.9    .063       0
  5916.5    .094       0  6080.8    .063       0  6121.7    .094       0
Bank Sta=5001.4,5005.4
XS Rating Curve= 0 ,0
Exp/Cntr=0.3,0.1

Type RM Length L Ch R = 1 ,9666    ,430,430,430
BEGIN DESCRIPTION:
North Guadalupe Tributary 20.0
END DESCRIPTION:
XS GIS Cut Line= 3
      2248174.99       13798025.        2248775.       13797725.
      2248474.99     13796374.96
#Sta/Elev= 30
  4335.3  636.33    4380  635.14  4400.7  631.56    4626  625.65  4790.9     625
  4827.2  627.54  4863.6  623.47  4908.3  623.58  4925.1  625.04  4930.7  626.68
  4947.4  627.28    4953  625.87  4969.8  625.57  5001.3  622.62  5001.6  622.12
  5005.3  622.62  5079.1  623.35  5088.1  623.88  5098.3   626.7  5127.5   627.2
    5229  626.63  5288.6  626.65  5405.6  626.42  5530.7  627.76  5583.6  627.05
  5892.6  628.53  6191.3  630.17  6243.9  631.93  6291.4  632.24  6389.1  633.04
#Mann= 12 ,-1 , 0
  4335.3     .15       0  4400.7    .035       0  5001.3    .035       0
  5005.3    .035       0  5127.5    .063       0    5229    .094       0
  5288.6    .063       0  5530.7    .094       0  5892.6    .063       0
  6191.3    .094       0  6243.9    .063       0  6291.4    .094       0
Bank Sta=5001.3,5005.3
XS Rating Curve= 0 ,0
Exp/Cntr=0.3,0.1

Type RM Length L Ch R = 1 ,9236    ,462,462,462
BEGIN DESCRIPTION:
North Guadalupe Tributary 19.0
END DESCRIPTION:
XS GIS Cut Line= 3
      2248826.96     13798446.39        2249125.       13797875.
        2249325.       13796675.
#Sta/Elev= 30
  4360.1  629.09  4704.6  627.08    4840  627.06  4950.5  626.07  4968.6  624.84
    4982   621.1  4994.3  620.85  4994.6  620.35  4998.3  620.85  5001.7  621.68
  5014.7  622.09  5055.2  622.12  5065.5  624.17  5105.9  626.47  5164.8  624.59
  5308.7  625.11  5336.6  626.29  5341.6  625.43  5391.8  627.09  5421.1  627.02
  5450.6  625.34    5481  625.57  5524.1  627.32  5685.3  626.49    5732  626.98
  5897.2  628.22  6017.1  629.49  6089.3  628.55  6127.3  631.04  6221.1  631.21
#Mann= 13 ,-1 , 0
  4360.1     .15       0  4704.6    .094       0    4840     .15       0
  4994.3     .05       0  4998.3     .15       0  5065.5    .063       0
  5164.8    .094       0  5391.8    .063       0  5421.1    .094       0
  5685.3    .063       0    5732    .094       0  5897.2    .063       0
  6017.1    .094       0
Bank Sta=4994.3,4998.3
XS Rating Curve= 0 ,0
Exp/Cntr=0.3,0.1

Type RM Length L Ch R = 1 ,8774    ,455,455,455
BEGIN DESCRIPTION:
North Guadalupe Tributary 18.0
END DESCRIPTION:
XS GIS Cut Line= 3
      2249325.01     13798574.97        2249525.       13798075.
        2249325.     13796975.02
#Sta/Elev= 30
  4455.9  628.66  4525.7  628.02  4544.3  627.58  4624.5  625.84  4776.9  626.41
  4901.5  626.26  4944.7  625.23  4955.3  624.96  4979.6  619.94    4983  617.99
  4983.2  617.49    4987  617.99  4991.7  619.46  5004.5  620.12  5058.4  621.33
  5074.4   623.9  5079.5  623.23  5085.9  624.53  5106.2  625.36  5238.3   624.6
  5348.9  625.61  5449.5   625.1  5613.2  626.18  5685.5  625.88  5803.7  627.02
    5838  626.26  5929.5  626.49  6034.3  628.07  6102.3  629.27  6112.4  628.45
#Mann= 13 ,-1 , 0
  4455.9    .094       0  4525.7    .063       0  4544.3    .094       0
  4624.5    .063       0  4776.9     .15       0  4944.7    .063       0
    4983     .05       0    4987    .063       0  5058.4    .035       0
  5348.9    .094       0  5449.5    .063       0  5613.2    .094       0
  6034.3    .063       0
Bank Sta=4983,4987
XS Rating Curve= 0 ,0
Exp/Cntr=0.3,0.1

Type RM Length L Ch R = 1 ,8319    ,462,462,462
BEGIN DESCRIPTION:
North Guadalupe Tributary 17.0
END DESCRIPTION:
XS GIS Cut Line= 3
      2249424.99     13798525.01        2249925.       13798225.
      2249575.01     13797525.03
#Sta/Elev= 30
  4416.9  627.67    4483  625.84  4547.9  625.59  4658.6  624.32    4759  624.09
  4790.1  622.48  4828.8  623.16  4891.2  623.13  4928.1  621.69  4933.9  618.89
  4974.7  616.34  4974.9  615.84  4978.7  616.34  4986.9  616.38  5044.7  617.27
  5053.1  619.04  5058.7  618.54  5066.5  620.62  5192.9  621.67  5223.6  619.81
  5307.1   621.4  5366.2  622.25  5371.8  624.03  5394.1  625.45  5410.9   625.4
  5433.2  623.54  5483.6  624.63  5550.5  623.73  5662.2     625  5782.6  626.49
#Mann= 11 ,-1 , 0
  4416.9    .094       0  4547.9    .063       0  4658.6    .094       0
  4828.8     .15       0  4974.7    .035       0  4978.7     .15       0
  4986.9    .035       0  5066.5    .063       0  5307.1    .035       0
  5550.5    .063       0  5662.2    .094       0
Bank Sta=4974.7,4978.7
XS Rating Curve= 0 ,0
Exp/Cntr=0.3,0.1

Type RM Length L Ch R = 1 ,7857    ,448,448,448
BEGIN DESCRIPTION:
North Guadalupe Tributary 16.0
END DESCRIPTION:
XS GIS Cut Line= 3
      2249274.99     13799075.01        2250375.       13798275.
      2249824.99     13797474.99
#Sta/Elev= 30
  3644.8  625.87  3723.3  625.88  3783.9  622.42    3794   621.7  3830.3  624.24
  3880.1  621.59  3926.9  622.73  4088.8  621.74    4101  621.71  4225.5   621.3
  4477.2  621.36    4555  620.97    4599  621.14  4819.4  620.88  4892.4  620.66
  4911.8  615.88  4966.2  614.24  4966.5  613.74  4970.2  614.24  5018.5   615.9
  5041.4  620.57  5095.5  620.31  5187.5  620.67  5248.5  618.27  5523.2  621.31
  5645.6  620.18    5804  621.92  5860.8  626.04  5931.6  624.69  5975.8  624.93
#Mann= 17 ,-1 , 0
  3644.8     .15       0  3783.9    .094       0    3794     .15       0
  3926.9    .094       0  4088.8     .15       0    4101    .094       0
  4225.5     .15       0  4477.2    .094       0    4555     .15       0
    4599    .094       0  4819.4     .15       0  4892.4    .063       0
  4966.2     .05       0  4970.2    .063       0  5095.5    .035       0
  5187.5    .063       0  5931.6    .094       0
Bank Sta=4966.2,4970.2
XS Rating Curve= 0 ,0
Exp/Cntr=0.3,0.1