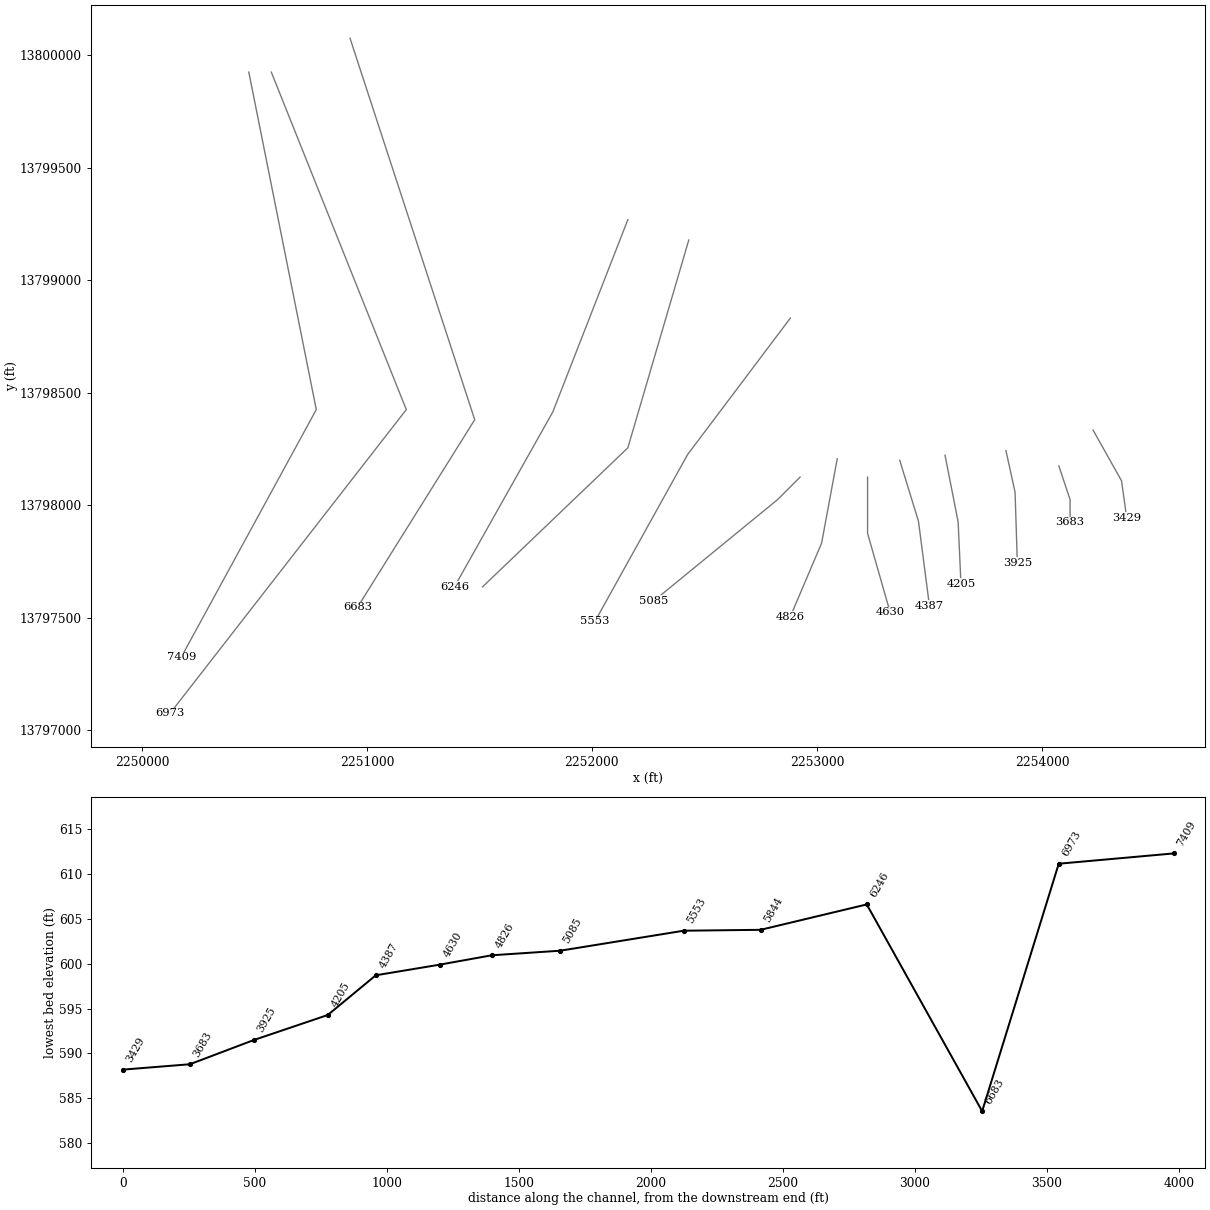
HEC-RAS study North Guadalupe Tributary.prj: North Guadalupe Tributary Base Level Engineering

--- North Guadalupe Tributary.g01 (geometry) --- (continued)

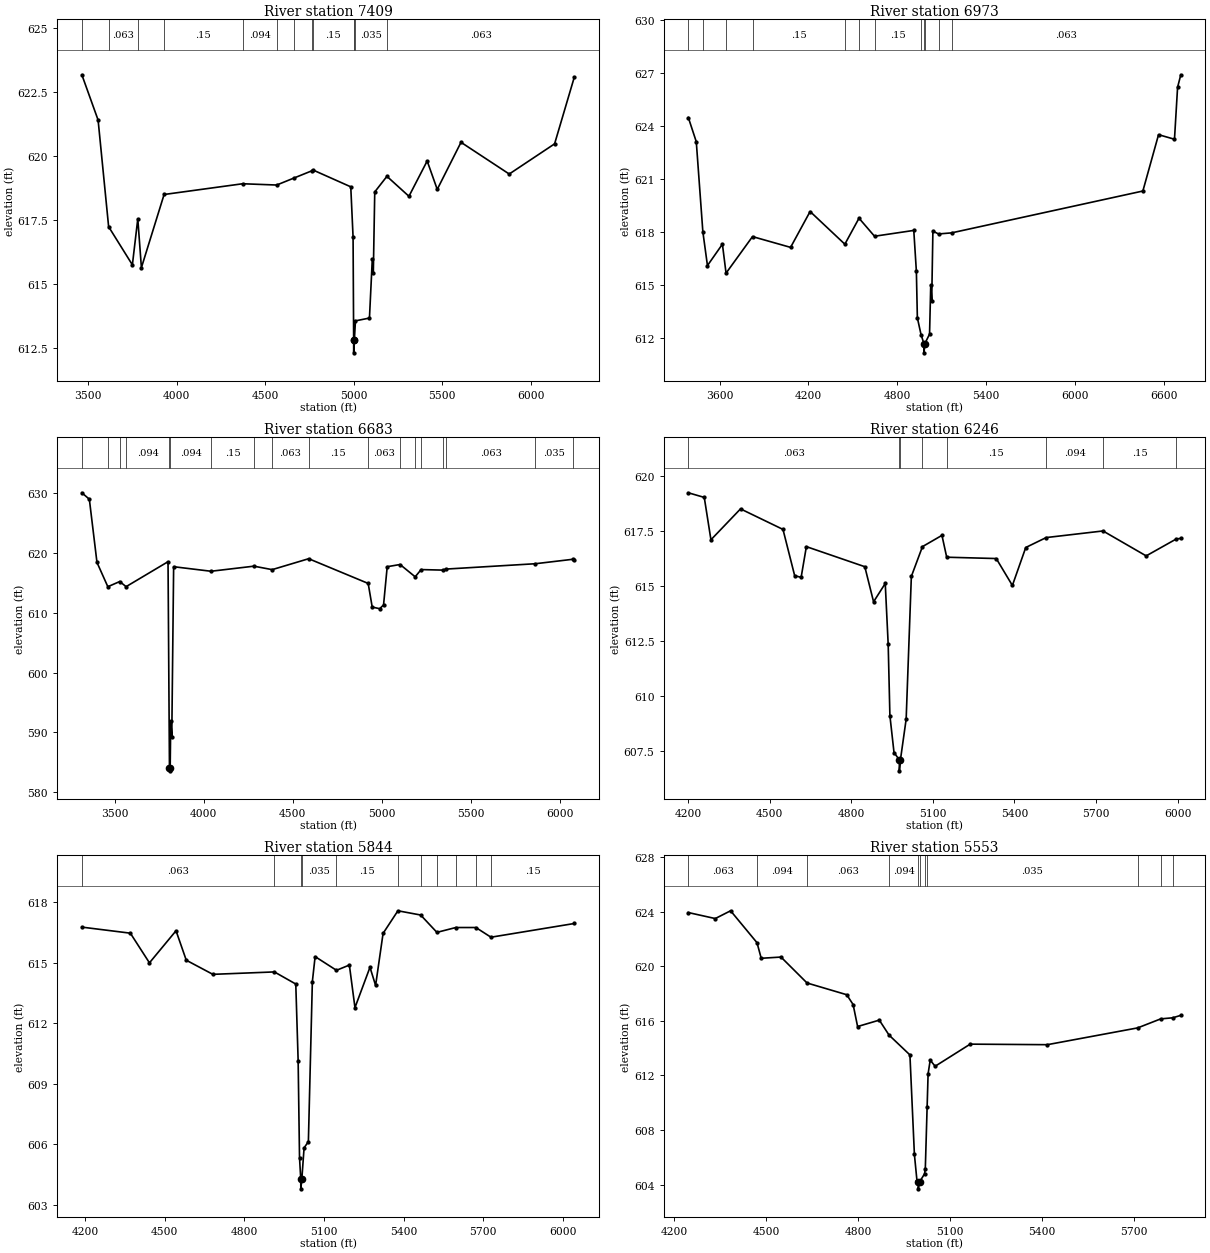
Type RM Length L Ch R = 1 ,7409    ,436,436,436
BEGIN DESCRIPTION:
North Guadalupe Tributary 15.0
END DESCRIPTION:
XS GIS Cut Line= 3
        2250475.     13799924.99        2250775.       13798425.
        2250175.       13797325.
#Sta/Elev= 30
  3463.4  623.18  3555.2  621.41  3614.7  617.24  3748.9  615.75  3779.5  617.55
  3799.9  615.64  3928.1   618.5    4372  618.92  4564.4  618.87  4664.2  619.15
  4764.5  619.43  4768.6  619.46  4982.9   618.8  4995.9  616.84  4999.2  612.81
  4999.4  612.31  5003.2  612.81  5009.3  613.56  5088.5  613.67  5104.6  615.98
  5110.3  615.43  5118.4   618.6  5187.2  619.21  5311.6  618.43  5414.6  619.81
  5471.5   618.7  5605.8  620.54  5878.3   619.3  6134.6  620.48  6246.1  623.09
#Mann= 13 ,-1 , 0
  3463.4    .094       0  3614.7    .063       0  3779.5    .094       0
  3928.1     .15       0    4372    .094       0  4564.4    .063       0
  4664.2     .15       0  4764.5    .094       0  4768.6     .15       0
  4999.2     .05       0  5003.2     .15       0  5009.3    .035       0
  5187.2    .063       0
Bank Sta=4999.2,5003.2
XS Rating Curve= 0 ,0
Exp/Cntr=0.3,0.1

Type RM Length L Ch R = 1 ,6973    ,290,290,290
BEGIN DESCRIPTION:
North Guadalupe Tributary 14.0
END DESCRIPTION:
XS GIS Cut Line= 3
      2250575.02     13799924.96        2251175.       13798425.
      2250124.98     13797074.97
#Sta/Elev= 30
  3388.6  624.48  3442.4  623.11  3486.8  618.01  3517.8   616.1  3618.8  617.31
  3643.4  615.67  3822.1  617.74  4079.2  617.13  4211.1  619.16  4445.7  617.31
  4541.3  618.78  4646.1  617.76  4911.2  618.09  4928.7  615.78  4935.4  613.14
  4960.3  612.19  4980.6  611.66  4980.8  611.16  4984.6  611.66  5017.7  612.22
  5025.8  615.01  5032.2  614.09  5040.3  618.05  5078.4  617.89    5166  617.95
  6458.3  620.32  6564.2  623.51  6671.8  623.25  6692.7  626.19  6714.4   626.9
#Mann= 12 ,-1 , 0
  3388.6    .094       0  3486.8    .063       0  3643.4    .094       0
  3822.1     .15       0  4445.7    .063       0  4541.3    .094       0
  4646.1     .15       0  4960.3    .063       0  4980.6     .05       0
  4984.6    .063       0  5078.4     .15       0    5166    .063       0
Bank Sta=4980.6,4984.6
XS Rating Curve= 0 ,0
Exp/Cntr=0.3,0.1

Type RM Length L Ch R = 1 ,6683    ,437,437,437
BEGIN DESCRIPTION:
North Guadalupe Tributary 13.0
END DESCRIPTION:
XS GIS Cut Line= 3
        2250925.       13800075.      2251479.05     13798380.18
      2250958.21     13797546.84
#Sta/Elev= 30
  3316.4  630.12  3358.5  629.04  3401.3  618.46  3462.3  614.39  3529.2  615.26
  3564.9   614.4  3800.4  618.58  3808.4  584.06  3808.7  583.56  3812.4  584.06
  3815.7  591.95  3821.4  589.25  3831.9  617.74  4041.6  616.98  4282.7  617.83
  4385.2  617.25  4590.3  619.08  4924.5  614.94  4947.1  610.98  4989.2  610.71
  5010.8  611.34  5031.3  617.74  5103.5  618.11  5188.4  616.05  5221.8  617.26
  5345.5  617.17  5359.8  617.34  5863.4  618.24  6075.3  618.99  6082.2  618.82
#Mann= 18 ,-1 , 0
  3316.4     .15       0  3462.3    .063       0  3529.2     .15       0
  3564.9    .094       0  3808.4     .05       0  3812.4    .094       0
  4041.6     .15       0  4282.7    .094       0  4385.2    .063       0
  4590.3     .15       0  4924.5    .063       0  5103.5    .094       0
  5188.4    .063       0  5221.8     .15       0  5345.5    .094       0
  5359.8    .063       0  5863.4    .035       0  6075.3    .094       0
Bank Sta=3808.4,3812.4
XS Rating Curve= 0 ,0
Exp/Cntr=0.3,0.1

Type RM Length L Ch R = 1 ,6246    ,402,402,402
BEGIN DESCRIPTION:
North Guadalupe Tributary 12.0
END DESCRIPTION:
XS GIS Cut Line= 3
      2252159.59     13799269.04      2251826.27      13798414.9
      2251388.75     13797637.08
#Sta/Elev= 30
  4201.7  619.22  4260.3  619.01  4284.8  617.09  4393.5  618.49  4549.5  617.56
  4592.5  615.46  4616.2  615.39  4635.4  616.78  4850.1  615.87  4882.3  614.28
  4925.2  615.11    4936  612.35  4942.3  609.12  4957.4  607.45  4976.8  607.12
  4977.1  606.62    4981  607.12    5002  608.96  5021.1  615.43  5061.9  616.78
  5133.5  617.29    5151   616.3    5333  616.24  5392.3  615.02  5441.4  616.74
  5516.3  617.19  5725.2  617.49  5883.8  616.36  5994.9  617.13    6011  617.15
#Mann= 8 ,-1 , 0
  4201.7    .063       0  4976.8     .05       0    4981    .063       0
  5061.9    .094       0    5151     .15       0  5516.3    .094       0
  5725.2     .15       0  5994.9    .063       0
Bank Sta=4976.8,4981
XS Rating Curve= 0 ,0
Exp/Cntr=0.3,0.1

Type RM Length L Ch R = 1 ,5844    ,291,291,291
BEGIN DESCRIPTION:
B19821
END DESCRIPTION:
XS GIS Cut Line= 3
      2252430.44     13799178.81       2252159.6     13798255.18
       2251513.8     13797637.15
#Sta/Elev= 30
  4187.4  616.76  4370.2  616.46  4442.2  614.99  4542.4  616.58    4581  615.12
  4681.2  614.42  4913.1  614.54  4993.8  613.94  5002.7  610.15  5007.9  605.34
  5012.5  604.29  5012.8  603.79  5016.7  604.29  5025.1  605.82  5041.3  606.13
  5056.3  614.06  5066.7   615.3  5147.2  614.62  5195.8  614.88  5216.9  612.77
  5273.5  614.77  5294.7  613.87  5322.9  616.45  5378.8  617.57  5464.5  617.36
  5525.8   616.5    5597  616.74  5672.7  616.74  5729.6  616.26  6043.8  616.94
#Mann= 11 ,-1 , 0
  4187.4    .063       0  4913.1    .035       0  5012.5    .035       0
  5016.7    .035       0  5147.2     .15       0  5378.8    .035       0
  5464.5     .15       0  5525.8    .063       0    5597    .094       0
  5672.7    .063       0  5729.6     .15       0
Bank Sta=5012.5,5016.7
XS Rating Curve= 0 ,0
Exp/Cntr=0.3,0.1

Type RM Length L Ch R = 1 ,5553    ,468,468,468
BEGIN DESCRIPTION:
North Guadalupe Tributary 11.0
END DESCRIPTION:
XS GIS Cut Line= 3
      2252881.83     13798831.58        2252425.       13798225.
      2252013.78     13797484.37
#Sta/Elev= 30
  4245.4  623.93  4333.3  623.49  4383.3  624.06  4469.5  621.72  4483.2  620.58
  4547.7  620.67  4632.7  618.77  4762.2  617.91    4783  617.19  4797.6  615.58
  4868.4  616.05  4900.3  614.95  4968.3   613.5  4982.9  606.21  4991.2   604.3
  4995.4  604.19  4995.6  603.69  4999.6  604.19    5016  604.79  5018.5  605.17
  5024.4  609.68  5027.6  612.12  5034.5  613.12  5050.5  612.67  5164.9  614.29
  5416.5  614.25  5711.1  615.48  5786.3  616.14  5825.6  616.22  5851.9   616.4
#Mann= 11 ,-1 , 0
  4245.4    .063       0  4469.5    .094       0  4632.7    .063       0
  4900.3    .094       0  4995.4     .05       0  4999.6    .094       0
    5016    .063       0  5024.4    .035       0  5711.1     .07       0
  5786.3    .094       0  5825.6     .15       0
Bank Sta=4995.4,4999.6
XS Rating Curve= 0 ,0
Exp/Cntr=0.3,0.1

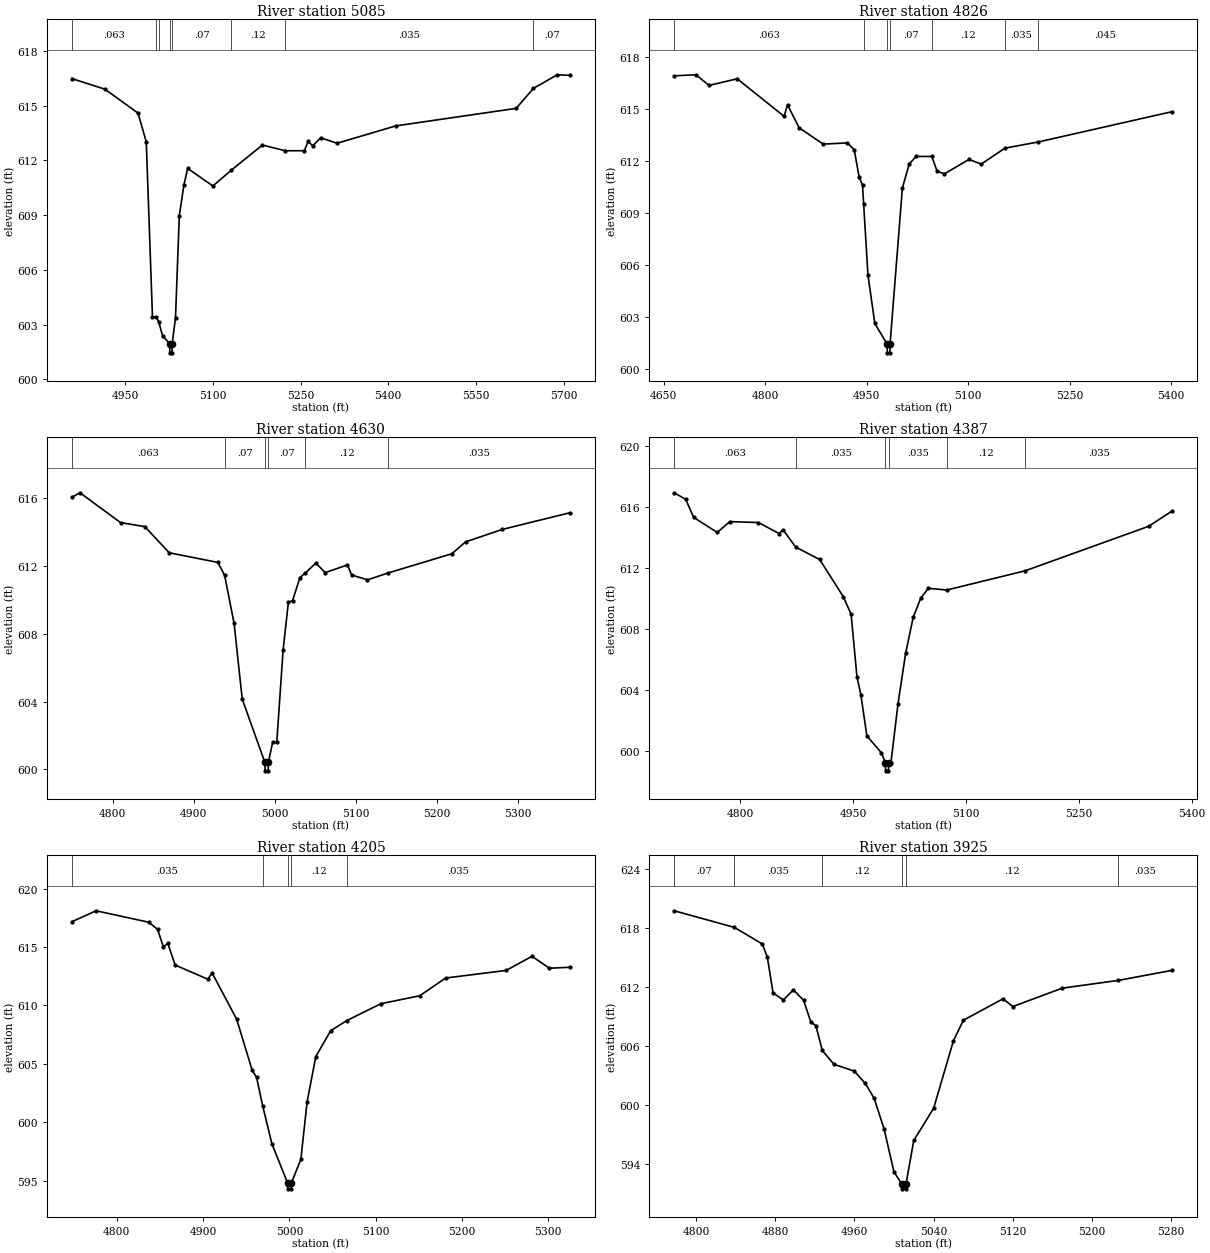
Type RM Length L Ch R = 1 ,5085    ,259,259,259
BEGIN DESCRIPTION:
North Guadalupe Tributary 10.0
END DESCRIPTION:
XS GIS Cut Line= 3
      2252925.02     13798125.02        2252825.       13798025.
      2252274.98     13797574.99
#Sta/Elev= 30
  4858.8  616.48  4915.4   615.9    4972  614.59  4986.1  613.01  4996.7  603.42
  5003.1  603.42  5007.6  603.14  5013.9   602.4  5026.1  601.96  5026.4  601.46
  5030.1  601.46  5030.4  601.96  5036.1  603.38  5042.6  608.98  5050.5  610.66
    5057  611.56    5100   610.6  5131.8  611.47  5184.7  612.84  5223.9  612.53
  5256.5  612.53    5263  613.04  5270.9   612.8  5284.5  613.24  5312.5  612.94
    5413  613.89    5619  614.85  5648.3  615.94  5689.3  616.69  5710.9  616.66
#Mann= 8 ,-1 , 0
  4858.8    .063       0  5003.1     .12       0  5007.6     .07       0
  5026.1     .05       0  5030.4     .07       0  5131.8     .12       0
  5223.9    .035       0  5648.3     .07       0
Bank Sta=5026.1,5030.4
XS Rating Curve= 0 ,0
Exp/Cntr=0.3,0.1

Type RM Length L Ch R = 1 ,4826    ,196,196,196
BEGIN DESCRIPTION:
B19823
END DESCRIPTION:
XS GIS Cut Line= 3
      2253090.15     13798206.52      2253020.71     13797831.57
      2252881.84     13797505.21
#Sta/Elev= 30
  4665.7  616.89  4697.8  616.95  4717.2  616.34  4758.8  616.72  4828.1  614.56
  4833.2  615.22  4850.3   613.9    4886  612.96  4921.5  613.03  4931.7  612.64
  4938.9  611.09    4944  610.59  4945.7   609.5    4952  605.44  4962.2  602.64
  4980.4  601.45  4980.7  600.95  4984.4  600.95  4984.7  601.45  5002.9  610.43
    5013  611.82  5023.2  612.25  5046.4  612.25  5054.2   611.4    5065  611.25
  5101.5  612.08  5119.4  611.81  5154.6  612.73  5203.3  613.08  5401.7  614.83
#Mann= 7 ,-1 , 0
  4665.7    .063       0  4945.7     .07       0  4980.4     .05       0
  4984.7     .07       0  5046.4     .12       0  5154.6    .035       0
  5203.3    .045       0
Bank Sta=4980.4,4984.7
XS Rating Curve= 0 ,0
Exp/Cntr=0.3,0.1

Type RM Length L Ch R = 1 ,4630    ,243,243,243
BEGIN DESCRIPTION:
North Guadalupe Tributary 9.0
END DESCRIPTION:
XS GIS Cut Line= 3
        2253225.       13798125.        2253225.       13797875.
        2253325.     13797525.01
#Sta/Elev= 30
  4749.6  616.06  4759.6  616.32  4809.6  614.56  4839.6  614.32  4869.6  612.78
  4929.6  612.21  4937.9  611.45  4949.6  608.61  4959.6  604.15  4987.5  600.41
  4987.8  599.91  4991.5  599.91  4991.8  600.41  4997.1  601.59  5002.2  601.59
    5010  607.03  5016.5  609.85  5021.7  609.96  5030.8  611.32  5037.4  611.58
  5050.3  612.17    5062  611.61  5089.3  612.06  5094.5  611.47    5114  611.18
  5138.9  611.58    5218  612.72  5234.9  613.42  5280.4  614.16  5363.6  615.14
#Mann= 6 ,-1 , 0
  4749.6    .063       0  4937.9     .07       0  4987.5     .05       0
  4991.8     .07       0  5037.4     .12       0  5138.9    .035       0
Bank Sta=4987.5,4991.8
XS Rating Curve= 0 ,0
Exp/Cntr=0.3,0.1

Type RM Length L Ch R = 1 ,4387    ,182,182,182
BEGIN DESCRIPTION:
B19822
END DESCRIPTION:
XS GIS Cut Line= 3
      2253367.93     13798199.63      2253451.27     13797928.79
      2253499.88      13797553.8
#Sta/Elev= 30
  4712.6  616.94  4727.9  616.51  4738.4  615.33  4769.8  614.34  4786.5  615.05
  4824.5  614.99  4851.9  614.27  4857.2  614.52  4873.9  613.38  4905.8  612.57
  4937.2  610.13  4947.6  608.98  4955.3  604.89  4960.5  603.72  4968.5  601.01
  4987.9   599.9  4993.2  599.22  4993.4  598.72  4997.2  598.72  4997.5  599.22
  5000.4  599.22  5009.9  603.12    5020  606.42    5030  608.77  5040.1  610.04
  5050.2  610.68  5074.8  610.57  5178.9  611.83  5342.6  614.74  5374.1  615.75
#Mann= 6 ,-1 , 0
  4712.6    .063       0  4873.9    .035       0  4993.2    .035       0
  4997.5    .035       0  5074.8     .12       0  5178.9    .035       0
Bank Sta=4993.2,4997.5
XS Rating Curve= 0 ,0
Exp/Cntr=0.3,0.1

Type RM Length L Ch R = 1 ,4205    ,280,280,280
BEGIN DESCRIPTION:
B19824
END DESCRIPTION:
XS GIS Cut Line= 3
       2253569.2     13798222.43      2253627.41     13797926.29
      2253640.03     13797651.19
#Sta/Elev= 30
  4747.9  617.17  4775.9  618.11    4837  617.13  4847.2  616.52    4854  615.01
  4859.1  615.32  4867.6  613.46  4905.4  612.25  4910.5  612.77  4938.9  608.82
  4956.8  604.46  4961.9  603.85  4969.2  601.35  4979.7  598.15  4997.9  594.79
  4998.2  594.29    5002  594.29  5002.3  594.79  5013.3  596.82  5020.5  601.73
  5030.6  605.62  5047.8  607.83  5066.4   608.7  5106.1  610.15  5151.1  610.83
  5181.1  612.35  5251.2     613  5281.2  614.21  5301.3  613.19  5325.1  613.27
#Mann= 5 ,-1 , 0
  4747.9    .035       0  4969.2     .12       0  4997.9     .05       0
  5002.3     .12       0  5066.4    .035       0
Bank Sta=4997.9,5002.3
XS Rating Curve= 0 ,0
Exp/Cntr=0.3,0.1

Type RM Length L Ch R = 1 ,3925    ,242,242,242
BEGIN DESCRIPTION:
B19825
END DESCRIPTION:
XS GIS Cut Line= 3
        2253840.     13798242.63      2253880.49     13798057.89
      2253890.61     13797744.08
#Sta/Elev= 30
    4778  619.79  4838.8   618.1    4867  616.41  4872.1  615.07  4877.9  611.43
  4888.2  610.72  4898.4  611.74  4908.7  610.69    4916  608.48  4921.1   608.1
  4927.6  605.58  4939.4  604.17  4959.8  603.48  4971.1  602.22    4980   600.7
    4990   597.6    5000  593.23  5007.8     592  5008.1   591.5  5011.9   591.5
  5012.2     592    5020  596.42  5040.1   599.7  5060.1  606.57  5070.1  608.65
  5110.1  610.83  5120.1  610.05  5170.1  611.92  5226.2   612.7  5281.1  613.73
#Mann= 6 ,-1 , 0
    4778     .07       0  4838.8    .035       0  4927.6     .12       0
  5007.8     .05       0  5012.2     .12       0  5226.2    .035       0
Bank Sta=5007.8,5012.2
XS Rating Curve= 0 ,0
Exp/Cntr=0.3,0.1

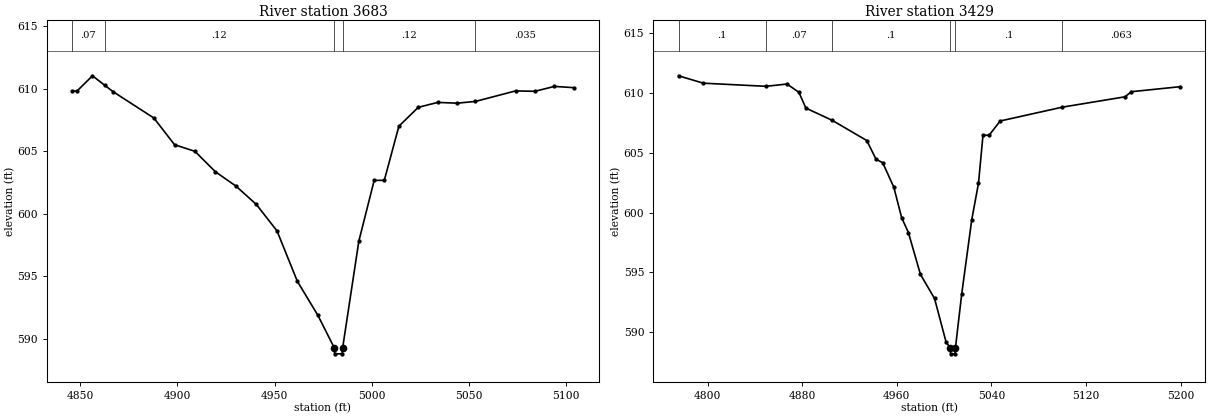
Type RM Length L Ch R = 1 ,3683    ,254,254,254
BEGIN DESCRIPTION:
North Guadalupe Tributary 7.0
END DESCRIPTION:
XS GIS Cut Line= 3
      2254075.01     13798174.96        2254125.       13798025.
        2254125.     13797924.97
#Sta/Elev= 30
  4845.8  609.82  4848.4  609.82  4856.3  611.03  4862.6  610.27  4866.8  609.77
  4887.9  607.65  4898.5  605.52    4909  604.99  4919.5  603.36  4930.1  602.21
  4940.6  600.74  4951.2  598.63  4961.7  594.59  4972.2  591.89  4980.6   589.3
  4980.9   588.8  4984.7   588.8    4985   589.3  4993.3  597.81  5001.2  602.67
  5006.4  602.67  5013.9     607  5023.9  608.51  5033.9   608.9  5043.9  608.84
  5053.3  608.98  5073.9  609.82  5083.9  609.79  5093.9  610.18  5103.9  610.08
#Mann= 5 ,-1 , 0
  4845.8     .07       0  4862.6     .12       0  4980.6     .05       0
    4985     .12       0  5053.3    .035       0
Bank Sta=4980.6,4985
XS Rating Curve= 0 ,0
Exp/Cntr=0.3,0.1

Type RM Length L Ch R = 1 ,3429    ,214,214,214
BEGIN DESCRIPTION:
B19826
END DESCRIPTION:
XS GIS Cut Line= 3
      2254227.19     13798333.77      2254353.74     13798108.51
      2254376.51     13797944.05
#Sta/Elev= 30
  4775.4  611.44  4796.4  610.82  4849.4  610.56  4867.1  610.75  4877.2  610.06
  4883.1  608.74  4905.3  607.72  4934.6  606.03  4942.4  604.47  4948.1  604.17
  4957.5  602.12  4964.1  599.58  4969.8  598.34    4980  594.84  4991.9  592.83
  5001.7  589.18  5005.2   588.7  5005.5   588.2  5009.3   588.2  5009.6   588.7
  5014.9   593.2  5023.4  599.41  5029.1  602.46  5032.9  606.47  5038.1  606.47
  5047.4  607.66  5100.1  608.82  5152.9  609.68  5158.5  610.11  5199.8  610.53
#Mann= 6 ,-1 , 0
  4775.4      .1       0  4849.4     .07       0  4905.3      .1       0
  5005.2     .05       0  5009.6      .1       0  5100.1    .063       0
Bank Sta=5005.2,5009.6
XS Rating Curve= 0 ,0
Exp/Cntr=0.3,0.1