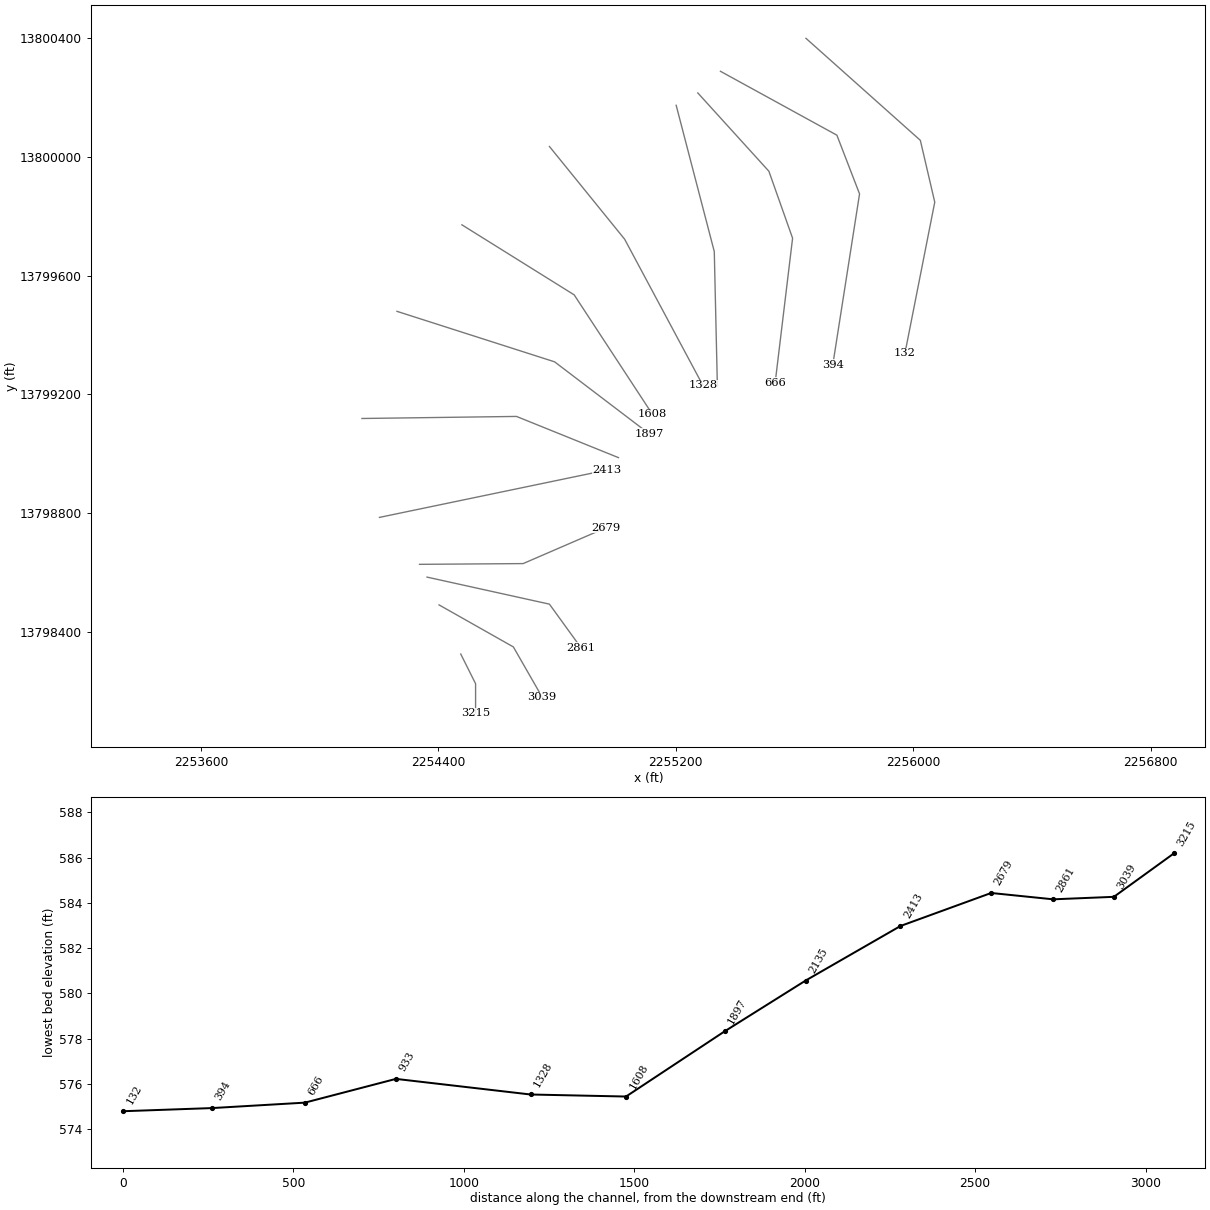
HEC-RAS study North Guadalupe Tributary.prj: North Guadalupe Tributary Base Level Engineering

--- North Guadalupe Tributary.g01 (geometry) --- (continued)

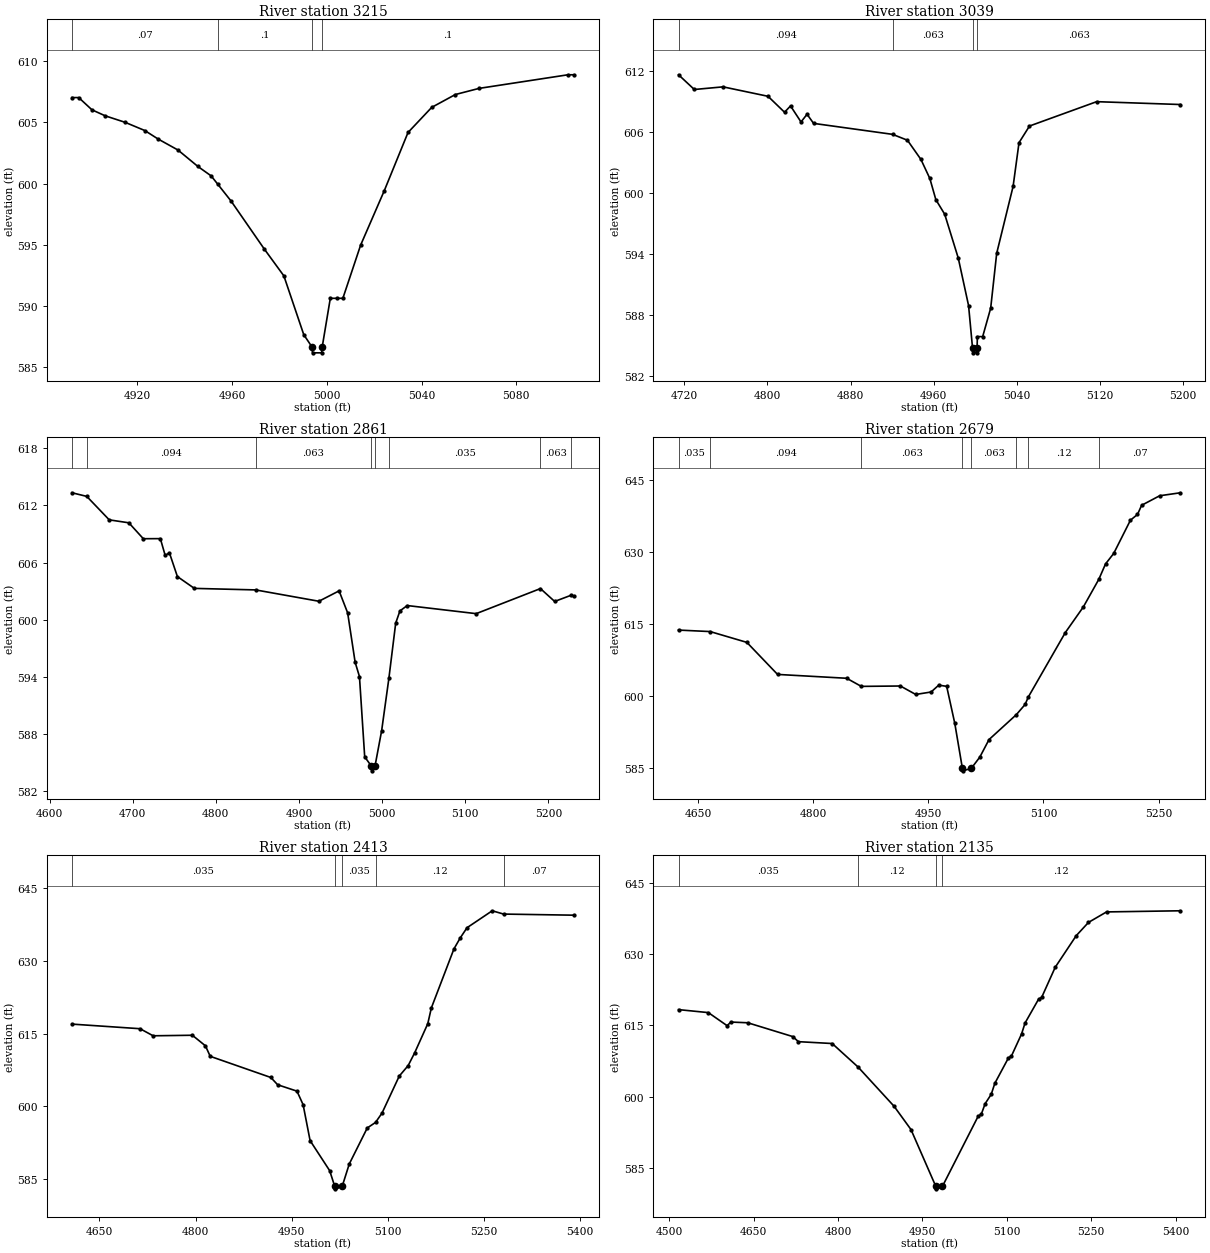
Type RM Length L Ch R = 1 ,3215    ,176,176,176
BEGIN DESCRIPTION:
North Guadalupe Tributary 6.0
END DESCRIPTION:
XS GIS Cut Line= 3
        2254475.       13798325.        2254525.       13798225.
        2254525.     13798125.01
#Sta/Elev= 30
  4892.5  607.02  4895.3  607.02  4900.9  606.02  4906.5  605.53  4914.9     605
  4923.2  604.33  4928.8  603.64  4937.2  602.74  4945.6   601.4  4951.2  600.63
    4954  599.95  4959.6  598.58  4973.6  594.67  4981.9  592.47  4990.3  587.67
  4993.7  586.69    4994  586.19  4997.8  586.19  4998.1  586.69  5001.5  590.64
  5004.3  590.64  5006.8  590.64  5014.3  594.98  5024.3  599.43  5034.3  604.17
  5044.3  606.22  5054.3  607.27  5064.3  607.77  5101.8  608.88  5104.3  608.88
#Mann= 4 ,-1 , 0
  4892.5     .07       0    4954      .1       0  4993.7     .05       0
  4998.1      .1       0
Bank Sta=4993.7,4998.1
XS Rating Curve= 0 ,0
Exp/Cntr=0.3,0.1

Type RM Length L Ch R = 1 ,3039    ,178,178,178
BEGIN DESCRIPTION:
B19827
END DESCRIPTION:
XS GIS Cut Line= 3
       2254401.8     13798490.66      2254652.37     13798348.93
      2254749.64     13798179.32
#Sta/Elev= 30
  4714.3  611.67  4729.5  610.22  4757.2  610.48  4800.5  609.55  4816.4  607.98
  4822.2   608.6  4832.3  607.02  4838.1  607.78  4844.4  606.88  4920.5   605.8
  4934.8  605.22  4947.8  603.33  4956.4  601.45  4962.2  599.36  4970.7  597.93
  4983.8   593.6  4993.7  588.93  4997.5  584.77  4997.8  584.27  5001.6  584.27
  5001.9  584.77  5002.2  585.87  5007.3  585.87    5015  588.67  5020.8  594.08
  5036.6  600.67  5042.3  604.98  5052.4  606.62  5117.1  609.02  5197.7  608.74
#Mann= 4 ,-1 , 0
  4714.3    .094       0  4920.5    .063       0  4997.5     .05       0
  5001.9    .063       0
Bank Sta=4997.5,5001.9
XS Rating Curve= 0 ,0
Exp/Cntr=0.3,0.1

Type RM Length L Ch R = 1 ,2861    ,182,182,182
BEGIN DESCRIPTION:
B19828
END DESCRIPTION:
XS GIS Cut Line= 3
      2254361.32     13798584.29      2254773.84     13798493.18
      2254880.08     13798346.47
#Sta/Elev= 30
  4627.1  613.33  4644.8  612.95  4671.8  610.49  4695.4  610.18  4712.8  608.51
  4733.3  608.52  4739.1  606.76  4744.2  607.03  4753.8  604.54  4774.2   603.3
  4847.9  603.14    4924  601.95  4948.3  603.04  4958.6  600.73  4967.6  595.55
  4972.8  594.05  4979.1  585.63  4987.1  584.66  4987.4  584.16  4991.5  584.66
  4999.5  588.38  5008.2  593.87  5016.4  599.66  5021.5  600.94  5030.3   601.5
  5113.2  600.65  5190.5  603.28  5207.6  601.93  5227.1  602.57  5230.7  602.47
#Mann= 8 ,-1 , 0
  4627.1    .035       0  4644.8    .094       0  4847.9    .063       0
  4987.1     .05       0  4991.5    .063       0  5008.2    .035       0
  5190.5    .063       0  5227.1    .094       0
Bank Sta=4987.1,4991.5
XS Rating Curve= 0 ,0
Exp/Cntr=0.3,0.1

Type RM Length L Ch R = 1 ,2679    ,266,266,266
BEGIN DESCRIPTION:
B19829
END DESCRIPTION:
XS GIS Cut Line= 3
      2254336.02     13798627.31      2254685.27     13798629.84
       2254964.7     13798750.68
#Sta/Elev= 30
  4624.7  613.74  4665.9  613.43  4713.7  611.18  4753.7  604.51  4843.7  603.71
  4862.8  602.02  4913.7   602.1  4933.7  600.34  4953.7  600.85  4963.7  602.28
    4974  602.03  4984.6  594.31  4994.5  584.94    4995  584.44    5006  584.94
  5017.2   587.3  5029.2  590.95  5064.8  596.14  5076.2  598.26  5080.3  599.79
  5128.6  613.23  5152.1  618.57  5172.2   624.3    5181  627.52  5191.6  629.69
  5213.4  636.61  5222.6  637.81    5228  639.72  5251.5   641.7  5278.4  642.32
#Mann= 8 ,-1 , 0
  4624.7    .035       0  4665.9    .094       0  4862.8    .063       0
  4994.5     .05       0    5006    .063       0  5064.8    .035       0
  5080.3     .12       0  5172.2     .07       0
Bank Sta=4994.5,5006
XS Rating Curve= 0 ,0
Exp/Cntr=0.3,0.1

Type RM Length L Ch R = 1 ,2413    ,278,278,278
BEGIN DESCRIPTION:
B19830
END DESCRIPTION:
XS GIS Cut Line= 2
      2254201.05     13798785.54       2254968.4     13798945.26
#Sta/Elev= 30
  4607.2  616.99  4713.4  616.04  4733.8  614.58  4795.1  614.69  4815.5  612.51
    4823  610.34  4917.7  605.97  4928.3  604.47  4958.5  603.15  4968.1  600.35
    4979  592.94  5009.6  586.73  5017.5  583.48    5018  582.98  5029.1  583.48
  5040.2  588.12  5068.3  595.55  5081.2  596.69  5091.3  598.61  5118.3  606.27
  5132.2  608.43  5142.4  611.08  5162.8  617.07  5168.4  620.33  5203.7  632.52
  5213.4  634.76  5224.1  636.89  5263.5  640.39  5281.2  639.71    5391  639.48
#Mann= 5 ,-1 , 0
  4607.2    .035       0  5017.5    .035       0  5029.1    .035       0
  5081.2     .12       0  5281.2     .07       0
Bank Sta=5017.5,5029.1
XS Rating Curve= 0 ,0
Exp/Cntr=0.3,0.1

Type RM Length L Ch R = 1 ,2135    ,238,238,238
BEGIN DESCRIPTION:
B19831
END DESCRIPTION:
XS GIS Cut Line= 3
      2254142.01     13799118.87      2254662.86     13799125.82
      2255006.57     13798986.94
#Sta/Elev= 30
  4516.6  618.32  4569.6  617.69  4602.9  614.94  4609.6   615.7  4639.6  615.55
  4719.6  612.64  4729.6  611.57  4789.6  611.18  4835.5  606.24  4899.6  597.96
  4929.6  593.06  4973.8  581.07  4974.3  580.57  4985.4  581.07  5049.1  595.89
  5054.5  596.27  5061.4  598.51  5072.2  600.48  5078.6   602.8  5102.8  608.15
  5108.2  608.57  5126.1  613.19  5132.3   615.5  5156.4  620.53  5161.8  620.89
  5185.9  627.24  5223.2  633.89    5245  636.69  5277.1   638.9  5408.2  639.14
#Mann= 4 ,-1 , 0
  4516.6    .035       0  4835.5     .12       0  4973.8     .05       0
  4985.4     .12       0
Bank Sta=4973.8,4985.4
XS Rating Curve= 0 ,0
Exp/Cntr=0.3,0.1

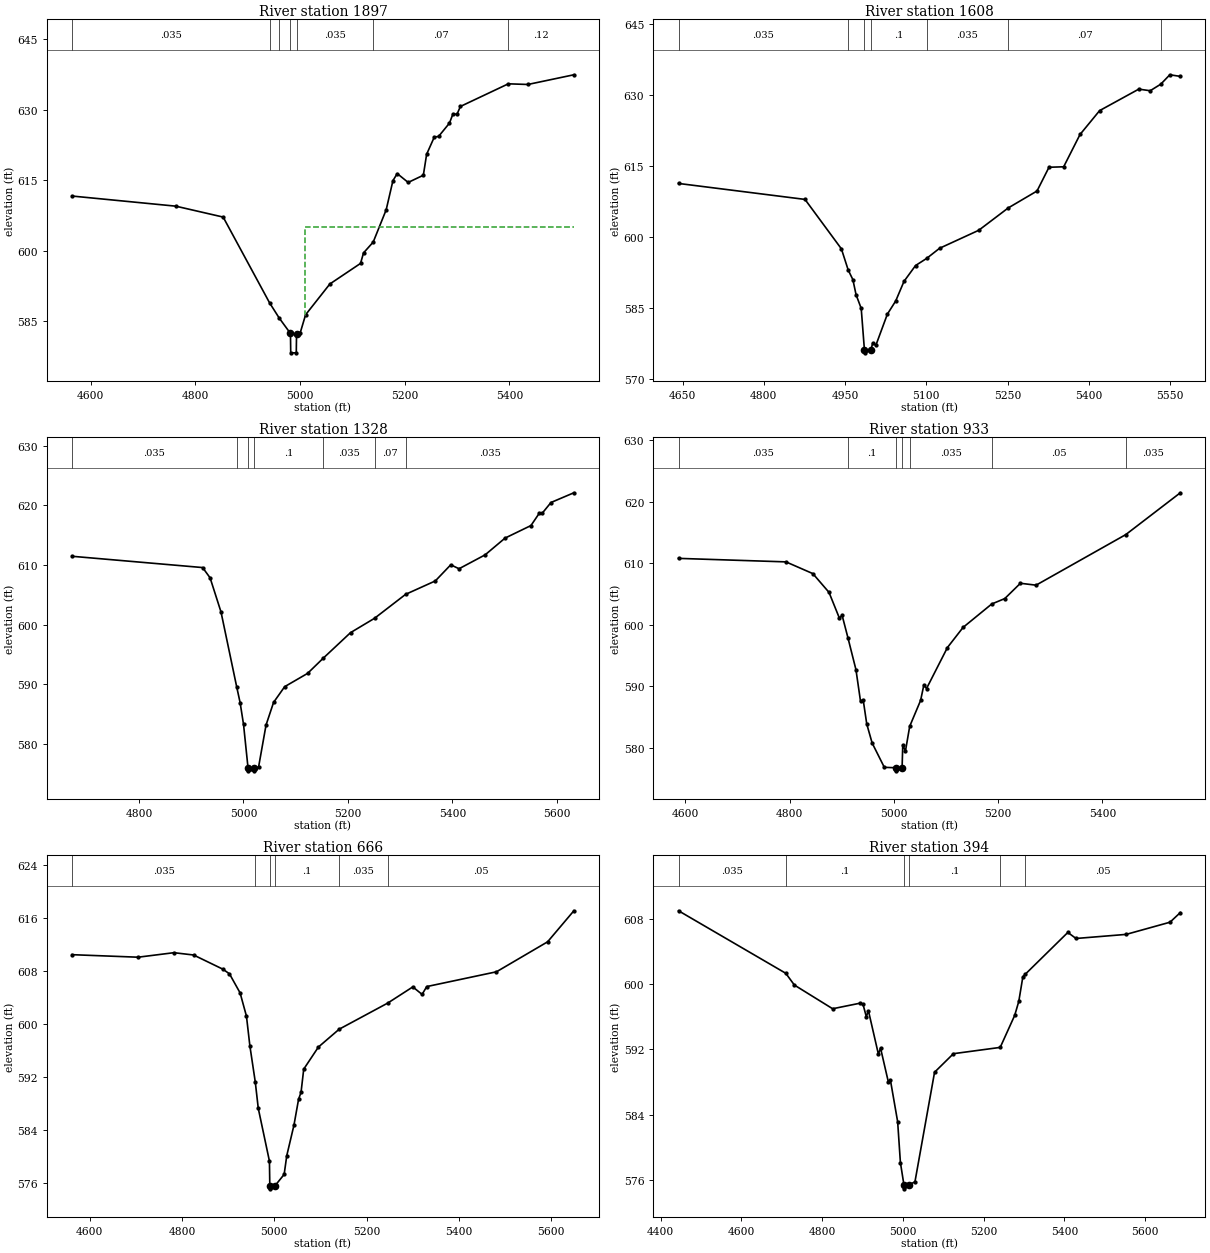
Type RM Length L Ch R = 1 ,1897    ,289,289,289
BEGIN DESCRIPTION:
B19832
END DESCRIPTION:
XS GIS Cut Line= 3
      2254260.05     13799479.99      2254791.33     13799309.84
      2255110.41     13799067.07
#Sta/Elev= 30
  4564.5  611.63  4762.6  609.48  4853.2  607.16    4942  588.92  4960.3  585.71
  4981.8  582.44  4982.3  578.32  4992.9  578.32  4993.4  582.22  5000.2  582.48
  5010.7  586.41  5057.1  592.95  5115.7  597.32  5121.4  599.55  5139.9  601.85
  5164.7  608.71  5177.6   614.9  5185.8   616.4  5206.7  614.52  5235.7  616.05
    5242  620.51  5256.6  624.15  5264.8  624.29  5285.6  627.12  5291.9  628.96
  5300.2  629.06  5306.5  630.66  5398.1  635.47  5435.4  635.33  5523.3  637.39
#Mann= 7 ,-1 , 0
  4564.5    .035       0    4942      .1       0  4960.3    .035       0
  4981.8    .035       0  4993.4    .035       0  5139.9     .07       0
  5398.1     .12       0
#XS Ineff= 2 , 0
       0                    5010       0  604.96
Permanent Ineff=
       F       F
Bank Sta=4981.8,4993.4
XS Rating Curve= 0 ,0
Exp/Cntr=0.3,0.1

Type RM Length L Ch R = 1 ,1608    ,280,280,280
BEGIN DESCRIPTION:
B19833
END DESCRIPTION:
XS GIS Cut Line= 3
      2254478.84     13799771.64       2254857.3     13799535.54
      2255120.59     13799133.68
#Sta/Elev= 30
  4642.5  611.32    4876  607.94  4943.2  597.47  4955.8  592.97  4964.4  590.95
  4970.3  587.75  4979.8  584.85  4985.8  575.94  4986.3  575.44  4997.4  575.94
    5001  577.51  5006.9  577.05  5028.1  583.64  5043.5  586.43  5058.8  590.58
  5080.1  593.93  5100.6  595.44  5124.5  597.59  5196.8   601.4  5251.2  606.13
  5304.4  609.72  5326.5  614.75  5353.6  614.85  5383.8  621.69    5420  626.75
  5492.3   631.3  5513.4  630.96  5532.9  632.35  5549.6  634.34    5569     634
#Mann= 7 ,-1 , 0
  4642.5    .035       0  4955.8      .1       0  4985.8     .05       0
  4997.4      .1       0  5100.6    .035       0  5251.2     .07       0
  5532.9     .12       0
Bank Sta=4985.8,4997.4
XS Rating Curve= 0 ,0
Exp/Cntr=0.3,0.1

Type RM Length L Ch R = 1 ,1328    ,395,395,395
BEGIN DESCRIPTION:
B19834
END DESCRIPTION:
XS GIS Cut Line= 3
      2254773.94     13800035.57      2255027.44     13799723.04
      2255290.65     13799231.26
#Sta/Elev= 30
  4672.1  611.48  4921.9  609.59  4936.2  607.87  4957.1  602.15  4987.1  589.61
  4993.7  586.94  5000.2  583.31  5008.8  576.03  5009.3  575.53  5019.9  575.53
  5020.4  576.03  5028.9  576.12  5043.3  583.21  5057.7     587  5078.9  589.63
  5122.8  591.86  5152.2  594.36  5204.9  598.68  5250.9  601.09  5310.3   605.1
  5367.2  607.35  5396.7  610.05  5412.6  609.39  5462.5  611.72  5500.7  614.53
  5550.2  616.63  5566.5  618.74  5572.2  618.74  5588.5  620.49  5632.3  622.12
#Mann= 7 ,-1 , 0
  4672.1    .035       0  4987.1      .1       0  5008.8     .05       0
  5020.4      .1       0  5152.2    .035       0  5250.9     .07       0
  5310.3    .035       0
Bank Sta=5008.8,5020.4
XS Rating Curve= 0 ,0
Exp/Cntr=0.3,0.1

Type RM Length L Ch R = 1 ,933     ,267,267,267
BEGIN DESCRIPTION:
B19835
END DESCRIPTION:
XS GIS Cut Line= 3
      2255201.05     13800174.42      2255329.52     13799681.37
       2255339.9      13799228.3
#Sta/Elev= 30
  4586.9  610.78    4793  610.21  4844.6   608.3  4875.6  605.25  4895.6  601.04
  4900.7  601.53    4912  597.83  4927.3  592.67  4936.1   587.5  4941.2  587.75
    4948  583.84  4958.3  580.75  4981.7  576.79  5004.1  576.72  5004.6  576.22
  5015.8  576.72  5017.1  580.46  5022.2  579.41  5030.4  583.46  5051.3  587.67
  5057.6   590.2  5062.7  589.61  5102.8  596.28  5132.8  599.55  5187.8  603.36
  5212.8  604.24  5242.8  606.73  5272.8  606.42    5445  614.65  5549.6  621.45
#Mann= 7 ,-1 , 0
  4586.9    .035       0    4912      .1       0  5004.1     .05       0
  5015.8      .1       0  5030.4    .035       0  5187.8     .05       0
    5445    .035       0
Bank Sta=5004.1,5015.8
XS Rating Curve= 0 ,0
Exp/Cntr=0.3,0.1

Type RM Length L Ch R = 1 ,666     ,272,272,272
BEGIN DESCRIPTION:
B19836
END DESCRIPTION:
XS GIS Cut Line= 4
      2255273.96     13800216.11      2255513.55      13799952.2
      2255593.41     13799726.51      2255534.57     13799238.49
#Sta/Elev= 30
  4561.8  610.48  4704.9   610.1  4782.6  610.78  4825.2  610.43  4888.7  608.29
  4902.9  607.59  4925.9  604.72  4939.7  601.21  4947.1  596.74  4958.8  591.29
  4965.3  587.31  4989.5  579.35  4990.3  575.67  4990.8  575.17    5002  575.67
  5021.4  577.35  5027.1  580.19  5042.6  584.76  5052.7   588.7    5058  589.72
  5063.8  593.22  5095.6  596.55  5140.6  599.24  5245.8  603.18  5300.2  605.62
  5320.3  604.49  5330.4  605.67  5481.5   607.9  5592.3  612.42  5649.2   617.1
#Mann= 6 ,-1 , 0
  4561.8    .035       0  4958.8      .1       0  4990.3     .05       0
    5002      .1       0  5140.6    .035       0  5245.8     .05       0
Bank Sta=4990.3,5002
XS Rating Curve= 0 ,0
Exp/Cntr=0.3,0.1

Type RM Length L Ch R = 1 ,394     ,262,262,262
BEGIN DESCRIPTION:
B19837
END DESCRIPTION:
XS GIS Cut Line= 4
      2255350.36     13800289.01      2255742.72     13800073.73
      2255819.11     13799875.82      2255728.88     13799299.73
#Sta/Elev= 30
  4444.4  608.96    4710  601.31  4731.3  599.87  4826.1  596.97  4893.9  597.65
  4901.3  597.51  4909.4  596.01  4914.8  596.71  4939.4  591.41  4944.7  592.16
    4964  588.02  4969.3   588.2  4987.1  583.14  4993.9  578.15  5002.6  575.43
  5003.1  574.93  5014.3  575.43  5029.9  575.78  5078.5   589.2  5125.2  591.47
  5241.1  592.24    5277  596.16  5287.1  597.87  5297.2  600.88  5303.3   601.2
  5408.6  606.31  5428.8  605.57    5553  606.07  5661.6  607.56  5687.2  608.74
#Mann= 6 ,-1 , 0
  4444.4    .035       0    4710      .1       0  5002.6     .05       0
  5014.3      .1       0  5241.1    .035       0  5303.3     .05       0
Bank Sta=5002.6,5014.3
XS Rating Curve= 0 ,0
Exp/Cntr=0.3,0.1

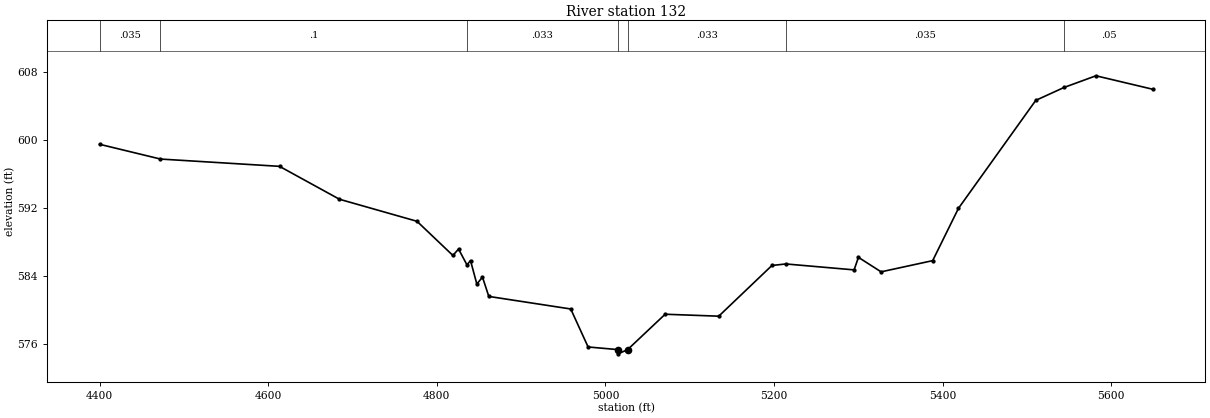
Type RM Length L Ch R = 1 ,132     ,0,0,0
BEGIN DESCRIPTION:
B19838
END DESCRIPTION:
XS GIS Cut Line= 4
      2255638.54     13800400.13      2256023.97     13800056.37
      2256072.58     13799848.04      2255972.13     13799338.84
#Sta/Elev= 30
    4400   599.5  4472.2  597.76  4613.4   596.9  4684.5  593.02  4776.5  590.42
  4819.1  586.39  4825.8  587.15  4835.8  585.28    4840  585.79  4847.5  583.02
  4854.2  583.84  4861.7  581.56  4958.9  580.08  4979.5   575.6  5014.7  575.29
  5015.2  574.79  5026.4  575.29  5070.9  579.46  5134.5  579.23  5197.6  585.21
  5214.1  585.39  5295.1  584.69  5300.2  586.17  5327.1  584.46  5388.3  585.78
  5418.9  591.95  5510.6  604.68  5544.1   606.2    5582  607.58  5649.4  605.99
#Mann= 7 ,-1 , 0
    4400    .035       0  4472.2      .1       0  4835.8    .033       0
  5014.7    .033       0  5026.4    .033       0  5214.1    .035       0
  5544.1     .05       0
Bank Sta=5014.7,5026.4
XS Rating Curve= 0 ,0
Exp/Cntr=0.3,0.1

Chan Stop Cuts=-1
Use User Specified Reach Order=0
Composite Channel Slope=5