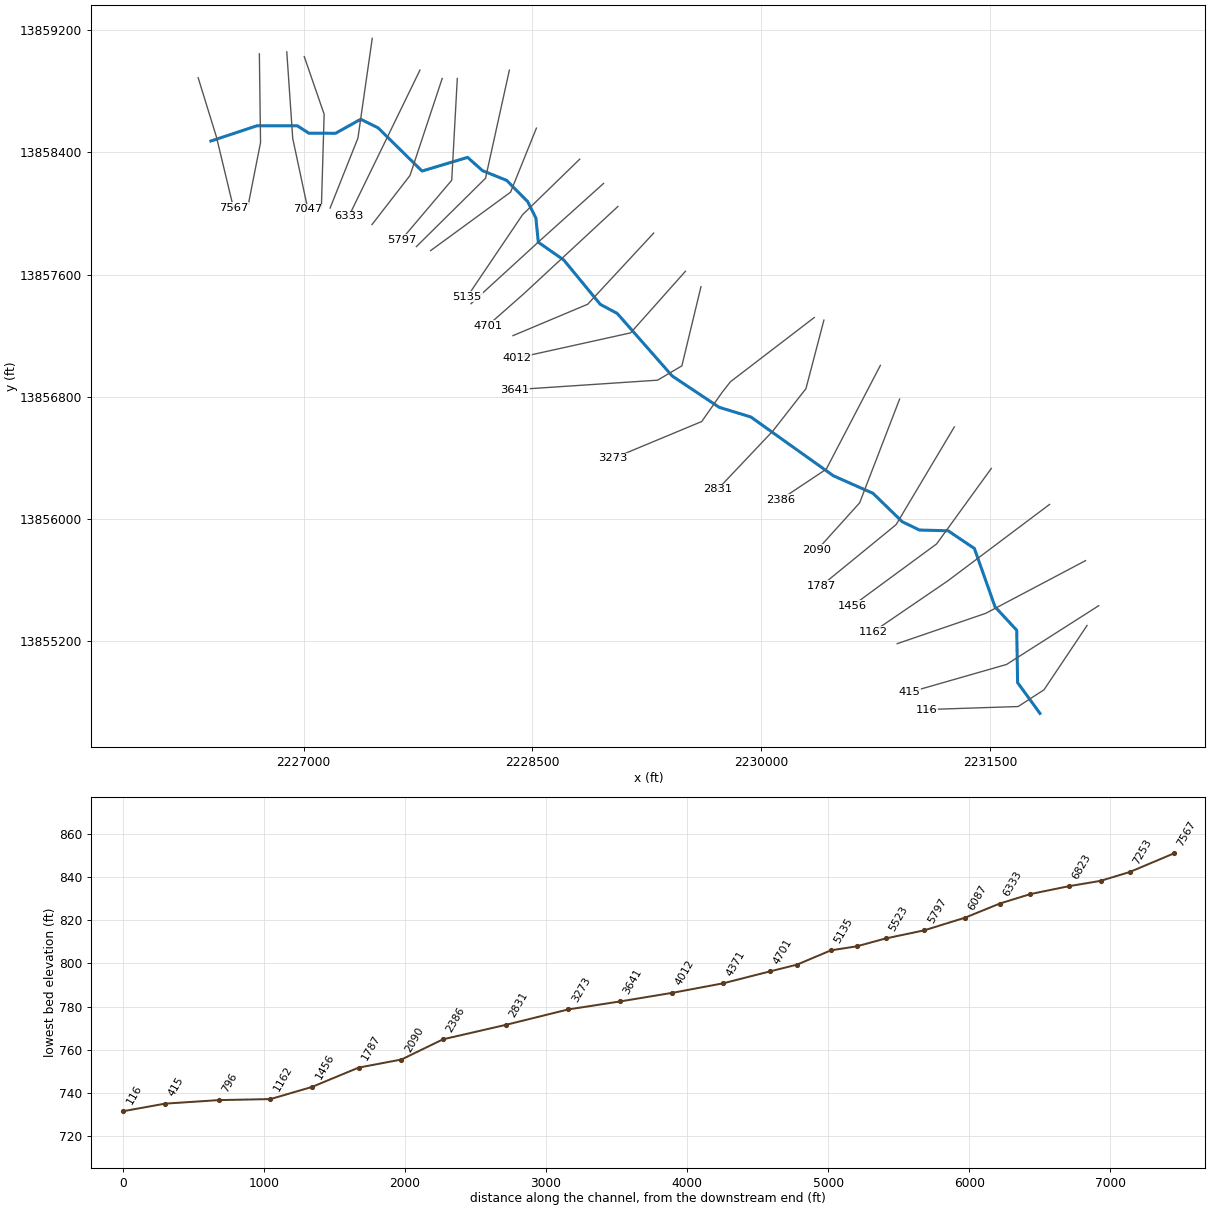
--- Sattler Tributary.prj (project) ---

Proj Title=Sattler Tributary Base Level Engineering
Current Plan=p01
Default Exp/Contr=0.3,0.1
English Units
Geom File=g01
Flow File=f01
Plan File=p01
Y Axis Title=Elevation
X Axis Title(PF)=Main Channel Distance
X Axis Title(XS)=Station
BEGIN DESCRIPTION:
Sattler Tributary
END DESCRIPTION:
DSS Export Rating Curves= 0
DSS Export Rating Curve Sorted= 0
DSS Export Volume Flow Curves= 0
DXF OffsetX= 0
DXF OffsetY= 0
DXF ScaleX= 1
DXF ScaleY= 10

--- Sattler Tributary.p01 (plan) ---

Plan Title=Multiple Run
Short Identifier=Multiple
Geom File=g01
Flow File=f01
Subcritical Flow
K Sum by GR= 0
Std Step Tol= 0.01
Critical Tol= 0.01
Num of Std Step Trials= 20
Max Error Tol= 0.3
Flow Tol Ratio= 0.001
Split Flow NTrial= 30
Split Flow Tol= 0.02
Split Flow Ratio= 0.02
Log Output Level= 0
Friction Slope Method= 1
Unsteady Friction Slope Method= 2
Unsteady Bridges Friction Slope Method= 1
Parabolic Critical Depth
Global Vel Dist=  1 , 1 , 1
Global Log Level= 0
CheckData=True
Encroach Param= -1, 0, 0, 0
BEGIN DESCRIPTION:
Multiple Run
END DESCRIPTION:

--- Sattler Tributary.f01 (steady flow) ---

Flow Title=Multiple
Number of Profiles=7
Profile Names=10-year,25-year,50-year,1pct_min,100-year,1pct_plu,500-year
River Rch & RM= Sattler Tributar,Reach-1,7567
     616     997    1344     880    1755    3501    2954
River Rch & RM= Sattler Tributar,Reach-1,1456
     914    1518    2081    1383    2759    5505    4793
Boundary for River Rch & Prof#=Sattler Tributar,Reach-1,1
Up Type=0
Dn Type=3
Dn Slope=0.005
Boundary for River Rch & Prof#=Sattler Tributar,Reach-1,2
Up Type=0
Dn Type=3
Dn Slope=0.005
Boundary for River Rch & Prof#=Sattler Tributar,Reach-1,3
Up Type=0
Dn Type=3
Dn Slope=0.005
Boundary for River Rch & Prof#=Sattler Tributar,Reach-1,4
Up Type=0
Dn Type=3
Dn Slope=0.005
Boundary for River Rch & Prof#=Sattler Tributar,Reach-1,5
Up Type=0
Dn Type=3
Dn Slope=0.005
Boundary for River Rch & Prof#=Sattler Tributar,Reach-1,6
Up Type=0
Dn Type=3
Dn Slope=0.005
Boundary for River Rch & Prof#=Sattler Tributar,Reach-1,7
Up Type=0
Dn Type=3
Dn Slope=0.005

--- Sattler Tributary.g01 (geometry) ---

Geom Title=Existing Conditions
Program Version=4.10

River Reach=Sattler Tributar,Reach-1
Reach XY= 30
      2226393.57       13858475.      2226695.03     13858574.93
      2226959.78     13858574.48      2227034.66     13858526.38
      2227209.79     13858525.51        2227375.      13858617.5
      2227488.21     13858561.39      2227776.63     13858278.13
       2228075.1     13858367.67       2228172.7     13858280.86
      2228331.06     13858216.86      2228469.17      13858077.3
      2228522.64     13857969.48      2228538.36     13857811.66
      2228705.16     13857695.38      2228944.63     13857404.53
      2229055.23     13857345.41      2229415.32     13856935.78
      2229722.58     13856730.54      2229931.05     13856666.84
      2230472.71     13856280.85      2230731.06     13856166.86
       2230922.7     13855980.83      2231034.65     13855926.36
      2231223.45     13855921.25      2231395.51     13855805.27
      2231530.83      13855422.7      2231672.83     13855269.56
      2231678.54     13854926.47        2231825.       13854725.

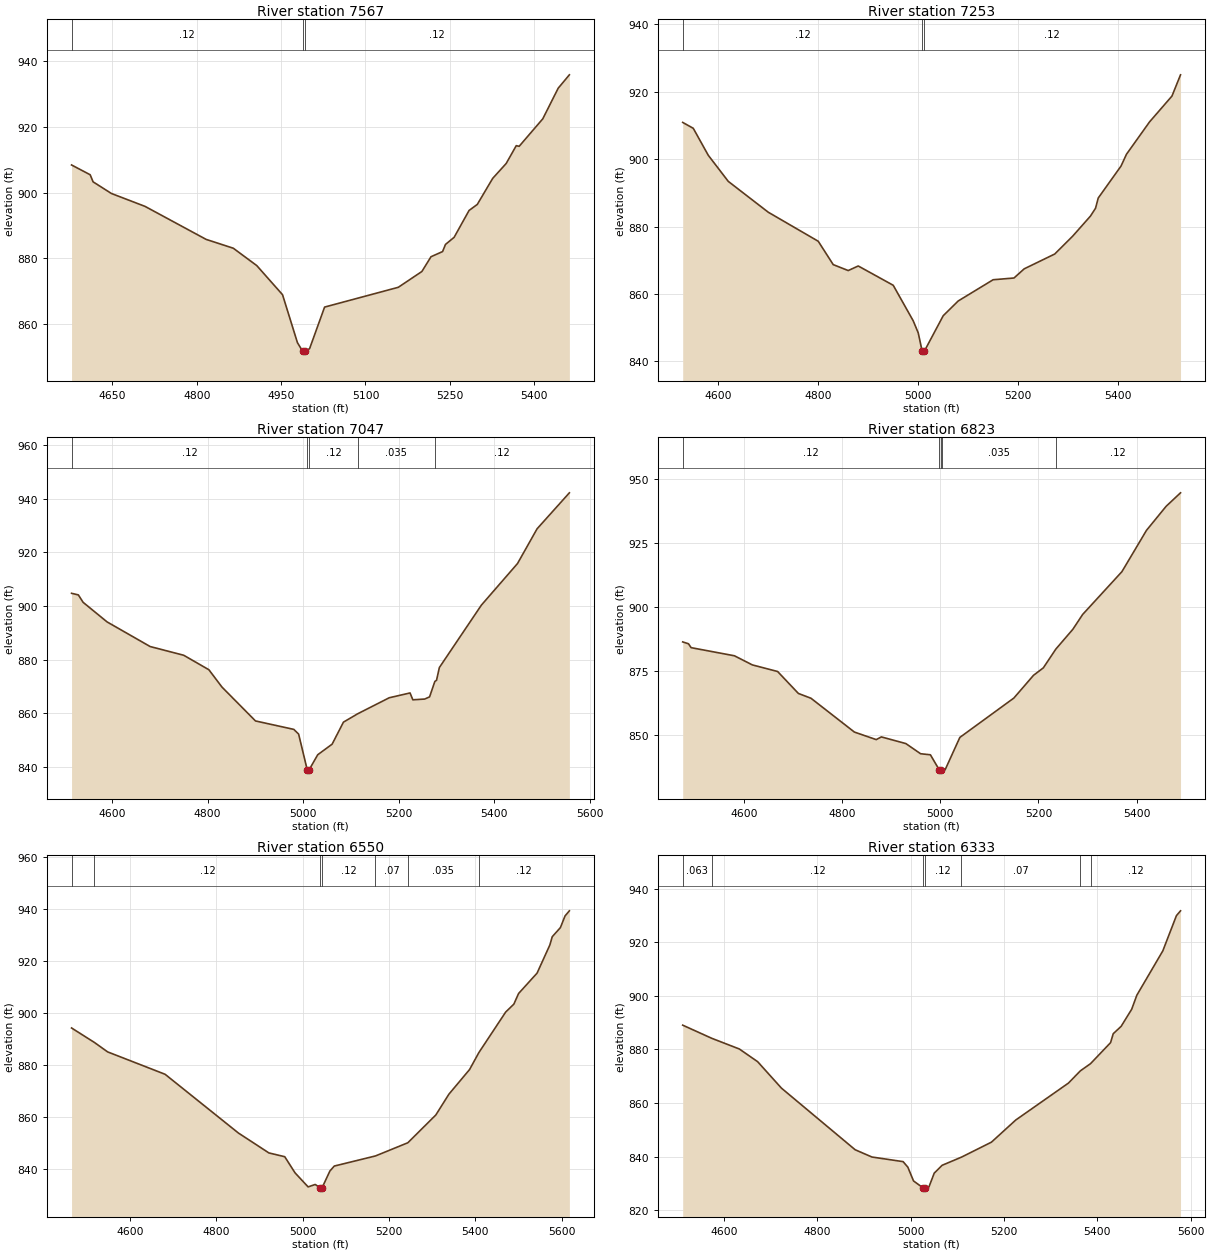
Type RM Length L Ch R = 1 ,7567    ,314,314,314
BEGIN DESCRIPTION:
E20742
END DESCRIPTION:
XS GIS Cut Line= 3
       2226309.7     13858889.86       2226429.5      13858501.8
      2226541.47     13858035.69
#Sta/Elev= 30
  4577.2  908.46  4610.3  905.48  4615.5  903.32  4648.2  899.76  4707.9  895.84
  4816.6  885.78  4864.9  883.09  4906.7  877.79  4952.5  868.92    4979  854.31
  4988.5  851.62  4988.7  851.12  4992.5  851.62  5000.6  852.48  5027.3  865.15
  5158.4  871.18  5200.3  875.99  5216.6   880.5  5237.2  882.07  5242.3  884.24
  5257.7  886.41  5284.3   894.6  5298.9  896.43  5326.3  904.37  5350.3  908.91
  5368.2  914.34  5373.4  914.15  5415.4  922.52  5442.8  931.85  5462.7  935.93
#Mann= 3 ,-1 , 0
  4577.2     .12       0  4988.5     .05       0  4992.5     .12       0
Bank Sta=4988.5,4992.5
XS Rating Curve= 0 ,0
Exp/Cntr=0.3,0.1

Type RM Length L Ch R = 1 ,7253    ,206,206,206
BEGIN DESCRIPTION:
E20741
END DESCRIPTION:
XS GIS Cut Line= 3
      2226710.75     13859046.09      2226718.56     13858465.34
      2226638.17     13858058.21
#Sta/Elev= 30
  4529.3  910.93  4550.4  909.19  4580.4  901.19  4620.4  893.44  4700.4  884.28
  4800.4  875.66  4830.4  868.72  4860.4  866.96  4880.4  868.32  4950.4  862.59
  4990.4  852.04  5000.4  848.48  5008.4  842.95  5008.7  842.45  5012.4  842.95
  5050.4  853.55  5080.4  857.93  5150.2  864.23    5192  864.75  5212.4  867.47
  5273.5  871.87  5309.2  877.14  5344.9  883.12  5355.1  885.46  5360.5  888.49
  5406.1  897.98  5416.9  901.46  5463.1  911.08    5508  918.76  5525.1  925.06
#Mann= 3 ,-1 , 0
  4529.3     .12       0  5008.4     .05       0  5012.4     .12       0
Bank Sta=5008.4,5012.4
XS Rating Curve= 0 ,0
Exp/Cntr=0.3,0.1

Type RM Length L Ch R = 1 ,7047    ,224,224,224
BEGIN DESCRIPTION:
E20740
END DESCRIPTION:
XS GIS Cut Line= 3
      2226890.43     13859059.13       2226929.5     13858491.38
      2227028.23      13858028.9
#Sta/Elev= 30
  4515.1  904.74  4529.3  904.14  4539.3  901.37  4589.4  894.07  4679.6  884.87
  4749.8  881.62  4802.5  876.22    4830  869.73  4900.1   857.1  4980.3  853.95
  4990.4  852.19  5008.4  838.87  5008.7  838.37  5012.4  838.87  5030.4  844.49
  5060.5  848.43  5084.2  856.65    5114  859.77    5180  865.75  5223.6  867.55
  5229.5  864.99  5254.3  865.27  5264.5  866.09  5275.5  871.83    5279  872.26
    5285  877.04  5372.9  900.32  5448.6  915.86  5489.5  928.81  5557.1  942.24
#Mann= 5 ,-1 , 0
  4515.1     .12       0  5008.4     .05       0  5012.4     .12       0
    5114    .035       0  5275.5     .12       0
Bank Sta=5008.4,5012.4
XS Rating Curve= 0 ,0
Exp/Cntr=0.3,0.1

Type RM Length L Ch R = 1 ,6823    ,273,273,273
BEGIN DESCRIPTION:
E20739
END DESCRIPTION:
XS GIS Cut Line= 3
      2227005.02     13859027.86      2227135.23     13858650.24
        2227117.     13858035.65
#Sta/Elev= 30
  4475.1  886.37  4486.9  885.64  4492.2  884.13  4580.5  880.95    4617  877.39
  4668.5  874.81  4710.8  866.24  4736.5  864.36  4824.9  851.16  4869.4  848.21
  4879.8  849.27  4929.8  846.66  4959.8  842.69  4979.8  842.28  4997.8   836.4
  4998.1   835.9  5001.8   836.4  5002.9  836.41  5009.8  836.44  5039.8  849.07
  5149.9  864.45  5189.9  873.33  5209.9  876.24  5235.5   883.6    5270  891.29
    5290  897.09    5370  913.81    5420  929.93    5460  939.32  5489.4   944.6
#Mann= 5 ,-1 , 0
  4475.1     .12       0  4997.8     .05       0  5001.8     .12       0
  5002.9    .035       0  5235.5     .12       0
Bank Sta=4997.8,5001.8
XS Rating Curve= 0 ,0
Exp/Cntr=0.3,0.1

Type RM Length L Ch R = 1 ,6550    ,217,217,217
BEGIN DESCRIPTION:
E20738
END DESCRIPTION:
XS GIS Cut Line= 3
      2227450.34     13859147.66      2227356.58     13858493.99
       2227174.3     13858035.67
#Sta/Elev= 30
  4464.3  894.21  4517.4  888.63  4547.8  885.02  4681.1   876.4  4850.9  853.82
  4921.6  846.16  4958.3  844.71  4982.2   838.5  5012.5   833.1  5028.9  834.03
  5040.8  832.74  5041.1  832.24  5044.8  832.74    5063  839.21  5073.1  841.11
  5168.6     845  5243.6  850.07  5308.4  860.75  5338.8  868.76  5386.6  878.22
    5408   884.7  5470.3  900.33  5489.2  903.37  5500.2  907.46  5543.1  915.32
  5572.8  926.18  5578.2   929.3  5597.1  932.81  5607.9   937.3  5617.9  939.26
#Mann= 7 ,-1 , 0
  4464.3    .063       0  4517.4     .12       0  5040.8     .05       0
  5044.8     .12       0  5168.6     .07       0  5243.6    .035       0
    5408     .12       0
Bank Sta=5040.8,5044.8
XS Rating Curve= 0 ,0
Exp/Cntr=0.3,0.1

Type RM Length L Ch R = 1 ,6333    ,246,246,246
BEGIN DESCRIPTION:
E20737
END DESCRIPTION:
XS GIS Cut Line= 2
      2227762.83     13858939.29      2227296.68     13857980.95
#Sta/Elev= 30
  4512.2  889.02  4574.6   884.1  4633.4  880.13  4672.7  875.38  4723.6  865.52
  4881.4  842.53  4917.3  839.82    4984   838.1  4994.2  836.03  5006.3   830.9
  5026.5  828.34  5026.8  827.84  5030.5  828.34  5039.3  828.66  5050.7  833.82
  5067.4  836.72  5108.9  839.77  5173.1  845.36  5225.2  853.63    5338  867.41
  5363.4  871.96  5385.3  874.66  5428.2  882.51  5433.8  885.82  5450.8  888.58
  5473.3  894.94  5484.4   900.2    5540  916.74  5569.1  929.87  5577.9  931.68
#Mann= 7 ,-1 , 0
  4512.2    .063       0  4574.6     .12       0  5026.5     .05       0
  5030.5     .12       0  5108.9     .07       0  5363.4    .035       0
  5385.3     .12       0
Bank Sta=5026.5,5030.5
XS Rating Curve= 0 ,0
Exp/Cntr=0.3,0.1

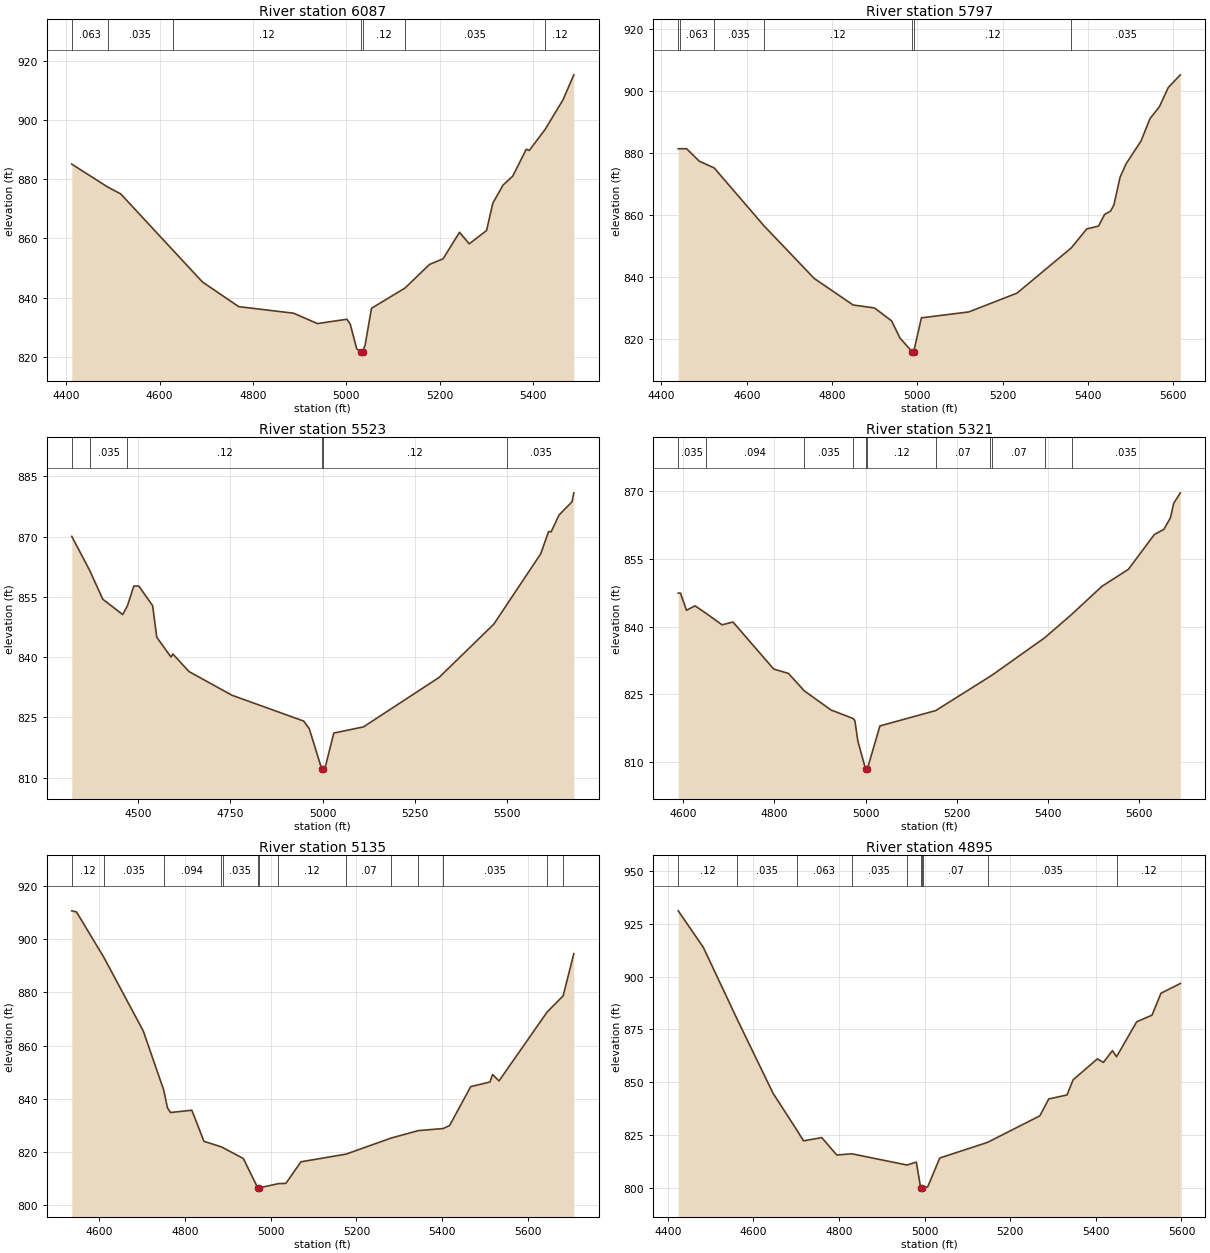
Type RM Length L Ch R = 1 ,6087    ,290,290,290
BEGIN DESCRIPTION:
E20736
END DESCRIPTION:
XS GIS Cut Line= 3
      2227908.68     13858884.65      2227697.73      13858249.2
      2227448.85     13857927.73
#Sta/Elev= 30
  4411.7  885.04  4488.5  877.34  4516.7  874.99  4628.2  856.06  4691.9  845.27
  4769.6  836.96  4887.2  834.75  4938.2  831.25  5001.4  832.71  5008.6  831.03
  5022.5  822.71    5031  821.78  5031.2  821.28    5035  821.78  5040.3  823.91
  5054.1  836.41  5125.8  843.22  5178.5  851.21  5207.5   853.1  5242.8  862.05
  5263.6  858.14  5300.7  862.64  5314.2   871.9    5336  877.96  5356.9     881
  5385.8  890.06  5392.2  889.65  5426.2  896.74  5464.6  906.76  5487.8  915.17
#Mann= 7 ,-1 , 0
  4411.7    .063       0  4488.5    .035       0  4628.2     .12       0
    5031     .05       0    5035     .12       0  5125.8    .035       0
  5426.2     .12       0
Bank Sta=5031,5035
XS Rating Curve= 0 ,0
Exp/Cntr=0.3,0.1

Type RM Length L Ch R = 1 ,5797    ,274,274,274
BEGIN DESCRIPTION:
E20735
END DESCRIPTION:
XS GIS Cut Line= 3
      2228007.62     13858884.56      2227971.17     13858217.95
      2227641.56     13857828.65
#Sta/Elev= 30
  4439.3  881.25  4442.9  881.25  4458.9  881.26  4488.9  877.22  4523.6  875.08
  4640.3  856.43  4758.2  839.46  4849.5  830.89  4899.6  829.94  4939.6   825.8
  4959.6  820.22  4987.7  815.88  4987.9  815.38  4991.7  815.88  5009.7  826.75
  5120.8  828.66  5233.9  834.71  5361.3   849.3  5397.6  855.41  5425.2  856.33
  5439.3  860.05  5453.6  861.19  5461.3  863.17  5475.6  872.03  5489.9  876.43
    5525  883.78  5545.9  890.97  5567.9  894.78  5588.7  900.97    5617  905.07
#Mann= 7 ,-1 , 0
  4439.3    .035       0  4442.9    .063       0  4523.6    .035       0
  4640.3     .12       0  4987.7     .05       0  4991.7     .12       0
  5361.3    .035       0
Bank Sta=4987.7,4991.7
XS Rating Curve= 0 ,0
Exp/Cntr=0.3,0.1

Type RM Length L Ch R = 1 ,5523    ,202,202,202
BEGIN DESCRIPTION:
E20734
END DESCRIPTION:
XS GIS Cut Line= 3
      2228348.76     13858939.26      2228192.52     13858230.97
      2227739.72     13857783.38
#Sta/Elev= 30
  4319.5  870.05  4368.1  861.58  4403.6  854.41  4457.6  850.59  4470.5  852.78
  4487.7  857.66  4501.3  857.69  4538.9   852.8  4550.1  844.94  4588.6  840.01
  4593.8  840.77  4637.5   836.4    4754   830.5  4948.5  824.08  4963.8  822.17
  4997.7  812.11    4998  811.61  5001.7  812.11  5007.5  812.75  5030.4  821.09
    5111  822.63    5316  834.94  5464.5  848.21  5501.1  853.25  5591.7  865.72
    5613  871.26    5620  871.19  5641.3  875.36  5676.6  878.67  5681.5  880.89
#Mann= 6 ,-1 , 0
  4319.5     .12       0  4368.1    .035       0  4470.5     .12       0
  4997.7     .05       0  5001.7     .12       0  5501.1    .035       0
Bank Sta=4997.7,5001.7
XS Rating Curve= 0 ,0
Exp/Cntr=0.3,0.1

Type RM Length L Ch R = 1 ,5321    ,186,186,186
BEGIN DESCRIPTION:
E20733
END DESCRIPTION:
XS GIS Cut Line= 3
      2228525.86      13858559.1      2228356.58     13858139.82
      2227833.18     13857757.03
#Sta/Elev= 30
  4589.3  847.47  4594.2  847.47  4607.4  843.66  4626.1  844.65  4650.6  842.97
  4685.2  840.44  4709.4  841.05  4798.6  830.63    4831  829.66  4865.4  825.82
  4924.1  821.56  4972.8  819.66  4976.6  819.17  4983.1  814.63  4999.9   808.5
  5000.1     808  5003.9   808.5  5031.4  818.02  5153.8  821.43  5273.3  829.03
  5277.9  829.33  5392.8  837.58  5451.7  842.74  5517.9  848.96  5576.1  852.74
    5633  860.46  5653.8  861.59  5668.5  864.21  5675.3  867.36  5689.9   869.7
#Mann= 11 ,-1 , 0
  4589.3    .035       0  4650.6    .094       0  4865.4    .035       0
  4972.8     .12       0  4999.9     .05       0  5003.9     .12       0
  5153.8     .07       0  5273.3     .12       0  5277.9     .07       0
  5392.8     .12       0  5451.7    .035       0
Bank Sta=4999.9,5003.9
XS Rating Curve= 0 ,0
Exp/Cntr=0.3,0.1

Type RM Length L Ch R = 1 ,5135    ,240,240,240
BEGIN DESCRIPTION:
E20732
END DESCRIPTION:
XS GIS Cut Line= 3
      2228809.69     13858355.94      2228434.71     13857991.38
      2228072.75     13857454.96
#Sta/Elev= 30
  4536.5   910.6  4547.5  910.19  4611.2  893.15  4703.1  865.51  4750.8  843.28
  4759.7  836.55  4766.7  834.86  4816.3  835.72  4844.6  824.03  4884.4     822
  4888.8  821.65  4936.4  817.58  4969.9  806.59  4970.2  806.09  4973.9  806.59
  5017.9  808.15  5035.5  808.26  5070.6  816.35  5175.6  819.23  5280.9  825.27
  5344.3  828.07  5402.1  828.84    5417  829.97  5466.3  844.58  5511.2  846.33
  5517.2  849.15  5532.2  846.72  5644.3  872.59  5681.6  878.67  5706.6  894.53
#Mann= 14 ,-1 , 0
  4536.5     .12       0  4611.2    .035       0  4750.8    .094       0
  4884.4    .063       0  4888.8    .035       0  4969.9    .035       0
  4973.9    .035       0  5017.9     .12       0  5175.6     .07       0
  5280.9    .035       0  5344.3     .07       0  5402.1    .035       0
  5644.3     .12       0  5681.6    .035       0
Bank Sta=4969.9,4973.9
XS Rating Curve= 0 ,0
Exp/Cntr=0.3,0.1

Type RM Length L Ch R = 1 ,4895    ,194,194,194
BEGIN DESCRIPTION:
E20731
END DESCRIPTION:
XS GIS Cut Line= 3
      2228965.99     13858197.14       2228554.5     13857827.32
      2228097.22     13857409.02
#Sta/Elev= 30
  4424.3  931.13    4483  913.83  4562.1  879.79    4646  844.75  4700.8   827.6
    4717   822.3  4759.6  823.85  4794.7   815.6  4829.8  816.18  4958.8  810.87
  4980.6  812.24  4990.8  799.96  4991.1  799.46  4994.8  799.96  4996.3  800.17
    5007  800.48  5035.4  814.19    5147  821.59  5269.1  834.13    5290  842.12
  5332.6  844.01  5346.8  851.18  5403.5  861.08  5417.7  859.42  5438.7  864.99
  5448.3  862.09  5495.4  878.64  5531.2  881.78  5552.1  892.13  5597.3  896.75
#Mann= 10 ,-1 , 0
  4424.3     .12       0  4562.1    .035       0  4700.8    .063       0
  4829.8    .035       0  4958.8     .12       0  4990.8     .05       0
  4994.8     .12       0  4996.3     .07       0    5147    .035       0
  5448.3     .12       0
Bank Sta=4990.8,4994.8
XS Rating Curve= 0 ,0
Exp/Cntr=0.3,0.1

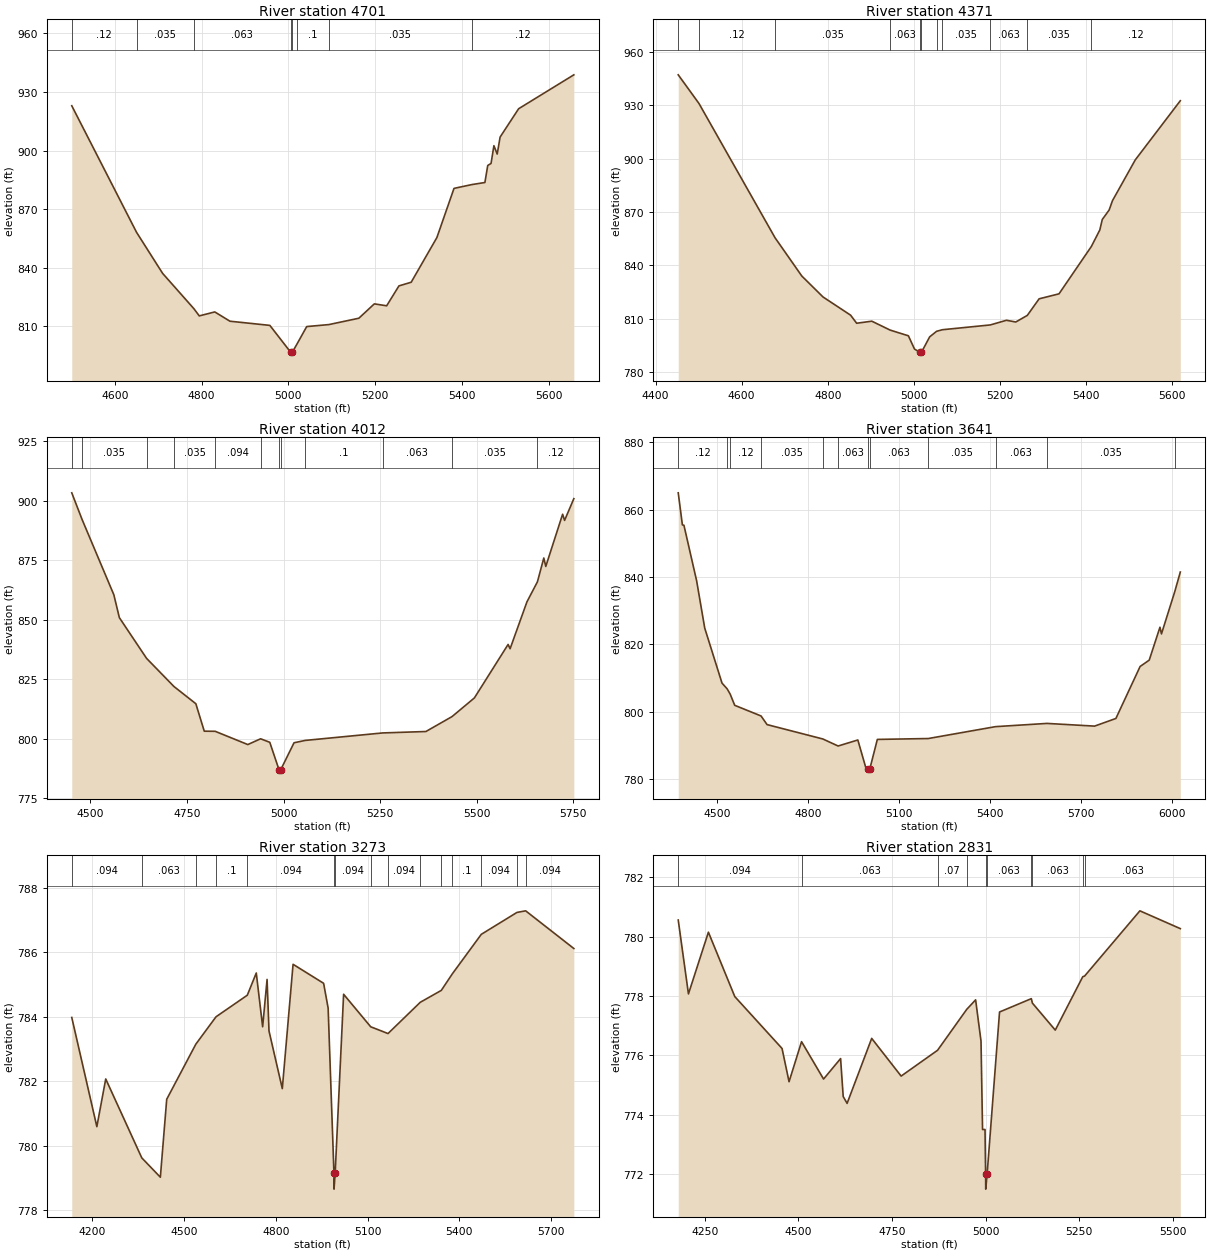
Type RM Length L Ch R = 1 ,4701    ,330,330,330
BEGIN DESCRIPTION:
E20730
END DESCRIPTION:
XS GIS Cut Line= 3
      2229059.71     13858046.07      2228445.13     13857475.76
      2228205.57     13857264.85
#Sta/Elev= 30
  4500.7  922.97  4650.1  858.14  4710.2  837.12  4782.3  819.03  4794.7  815.35
  4830.4  817.38  4865.5  812.62  4957.4  810.49  5005.3  796.78  5005.5  796.28
  5009.3  796.78  5019.5  800.75  5042.4  809.88  5093.5   810.9  5162.6  814.15
  5198.3  821.51  5226.7  820.52    5255   830.7  5283.3  832.59  5342.5  855.46
    5382  880.65  5423.2   882.6  5453.2  883.66  5459.8   892.4  5467.4  893.41
    5474  902.51  5481.6  898.24  5488.3  906.94    5531  921.44  5658.3  938.81
#Mann= 8 ,-1 , 0
  4500.7     .12       0  4650.1    .035       0  4782.3    .063       0
  5005.3     .05       0  5009.3    .063       0  5019.5      .1       0
  5093.5    .035       0  5423.2     .12       0
Bank Sta=5005.3,5009.3
XS Rating Curve= 0 ,0
Exp/Cntr=0.3,0.1

Type RM Length L Ch R = 1 ,4371    ,359,359,359
BEGIN DESCRIPTION:
E20729
END DESCRIPTION:
XS GIS Cut Line= 3
      2229294.08     13857871.59      2228861.79     13857405.45
      2228372.57     13857199.87
#Sta/Elev= 30
  4452.8  946.98    4501  930.89  4677.7  855.54  4739.8  834.08  4789.1  822.31
  4853.2  812.09  4867.3  807.56  4902.5  808.71    4945  803.72  4987.5  800.51
  5001.7  793.07  5013.9  791.28  5014.1  790.78  5017.9  791.28  5036.9  799.91
    5053  803.03  5066.7  803.92  5177.7   806.6  5215.2  809.21    5237  808.25
  5263.8  811.97  5291.2  821.26  5337.4  824.06  5412.6  850.66  5432.2  859.91
  5437.9  865.77  5453.9  871.12  5461.6  876.35  5514.6  899.25  5619.2  932.44
#Mann= 11 ,-1 , 0
  4452.8    .063       0    4501     .12       0  4677.7    .035       0
    4945    .063       0  5013.9     .05       0  5017.9    .063       0
    5053      .1       0  5066.7    .035       0  5177.7    .063       0
  5263.8    .035       0  5412.6     .12       0
Bank Sta=5013.9,5017.9
XS Rating Curve= 0 ,0
Exp/Cntr=0.3,0.1

Type RM Length L Ch R = 1 ,4012    ,371,371,371
BEGIN DESCRIPTION:
E20728
END DESCRIPTION:
XS GIS Cut Line= 3
       2229502.4     13857621.57      2229143.04     13857217.95
      2228400.87     13857053.89
#Sta/Elev= 30
  4451.5  903.27  4478.2  892.08  4560.5  860.44  4574.8  850.83  4645.3  833.73
  4716.1  821.93  4772.9  814.68  4794.7  803.15  4822.9   803.1  4907.5  797.53
  4940.6  799.95  4964.4  798.48  4988.5  786.87  4988.8  786.37  4992.5  786.87
  5027.2  798.28  5056.3  799.27  5256.7  802.41  5368.8  803.01  5436.6  809.29
  5494.4  817.12  5581.7  839.58  5586.9  837.78  5630.5  857.47  5657.7   865.9
  5674.2   875.9  5679.3  872.35  5722.9  894.28    5728  891.69    5752  900.83
#Mann= 12 ,-1 , 0
  4451.5     .12       0  4478.2    .035       0  4645.3     .12       0
  4716.1    .035       0  4822.9    .094       0  4940.6    .063       0
  4988.5     .05       0  4992.5    .063       0  5056.3      .1       0
  5256.7    .063       0  5436.6    .035       0  5657.7     .12       0
Bank Sta=4988.5,4992.5
XS Rating Curve= 0 ,0
Exp/Cntr=0.3,0.1

Type RM Length L Ch R = 1 ,3641    ,368,368,368
BEGIN DESCRIPTION:
E20727
END DESCRIPTION:
XS GIS Cut Line= 4
      2229603.99     13857520.06      2229478.98      13857001.8
      2229320.13     13856908.05      2228382.58     13856845.55
#Sta/Elev= 30
    4371  865.03  4384.7  855.51  4389.8   855.4  4431.7  838.91  4458.5  824.84
  4515.5  808.51  4532.4  806.82  4542.5  805.24  4557.4  801.92  4644.4  798.75
  4664.2  796.19  4848.3  791.92  4898.7  789.83  4963.8  791.62  4991.1   783.1
  4998.9  782.87  4999.2  782.37  5002.9  782.87  5028.2  791.79  5196.2  792.05
  5418.2  795.58  5588.2  796.54  5745.2  795.74  5815.6  798.01  5895.5  813.45
  5925.6  815.34    5961  825.11    5966  823.13  6009.5  835.56  6028.2   841.5
#Mann= 12 ,-1 , 0
    4371     .12       0  4532.4    .035       0  4542.5     .12       0
  4644.4    .035       0  4848.3    .094       0  4898.7    .063       0
  4998.9     .05       0  5002.9    .063       0  5196.2    .035       0
  5418.2    .063       0  5588.2    .035       0  6009.5     .12       0
Bank Sta=4998.9,5002.9
XS Rating Curve= 0 ,0
Exp/Cntr=0.3,0.1

Type RM Length L Ch R = 1 ,3273    ,442,442,442
BEGIN DESCRIPTION:
E20726
END DESCRIPTION:
XS GIS Cut Line= 5
       2230346.6     13857318.75      2229797.36     13856897.91
        2229742.     13856827.32      2229609.19     13856637.22
      2229029.09     13856395.72
#Sta/Elev= 30
  4132.3  783.98  4214.3  780.59  4243.4  782.07  4361.3  779.62    4422  779.02
  4442.8  781.44    4538  783.15    4604     784  4706.3  784.67  4735.7  785.36
  4756.5  783.69    4771  785.16  4777.3  783.56  4820.8  781.77    4856  785.63
  4955.9  785.04  4970.7  784.27  4989.7  779.15  4989.9  778.65  4993.7  779.15
  5021.3   784.7  5109.9  783.69  5166.5  783.48  5271.9  784.45  5340.8  784.82
  5377.3  785.34  5471.5  786.56  5588.1  787.24  5616.6  787.29  5774.2  786.12
#Mann= 15 ,-1 , 0
  4132.3    .094       0  4361.3    .063       0    4538    .094       0
    4604      .1       0  4706.3    .094       0  4989.7     .05       0
  4993.7    .094       0  5109.9    .063       0  5166.5    .094       0
  5271.9      .1       0  5340.8    .094       0  5377.3      .1       0
  5471.5    .094       0  5588.1      .1       0  5616.6    .094       0
Bank Sta=4989.7,4993.7
XS Rating Curve= 0 ,0
Exp/Cntr=0.3,0.1

Type RM Length L Ch R = 1 ,2831    ,445,445,445
BEGIN DESCRIPTION:
Sattler Tributary 6.0
END DESCRIPTION:
XS GIS Cut Line= 4
      2230409.55     13857301.42      2230291.87     13856852.56
        2230075.       13856575.      2229713.98     13856193.51
#Sta/Elev= 30
    4179  780.56  4206.3  778.07  4259.6  780.15  4330.1  777.98  4456.4  776.23
  4475.1  775.11  4508.5  776.46  4567.3   775.2  4612.8  775.89  4619.8  774.61
  4630.2  774.38  4695.9  776.57  4774.6   775.3  4871.9  776.17  4949.9  777.55
  4973.6  777.87    4988  776.48  4992.1   773.5  4998.7   773.5  5000.3  771.99
  5000.6  771.49  5004.3  771.99  5037.5  777.46  5122.4  777.91  5125.3  777.76
  5186.4  776.85  5259.9  778.65  5264.7  778.67  5412.5  780.87  5520.5  780.27
#Mann= 10 ,-1 , 0
    4179    .094       0  4508.5    .063       0  4871.9     .07       0
  4949.9    .063       0  5000.3     .05       0  5004.3    .063       0
  5122.4    .094       0  5125.3    .063       0  5259.9     .07       0
  5264.7    .063       0
Bank Sta=5000.3,5004.3
XS Rating Curve= 0 ,0
Exp/Cntr=0.3,0.1

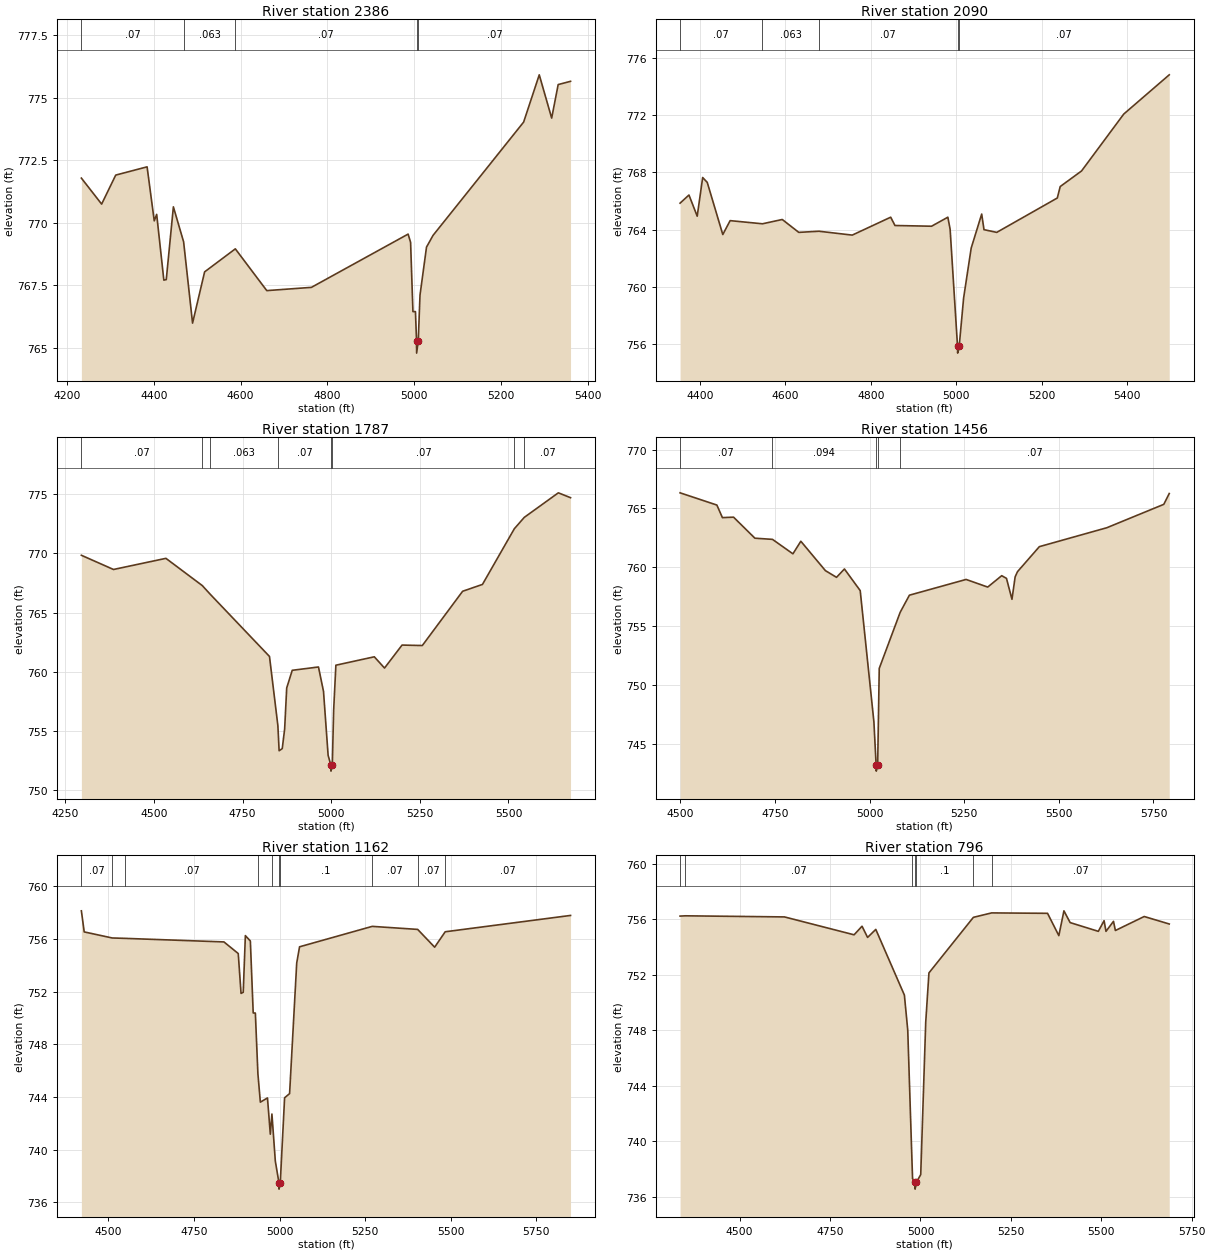
Type RM Length L Ch R = 1 ,2386    ,296,296,296
BEGIN DESCRIPTION:
Sattler Tributary 5.0
END DESCRIPTION:
XS GIS Cut Line= 3
      2230779.57     13857005.22        2230425.       13856325.
      2230125.03     13856125.02
#Sta/Elev= 30
  4232.9  771.79  4279.6  770.75  4312.1  771.91  4384.4  772.24  4400.9  770.08
  4406.5  770.34    4423  767.71  4428.6  767.73    4445  770.64  4468.6  769.24
  4489.2  765.99    4517  768.04  4587.8  768.96  4660.3  767.29  4763.2  767.42
  4986.1  769.55  4991.8  769.22  4997.2  766.45    5003  766.45  5005.5  765.29
  5005.7  764.79  5009.5  765.29  5013.5  767.11  5028.5  769.03  5043.6   769.5
  5252.4  774.03  5288.4  775.92    5317  774.19    5332  775.53  5360.5  775.66
#Mann= 5 ,-1 , 0
  4232.9     .07       0  4468.6    .063       0  4587.8     .07       0
  5005.5     .05       0  5009.5     .07       0
Bank Sta=5005.5,5009.5
XS Rating Curve= 0 ,0
Exp/Cntr=0.3,0.1

Type RM Length L Ch R = 1 ,2090    ,303,303,303
BEGIN DESCRIPTION:
E20725
END DESCRIPTION:
XS GIS Cut Line= 3
      2230905.59     13856784.33      2230643.41     13856103.99
      2230364.64     13855795.35
#Sta/Elev= 30
  4353.4  765.85  4374.2  766.42  4393.5  764.94  4406.3  767.64    4417   767.3
  4453.4  763.66  4470.6  764.63  4546.3  764.41  4592.6  764.71  4631.3  763.81
  4678.4  763.89  4756.4  763.62  4846.4  764.87  4856.4  764.29  4942.1  764.24
  4980.2  764.87  4985.5  764.03  5002.8  755.88  5003.1  755.38  5006.8  755.88
  5017.1  759.23  5034.8  762.71  5059.4  765.09  5064.8     764  5094.6  763.81
  5236.4  766.21  5243.2  767.01  5293.2   768.1  5391.9  772.07  5498.4  774.81
#Mann= 5 ,-1 , 0
  4353.4     .07       0  4546.3    .063       0  4678.4     .07       0
  5002.8     .05       0  5006.8     .07       0
Bank Sta=5002.8,5006.8
XS Rating Curve= 0 ,0
Exp/Cntr=0.3,0.1

Type RM Length L Ch R = 1 ,1787    ,331,331,331
BEGIN DESCRIPTION:
E20724
END DESCRIPTION:
XS GIS Cut Line= 3
      2231263.99     13856601.76      2230882.36     13855961.29
      2230391.33     13855559.84
#Sta/Elev= 30
  4295.3  769.85  4385.9  768.65  4533.8  769.59  4636.4  767.29  4658.1  766.58
  4825.9  761.31  4849.6  755.47  4853.1  753.35  4861.9  753.53  4868.7  755.18
  4874.5  758.65  4890.1  760.14  4964.1  760.42  4978.3  758.36  4991.3  752.97
  4999.1  752.13  4999.3  751.63  5003.1  752.13  5006.9  756.76  5013.2  760.57
  5121.6  761.28  5150.4  760.33  5199.9  762.27    5257  762.23  5370.7  766.81
  5426.7  767.39  5516.6  772.09  5544.7  773.05  5640.7  775.12  5675.1  774.71
#Mann= 8 ,-1 , 0
  4295.3     .07       0  4636.4    .094       0  4658.1    .063       0
  4849.6     .07       0  4999.1     .05       0  5003.1     .07       0
  5516.6    .063       0  5544.7     .07       0
Bank Sta=4999.1,5003.1
XS Rating Curve= 0 ,0
Exp/Cntr=0.3,0.1

Type RM Length L Ch R = 1 ,1456    ,294,294,294
BEGIN DESCRIPTION:
E20723
END DESCRIPTION:
XS GIS Cut Line= 3
       2231506.3      13856329.7      2231147.86     13855835.18
      2230598.44     13855431.39
#Sta/Elev= 30
  4499.1  766.33  4596.3  765.29    4611  764.22  4640.4  764.26  4696.8  762.47
  4743.3  762.37  4797.3  761.14  4818.2  762.21  4883.1  759.71  4912.5  759.14
  4933.4  759.85  4975.1  758.01  5011.3  746.84  5017.2  743.15  5017.5  742.65
  5021.2  743.15  5025.4  751.39  5080.8  756.17  5105.1  757.62  5254.9  758.96
    5312  758.31    5349  759.28  5361.6  759.05  5376.1  757.27  5384.5  759.18
  5390.7  759.62  5448.5  761.75  5626.8  763.36  5777.3  765.35  5791.7  766.27
#Mann= 5 ,-1 , 0
  4499.1     .07       0  4743.3    .094       0  5017.2     .05       0
  5021.2    .094       0  5080.8     .07       0
Bank Sta=5017.2,5021.2
XS Rating Curve= 0 ,0
Exp/Cntr=0.3,0.1

Type RM Length L Ch R = 1 ,1162    ,366,366,366
BEGIN DESCRIPTION:
E20722
END DESCRIPTION:
XS GIS Cut Line= 3
      2231887.93     13856094.03      2231220.87     13855592.91
      2230729.83     13855257.81
#Sta/Elev= 30
  4421.2  758.13  4429.5  756.53  4511.2  756.07  4549.1  756.04  4837.6  755.77
  4879.4  754.89  4887.6  751.86    4894  751.95  4900.2  756.25  4914.8  755.84
  4923.1  750.38  4929.4  750.37  4936.8  745.78    4944  743.61  4964.8  743.93
  4973.1  741.18  4977.8  742.71  4987.7  739.14  4998.2  737.51  4998.5  737.01
  5002.2  737.51  5014.8  743.94  5029.4  744.26  5050.2  754.17  5058.5   755.4
  5270.7  756.95  5403.5  756.72  5453.1  755.37  5483.9  756.54    5850  757.78
#Mann= 10 ,-1 , 0
  4421.2     .07       0  4511.2    .094       0  4549.1     .07       0
  4936.8    .094       0  4977.8      .1       0  4998.2     .05       0
  5002.2      .1       0  5270.7     .07       0  5403.5     .07       0
  5483.9     .07       0
Bank Sta=4998.2,5002.2
XS Rating Curve= 0 ,0
Exp/Cntr=0.3,0.1

Type RM Length L Ch R = 1 ,796     ,381,381,381
BEGIN DESCRIPTION:
E20721
END DESCRIPTION:
XS GIS Cut Line= 3
      2232123.56     13855725.66      2231469.77     13855380.51
      2230889.53     13855181.57
#Sta/Elev= 30
  4335.3  756.24    4350  756.26    4624  756.18  4816.5  754.89  4838.5  755.51
  4853.8   754.7  4876.5  755.28  4955.6  750.54  4964.9  748.01  4975.8  739.19
  4978.2   737.3    4985  737.04  4985.2  736.54    4989  737.04  5000.8  737.59
  5014.6  748.58  5023.5  752.14  5146.4  756.15  5196.9  756.47  5351.5  756.44
  5382.7  754.83  5396.8  756.62    5414  755.77  5491.9  755.14  5507.8  755.91
  5513.1  755.14  5533.8  755.86  5539.1   755.2  5618.8  756.21    5688  755.67
#Mann= 7 ,-1 , 0
  4335.3    .063       0    4350     .07       0  4975.8      .1       0
    4985     .05       0    4989      .1       0  5146.4     .07       0
  5196.9     .07       0
Bank Sta=4985,4989
XS Rating Curve= 0 ,0
Exp/Cntr=0.3,0.1

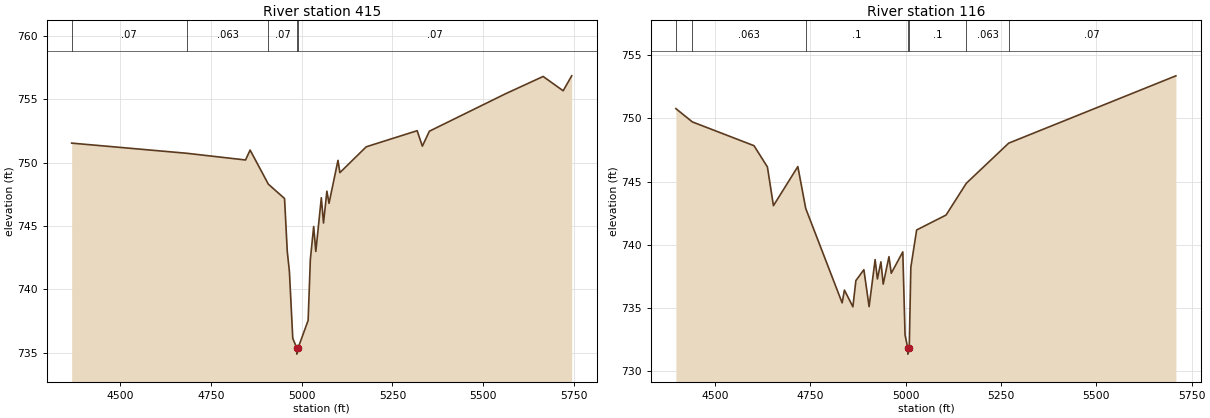
Type RM Length L Ch R = 1 ,415     ,299,299,299
BEGIN DESCRIPTION:
E20720
END DESCRIPTION:
XS GIS Cut Line= 3
      2232209.81     13855430.27      2231605.84     13855045.32
      2230969.35     13854862.99
#Sta/Elev= 30
  4365.8  751.55  4682.5  750.75    4845  750.22  4857.7     751    4908  748.31
  4952.6  747.18  4960.1  743.01    4966  741.42  4975.3  736.14  4986.1   735.4
  4986.4   734.9  4990.1   735.4  5017.6  737.56  5023.7  742.36  5032.9  744.97
  5038.8     743    5054  747.24    5060  745.25  5069.3  747.76  5075.2   746.8
  5099.9  750.19  5105.1  749.22  5177.8  751.26  5318.1  752.53  5332.5  751.31
  5351.8  752.49  5561.4  755.44  5665.4  756.81  5720.6  755.68  5744.1  756.86
#Mann= 5 ,-1 , 0
  4365.8     .07       0  4682.5    .063       0    4908     .07       0
  4986.1     .05       0  4990.1     .07       0
Bank Sta=4986.1,4990.1
XS Rating Curve= 0 ,0
Exp/Cntr=0.3,0.1

Type RM Length L Ch R = 1 ,116     ,0,0,0
BEGIN DESCRIPTION:
E20719
END DESCRIPTION:
XS GIS Cut Line= 4
      2232133.53     13855300.89      2231851.43     13854879.39
      2231682.17     13854769.87      2231079.79     13854750.01
#Sta/Elev= 30
  4397.2  750.77  4440.3  749.72  4602.1  747.84  4637.3  746.16  4653.1   743.1
  4717.1  746.19  4737.8  742.88  4833.3  735.42  4839.3  736.43  4861.5  735.11
  4869.3  737.18  4890.3  738.04    4904  735.12  4919.8  738.84  4925.8  737.31
    4935  738.66    4941   736.9  4956.1  739.07  4962.1  737.76  4992.4  739.45
  4998.3  732.88  5005.3  731.87  5005.6  731.37  5009.3  731.87  5013.5  738.24
  5028.7  741.18  5105.9  742.36    5159  744.87  5270.1  748.04  5708.7  753.36
#Mann= 7 ,-1 , 0
  4397.2     .07       0  4440.3    .063       0  4737.8      .1       0
  5005.3     .05       0  5009.3      .1       0    5159    .063       0
  5270.1     .07       0
Bank Sta=5005.3,5009.3
XS Rating Curve= 0 ,0
Exp/Cntr=0.3,0.1

Chan Stop Cuts=-1
Use User Specified Reach Order=0
Composite Channel Slope=5