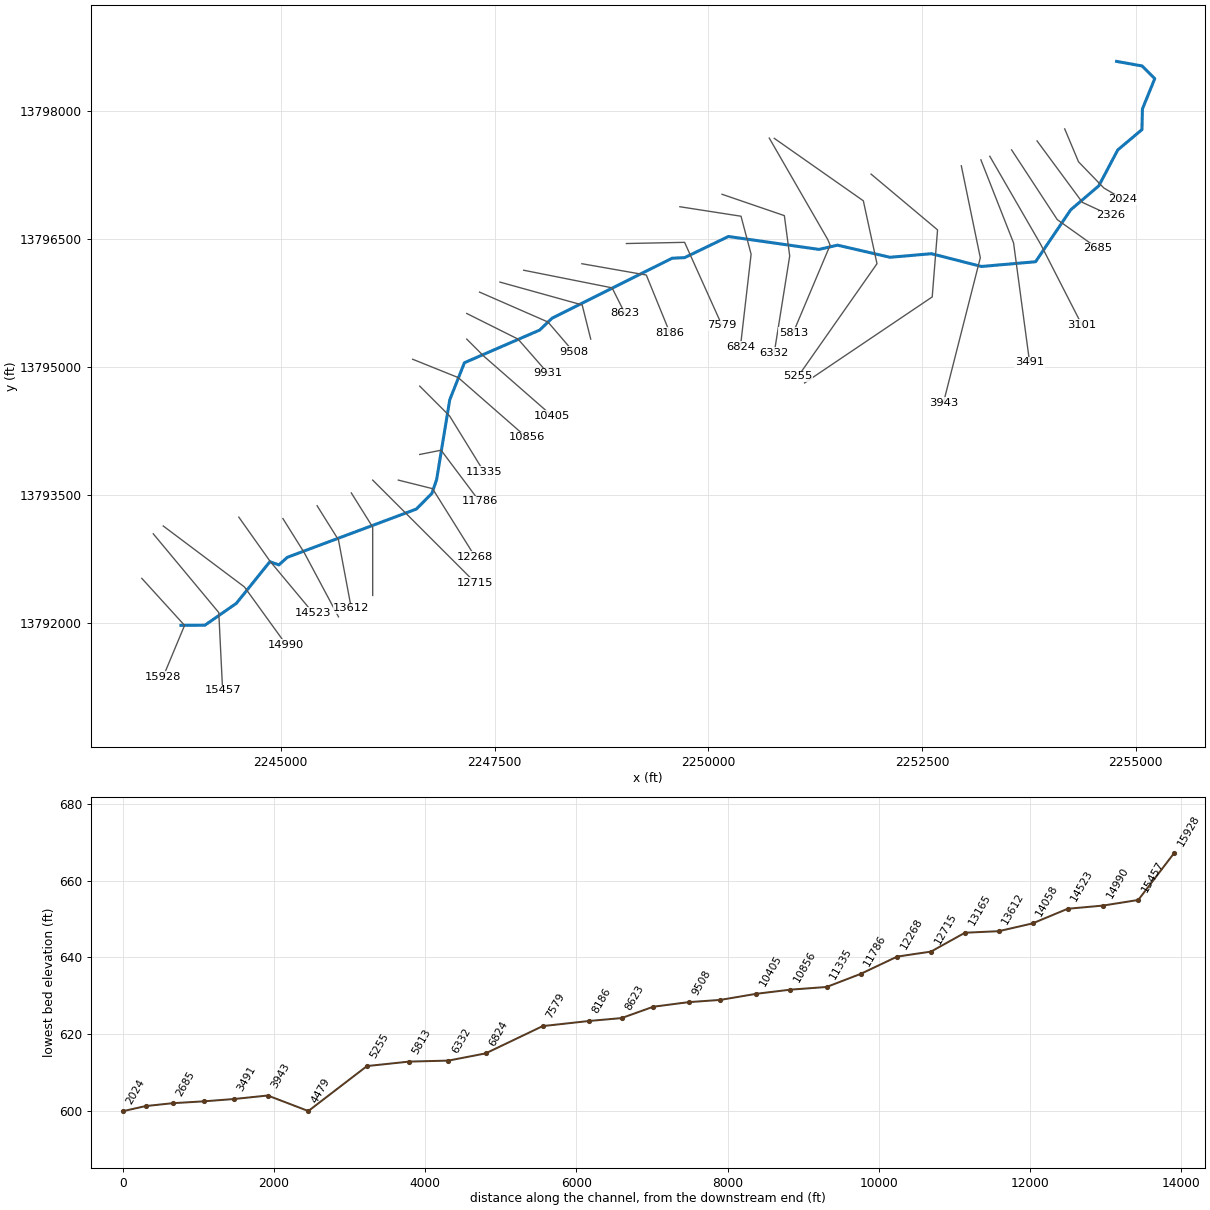
--- South Guadalupe Tributary.prj (project) ---

Proj Title=South Guadalupe Tributary Base Level Engineering
Current Plan=p01
Default Exp/Contr=0.3,0.1
English Units
Geom File=g01
Flow File=f01
Plan File=p01
BEGIN DESCRIPTION:
South Guadalupe Tributary
END DESCRIPTION:

--- South Guadalupe Tributary.p01 (plan) ---

Plan Title=Multiple Run
Short Identifier=Multiple
Geom File=g01
Flow File=f01
Subcritical Flow
K Sum by GR= 0
Std Step Tol= 0.01
Critical Tol= 0.01
Num of Std Step Trials= 20
Max Error Tol= 0.3
Flow Tol Ratio= 0.001
Split Flow NTrial= 30
Split Flow Tol= 0.02
Split Flow Ratio= 0.02
Log Output Level= 0
Friction Slope Method= 1
Unsteady Friction Slope Method= 2
Unsteady Bridges Friction Slope Method= 1
Parabolic Critical Depth
Global Vel Dist=  1 , 1 , 1
Global Log Level= 0
CheckData=True
Encroach Param= -1, 0, 0, 0
BEGIN DESCRIPTION:
Multiple Run
END DESCRIPTION:

--- South Guadalupe Tributary.f01 (steady flow) ---

Flow Title=Multiple
Number of Profiles=7
Profile Names=10-year,25-year,50-year,1pct_min,100-year,1pct_plu,500-year
River Rch & RM= South Guadalupe ,Reach-1,15928
     638    1032    1389     907    1809    3609    3031
River Rch & RM= South Guadalupe ,Reach-1,14523
    1136    1896    2606    1732    3455    6894    6013
River Rch & RM= South Guadalupe ,Reach-1,12268
    1368    2291    3153    2096    4182    8344    7285
River Rch & RM= South Guadalupe ,Reach-1,5255
    1499    2509    3453    2293    4576    9130    7957
Boundary for River Rch & Prof#=South Guadalupe ,Reach-1,1
Up Type=0
Dn Type=3
Dn Slope=0.005
Boundary for River Rch & Prof#=South Guadalupe ,Reach-1,2
Up Type=0
Dn Type=3
Dn Slope=0.005
Boundary for River Rch & Prof#=South Guadalupe ,Reach-1,3
Up Type=0
Dn Type=3
Dn Slope=0.005
Boundary for River Rch & Prof#=South Guadalupe ,Reach-1,4
Up Type=0
Dn Type=3
Dn Slope=0.005
Boundary for River Rch & Prof#=South Guadalupe ,Reach-1,5
Up Type=0
Dn Type=3
Dn Slope=0.005
Boundary for River Rch & Prof#=South Guadalupe ,Reach-1,6
Up Type=0
Dn Type=3
Dn Slope=0.005
Boundary for River Rch & Prof#=South Guadalupe ,Reach-1,7
Up Type=0
Dn Type=3
Dn Slope=0.005

--- South Guadalupe Tributary.g01 (geometry) ---

Geom Title=Existing Conditions

River Reach=South Guadalupe ,Reach-1
Reach XY= 30
      2243832.55     13791975.00      2244113.05     13791976.92
      2244481.07     13792233.13      2244872.46     13792719.99
      2244978.40     13792682.84      2245076.47     13792771.43
      2246584.68     13793335.76      2246767.14     13793518.83
      2246822.62     13793680.53      2246976.38     13794615.34
      2247148.11     13795048.74      2248027.43     13795430.52
      2248172.57     13795569.48      2249576.47     13796271.44
      2249723.44     13796278.76      2250235.05     13796525.78
      2251295.10     13796374.91      2251511.03     13796424.45
      2252125.01     13796282.59      2252609.78     13796324.48
      2253195.03     13796175.07      2253827.43     13796230.52
      2254238.62     13796838.24      2254567.14     13797118.83
      2254788.49     13797538.56      2255071.46     13797776.46
      2255077.26     13798019.06      2255221.54     13798373.50
      2255073.54     13798521.46      2254775.00     13798575.00

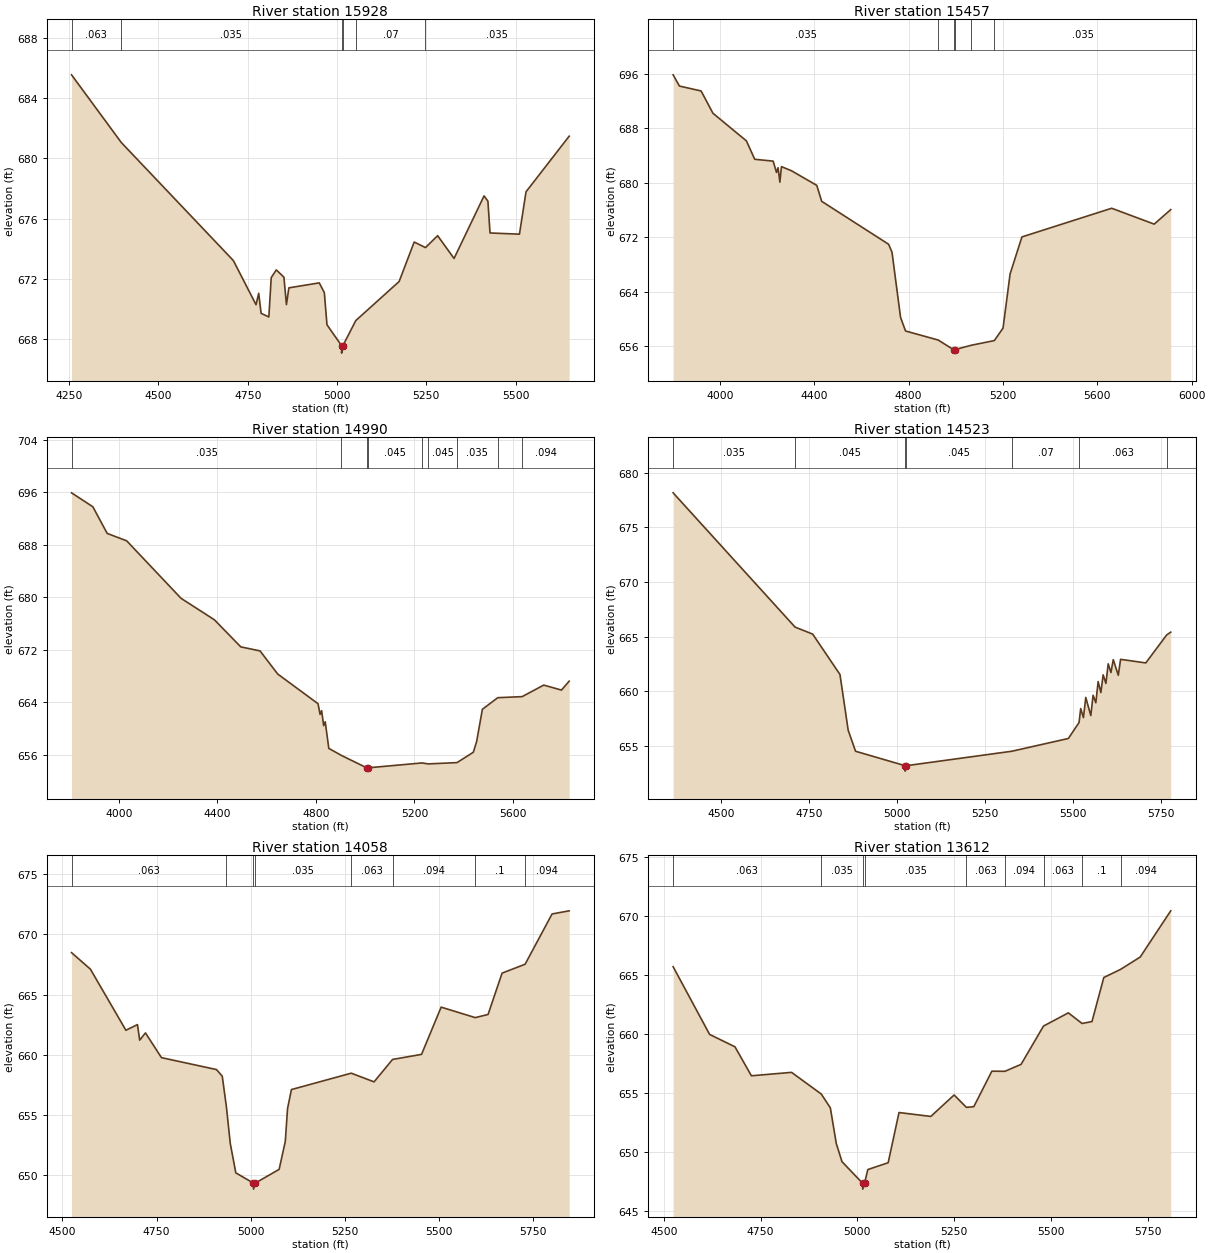
Type RM Length L Ch R = 1,15928,471,471,471
BEGIN DESCRIPTION:
South Guadalupe Tributary 25.0
END DESCRIPTION:
XS GIS Cut Line= 3
      2243375.01     13792524.99      2243875.00     13791975.00
      2243624.99     13791374.99
#Sta/Elev= 30
  4256.7  685.53  4396.0  681.04  4709.8  673.21  4773.3  670.28  4780.7  671.04
  4787.5  669.71  4809.1  669.47  4815.8  672.08  4830.0  672.59  4851.3  672.11
  4858.4  670.29  4865.2  671.40  4950.3  671.73  4964.5  671.08  4971.9  668.95
  5012.6  667.57  5012.9  667.07  5016.6  667.57  5052.6  669.23  5173.9  671.82
  5216.1  674.44  5247.7  674.07  5281.7  674.86  5327.7  673.35  5411.7  677.50
  5422.5  677.15  5428.4  675.04  5510.8  674.96  5529.2  677.77  5650.0  681.46
#Mann=6,-1,0
  4256.7   0.063       0  4396.0   0.035       0  5012.6   0.035       0
  5016.6   0.035       0  5052.6    0.07       0  5247.7   0.035       0
Bank Sta=5012.6,5016.6
Exp/Cntr=0.3,0.1

Type RM Length L Ch R = 1,15457,467,467,467
BEGIN DESCRIPTION:
South Guadalupe Tributary 24.0
END DESCRIPTION:
XS GIS Cut Line= 3
      2243509.15     13793046.26      2244275.00     13792125.00
      2244320.04     13791215.03
#Sta/Elev= 30
  3802.2  695.82  3829.1  694.17  3920.9  693.45  3971.0  690.18  4112.9  686.12
  4148.1  683.42  4226.2  683.15  4240.5  681.48  4247.0  682.18  4254.8  680.06
  4261.3  682.34  4304.3  681.73  4411.1  679.59  4431.9  677.25  4715.7  670.94
  4730.0  669.77  4766.1  660.23  4787.3  658.21  4926.0  656.88  4991.1  655.46
  4991.3  654.96  4995.1  655.46  5065.2  656.11  5163.6  656.80  5200.5  658.63
  5230.5  666.59  5280.6  672.02  5661.0  676.23  5841.2  673.90  5911.3  676.03
#Mann=6,-1,0
  3802.2   0.035       0  4926.0   0.045       0  4991.1   0.045       0
  4995.1   0.045       0  5065.2    0.07       0  5163.6   0.035       0
Bank Sta=4991.1,4995.1
Exp/Cntr=0.3,0.1

Type RM Length L Ch R = 1,14990,467,467,467
BEGIN DESCRIPTION:
South Guadalupe Tributary 23.0
END DESCRIPTION:
XS GIS Cut Line= 3
      2243625.73     13793138.00      2244575.00     13792425.00
      2245062.87     13791749.59
#Sta/Elev= 30
  3808.0  695.94  3894.6  693.81  3952.7  689.75  4031.9  688.62  4252.7  679.85
  4388.0  676.58  4495.0  672.45  4573.4  671.83  4645.0  668.31  4808.8  663.78
  4817.1  662.15  4823.4  662.72  4831.7  660.44  4838.0  661.02  4852.5  656.97
  4903.4  655.90  5006.7  654.00  5007.0  653.50  5010.7  654.00  5231.5  654.75
  5255.9  654.60  5373.1  654.80  5439.3  656.38  5452.8  658.02  5476.0  662.93
  5538.5  664.70  5637.4  664.86  5725.1  666.62  5797.1  665.86  5828.4  667.22
#Mann=9,-1,0
  3808.0   0.035       0  4903.4   0.045       0  5006.7   0.045       0
  5010.7   0.045       0  5231.5   0.035       0  5255.9   0.045       0
  5373.1   0.035       0  5538.5   0.063       0  5637.4   0.094       0
Bank Sta=5006.7,5010.7
Exp/Cntr=0.3,0.1

Type RM Length L Ch R = 1,14523,465,465,465
BEGIN DESCRIPTION:
South Guadalupe Tributary 22.0
END DESCRIPTION:
XS GIS Cut Line= 3
      2244509.46     13793241.66      2244875.00     13792725.00
      2245374.99     13792125.01
#Sta/Elev= 30
  4363.5  678.16  4710.1  665.86  4760.1  665.22  4837.6  661.52  4861.0  656.41
  4881.9  654.49  5022.4  653.17  5022.6  652.67  5026.4  653.17  5325.7  654.49
  5486.5  655.66  5516.9  657.12  5521.6  658.40  5529.4  657.57  5536.0  659.42
  5550.3  657.76  5556.8  659.62  5564.6  658.93  5571.1  660.87  5578.9  659.87
  5585.4  661.49  5593.2  660.70  5599.7  662.50  5607.5  661.70  5614.1  662.88
  5628.4  661.45  5634.9  662.91  5706.5  662.58  5765.8  665.14  5777.4  665.40
#Mann=7,-1,0
  4363.5   0.035       0  4710.1   0.045       0  5022.4   0.045       0
  5026.4   0.045       0  5325.7    0.07       0  5516.9   0.063       0
  5765.8   0.094       0
Bank Sta=5022.4,5026.4
Exp/Cntr=0.3,0.1

Type RM Length L Ch R = 1,14058,446,446,446
BEGIN DESCRIPTION:
South Guadalupe Tributary 21.0
END DESCRIPTION:
XS GIS Cut Line= 3
      2245025.01     13793224.98      2245275.00     13792825.00
      2245675.01     13792074.98
#Sta/Elev= 30
  4524.1  668.48  4574.2  667.11  4668.5  662.04  4699.2  662.51  4705.1  661.22
  4720.4  661.82  4762.9  659.77  4909.1  658.78  4924.4  658.23  4935.4  655.69
  4945.7  652.65  4960.4  650.21  5007.1  649.36  5007.4  648.86  5012.1  649.36
  5075.5  650.50  5091.8  652.82  5097.8  655.54  5108.1  657.12  5267.0  658.48
  5327.6  657.76  5376.7  659.62  5453.7  660.04  5505.8  663.96  5596.3  663.09
  5630.4  663.35  5667.6  666.78  5728.8  667.52  5800.4  671.69  5845.8  671.95
#Mann=8,-1,0
  4524.1   0.063       0  4935.4   0.035       0  5007.1   0.035       0
  5012.1   0.035       0  5267.0   0.063       0  5376.7   0.094       0
  5596.3     0.1       0  5728.8   0.094       0
Bank Sta=5007.1,5012.1
Exp/Cntr=0.3,0.1

Type RM Length L Ch R = 1,13612,447,447,447
BEGIN DESCRIPTION:
South Guadalupe Tributary 20.0
END DESCRIPTION:
XS GIS Cut Line= 3
      2245425.01     13793374.98      2245675.00     13792975.00
      2245825.00     13792175.01
#Sta/Elev= 30
  4524.0  665.72  4618.3  659.97  4683.8  658.92  4726.2  656.46  4830.0  656.75
  4906.8  654.91  4930.2  653.74  4945.6  650.71  4960.3  649.17  5013.5  647.34
  5013.9  646.84  5018.5  647.34  5027.0  648.50  5079.6  649.08  5107.6  653.34
  5189.8  653.01  5250.0  654.83  5281.7  653.78  5300.9  653.84  5347.5  656.85
  5381.3  656.84  5423.0  657.43  5480.9  660.68  5545.1  661.80  5580.5  660.90
  5606.1  661.06  5636.7  664.80  5680.0  665.49  5730.8  666.54  5809.6  670.46
#Mann=9,-1,0
  4524.0   0.063       0  4906.8   0.035       0  5013.5   0.035       0
  5018.5   0.035       0  5281.7   0.063       0  5381.3   0.094       0
  5480.9   0.063       0  5580.5     0.1       0  5680.0   0.094       0
Bank Sta=5013.5,5018.5
Exp/Cntr=0.3,0.1

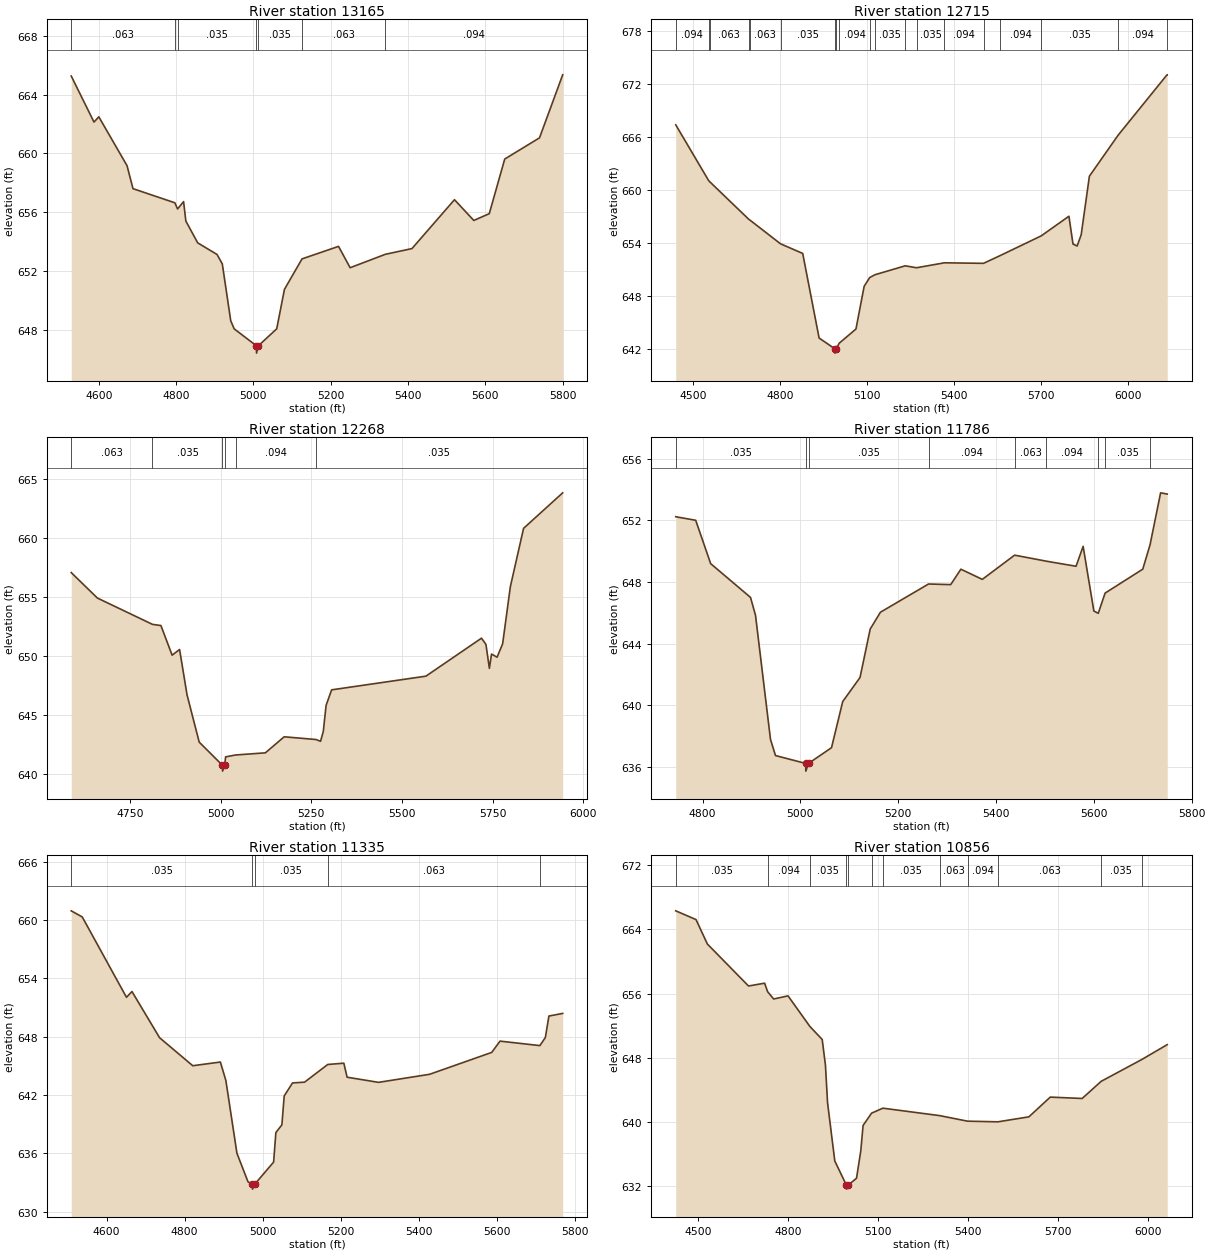
Type RM Length L Ch R = 1,13165,450,450,450
BEGIN DESCRIPTION:
South Guadalupe Tributary 19.0
END DESCRIPTION:
XS GIS Cut Line= 3
      2245825.01     13793524.98      2246075.00     13793125.00
      2246075.00     13792324.98
#Sta/Elev= 30
  4528.7  665.26  4587.6  662.13  4600.0  662.49  4673.1  659.17  4688.5  657.61
  4796.8  656.65  4803.9  656.23  4819.4  656.73  4825.3  655.41  4855.9  653.93
  4906.0  653.14  4919.6  652.50  4941.4  648.64  4950.3  648.09  5007.8  646.94
  5008.2  646.44  5012.9  646.94  5060.4  648.09  5080.4  650.77  5125.9  652.84
  5220.4  653.69  5250.4  652.24  5341.4  653.15  5410.4  653.54  5520.4  656.86
  5570.4  655.45  5610.4  655.91  5650.4  659.62  5740.4  661.06  5800.4  665.34
#Mann=7,-1,0
  4528.7   0.063       0  4796.8   0.094       0  4803.9   0.035       0
  5007.8   0.035       0  5012.9   0.035       0  5125.9   0.063       0
  5341.4   0.094       0
Bank Sta=5007.8,5012.9
Exp/Cntr=0.3,0.1

Type RM Length L Ch R = 1,12715,447,447,447
BEGIN DESCRIPTION:
South Guadalupe Tributary 18.0
END DESCRIPTION:
XS GIS Cut Line= 3
      2246074.98     13793675.02      2246475.00     13793275.00
      2247275.01     13792474.99
#Sta/Elev= 30
  4439.3  667.36  4552.8  661.06  4556.1  660.94  4691.2  656.68  4696.4  656.56
  4801.1  653.90  4877.7  652.81  4934.3  643.24  4988.3  642.03  4988.7  641.53
  4993.5  642.03  5004.1  642.66  5061.6  644.26  5089.9  649.09  5108.9  650.08
  5127.1  650.40  5231.8  651.41  5270.7  651.19  5367.0  651.75  5502.1  651.69
  5557.9  652.54  5701.4  654.80  5797.0  657.02  5811.1  653.87  5825.3  653.65
  5839.4  654.93  5867.7  661.55  5966.9  666.19  6135.7  673.02  6136.4  673.02
#Mann=19,-1,0
  4439.3   0.094       0  4552.8   0.035       0  4556.1   0.063       0
  4691.2   0.094       0  4696.4   0.063       0  4801.1   0.035       0
  4988.3   0.035       0  4993.5   0.035       0  5004.1   0.094       0
  5108.9   0.063       0  5127.1   0.035       0  5231.8   0.063       0
  5270.7   0.035       0  5367.0   0.094       0  5502.1   0.063       0
  5557.9   0.094       0  5701.4   0.035       0  5966.9   0.094       0
  6135.7     0.1       0
Bank Sta=4988.3,4993.5
Exp/Cntr=0.3,0.1

Type RM Length L Ch R = 1,12268,482,482,482
BEGIN DESCRIPTION:
South Guadalupe Tributary 17.0
END DESCRIPTION:
XS GIS Cut Line= 3
      2246375.00     13793675.00      2246775.00     13793575.00
      2247274.99     13792775.01
#Sta/Elev= 30
  4587.6  657.06  4659.8  654.90  4811.7  652.67  4835.0  652.57  4865.9  650.06
  4886.5  650.54  4907.1  646.69  4940.6  642.69  5004.6  640.73  5005.1  640.23
  5010.6  640.73  5013.5  641.44  5041.6  641.60  5123.1  641.78  5175.0  643.14
  5262.6  642.91  5275.3  642.76  5282.9  643.59  5290.6  645.80  5305.9  647.12
  5566.0  648.28  5719.3  651.50  5731.6  650.97  5741.1  648.94  5747.0  650.15
  5762.3  649.89  5777.6  651.02  5798.9  655.86  5835.4  660.81  5943.3  663.82
#Mann=6,-1,0
  4587.6   0.063       0  4811.7   0.035       0  5004.6   0.035       0
  5010.6   0.035       0  5041.6   0.094       0  5262.6   0.035       0
Bank Sta=5004.6,5010.6
Exp/Cntr=0.3,0.1

Type RM Length L Ch R = 1,11786,451,451,451
BEGIN DESCRIPTION:
South Guadalupe Tributary 16.0
END DESCRIPTION:
XS GIS Cut Line= 3
      2246625.03     13793975.01      2246875.00     13794025.00
      2247324.99     13793425.02
#Sta/Elev= 30
  4745.1  652.23  4785.9  652.00  4816.5  649.19  4898.0  647.00  4908.2  645.84
  4938.8  637.80  4949.0  636.75  5010.6  636.24  5011.1  635.74  5016.6  636.24
  5063.6  637.26  5086.5  640.25  5121.9  641.81  5142.7  644.95  5163.6  646.04
  5262.0  647.87  5307.3  647.83  5328.1  648.83  5371.9  648.17  5438.0  649.74
  5502.7  649.35  5563.6  649.02  5578.1  650.31  5600.0  646.12  5609.0  645.97
  5623.0  647.28  5700.0  648.83  5714.9  650.41  5736.5  653.78  5750.0  653.70
#Mann=9,-1,0
  4745.1   0.035       0  5010.6   0.035       0  5016.6   0.035       0
  5262.0   0.094       0  5438.0   0.063       0  5502.7   0.094       0
  5609.0   0.063       0  5623.0   0.035       0  5714.9   0.094       0
Bank Sta=5010.6,5016.6
Exp/Cntr=0.3,0.1

Type RM Length L Ch R = 1,11335,479,479,479
BEGIN DESCRIPTION:
South Guadalupe Tributary 15.0
END DESCRIPTION:
XS GIS Cut Line= 3
      2246625.02     13794774.98      2246975.00     13794425.00
      2247375.02     13793774.96
#Sta/Elev= 30
  4509.6  660.95  4537.8  660.32  4651.0  652.06  4665.1  652.65  4735.8  647.90
  4820.7  645.02  4891.4  645.40  4905.5  643.50  4933.8  636.02  4962.1  633.09
  4973.2  632.83  4973.7  632.33  4979.3  632.83  5027.7  635.11  5033.5  638.15
  5048.9  638.94  5054.8  641.91  5076.1  643.25  5106.9  643.33  5166.3  645.15
  5207.5  645.28  5215.9  643.84  5296.3  643.31  5427.2  644.14  5586.1  646.39
  5607.4  647.55  5709.4  647.09  5723.4  647.92  5732.5  650.13  5767.8  650.40
#Mann=5,-1,0
  4509.6   0.035       0  4973.2   0.035       0  4979.3   0.035       0
  5166.3   0.063       0  5709.4   0.094       0
Bank Sta=4973.2,4979.3
Exp/Cntr=0.3,0.1

Type RM Length L Ch R = 1,10856,451,451,451
BEGIN DESCRIPTION:
South Guadalupe Tributary 14.0
END DESCRIPTION:
XS GIS Cut Line= 3
      2246542.37     13795089.40      2247075.00     13794875.00
      2247875.02     13794174.98
#Sta/Elev= 30
  4425.4  666.32  4492.9  665.23  4530.8  662.18  4667.8  656.95  4721.5  657.30
  4731.4  656.24  4751.6  655.33  4799.4  655.72  4872.4  651.90  4913.3  650.28
  4924.1  647.06  4931.1  642.40  4955.2  635.14  4993.8  632.13  4994.3  631.63
  4999.9  632.13  5027.6  632.99  5041.8  636.40  5049.4  639.56  5077.7  641.10
  5115.5  641.72  5305.1  640.79  5397.5  640.10  5498.6  640.02  5601.8  640.64
  5673.0  643.10  5779.3  642.93  5842.7  645.07  5977.1  647.77  6062.6  649.64
#Mann=12,-1,0
  4425.4   0.035       0  4731.4   0.094       0  4872.4   0.035       0
  4993.8   0.035       0  4999.9   0.035       0  5077.7   0.094       0
  5115.5   0.035       0  5305.1   0.063       0  5397.5   0.094       0
  5498.6   0.063       0  5842.7   0.035       0  5977.1   0.063       0
Bank Sta=4993.8,4999.9
Exp/Cntr=0.3,0.1

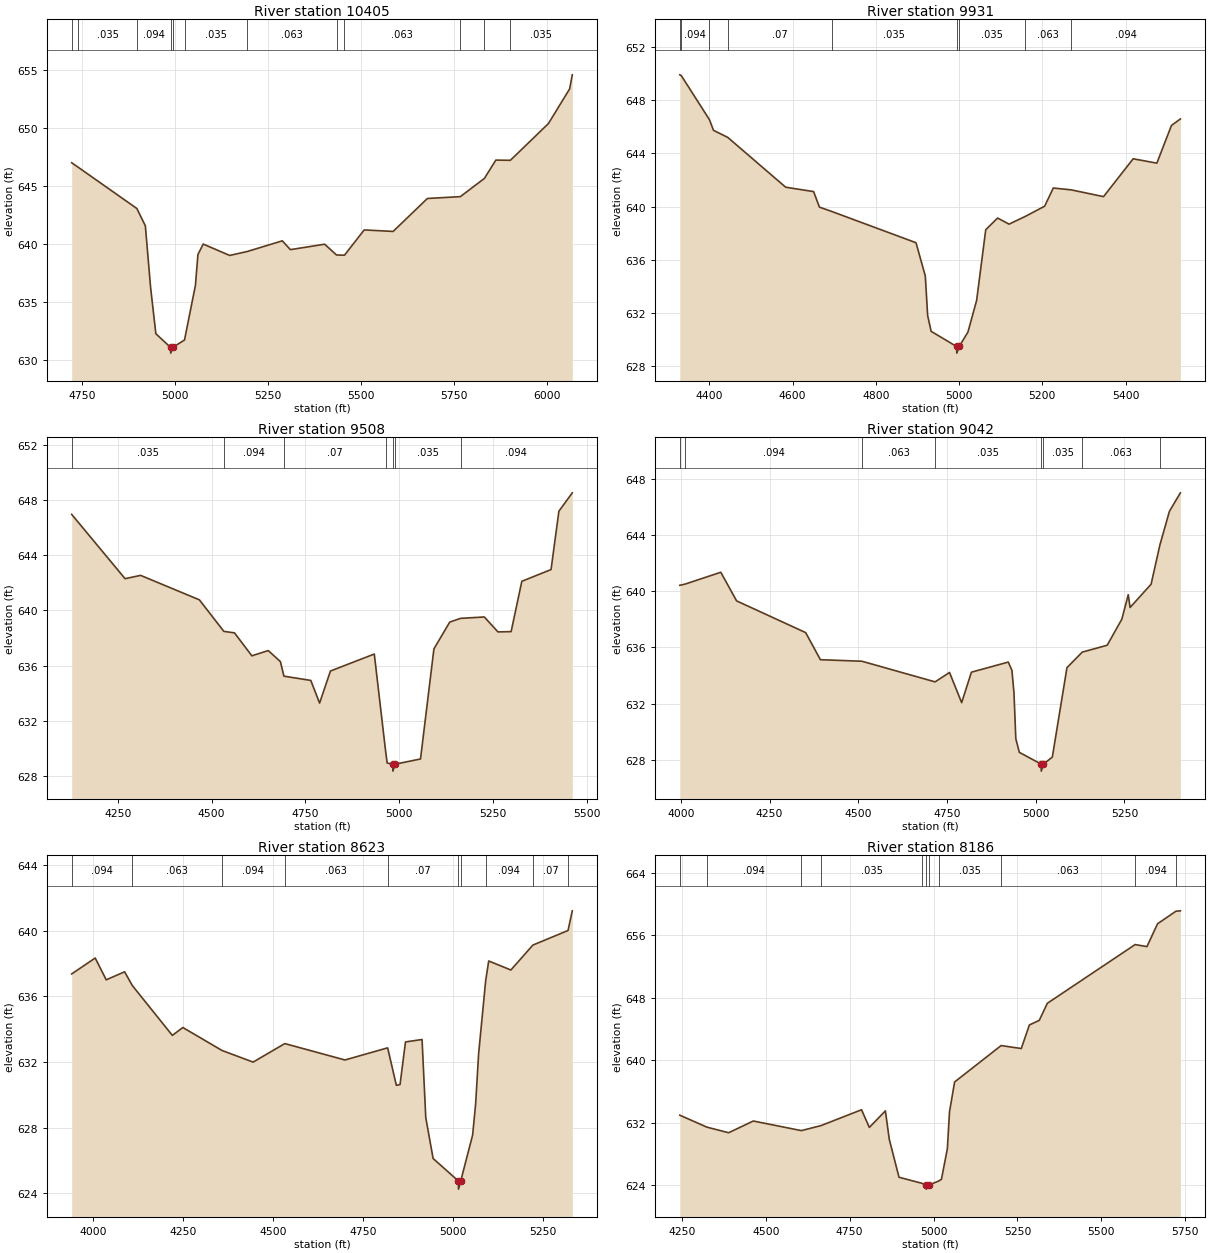
Type RM Length L Ch R = 1,10405,474,474,474
BEGIN DESCRIPTION:
South Guadalupe Tributary 13.0
END DESCRIPTION:
XS GIS Cut Line= 3
      2247174.96     13795325.04      2247375.00     13795125.00
      2248174.99     13794425.00
#Sta/Elev= 30
  4721.7  646.97  4739.3  646.58  4896.8  643.03  4919.7  641.54  4933.9  636.21
  4948.0  632.23  4987.4  631.06  4987.9  630.56  4993.6  631.06  5025.0  631.69
  5054.4  636.41  5061.1  639.06  5075.3  639.96  5146.5  638.98  5193.7  639.32
  5287.9  640.24  5309.7  639.48  5401.8  639.95  5433.7  639.02  5455.1  639.00
  5508.1  641.18  5585.9  641.05  5678.0  643.89  5766.7  644.05  5831.3  645.62
  5862.1  647.20  5901.1  647.18  6003.5  650.35  6060.5  653.34  6067.6  654.55
#Mann=12,-1,0
  4721.7   0.094       0  4739.3   0.035       0  4896.8   0.094       0
  4987.4    0.05       0  4993.6   0.094       0  5025.0   0.035       0
  5193.7   0.063       0  5433.7   0.094       0  5455.1   0.063       0
  5766.7   0.094       0  5831.3   0.063       0  5901.1   0.035       0
Bank Sta=4987.4,4993.6
Exp/Cntr=0.3,0.1

Type RM Length L Ch R = 1,9931,423,423,423
BEGIN DESCRIPTION:
South Guadalupe Tributary 12.0
END DESCRIPTION:
XS GIS Cut Line= 3
      2247175.04     13795624.98      2247775.00     13795325.00
      2248125.01     13794924.98
#Sta/Elev= 30
  4329.2  649.92  4332.6  649.87  4400.5  646.54  4410.2  645.74  4444.4  645.21
  4583.5  641.46  4650.6  641.13  4664.6  639.96  4693.7  639.64  4896.6  637.28
  4918.9  634.77  4924.5  631.80  4932.9  630.61  4994.0  629.47  4994.5  628.97
  5000.4  629.47  5021.3  630.56  5042.2  632.95  5064.0  638.26  5092.5  639.14
  5120.0  638.68  5159.5  639.27  5205.5  640.03  5226.3  641.40  5269.3  641.26
  5346.9  640.75  5418.1  643.60  5475.0  643.27  5510.1  646.11  5531.5  646.60
#Mann=9,-1,0
  4329.2     0.1       0  4332.6   0.094       0  4400.5     0.1       0
  4444.4    0.07       0  4693.7   0.035       0  4994.0   0.035       0
  5000.4   0.035       0  5159.5   0.063       0  5269.3   0.094       0
Bank Sta=4994,5000.4
Exp/Cntr=0.3,0.1

Type RM Length L Ch R = 1,9508,466,466,466
BEGIN DESCRIPTION:
South Guadalupe Tributary 11.0
END DESCRIPTION:
XS GIS Cut Line= 3
      2247325.02     13795874.99      2248125.00     13795525.00
      2248425.02     13795174.98
#Sta/Elev= 30
  4127.1  646.95  4269.4  642.30  4310.7  642.54  4467.4  640.77  4532.6  638.49
  4561.0  638.38  4607.3  636.72  4651.0  637.10  4683.4  636.30  4692.7  635.25
  4764.4  634.94  4787.8  633.30  4816.7  635.62  4933.6  636.85  4963.5  629.89
  4967.9  628.97  4982.7  628.88  4983.2  628.38  4989.1  628.88  5056.8  629.26
  5092.5  637.22  5134.7  639.16  5163.4  639.43  5226.9  639.53  5263.2  638.45
  5298.3  638.47  5326.8  642.11  5404.7  642.96  5425.6  647.18  5461.3  648.51
#Mann=7,-1,0
  4127.1   0.035       0  4532.6   0.094       0  4692.7    0.07       0
  4963.5   0.035       0  4982.7   0.035       0  4989.1   0.035       0
  5163.4   0.094       0
Bank Sta=4982.7,4989.1
Exp/Cntr=0.3,0.1

Type RM Length L Ch R = 1,9042,419,419,419
BEGIN DESCRIPTION:
South Guadalupe Tributary 10.0
END DESCRIPTION:
XS GIS Cut Line= 3
      2247563.25     13795992.17      2248525.00     13795725.00
      2248625.00     13795324.98
#Sta/Elev= 30
  3997.2  640.43  4012.6  640.52  4112.7  641.36  4157.3  639.32  4351.9  637.06
  4393.4  635.13  4510.3  635.02  4716.5  633.55  4757.2  634.22  4791.4  632.07
  4818.9  634.24  4922.7  634.96  4933.1  634.37  4938.8  632.77  4944.0  629.50
  4953.9  628.53  5015.3  627.69  5015.8  627.19  5021.8  627.69  5046.9  628.19
  5088.1  634.56  5131.2  635.67  5201.5  636.16  5242.8  638.02  5260.8  639.76
  5266.0  638.85  5325.2  640.51  5349.9  643.30  5376.8  645.70  5407.7  647.02
#Mann=8,-1,0
  3997.2   0.035       0  4012.6   0.094       0  4510.3   0.063       0
  4716.5   0.035       0  5015.3   0.035       0  5021.8   0.035       0
  5131.2   0.063       0  5349.9   0.094       0
Bank Sta=5015.3,5021.8
Exp/Cntr=0.3,0.1

Type RM Length L Ch R = 1,8623,437,437,437
BEGIN DESCRIPTION:
South Guadalupe Tributary 9.0
END DESCRIPTION:
XS GIS Cut Line= 3
      2247840.97     13796131.07      2248875.00     13795925.00
      2249025.01     13795624.98
#Sta/Elev= 30
  3941.1  637.37  4006.4  638.34  4037.0  637.01  4088.0  637.50  4109.5  636.66
  4220.5  633.62  4249.8  634.10  4358.4  632.70  4444.8  631.99  4532.8  633.12
  4699.8  632.12  4818.3  632.86  4842.5  630.57  4852.7  630.62  4867.8  633.22
  4913.8  633.37  4924.1  628.61  4944.5  626.11  5014.5  624.74  5015.0  624.24
  5021.2  624.74  5054.2  627.54  5062.5  629.42  5070.9  632.51  5090.5  636.97
  5098.9  638.16  5160.4  637.61  5221.5  639.13  5319.1  640.02  5330.9  641.22
#Mann=10,-1,0
  3941.1   0.094       0  4109.5   0.063       0  4358.4   0.094       0
  4532.8   0.063       0  4818.3    0.07       0  5014.5    0.05       0
  5021.2    0.07       0  5090.5   0.094       0  5221.5    0.07       0
  5319.1   0.094       0
Bank Sta=5014.5,5021.2
Exp/Cntr=0.3,0.1

Type RM Length L Ch R = 1,8186,607,607,607
BEGIN DESCRIPTION:
South Guadalupe Tributary 8.0
END DESCRIPTION:
XS GIS Cut Line= 3
      2248521.56     13796207.45      2249275.00     13796075.00
      2249549.29     13795401.95
#Sta/Elev= 30
  4243.9  632.94  4324.3  631.41  4389.5  630.69  4463.0  632.19  4606.1  630.96
  4664.5  631.60  4785.5  633.63  4808.8  631.37  4856.6  633.49  4868.2  629.85
  4897.2  624.99  4966.1  624.21  4978.4  623.97  4978.9  623.47  4985.1  623.97
  5014.9  624.50  5023.6  624.72  5041.3  628.65  5047.7  633.38  5062.9  637.19
  5201.5  641.85  5261.6  641.47  5285.7  644.49  5315.1  645.07  5339.2  647.26
  5600.9  654.78  5636.1  654.52  5667.6  657.44  5722.4  659.05  5735.7  659.10
#Mann=11,-1,0
  4243.9   0.063       0  4324.3   0.094       0  4606.1   0.063       0
  4664.5   0.035       0  4966.1    0.07       0  4978.4    0.05       0
  4985.1    0.07       0  5014.9   0.035       0  5201.5   0.063       0
  5600.9   0.094       0  5722.4   0.063       0
Bank Sta=4978.4,4985.1
Exp/Cntr=0.3,0.1

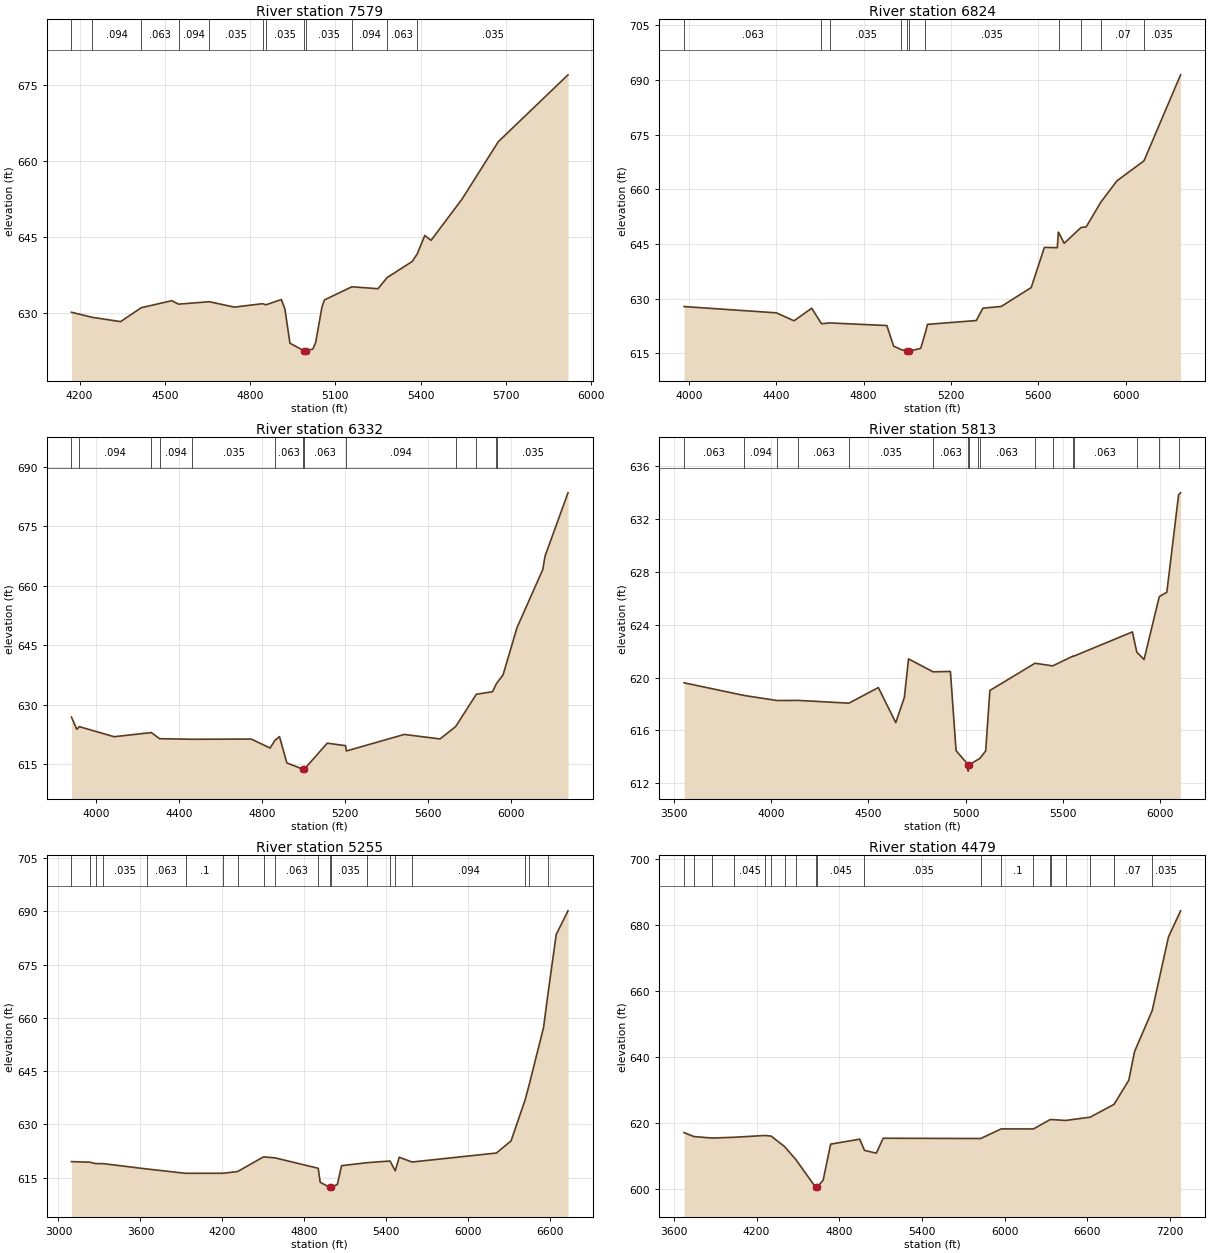
Type RM Length L Ch R = 1,7579,755,755,755
BEGIN DESCRIPTION:
SGT21641
END DESCRIPTION:
XS GIS Cut Line= 3
      2249042.39     13796443.57      2249722.92     13796457.46
      2250160.22     13795485.69
#Sta/Elev= 30
  4171.7  630.19  4244.6  629.20  4344.3  628.35  4417.1  631.09  4524.4  632.47
  4548.2  631.79  4656.2  632.27  4744.4  631.21  4843.5  631.88  4855.6  631.66
  4909.9  632.70  4922.4  630.81  4940.0  624.10  4988.4  622.65  4988.9  622.15
  4995.2  622.65  5020.4  622.95  5030.5  624.23  5052.5  631.19  5061.3  632.62
  5157.9  635.21  5249.8  634.83  5281.5  637.01  5370.5  640.21  5388.0  641.72
  5414.3  645.31  5436.3  644.34  5545.9  652.52  5672.9  663.77  5918.0  676.93
#Mann=12,-1,0
  4171.7   0.063       0  4244.6   0.094       0  4417.1   0.063       0
  4548.2   0.094       0  4656.2   0.035       0  4843.5   0.063       0
  4855.6   0.035       0  4988.4   0.035       0  4995.2   0.035       0
  5157.9   0.094       0  5281.5   0.063       0  5388.0   0.035       0
Bank Sta=4988.4,4995.2
Exp/Cntr=0.3,0.1

Type RM Length L Ch R = 1,6824,492,492,492
BEGIN DESCRIPTION:
SGT21640
END DESCRIPTION:
XS GIS Cut Line= 4
      2249667.37     13796874.12      2250382.65     13796763.01
      2250500.70     13796318.57      2250375.71     13795235.27
#Sta/Elev= 30
  3978.1  627.82  4400.8  626.10  4481.7  623.92  4562.7  627.36  4607.5  623.11
  4645.5  623.33  4906.8  622.62  4937.9  616.98  4973.3  616.00  5000.7  615.55
  5001.2  615.05  5007.6  615.55  5062.0  616.36  5083.7  620.75  5093.1  622.94
  5316.4  623.99  5347.0  627.38  5430.9  627.85  5568.1  633.04  5628.5  644.05
  5687.6  643.97  5692.6  648.22  5697.0  647.79  5719.1  645.16  5796.4  649.51
  5819.7  649.66  5887.6  656.51  5960.6  662.29  6084.7  667.79  6252.3  691.37
#Mann=11,-1,0
  3978.1   0.063       0  4607.5   0.094       0  4645.5   0.035       0
  4973.3   0.094       0  5000.7    0.05       0  5007.6   0.094       0
  5083.7   0.035       0  5697.0    0.07       0  5796.4   0.035       0
  5887.6    0.07       0  6084.7   0.035       0
Bank Sta=5000.7,5007.6
Exp/Cntr=0.3,0.1

Type RM Length L Ch R = 1,6332,519,519,519
BEGIN DESCRIPTION:
SGT21639
END DESCRIPTION:
XS GIS Cut Line= 4
      2250160.45     13797019.95      2250889.59     13796769.96
      2250952.09     13796297.74      2250771.53     13795165.79
#Sta/Elev= 30
  3880.9  626.82  3906.6  623.73  3918.3  624.42  4086.6  621.87  4265.6  622.92
  4305.8  621.37  4462.6  621.23  4747.5  621.28  4838.3  619.01  4860.9  620.91
  4883.6  621.90  4919.0  615.26  4996.2  613.68  4996.7  613.18  5003.2  613.68
  5113.9  620.24  5201.9  619.61  5205.8  618.27  5485.2  622.45  5657.4  621.31
  5732.4  624.41  5832.5  632.60  5910.6  633.24  5929.1  635.28  5932.6  635.52
  5961.2  637.49  6028.6  649.44  6152.8  664.11  6163.7  667.51  6274.3  683.48
#Mann=13,-1,0
  3880.9   0.063       0  3918.3   0.094       0  4265.6     0.1       0
  4305.8   0.094       0  4462.6   0.035       0  4860.9   0.063       0
  4996.2    0.05       0  5003.2   0.063       0  5201.9   0.094       0
  5732.4   0.063       0  5832.5   0.035       0  5929.1   0.063       0
  5932.6   0.035       0
Bank Sta=4996.2,5003.2
Exp/Cntr=0.3,0.1

Type RM Length L Ch R = 1,5813,558,558,558
BEGIN DESCRIPTION:
South Guadalupe Tributary 7.0
END DESCRIPTION:
XS GIS Cut Line= 4
      2250713.09     13797677.60      2251396.34     13796491.67
      2251425.00     13796425.00      2250993.76     13795401.91
#Sta/Elev= 30
  3552.5  619.60  3862.1  618.64  4030.5  618.26  4138.7  618.27  4399.7  618.06
  4550.8  619.24  4640.3  616.59  4684.4  618.49  4706.0  621.41  4832.3  620.43
  4921.2  620.46  4950.2  614.47  5011.9  613.42  5012.4  612.92  5019.0  613.42
  5061.1  613.78  5071.3  613.87  5102.3  614.44  5124.0  619.02  5355.9  621.08
  5446.4  620.88  5552.8  621.63  5554.5  621.61  5856.4  623.45  5879.0  621.92
  5916.2  621.36  5994.5  626.12  6033.3  626.45  6093.8  633.82  6104.0  633.97
#Mann=17,-1,0
  3552.5   0.063       0  3862.1   0.094       0  4030.5   0.035       0
  4138.7   0.063       0  4399.7   0.035       0  4832.3   0.063       0
  5011.9    0.05       0  5019.0   0.063       0  5061.1   0.094       0
  5071.3   0.063       0  5355.9   0.094       0  5446.4   0.063       0
  5552.8   0.094       0  5554.5   0.063       0  5879.0   0.094       0
  5994.5   0.035       0  6093.8    0.12       0
Bank Sta=5011.9,5019
Exp/Cntr=0.3,0.1

Type RM Length L Ch R = 1,5255,776,776,776
BEGIN DESCRIPTION:
SGT21638
END DESCRIPTION:
XS GIS Cut Line= 4
      2250772.08     13797674.18      2251813.20     13796943.57
      2251972.92     13796207.46      2251050.36     13794889.51
#Sta/Elev= 30
  3095.1  619.51  3229.1  619.35  3271.8  618.95  3327.4  618.94  3647.9  617.43
  3929.9  616.22  4203.6  616.23  4310.6  616.71  4500.7  620.85  4587.0  620.55
  4900.9  617.63  4915.4  613.69  4985.9  612.26  4986.4  611.76  4993.5  612.26
  5040.9  613.07  5071.6  618.37  5261.5  619.22  5426.2  619.68  5464.8  616.92
  5493.5  620.74  5587.5  619.40  6205.0  621.93  6312.2  625.34  6414.6  636.83
  6446.4  641.39  6550.3  657.35  6579.4  665.93  6642.7  683.50  6729.0  690.16
#Mann=20,-1,0
  3095.1   0.063       0  3229.1   0.035       0  3271.8   0.094       0
  3327.4   0.035       0  3647.9   0.063       0  3929.9     0.1       0
  4203.6   0.035       0  4310.6   0.094       0  4500.7   0.035       0
  4587.0   0.063       0  4900.9   0.035       0  4985.9   0.035       0
  4993.5   0.035       0  5261.5   0.063       0  5426.2   0.035       0
  5464.8   0.063       0  5587.5   0.094       0  6414.6    0.12       0
  6446.4    0.07       0  6579.4   0.035       0
Bank Sta=4985.9,4993.5
Exp/Cntr=0.3,0.1

Type RM Length L Ch R = 1,4479,536,536,536
BEGIN DESCRIPTION:
SGT21637
END DESCRIPTION:
XS GIS Cut Line= 4
      2251903.50     13797256.05      2252681.26     13796603.29
      2252618.76     13795818.57      2251125.68     13794811.61
#Sta/Elev= 30
  3674.0  617.18  3744.4  615.98  3875.8  615.52  4038.1  615.76  4263.2  616.30
  4306.4  616.10  4403.3  612.94  4484.7  609.04  4630.0  600.56  4630.5  600.06
  4637.8  600.56  4683.3  602.78  4737.8  613.68  4948.5  615.18  4983.4  611.79
  5068.9  610.94  5119.0  615.46  5826.6  615.38  5975.5  618.29  6209.9  618.28
  6326.4  621.01  6335.0  621.13  6442.8  620.85  6621.5  621.84  6794.7  625.73
  6901.6  633.01  6943.6  641.73  7071.6  654.12  7189.4  676.36  7277.5  684.30
#Mann=20,-1,0
  3674.0     0.1       0  3744.4   0.094       0  3875.8   0.035       0
  4038.1   0.045       0  4263.2    0.05       0  4306.4   0.045       0
  4403.3    0.05       0  4484.7   0.045       0  4630.0   0.035       0
  4637.8   0.045       0  4983.4   0.035       0  5826.6   0.094       0
  5975.5     0.1       0  6209.9   0.094       0  6326.4   0.035       0
  6335.0   0.094       0  6442.8   0.063       0  6621.5   0.094       0
  6794.7    0.07       0  7071.6   0.035       0
Bank Sta=4630,4637.8
Exp/Cntr=0.3,0.1

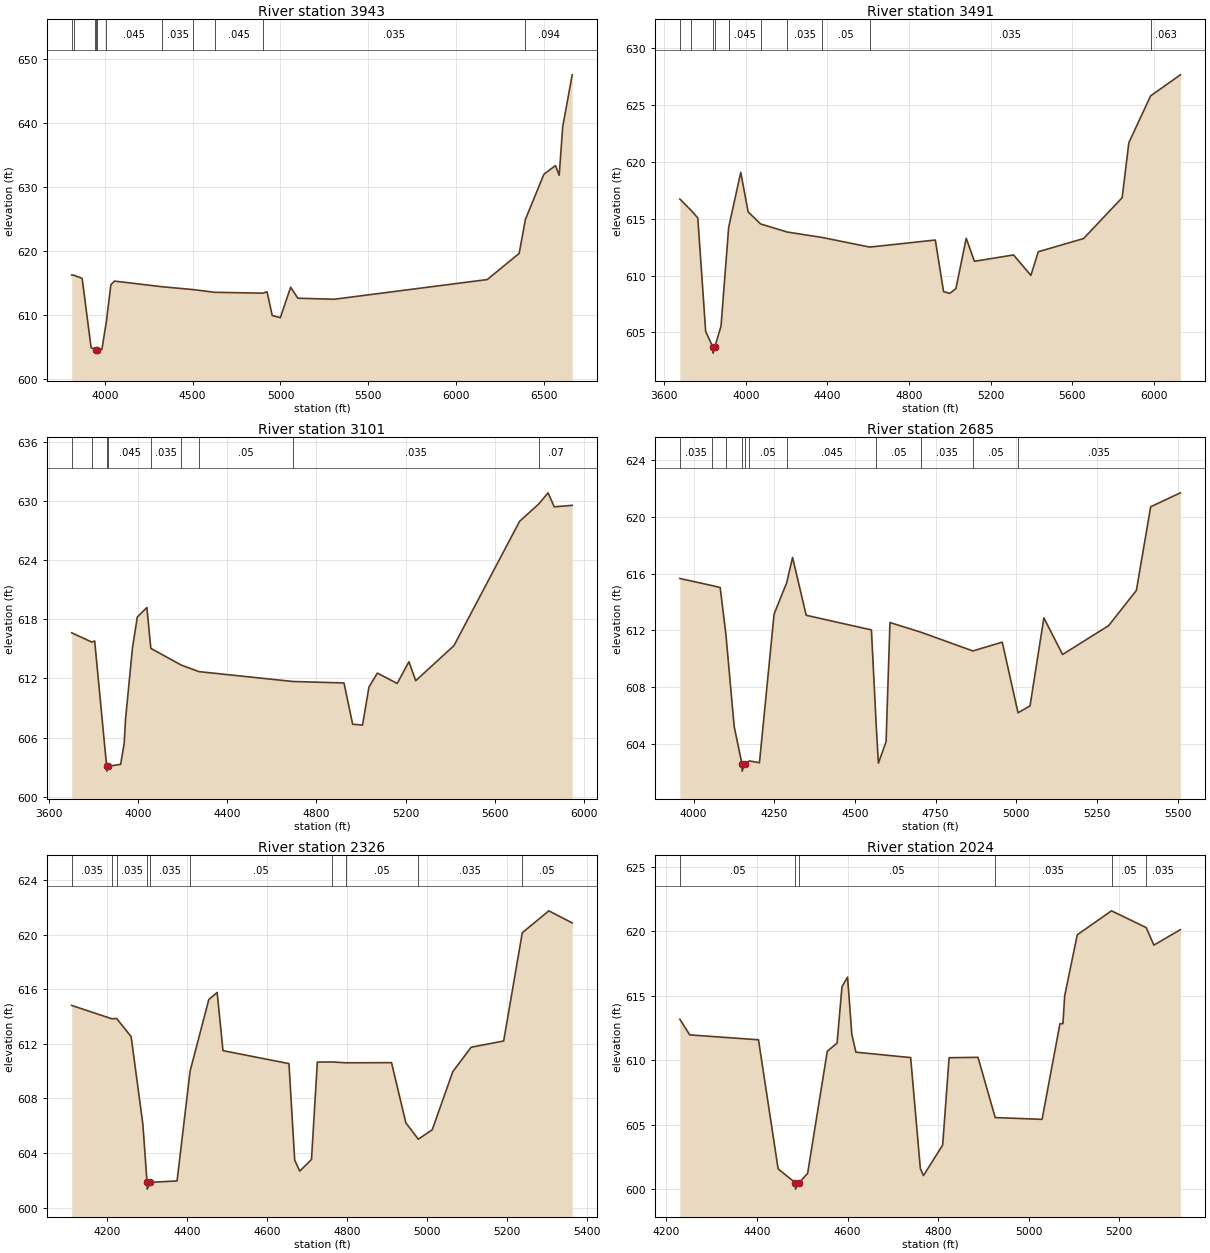
Type RM Length L Ch R = 1,3943,452,452,452
BEGIN DESCRIPTION:
SGT21636
END DESCRIPTION:
XS GIS Cut Line= 3
      2252959.04     13797353.26      2253181.26     13796276.90
      2252750.71     13794582.50
#Sta/Elev= 30
  3812.3  616.27  3823.4  616.25  3871.8  615.76  3922.8  604.93  3943.8  604.77
  3949.6  604.60  3950.1  604.10  3957.4  604.60  3984.1  604.68  4009.5  609.01
  4035.2  614.76  4055.6  615.33  4326.9  614.45  4504.6  614.00  4626.5  613.58
  4900.7  613.45  4923.6  613.67  4953.2  609.96  4999.3  609.63  5057.8  614.37
  5099.0  612.66  5305.4  612.50  6176.2  615.57  6357.8  619.65  6393.5  624.96
  6498.6  631.99  6564.2  633.34  6585.6  631.83  6605.4  639.38  6659.6  647.49
#Mann=11,-1,0
  3812.3   0.035       0  3823.4   0.045       0  3943.8   0.035       0
  3949.6   0.035       0  3957.4   0.035       0  4009.5   0.045       0
  4326.9   0.035       0  4504.6    0.05       0  4626.5   0.045       0
  4900.7   0.035       0  6393.5   0.094       0
Bank Sta=3949.6,3957.4
Exp/Cntr=0.3,0.1

Type RM Length L Ch R = 1,3491,390,390,390
BEGIN DESCRIPTION:
SGT21635
END DESCRIPTION:
XS GIS Cut Line= 3
      2253188.20     13797422.74      2253570.15     13796450.51
      2253757.64     13795054.71
#Sta/Elev= 30
  3677.2  616.72  3732.6  615.72  3765.1  615.06  3803.7  605.09  3839.8  603.68
  3840.3  603.18  3847.7  603.68  3878.9  605.55  3916.2  614.20  3916.5  614.25
  3975.6  619.07  4011.8  615.59  4073.2  614.53  4204.1  613.82  4373.3  613.35
  4607.8  612.50  4929.1  613.12  4969.5  608.59  4999.7  608.43  5030.0  608.85
  5080.5  613.27  5120.8  611.25  5312.5  611.81  5397.5  610.01  5433.6  612.09
  5655.6  613.25  5844.8  616.84  5877.6  621.68  5984.2  625.79  6130.1  627.64
#Mann=11,-1,0
  3677.2   0.035       0  3732.6   0.045       0  3839.8   0.035       0
  3847.7   0.045       0  3916.2   0.035       0  3916.5   0.045       0
  4073.2    0.05       0  4204.1   0.035       0  4373.3    0.05       0
  4607.8   0.035       0  5984.2   0.063       0
Bank Sta=3839.8,3847.7
Exp/Cntr=0.3,0.1

Type RM Length L Ch R = 1,3101,416,416,416
BEGIN DESCRIPTION:
SGT21634
END DESCRIPTION:
XS GIS Cut Line= 3
      2253292.36     13797464.42      2253889.59     13796429.68
      2254368.76     13795492.17
#Sta/Elev= 30
  3700.8  616.63  3791.0  615.69  3804.0  615.80  3857.7  603.09  3858.2  602.59
  3866.0  603.09  3920.7  603.28  3936.5  605.40  3942.6  607.86  3973.8  615.11
  3995.4  618.23  4038.5  619.20  4056.1  615.05  4192.4  613.36  4272.2  612.69
  4693.3  611.69  4923.6  611.54  4962.5  607.35  5006.9  607.27  5035.6  611.12
  5073.5  612.54  5162.4  611.49  5215.2  613.69  5245.7  611.77  5417.4  615.33
  5712.2  627.95  5797.3  629.69  5839.9  630.84  5867.7  629.42  5948.4  629.57
#Mann=9,-1,0
  3700.8   0.035       0  3791.0   0.045       0  3857.7   0.035       0
  3866.0   0.045       0  4056.1   0.035       0  4192.4   0.045       0
  4272.2    0.05       0  4693.3   0.035       0  5797.3    0.07       0
Bank Sta=3857.7,3866
Exp/Cntr=0.3,0.1

Type RM Length L Ch R = 1,2685,359,359,359
BEGIN DESCRIPTION:
South Guadalupe Tributary 6.0
END DESCRIPTION:
XS GIS Cut Line= 3
      2253547.12     13797539.53      2254081.00     13796723.52
      2254549.23     13796389.68
#Sta/Elev= 30
  3957.7  615.66  4057.7  615.16  4082.6  615.02  4100.4  611.70  4125.9  605.24
  4150.1  602.60  4150.6  602.10  4158.5  602.60  4173.0  602.82  4204.2  602.69
  4249.6  613.16  4288.4  615.35  4306.8  617.14  4349.0  613.07  4551.0  612.04
  4566.4  605.07  4572.6  602.66  4596.4  604.17  4608.4  612.56  4704.0  611.88
  4865.2  610.56  4956.2  611.18  5005.0  606.21  5042.2  606.69  5085.1  612.89
  5143.0  610.31  5285.6  612.34  5371.6  614.82  5415.9  620.71  5507.9  621.69
#Mann=11,-1,0
  3957.7   0.035       0  4057.7    0.05       0  4100.4   0.045       0
  4150.1    0.05       0  4158.5   0.045       0  4173.0    0.05       0
  4288.4   0.045       0  4566.4    0.05       0  4704.0   0.035       0
  4865.2    0.05       0  5005.0   0.035       0
Bank Sta=4150.1,4158.5
Exp/Cntr=0.3,0.1

Type RM Length L Ch R = 1,2326,302,302,302
BEGIN DESCRIPTION:
South Guadalupe Tributary 5.0
END DESCRIPTION:
XS GIS Cut Line= 3
      2253844.96     13797644.08      2254375.00     13796925.00
      2254700.60     13796774.31
#Sta/Elev= 30
  4111.2  614.83  4211.6  613.85  4223.7  613.87  4259.9  612.54  4289.2  606.12
  4299.7  601.85  4300.2  601.35  4308.1  601.85  4374.8  601.95  4407.4  610.01
  4454.2  615.26  4475.1  615.78  4489.7  611.51  4654.7  610.56  4669.1  603.47
  4681.8  602.67  4711.1  603.53  4725.7  610.67  4763.4  610.68  4796.4  610.62
  4911.3  610.63  4947.1  606.22  4978.3  605.01  5013.2  605.71  5064.6  609.97
  5110.4  611.76  5191.8  612.22  5238.4  620.16  5304.8  621.77  5363.3  620.88
#Mann=10,-1,0
  4111.2   0.035       0  4211.6    0.05       0  4223.7   0.035       0
  4299.7   0.035       0  4308.1   0.035       0  4407.4    0.05       0
  4763.4   0.035       0  4796.4    0.05       0  4978.3   0.035       0
  5238.4    0.05       0
Bank Sta=4299.7,4308.1
Exp/Cntr=0.3,0.1

Type RM Length L Ch R = 1,2024,276,276,276
BEGIN DESCRIPTION:
South Guadalupe Tributary 4.0
END DESCRIPTION:
XS GIS Cut Line= 4
      2254168.23     13797785.10      2254329.87     13797399.90
      2254625.63     13797093.83      2254851.05     13796960.62
#Sta/Elev= 30
  4229.6  613.18  4251.4  611.97  4403.2  611.59  4446.6  601.58  4484.4  600.51
  4484.9  600.01  4492.8  600.51  4511.7  601.23  4555.1  610.70  4576.7  611.33
  4587.6  615.71  4599.9  616.45  4609.3  612.01  4618.3  610.63  4739.2  610.21
  4760.6  601.61  4767.5  601.06  4809.9  603.43  4824.1  610.20  4887.9  610.23
  4925.9  605.56  5029.4  605.42  5068.9  612.84  5075.5  612.84  5079.3  615.00
  5107.1  619.73  5182.7  621.59  5259.3  620.29  5276.3  618.93  5334.8  620.13
#Mann=6,-1,0
  4229.6    0.05       0  4484.4   0.035       0  4492.8    0.05       0
  4925.9   0.035       0  5182.7    0.05       0  5259.3   0.035       0
Bank Sta=4484.4,4492.8
Exp/Cntr=0.3,0.1