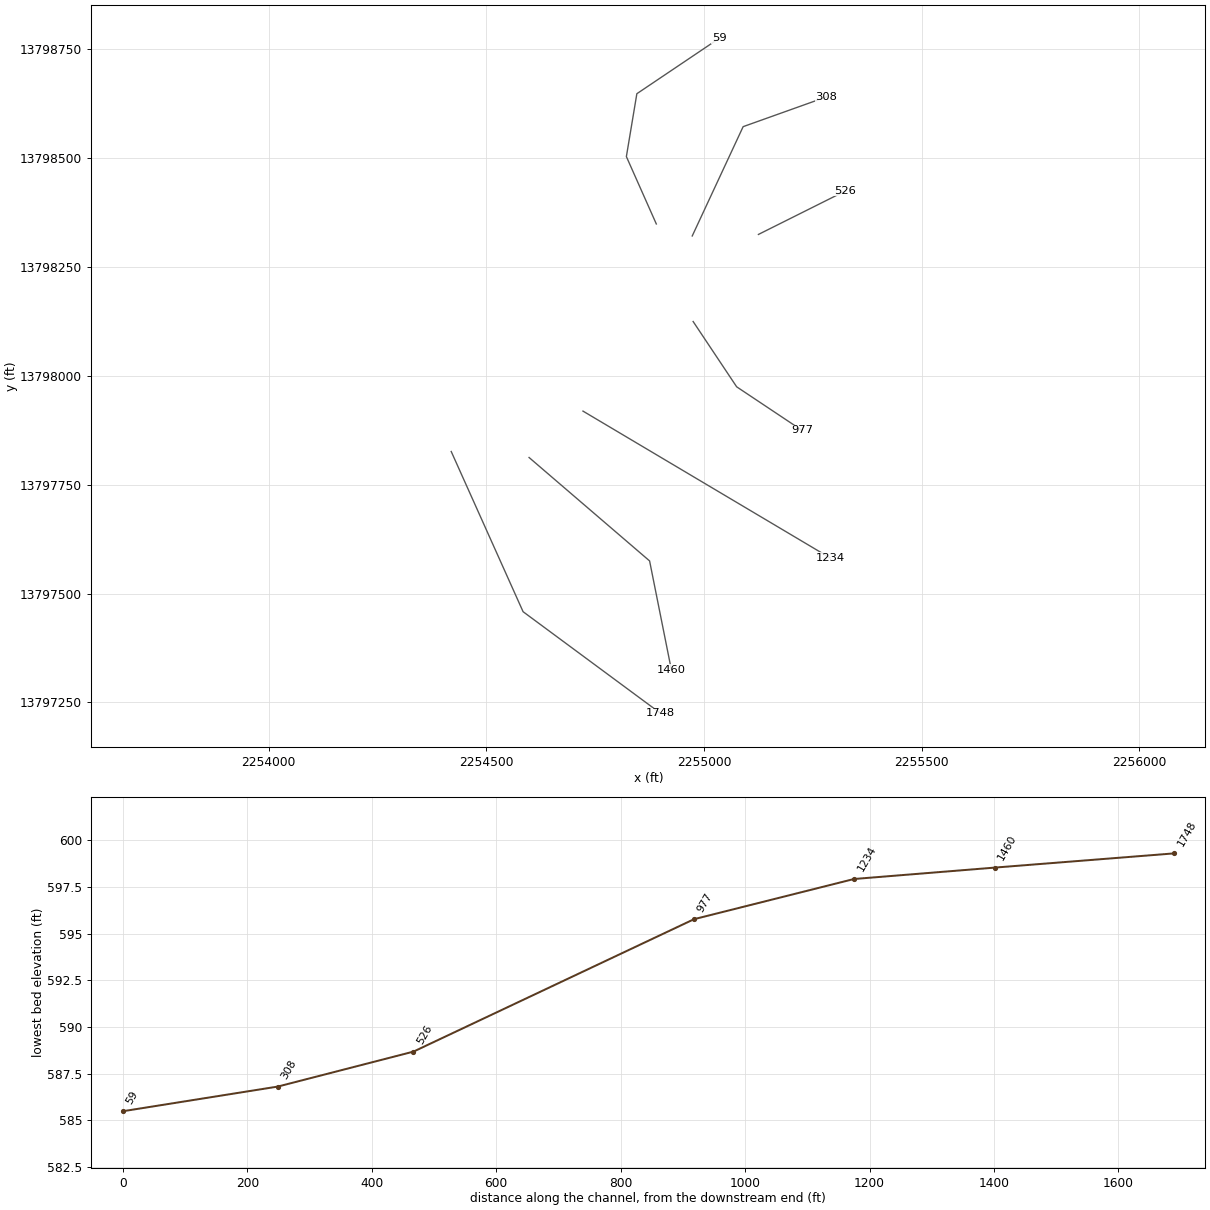
HEC-RAS study South Guadalupe Tributary.prj: South Guadalupe Tributary Base Level Engineering

--- South Guadalupe Tributary.g01 (geometry) --- (continued)

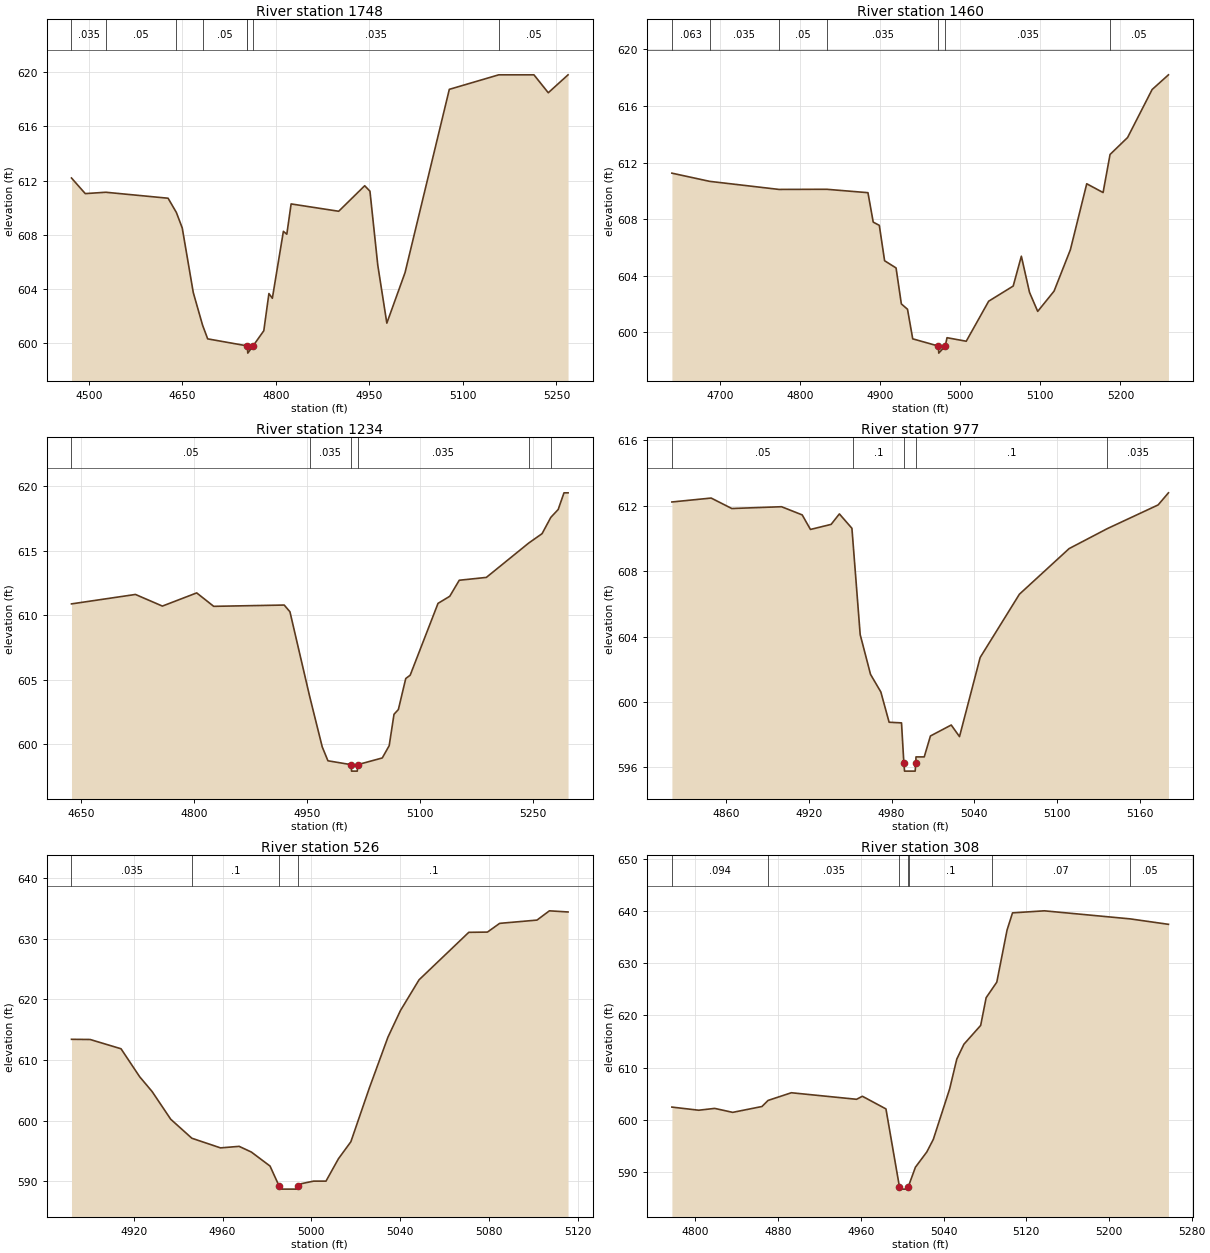
Type RM Length L Ch R = 1,1748,288,288,288
BEGIN DESCRIPTION:
SGT21633
END DESCRIPTION:
XS GIS Cut Line= 3
      2254419.28     13797826.37      2254584.36     13797458.37
      2254900.38     13797224.79
#Sta/Elev= 30
  4472.4  612.19  4494.5  611.04  4527.4  611.14  4627.3  610.70  4640.6  609.65
  4650.0  608.51  4667.7  603.75  4682.6  601.35  4690.8  600.34  4753.4  599.83
  4754.6  599.79  4755.1  599.29  4763.1  599.79  4780.8  600.94  4789.0  603.68
  4794.5  603.33  4812.2  608.26  4817.7  608.05  4824.6  610.28  4900.9  609.74
  4942.6  611.62  4951.0  611.22  4963.6  605.76  4978.1  601.50  5007.3  605.22
  5078.3  618.72  5157.6  619.79  5214.0  619.79  5237.0  618.47  5268.7  619.79
#Mann=8,-1,0
  4472.4   0.035       0  4527.4    0.05       0  4640.6   0.035       0
  4682.6    0.05       0  4753.4   0.035       0  4754.6   0.035       0
  4763.1   0.035       0  5157.6    0.05       0
Bank Sta=4754.6,4763.1
Exp/Cntr=0.3,0.1

Type RM Length L Ch R = 1,1460,226,226,226
BEGIN DESCRIPTION:
South Guadalupe Tributary 3.0
END DESCRIPTION:
XS GIS Cut Line= 3
      2254598.12     13797812.59      2254875.00     13797575.00
      2254925.00     13797325.00
#Sta/Elev= 30
  4640.2  611.25  4687.4  610.67  4773.9  610.10  4833.4  610.11  4884.9  609.87
  4891.5  607.79  4899.1  607.56  4905.7  605.06  4920.0  604.55  4926.6  602.01
  4934.3  601.63  4940.8  599.54  4972.8  599.03  4973.3  598.53  4981.4  599.03
  4983.6  599.62  5007.6  599.37  5035.6  602.20  5066.2  603.27  5076.4  605.38
  5086.6  602.82  5096.8  601.48  5117.2  602.91  5137.6  605.84  5158.0  610.50
  5178.4  609.88  5187.1  612.57  5209.0  613.77  5239.6  617.16  5260.0  618.20
#Mann=7,-1,0
  4640.2   0.063       0  4687.4   0.035       0  4773.9    0.05       0
  4833.4   0.035       0  4972.8   0.035       0  4981.4   0.035       0
  5187.1    0.05       0
Bank Sta=4972.8,4981.4
Exp/Cntr=0.3,0.1

Type RM Length L Ch R = 1,1234,257,257,257
BEGIN DESCRIPTION:
SGT21632
END DESCRIPTION:
XS GIS Cut Line= 2
      2254721.96     13797919.18      2255289.33     13797582.19
#Sta/Elev= 30
  4636.8  610.87  4721.8  611.60  4757.6  610.70  4803.2  611.72  4825.8  610.68
  4919.5  610.78  4927.1  610.26  4953.3  603.71  4970.0  599.80  4977.6  598.72
  5008.5  598.42  5009.0  597.92  5016.6  597.92  5017.1  598.42  5049.8  598.94
  5059.0  599.89  5065.4  602.32  5071.2  602.69  5081.0  605.09  5086.9  605.35
  5123.9  610.91  5139.5  611.46  5152.1  612.70  5188.1  612.92  5244.4  615.58
  5262.2  616.31  5273.8  617.57  5283.6  618.18  5291.3  619.47  5296.7  619.47
#Mann=6,-1,0
  4636.8    0.05       0  4953.3   0.035       0  5008.5   0.035       0
  5017.1   0.035       0  5244.4    0.05       0  5273.8   0.035       0
Bank Sta=5008.5,5017.1
Exp/Cntr=0.3,0.1

Type RM Length L Ch R = 1,977,451,451,451
BEGIN DESCRIPTION:
South Guadalupe Tributary 2.0
END DESCRIPTION:
XS GIS Cut Line= 3
      2254975.02     13798124.96      2255075.00     13797975.00
      2255224.99     13797875.01
#Sta/Elev= 30
  4820.5  612.23  4849.0  612.47  4864.0  611.83  4900.1  611.94  4915.1  611.44
  4921.1  610.55  4936.1  610.86  4942.1  611.50  4951.2  610.62  4952.2  609.54
  4957.2  604.12  4964.7  601.69  4972.2  600.61  4978.2  598.76  4987.2  598.72
  4988.9  596.27  4989.4  595.77  4997.1  595.77  4997.6  596.27  4997.7  596.64
  5003.7  596.64  5008.2  597.92  5023.3  598.59  5029.3  597.88  5044.3  602.72
  5072.8  606.59  5108.9  609.38  5136.6  610.60  5173.5  612.05  5181.0  612.79
#Mann=5,-1,0
  4820.5    0.05       0  4952.2     0.1       0  4988.9    0.05       0
  4997.6     0.1       0  5136.6   0.035       0
Bank Sta=4988.9,4997.6
Exp/Cntr=0.3,0.1

Type RM Length L Ch R = 1,526,218,218,218
BEGIN DESCRIPTION:
South Guadalupe Tributary 1.0
END DESCRIPTION:
XS GIS Cut Line= 3
      2255125.01     13798325.01      2255225.00     13798375.00
      2255325.01     13798425.00
#Sta/Elev= 30
  4892.0  613.41  4900.4  613.38  4914.3  611.85  4922.7  607.23  4928.3  604.79
  4936.7  600.21  4946.2  597.08  4959.1  595.49  4967.5  595.74  4973.0  594.80
  4981.4  592.49  4985.5  589.18  4986.0  588.68  4993.7  588.68  4994.2  589.18
  4995.4  589.57  5001.0  590.00  5006.6  590.00  5012.2  593.69  5017.8  596.50
  5026.1  605.35  5034.5  613.77  5040.1  618.14  5048.5  623.23  5070.9  631.07
  5079.3  631.11  5084.8  632.55  5101.6  633.09  5107.2  634.62  5115.6  634.43
#Mann=4,-1,0
  4892.0   0.035       0  4946.2     0.1       0  4985.5    0.05       0
  4994.2     0.1       0
Bank Sta=4985.5,4994.2
Exp/Cntr=0.3,0.1

Type RM Length L Ch R = 1,308,249,249,249
BEGIN DESCRIPTION:
SGT21631
END DESCRIPTION:
XS GIS Cut Line= 3
      2254972.96     13798321.54      2255089.90     13798572.62
      2255281.29     13798640.97
#Sta/Elev= 30
  4777.3  602.49  4803.2  601.89  4818.7  602.24  4836.1  601.48  4864.4  602.60
  4870.3  603.76  4892.8  605.23  4955.9  603.98  4961.5  604.56  4984.3  602.14
  4997.3  587.31  4997.8  586.81  5005.5  586.81  5006.0  587.31  5006.2  587.42
  5012.8  591.00  5023.8  593.91  5030.1  596.32  5045.9  605.96  5052.8  611.66
  5059.7  614.50  5075.9  618.10  5081.2  623.40  5087.2  625.13  5091.5  626.37
  5101.4  636.31  5106.7  639.61  5137.5  640.00  5220.5  638.46  5257.5  637.42
#Mann=7,-1,0
  4777.3   0.094       0  4870.3   0.035       0  4997.3   0.035       0
  5006.0   0.035       0  5006.2     0.1       0  5087.2    0.07       0
  5220.5    0.05       0
Bank Sta=4997.3,5006
Exp/Cntr=0.3,0.1

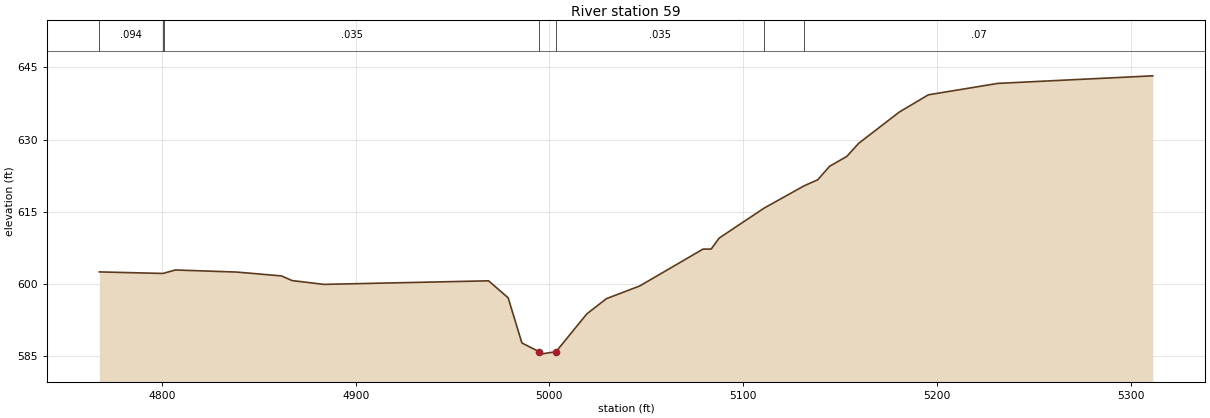
Type RM Length L Ch R = 1,59,0,0,0
BEGIN DESCRIPTION:
SGT21630
END DESCRIPTION:
XS GIS Cut Line= 4
      2254890.42     13798349.11      2254821.65     13798503.84
      2254845.73     13798648.28      2255034.86     13798775.51
#Sta/Elev= 30
  4767.7  602.56  4800.5  602.24  4801.1  602.31  4807.0  602.96  4838.5  602.53
  4861.7  601.73  4867.2  600.76  4883.6  599.97  4968.6  600.71  4978.7  597.19
  4985.8  587.81  4994.7  585.99  4995.2  585.49  5003.4  585.99  5019.3  593.84
  5029.4  597.00  5046.6  599.64  5079.3  607.30  5083.5  607.30  5087.6  609.58
  5111.0  615.85  5131.5  620.44  5138.5  621.69  5144.6  624.49  5153.5  626.54
  5159.6  629.25  5180.6  635.75  5195.6  639.33  5231.5  641.70  5311.4  643.27
#Mann=7,-1,0
  4767.7   0.094       0  4800.5   0.063       0  4801.1   0.035       0
  4994.7   0.035       0  5003.4   0.035       0  5111.0    0.12       0
  5131.5    0.07       0
Bank Sta=4994.7,5003.4
Exp/Cntr=0.3,0.1

Chan Stop Cuts=-1