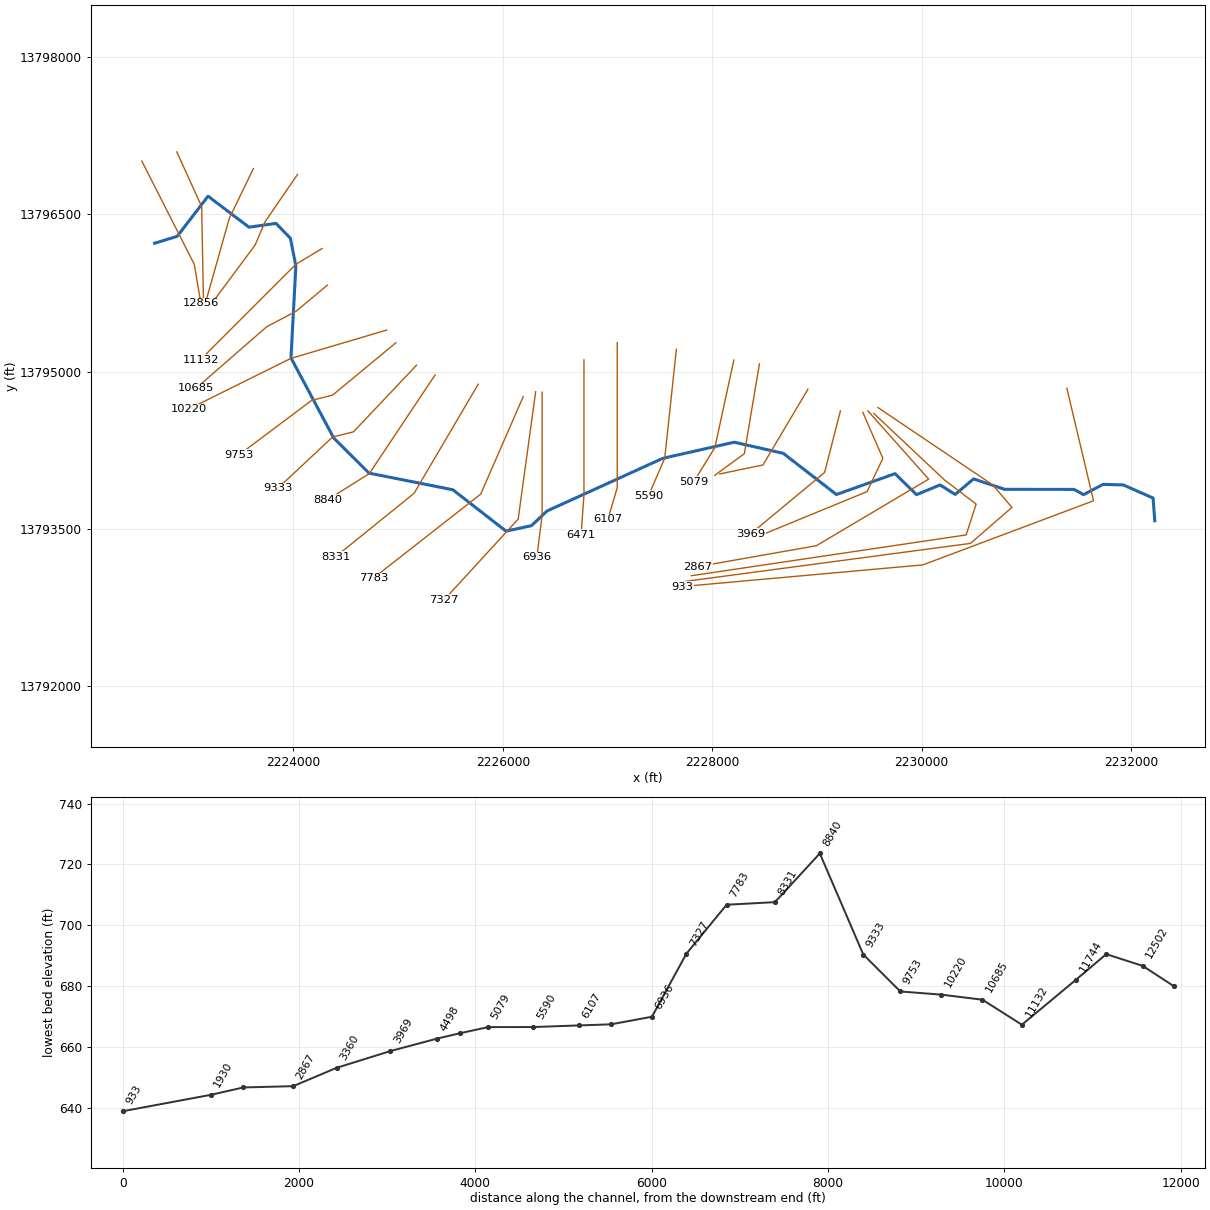
--- Stream0067.prj (project) ---

Proj Title=Stream0067 Base Level Engineering
Current Plan=p01
Default Exp/Contr=0.3,0.1
English Units
Geom File=g01
Flow File=f01
Plan File=p01
BEGIN DESCRIPTION:
Stream0067
END DESCRIPTION:

--- Stream0067.p01 (plan) ---

Plan Title=Multiple Run
Short Identifier=Multiple
Geom File=g01
Flow File=f01
Subcritical Flow
K Sum by GR= 0
Std Step Tol= 0.01
Critical Tol= 0.01
Num of Std Step Trials= 20
Max Error Tol= 0.3
Flow Tol Ratio= 0.001
Split Flow NTrial= 30
Split Flow Tol= 0.02
Split Flow Ratio= 0.02
Log Output Level= 0
Friction Slope Method= 1
Unsteady Friction Slope Method= 2
Unsteady Bridges Friction Slope Method= 1
Parabolic Critical Depth
Global Vel Dist=  1 , 1 , 1
Global Log Level= 0
CheckData=True
Encroach Param= -1, 0, 0, 0
BEGIN DESCRIPTION:
Multiple Run
END DESCRIPTION:

--- Stream0067.f01 (steady flow) ---

Flow Title=Multiple
Number of Profiles=7
Profile Names=10-year,25-year,50-year,1pct_min,100-year,1pct_plu,500-year
River Rch & RM= Stream0067,Reach-1,12856
    1105    1868    2591    1741    3474    6931    6179
River Rch & RM= Stream0067,Reach-1,12089
    1265    2145    2980    2003    3997    7976    7119
River Rch & RM= Stream0067,Reach-1,6936
    1325    2234    3091    2068    4126    8231    7275
Boundary for River Rch & Prof#=Stream0067,Reach-1,1
Up Type=0
Dn Type=3
Dn Slope=0.005
Boundary for River Rch & Prof#=Stream0067,Reach-1,2
Up Type=0
Dn Type=3
Dn Slope=0.005
Boundary for River Rch & Prof#=Stream0067,Reach-1,3
Up Type=0
Dn Type=3
Dn Slope=0.005
Boundary for River Rch & Prof#=Stream0067,Reach-1,4
Up Type=0
Dn Type=3
Dn Slope=0.005
Boundary for River Rch & Prof#=Stream0067,Reach-1,5
Up Type=0
Dn Type=3
Dn Slope=0.005
Boundary for River Rch & Prof#=Stream0067,Reach-1,6
Up Type=0
Dn Type=3
Dn Slope=0.005
Boundary for River Rch & Prof#=Stream0067,Reach-1,7
Up Type=0
Dn Type=3
Dn Slope=0.005

--- Stream0067.g01 (geometry) ---

Geom Title=Existing Conditions

River Reach=Stream0067,Reach-1
Reach XY= 30
      2222675.00     13796225.00      2222891.68     13796291.64
      2223185.49     13796674.52      2223576.56     13796378.74
      2223834.68     13796414.81      2223971.46     13796273.54
      2224024.48     13796009.78      2223977.26     13795130.94
      2224385.78     13794365.32      2224722.57     13794030.52
      2225523.42     13793871.17      2226031.03     13793476.62
      2226273.53     13793528.54      2226422.70     13793669.17
      2227526.58     13794171.17      2228209.84     13794325.47
      2228677.42     13794219.46      2229185.54     13793826.08
      2229745.21     13794025.37      2229949.88     13793824.47
      2230175.08     13793917.70      2230318.95     13793826.58
      2230495.13     13793975.40      2230790.22     13793875.52
      2231454.97     13793874.91      2231545.18     13793824.71
      2231730.97     13793922.85      2231925.00     13793917.44
      2232208.89     13793792.17      2232225.00     13793575.00

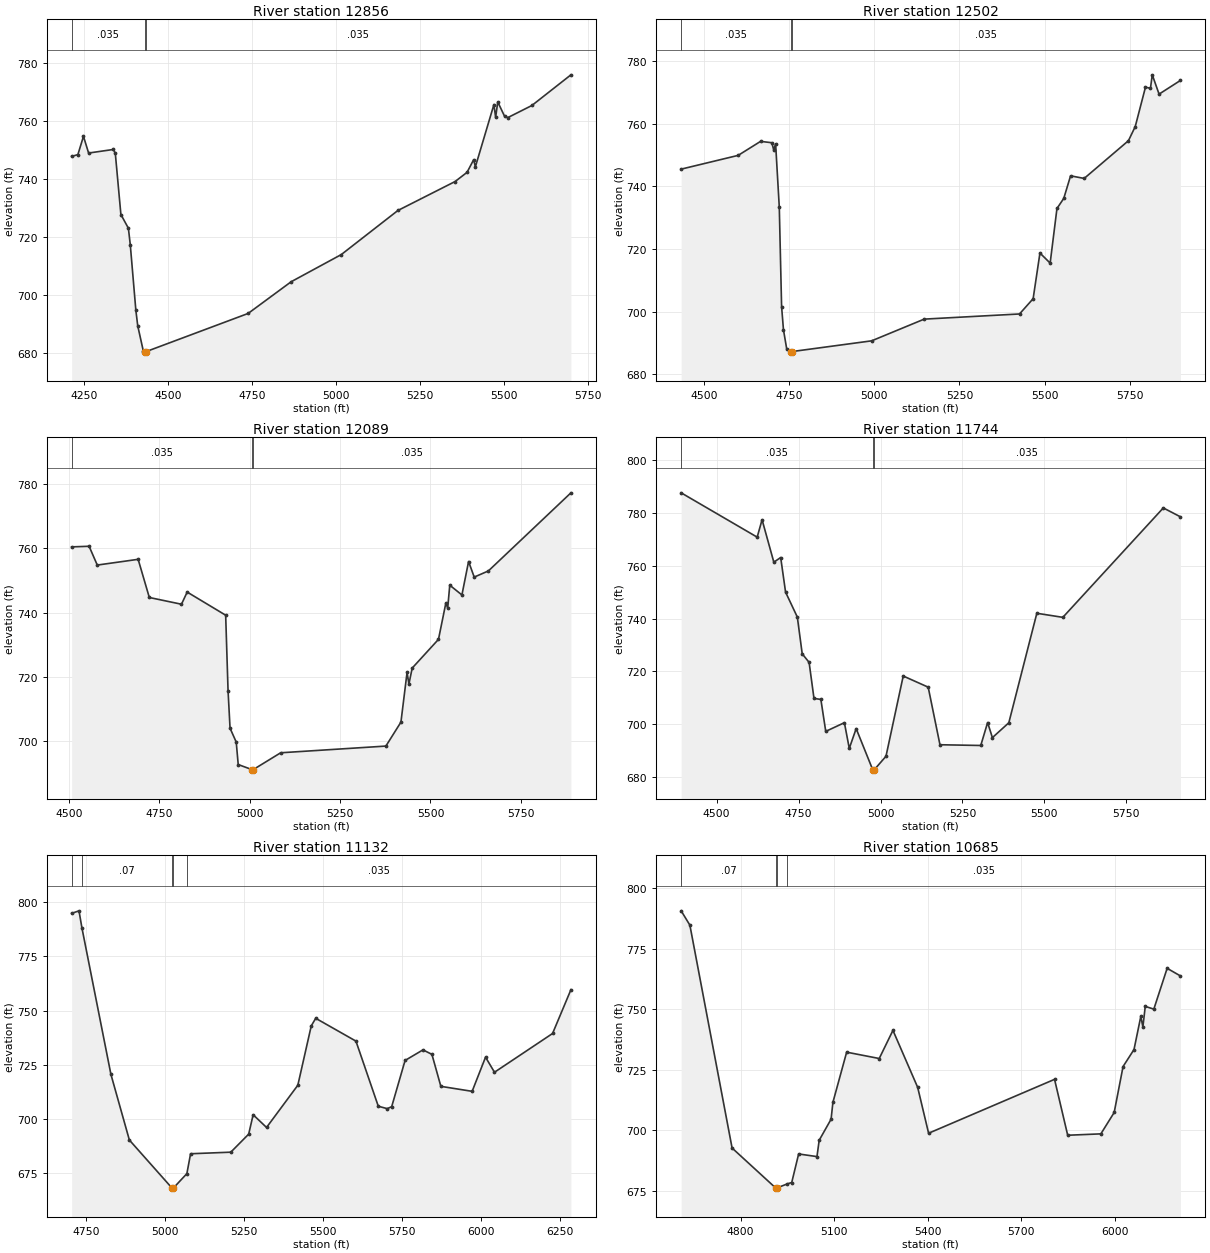
Type RM Length L Ch R = 1,12856,354,354,354
BEGIN DESCRIPTION:
Stream0067 22.0
END DESCRIPTION:
XS GIS Cut Line= 3
      2222553.33     13797009.98      2223054.19     13796024.15
      2223117.79     13795650.50
#Sta/Elev= 30
  4213.7  747.73  4232.3  748.36  4248.9  754.64  4264.2  748.90  4337.9  750.13
  4343.6  748.77  4360.2  727.75  4382.5  723.02  4388.1  717.37  4404.7  694.77
  4410.3  689.43  4427.0  680.71  4430.5  680.55  4430.8  680.05  4434.6  680.55
  4738.5  693.70  4866.5  704.61  5015.7  713.97  5183.9  729.13  5354.1  739.10
  5389.6  742.26  5409.3  746.62  5414.3  744.14  5469.5  765.58  5474.6  761.17
  5480.9  766.49  5501.2  761.54  5511.3  761.12  5582.4  765.26  5698.5  775.81
#Mann=3,-1,0
  4213.7   0.035       0  4430.5   0.035       0  4434.6   0.035       0
Bank Sta=4430.5,4434.6
Exp/Cntr=0.3,0.1

Type RM Length L Ch R = 1,12502,413,413,413
BEGIN DESCRIPTION:
Stream0067 21.0
END DESCRIPTION:
XS GIS Cut Line= 3
      2222887.24     13797097.44      2223125.00     13796575.00
      2223141.65     13795682.25
#Sta/Elev= 30
  4432.4  745.54  4599.9  749.94  4665.8  754.42  4698.8  753.98  4704.4  751.65
  4709.9  753.65  4720.7  733.39  4727.5  701.56  4733.0  694.17  4742.7  687.95
  4754.0  687.22  4754.2  686.72  4758.1  687.22  4992.1  690.65  5146.4  697.59
  5426.5  699.24  5466.5  704.12  5486.5  718.72  5516.5  715.50  5536.5  732.96
  5556.5  736.19  5576.5  743.40  5616.5  742.57  5746.5  754.63  5766.5  759.16
  5796.5  771.73  5811.2  771.39  5816.5  775.69  5836.5  769.52  5899.3  773.90
#Mann=3,-1,0
  4432.4   0.035       0  4754.0   0.035       0  4758.1   0.035       0
Bank Sta=4754,4758.1
Exp/Cntr=0.3,0.1

Type RM Length L Ch R = 1,12089,345,345,345
BEGIN DESCRIPTION:
Stream0067 20.0
END DESCRIPTION:
XS GIS Cut Line= 3
      2223618.66     13796938.42      2223388.10     13796461.41
      2223157.55     13795642.55
#Sta/Elev= 30
  4507.9  760.48  4556.2  760.67  4578.8  754.81  4691.8  756.60  4722.7  744.70
  4811.6  742.60  4827.4  746.39  4933.8  739.18  4940.4  715.63  4945.9  703.95
  4963.0  699.63  4968.5  692.62  5006.0  691.07  5006.3  690.57  5010.3  691.07
  5085.9  696.29  5376.8  698.38  5418.4  705.85  5435.3  721.32  5440.5  717.74
  5449.5  722.69  5522.2  731.65  5542.6  742.98  5547.7  741.41  5553.4  748.54
  5587.0  745.49  5605.4  755.92  5621.0  751.06  5660.2  752.98  5888.4  777.33
#Mann=3,-1,0
  4507.9   0.035       0  5006.0   0.035       0  5010.3   0.035       0
Bank Sta=5006,5010.3
Exp/Cntr=0.3,0.1

Type RM Length L Ch R = 1,11744,612,612,612
BEGIN DESCRIPTION:
Stream0067 19.0
END DESCRIPTION:
XS GIS Cut Line= 4
      2224040.05     13796882.81      2223729.96     13796429.61
      2223634.56     13796207.00      2223197.80     13795619.36
#Sta/Elev= 30
  4391.7  787.73  4623.7  770.91  4638.6  777.52  4674.5  761.41  4695.4  763.19
  4710.3  750.06  4746.2  740.58  4761.1  726.64  4782.1  723.40  4797.0  709.72
  4818.0  709.34  4832.9  697.21  4889.8  700.51  4904.7  690.75  4925.7  698.27
  4976.3  682.63  4976.6  682.13  4980.7  682.63  5016.7  687.77  5069.3  718.22
  5145.5  713.99  5181.4  692.14  5305.9  691.86  5326.8  700.56  5341.4  694.84
  5391.5  700.48  5477.0  742.03  5556.3  740.48  5862.9  782.00  5915.2  778.62
#Mann=3,-1,0
  4391.7   0.035       0  4976.3   0.035       0  4980.7   0.035       0
Bank Sta=4976.3,4980.7
Exp/Cntr=0.3,0.1

Type RM Length L Ch R = 1,11132,447,447,447
BEGIN DESCRIPTION:
Stream0067 18.0
END DESCRIPTION:
XS GIS Cut Line= 4
      2224275.01     13796175.01      2224025.00     13796025.00
      2223675.00     13795675.00      2223113.94     13795113.94
#Sta/Elev= 30
  4703.9  794.93  4727.2  796.11  4736.5  788.20  4828.3  720.43  4886.6  690.11
  5021.5  667.90  5021.8  667.40  5025.9  667.90  5068.6  674.57  5080.3  683.76
  5207.6  684.49  5264.2  692.84  5278.3  701.81  5320.7  695.92  5419.7  715.45
  5462.2  742.90  5476.3  746.41  5603.6  735.85  5674.3  705.74  5702.6  704.62
  5716.7  705.53  5759.1  726.92  5815.7  731.80  5844.0  729.73  5872.3  714.93
  5971.3  712.63  6013.7  728.43  6042.0  721.45  6225.8  739.38  6283.9  759.64
#Mann=5,-1,0
  4703.9   0.035       0  4736.5    0.07       0  5021.5    0.05       0
  5025.9    0.07       0  5068.6   0.035       0
Bank Sta=5021.5,5025.9
Exp/Cntr=0.3,0.1

Type RM Length L Ch R = 1,10685,465,465,465
BEGIN DESCRIPTION:
Stream0067 17.0
END DESCRIPTION:
XS GIS Cut Line= 4
      2224325.01     13795825.01      2224025.00     13795575.00
      2223745.86     13795427.88      2223070.35     13794839.78
#Sta/Elev= 30
  4609.6  790.58  4637.6  784.66  4773.0  692.59  4912.6  676.11  4913.0  675.61
  4917.1  676.11  4950.4  677.79  4964.3  678.34  4986.5  690.14  5045.3  689.05
  5052.4  695.80  5090.6  704.51  5096.4  711.46  5140.5  732.19  5245.0  729.57
  5289.0  741.20  5368.3  717.66  5403.4  698.70  5807.4  720.96  5849.6  697.87
  5956.0  698.44  5998.7  707.27  6027.2  726.25  6062.3  733.28  6084.2  746.98
  6090.8  742.61  6098.4  751.10  6125.9  749.97  6168.6  766.83  6211.3  763.68
#Mann=4,-1,0
  4609.6    0.07       0  4912.6   0.035       0  4917.1    0.07       0
  4950.4   0.035       0
Bank Sta=4912.6,4917.1
Exp/Cntr=0.3,0.1

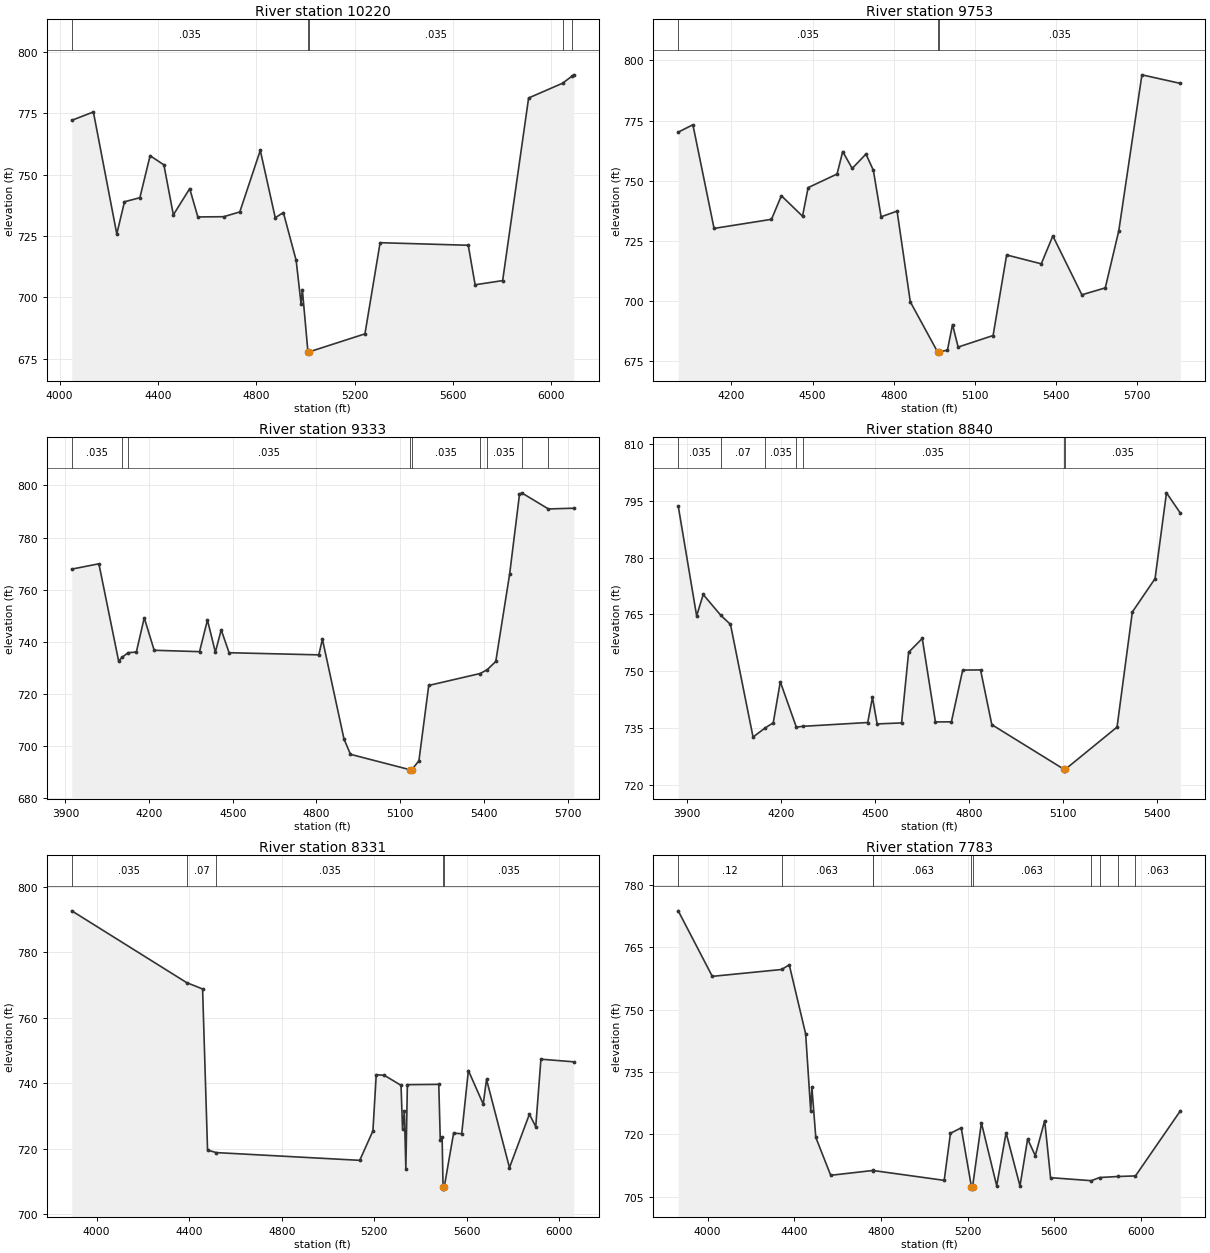
Type RM Length L Ch R = 1,10220,467,467,467
BEGIN DESCRIPTION:
Stream0067 16.0
END DESCRIPTION:
XS GIS Cut Line= 3
      2224890.66     13795396.07      2223975.00     13795125.00
      2223000.03     13794641.54
#Sta/Elev= 30
  4049.2  772.22  4137.2  775.63  4232.4  725.86  4263.7  739.00  4326.3  740.66
  4368.0  757.79  4424.1  754.05  4462.6  733.66  4529.1  744.37  4562.3  732.81
  4667.3  732.91  4733.0  734.86  4816.4  759.96  4877.3  732.48  4910.3  734.61
  4962.4  715.06  4982.3  697.38  4987.5  703.19  5010.3  677.77  5010.6  677.27
  5014.8  677.77  5242.3  685.13  5304.0  722.31  5662.7  721.26  5690.6  705.15
  5802.7  706.85  5908.3  781.32  6046.5  787.35  6086.6  790.36  6092.4  790.77
#Mann=5,-1,0
  4049.2   0.035       0  5010.3   0.035       0  5014.8   0.035       0
  6046.5    0.07       0  6086.6   0.035       0
Bank Sta=5010.3,5014.8
Exp/Cntr=0.3,0.1

Type RM Length L Ch R = 1,9753,420,420,420
BEGIN DESCRIPTION:
Stream0067 15.0
END DESCRIPTION:
XS GIS Cut Line= 5
      2224980.24     13795275.82      2224375.00     13794775.00
      2224175.00     13794725.00      2223975.00     13794575.00
      2223483.99     13794206.74
#Sta/Elev= 30
  4003.5  770.21  4057.7  773.28  4135.9  730.18  4348.1  733.96  4384.7  743.77
  4462.8  735.25  4483.6  747.14  4590.5  752.80  4611.3  762.15  4646.4  755.12
  4697.3  761.10  4724.6  754.34  4753.2  735.01  4812.3  737.37  4861.2  699.63
  4962.0  678.82  4962.4  678.32  4966.6  678.82  4998.4  679.55  5017.1  690.20
  5037.9  680.84  5167.1  685.64  5217.1  719.14  5345.2  715.46  5387.9  727.06
  5495.2  702.57  5581.7  705.46  5631.7  729.22  5717.1  794.04  5859.0  790.48
#Mann=3,-1,0
  4003.5   0.035       0  4962.0   0.035       0  4966.6   0.035       0
Bank Sta=4962,4966.6
Exp/Cntr=0.3,0.1

Type RM Length L Ch R = 1,9333,493,493,493
BEGIN DESCRIPTION:
Stream0067 14.0
END DESCRIPTION:
XS GIS Cut Line= 4
      2225176.36     13795061.06      2224575.00     13794425.00
      2224375.00     13794375.00      2223850.30     13793884.42
#Sta/Elev= 30
  3922.9  767.92  4020.1  769.97  4090.9  732.67  4103.6  734.11  4124.6  735.86
  4154.4  736.12  4182.7  749.25  4218.3  736.80  4380.9  736.27  4409.3  748.40
  4437.6  736.08  4458.6  744.61  4486.9  735.86  4808.5  735.04  4821.4  741.06
  4898.7  702.79  4921.9  696.90  5136.6  690.95  5137.0  690.45  5141.3  690.95
  5167.3  694.40  5202.5  723.31  5386.9  727.89  5411.9  729.33  5442.8  732.50
  5492.6  766.07  5527.8  796.54  5535.8  797.18  5631.5  791.00  5722.7  791.28
#Mann=9,-1,0
  3922.9   0.035       0  4103.6    0.07       0  4124.6   0.035       0
  5136.6   0.035       0  5141.3   0.035       0  5386.9    0.07       0
  5411.9   0.035       0  5535.8    0.07       0  5631.5   0.035       0
Bank Sta=5136.6,5141.3
Exp/Cntr=0.3,0.1

Type RM Length L Ch R = 1,8840,509,509,509
BEGIN DESCRIPTION:
Stream0067 13.0
END DESCRIPTION:
XS GIS Cut Line= 4
      2225353.44     13794967.66      2224825.00     13794175.00
      2224725.00     13794025.00      2224325.03     13793775.02
#Sta/Elev= 30
  3871.1  793.58  3929.9  764.61  3950.9  770.25  4007.5  764.72  4038.1  762.36
  4110.2  732.63  4147.9  734.98  4174.8  736.41  4197.3  747.21  4248.5  735.25
  4268.6  735.46  4476.7  736.47  4491.8  743.10  4506.8  736.10  4584.9  736.36
  4607.4  755.01  4651.0  758.65  4693.1  736.62  4744.1  736.65  4780.2  750.30
  4837.3  750.35  4873.3  735.90  5103.7  724.14  5104.0  723.64  5108.4  724.14
  5273.5  735.26  5322.4  765.64  5395.0  774.44  5431.5  797.08  5475.7  791.75
#Mann=7,-1,0
  3871.1   0.035       0  4007.5    0.07       0  4147.9   0.035       0
  4248.5    0.07       0  4268.6   0.035       0  5103.7   0.035       0
  5108.4   0.035       0
Bank Sta=5103.7,5108.4
Exp/Cntr=0.3,0.1

Type RM Length L Ch R = 1,8331,548,548,548
BEGIN DESCRIPTION:
Stream0067 12.0
END DESCRIPTION:
XS GIS Cut Line= 3
      2225765.20     13794879.27      2225153.06     13793837.83
      2224405.70     13793233.58
#Sta/Elev= 30
  3893.1  792.71  4389.3  770.77  4458.3  768.82  4479.7  719.58  4517.2  718.81
  5137.2  716.44  5194.1  725.43  5208.5  742.63  5243.7  742.42  5315.6  739.37
  5322.0  726.15  5330.0  731.41  5336.4  713.87  5343.0  739.57  5478.7  739.66
  5485.1  722.76  5493.1  723.48  5497.2  708.14  5497.5  707.64  5501.9  708.14
  5542.7  724.73  5577.8  724.59  5606.6  743.90  5670.6  733.64  5685.0  741.16
  5784.1  714.21  5870.2  730.54  5897.6  726.74  5920.0  747.36  6062.2  746.55
#Mann=5,-1,0
  3893.1   0.035       0  4389.3    0.07       0  4517.2   0.035       0
  5497.2   0.035       0  5501.9   0.035       0
Bank Sta=5497.2,5501.9
Exp/Cntr=0.3,0.1

Type RM Length L Ch R = 1,7783,456,456,456
BEGIN DESCRIPTION:
Stream0067 11.0
END DESCRIPTION:
XS GIS Cut Line= 3
      2226194.56     13794760.10      2225789.08     13793829.88
      2224763.48     13793026.90
#Sta/Elev= 30
  3864.6  773.77  4021.8  758.00  4341.7  759.65  4377.0  760.77  4452.7  744.14
  4476.1  725.57  4481.6  731.25  4499.5  719.24  4568.3  710.12  4763.7  711.28
  4765.4  711.26  5092.1  708.90  5121.0  720.23  5170.7  721.54  5218.0  707.29
  5218.3  706.79  5222.9  707.29  5263.8  722.76  5334.4  707.59  5377.8  720.35
  5441.9  707.55  5477.2  718.86  5512.5  714.84  5555.9  723.27  5583.0  709.55
  5771.3  708.82  5809.0  709.58  5893.5  709.83  5975.0  709.97  6181.9  725.62
#Mann=10,-1,0
  3864.6    0.12       0  4341.7   0.063       0  4763.7   0.035       0
  4765.4   0.063       0  5218.0    0.05       0  5222.9   0.063       0
  5771.3   0.035       0  5809.0   0.063       0  5893.5   0.094       0
  5975.0   0.063       0
Bank Sta=5218,5222.9
Exp/Cntr=0.3,0.1

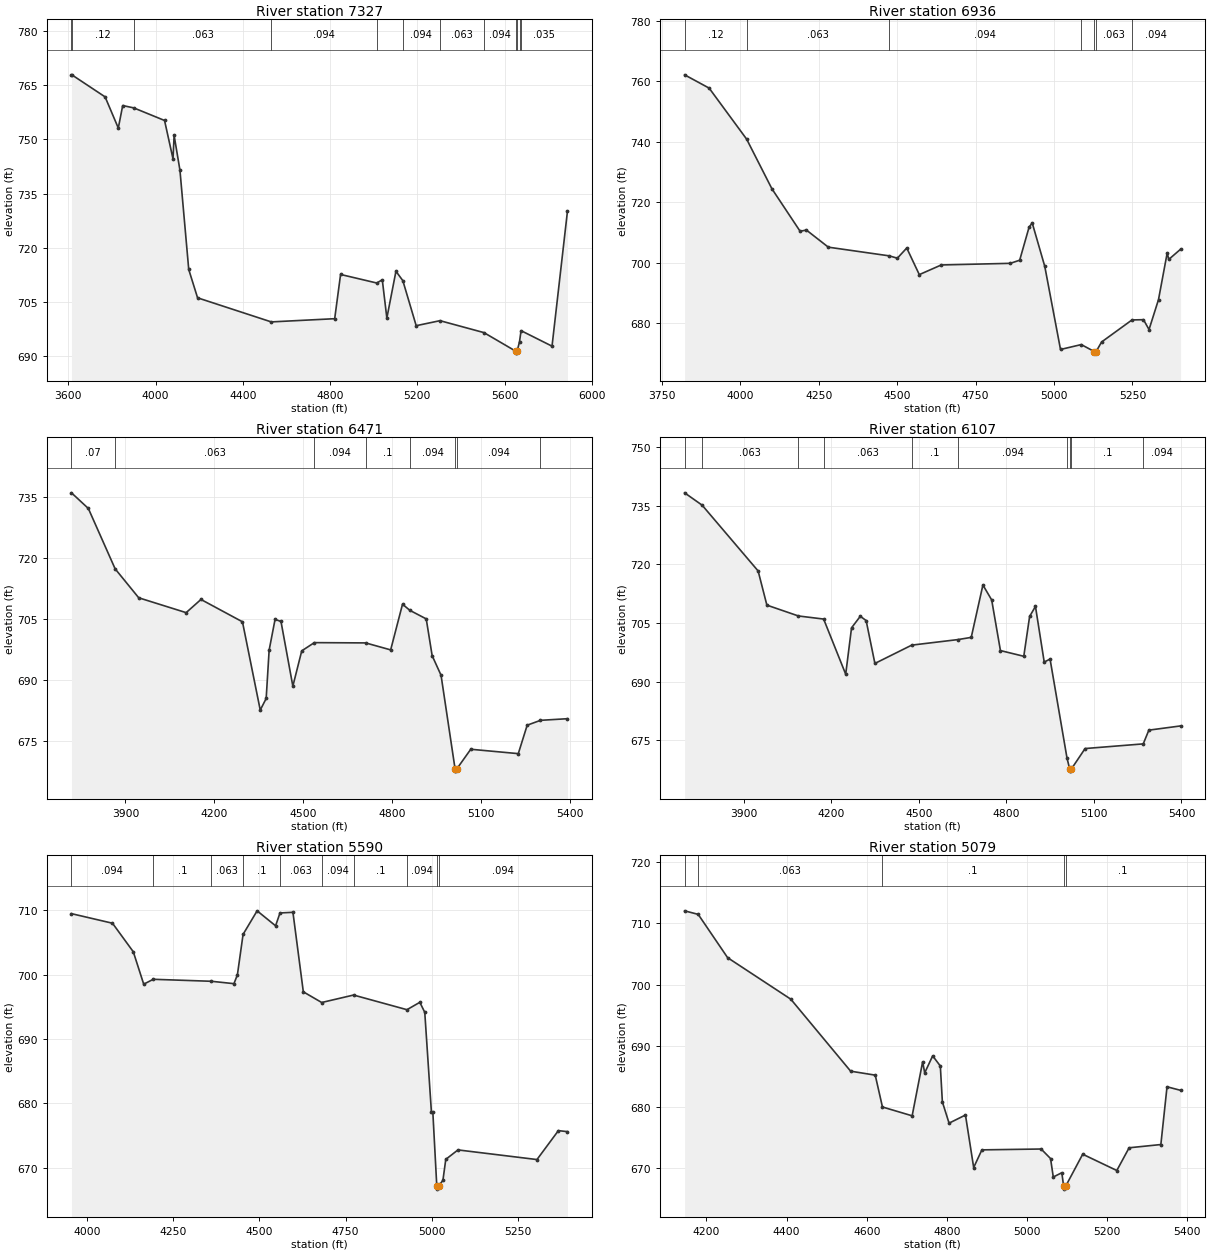
Type RM Length L Ch R = 1,7327,391,391,391
BEGIN DESCRIPTION:
Stream0067 10.0
END DESCRIPTION:
XS GIS Cut Line= 3
      2226313.79     13794807.72      2226146.84     13793591.37
      2225439.63     13792820.60
#Sta/Elev= 30
  3614.3  767.93  3616.0  767.93  3768.5  761.81  3829.0  753.17  3849.2  759.41
  3899.8  758.76  4041.0  755.27  4079.8  744.63  4084.9  751.12  4111.6  741.47
  4151.9  713.94  4192.4  706.08  4530.3  699.40  4821.0  700.29  4848.0  712.56
  5013.7  710.19  5039.2  711.08  5060.1  700.46  5101.8  713.45  5133.4  710.84
  5194.6  698.35  5303.7  699.74  5505.2  696.43  5652.0  691.24  5652.4  690.74
  5657.2  691.24  5668.3  693.92  5675.4  696.97  5817.3  692.67  5888.1  730.13
#Mann=12,-1,0
  3614.3    0.07       0  3616.0    0.12       0  3899.8   0.063       0
  4530.3   0.094       0  5013.7   0.063       0  5133.4   0.094       0
  5303.7   0.063       0  5505.2   0.094       0  5652.0    0.05       0
  5657.2   0.094       0  5668.3     0.1       0  5675.4   0.035       0
Bank Sta=5652,5657.2
Exp/Cntr=0.3,0.1

Type RM Length L Ch R = 1,6936,465,465,465
BEGIN DESCRIPTION:
Stream0067 9.0
END DESCRIPTION:
XS GIS Cut Line= 4
      2226375.00     13794803.23      2226375.00     13793725.00
      2226375.00     13793625.00      2226325.00     13793225.04
#Sta/Elev= 30
  3822.1  762.16  3900.3  757.76  4019.9  740.86  4100.3  724.45  4190.3  710.37
  4210.3  710.77  4280.3  705.10  4474.8  702.22  4500.3  701.45  4530.3  704.82
  4570.3  696.01  4640.3  699.21  4860.3  699.75  4890.3  700.78  4920.3  711.72
  4930.3  713.12  4970.3  698.75  5020.5  671.23  5086.7  672.85  5128.7  670.52
  5129.1  670.02  5133.9  670.52  5151.5  673.71  5248.4  681.01  5285.0  681.09
  5302.7  677.83  5332.9  687.74  5360.6  703.18  5365.6  701.04  5403.4  704.43
#Mann=7,-1,0
  3822.1    0.12       0  4019.9   0.063       0  4474.8   0.094       0
  5086.7   0.063       0  5128.7    0.05       0  5133.9   0.063       0
  5248.4   0.094       0
Bank Sta=5128.7,5133.9
Exp/Cntr=0.3,0.1

Type RM Length L Ch R = 1,6471,364,364,364
BEGIN DESCRIPTION:
Stream0067 8.0
END DESCRIPTION:
XS GIS Cut Line= 4
      2226775.00     13795111.91      2226775.00     13793925.00
      2226775.00     13793825.00      2226747.46     13793439.49
#Sta/Elev= 30
  3718.1  736.12  3775.0  732.27  3865.4  717.39  3945.0  710.25  4105.0  706.59
  4155.0  709.84  4295.0  704.33  4355.0  682.58  4375.0  685.43  4385.0  697.34
  4405.0  704.93  4425.0  704.41  4465.0  688.47  4495.0  697.17  4537.5  699.20
  4710.6  699.13  4795.0  697.41  4835.0  708.67  4859.7  707.16  4915.0  705.05
  4935.0  695.98  4965.0  691.16  5012.4  668.03  5012.8  667.53  5017.6  668.03
  5065.2  672.92  5225.6  671.84  5255.6  678.85  5300.5  680.05  5391.5  680.45
#Mann=8,-1,0
  3718.1    0.07       0  3865.4   0.063       0  4537.5   0.094       0
  4710.6     0.1       0  4859.7   0.094       0  5012.4    0.05       0
  5017.6   0.094       0  5300.5     0.1       0
Bank Sta=5012.4,5017.6
Exp/Cntr=0.3,0.1

Type RM Length L Ch R = 1,6107,517,517,517
BEGIN DESCRIPTION:
XS6187
END DESCRIPTION:
XS GIS Cut Line= 3
      2227092.91     13795276.79      2227092.91     13793893.48
      2227003.84     13793590.62
#Sta/Elev= 30
  3698.1  738.27  3758.2  735.11  3949.9  718.31  3979.9  709.58  4087.9  706.81
  4174.3  706.02  4249.9  691.93  4269.9  703.78  4299.9  706.73  4319.9  705.64
  4349.9  694.68  4476.1  699.36  4634.7  700.78  4679.9  701.34  4719.9  714.72
  4749.9  710.91  4779.9  697.97  4859.9  696.51  4879.9  706.69  4899.9  709.25
  4929.9  695.03  4949.9  695.80  5008.0  670.48  5017.3  667.67  5017.7  667.17
  5022.5  667.67  5069.9  672.94  5269.1  674.13  5288.3  677.64  5397.1  678.72
#Mann=10,-1,0
  3698.1    0.12       0  3758.2   0.063       0  4087.9   0.094       0
  4174.3   0.063       0  4476.1     0.1       0  4634.7   0.094       0
  5008.0     0.1       0  5017.3    0.05       0  5022.5     0.1       0
  5269.1   0.094       0
Bank Sta=5017.3,5022.5
Exp/Cntr=0.3,0.1

Type RM Length L Ch R = 1,5590,511,511,511
BEGIN DESCRIPTION:
Stream0067 7.0
END DESCRIPTION:
XS GIS Cut Line= 3
      2227657.38     13795213.22      2227546.08     13794171.74
      2227390.32     13793813.99
#Sta/Elev= 30
  3955.7  709.49  4074.6  708.00  4134.9  703.56  4165.1  698.52  4192.8  699.28
  4361.5  698.97  4426.6  698.60  4436.6  699.96  4453.1  706.27  4493.8  709.93
  4547.3  707.60  4560.1  709.60  4597.6  709.70  4627.7  697.33  4681.0  695.67
  4773.3  696.83  4928.1  694.55  4965.4  695.70  4979.7  694.14  4999.0  678.60
  5003.1  678.60  5014.5  667.14  5014.9  666.64  5019.8  667.14  5032.3  668.00
  5040.6  671.27  5075.9  672.74  5304.9  671.24  5367.0  675.74  5393.3  675.58
#Mann=10,-1,0
  3955.7   0.094       0  4192.8     0.1       0  4361.5   0.063       0
  4453.1     0.1       0  4560.1   0.063       0  4681.0   0.094       0
  4773.3     0.1       0  4928.1   0.094       0  5014.5    0.05       0
  5019.8   0.094       0
Bank Sta=5014.5,5019.8
Exp/Cntr=0.3,0.1

Type RM Length L Ch R = 1,5079,315,315,315
BEGIN DESCRIPTION:
Stream0067 6.0
END DESCRIPTION:
XS GIS Cut Line= 3
      2228205.94     13795109.83      2228025.00     13794275.00
      2227823.65     13793948.86
#Sta/Elev= 30
  4145.7  712.06  4179.6  711.48  4253.0  704.41  4410.7  697.63  4559.9  685.88
  4621.3  685.23  4639.3  680.03  4713.4  678.59  4739.6  687.42  4744.7  685.60
  4764.6  688.38  4783.7  686.72  4788.8  680.86  4805.5  677.39  4846.4  678.72
  4866.9  670.15  4887.4  673.03  5035.2  673.17  5058.7  671.61  5065.5  668.60
  5086.8  669.30  5091.3  667.12  5091.7  666.62  5096.6  667.12  5138.9  672.32
  5224.0  669.66  5254.7  673.37  5333.9  673.90  5349.3  683.33  5383.2  682.75
#Mann=5,-1,0
  4145.7   0.094       0  4179.6   0.063       0  4639.3     0.1       0
  5091.3    0.05       0  5096.6     0.1       0
Bank Sta=5091.3,5096.6
Exp/Cntr=0.3,0.1

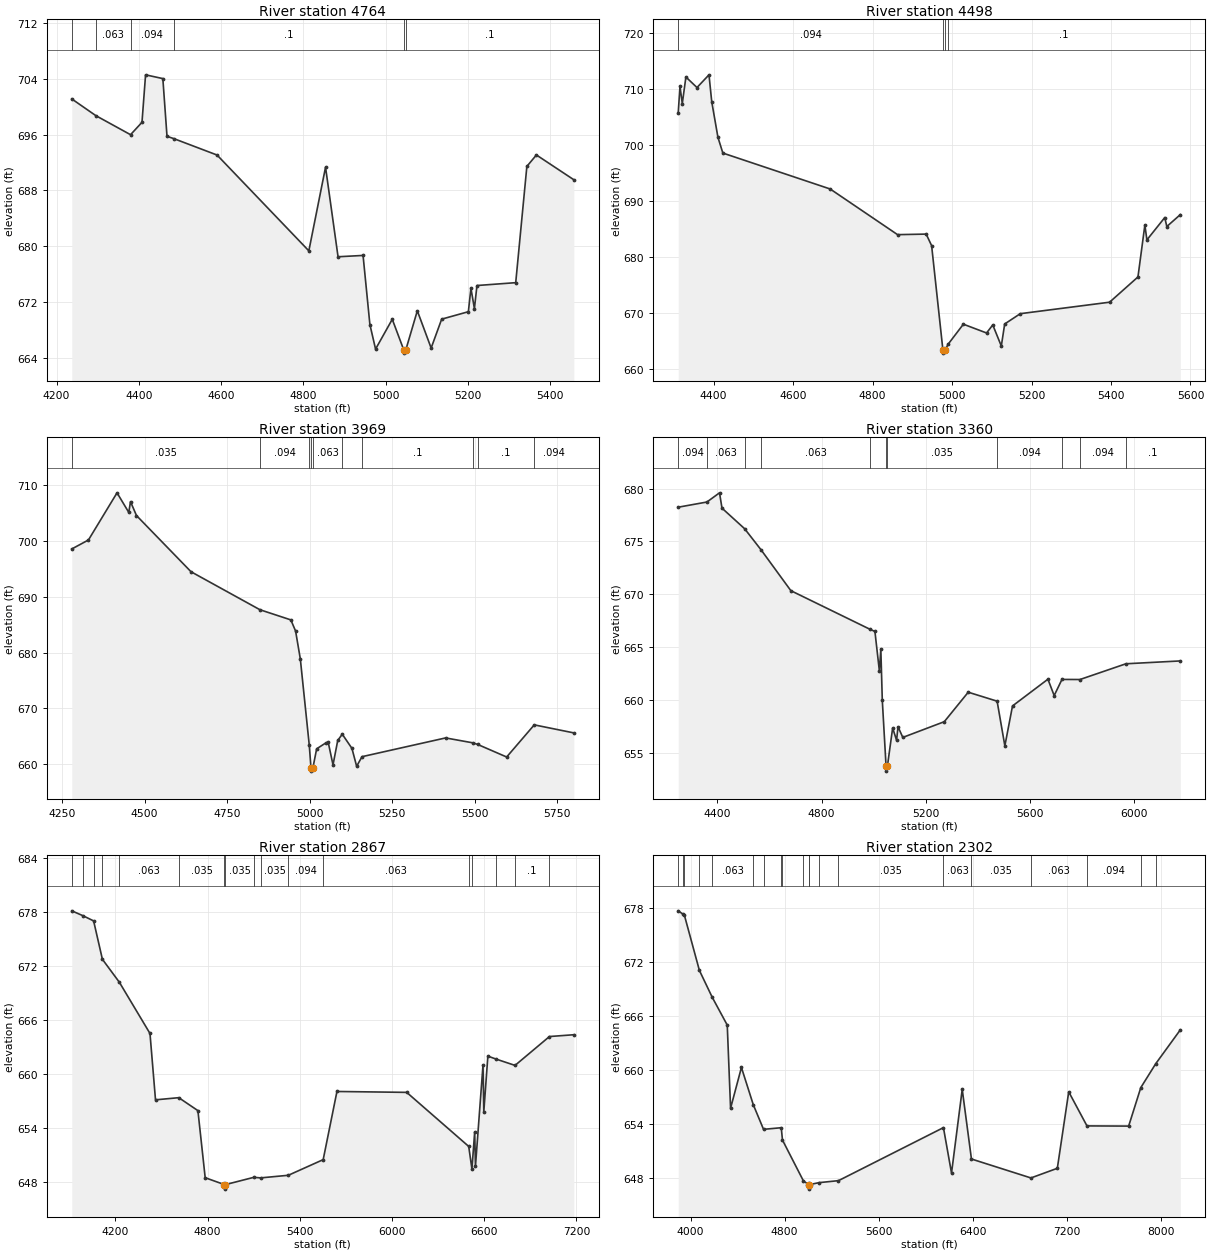
Type RM Length L Ch R = 1,4764,266,266,266
BEGIN DESCRIPTION:
E20830
END DESCRIPTION:
XS GIS Cut Line= 3
      2228450.33     13795073.34      2228306.20     13794215.62
      2228022.69     13794009.10
#Sta/Elev= 30
  4237.1  701.15  4295.6  698.75  4380.0  696.01  4407.8  697.79  4416.5  704.61
  4458.5  704.07  4468.6  695.78  4485.5  695.44  4590.3  693.09  4813.4  679.33
  4854.0  691.34  4884.4  678.48  4945.2  678.67  4961.8  668.75  4975.6  665.22
  5016.2  669.50  5043.9  665.14  5044.4  664.64  5049.3  665.14  5077.1  670.72
  5110.7  665.37  5136.3  669.52  5201.2  670.59  5207.4  673.95  5215.9  671.04
  5222.1  674.35  5316.3  674.76  5343.4  691.46  5366.6  693.10  5457.6  689.54
#Mann=6,-1,0
  4237.1   0.035       0  4295.6   0.063       0  4380.0   0.094       0
  4485.5     0.1       0  5043.9    0.05       0  5049.3     0.1       0
Bank Sta=5043.9,5049.3
Exp/Cntr=0.3,0.1

Type RM Length L Ch R = 1,4498,529,529,529
BEGIN DESCRIPTION:
XS6186
END DESCRIPTION:
XS GIS Cut Line= 3
      2228913.51     13794831.60      2228484.21     13794108.14
      2228070.67     13794022.28
#Sta/Elev= 30
  4310.8  705.82  4315.2  710.50  4321.0  707.43  4330.1  712.18  4358.0  710.30
  4388.2  712.57  4395.1  707.77  4410.7  701.41  4423.1  698.59  4693.2  692.17
  4862.8  684.01  4934.8  684.11  4948.5  682.05  4977.0  663.34  4977.4  662.84
  4982.4  663.34  4989.7  664.40  5028.4  668.01  5086.8  666.44  5102.4  667.88
  5123.9  664.11  5132.4  668.05  5171.7  669.89  5396.4  671.94  5467.8  676.45
  5485.2  685.73  5490.3  683.07  5535.3  687.07  5540.4  685.46  5574.4  687.59
#Mann=4,-1,0
  4310.8   0.094       0  4977.0    0.05       0  4982.4   0.094       0
  4989.7     0.1       0
Bank Sta=4977,4982.4
Exp/Cntr=0.3,0.1

Type RM Length L Ch R = 1,3969,609,609,609
BEGIN DESCRIPTION:
XS6185
END DESCRIPTION:
XS GIS Cut Line= 3
      2229223.57     13794624.88      2229072.52     13794036.59
      2228369.77     13793453.08
#Sta/Elev= 30
  4279.6  698.56  4330.1  700.17  4416.7  708.62  4452.3  705.11  4457.5  707.04
  4475.6  704.55  4640.8  694.48  4849.6  687.67  4943.2  685.85  4957.6  683.84
  4971.9  678.86  4999.0  663.39  5004.3  659.25  5004.8  658.75  5009.7  659.25
  5021.4  662.75  5050.0  663.84  5056.5  663.88  5070.9  659.87  5085.2  664.24
  5098.9  665.37  5128.2  662.83  5142.5  659.62  5158.8  661.34  5412.0  664.70
  5494.4  663.82  5509.2  663.53  5596.9  661.28  5680.5  667.04  5800.4  665.60
#Mann=10,-1,0
  4279.6   0.035       0  4849.6   0.094       0  4999.0   0.063       0
  5004.3    0.05       0  5009.7   0.063       0  5098.9   0.094       0
  5158.8     0.1       0  5494.4   0.094       0  5509.2     0.1       0
  5680.5   0.094       0
Bank Sta=5004.3,5009.7
Exp/Cntr=0.3,0.1

Type RM Length L Ch R = 1,3360,493,493,493
BEGIN DESCRIPTION:
Stream0067 5.0
END DESCRIPTION:
XS GIS Cut Line= 4
      2229438.23     13794609.00      2229629.04     13794171.74
      2229477.99     13793853.73      2228461.90     13793435.86
#Sta/Elev= 30
  4249.9  678.24  4360.0  678.73  4408.4  679.60  4417.9  678.15  4504.9  676.20
  4568.7  674.18  4682.3  670.34  4984.9  666.70  5005.1  666.48  5022.2  662.75
  5027.8  664.81  5033.4  659.98  5047.8  653.76  5048.2  653.26  5053.2  653.76
  5073.2  657.34  5088.3  656.18  5093.7  657.46  5112.2  656.45  5271.5  657.94
  5363.4  660.73  5474.3  659.88  5504.0  655.65  5533.4  659.43  5669.4  661.96
  5693.4  660.41  5723.3  661.94  5792.3  661.93  5968.9  663.42  6177.7  663.69
#Mann=11,-1,0
  4249.9   0.094       0  4360.0   0.063       0  4504.9   0.035       0
  4568.7   0.063       0  4984.9   0.035       0  5047.8   0.035       0
  5053.2   0.035       0  5474.3   0.094       0  5723.3     0.1       0
  5792.3   0.094       0  5968.9     0.1       0
Bank Sta=5047.8,5053.2
Exp/Cntr=0.3,0.1

Type RM Length L Ch R = 1,2867,565,565,565
BEGIN DESCRIPTION:
Stream0067 4.0
END DESCRIPTION:
XS GIS Cut Line= 4
      2229485.94     13794624.90      2230066.30     13793972.99
      2228993.02     13793336.97      2227864.08     13793138.21
#Sta/Elev= 30
  3916.6  678.18  3987.6  677.65  4058.7  677.06  4115.9  672.79  4226.5  670.23
  4425.5  664.54  4461.4  657.16  4612.8  657.40  4737.3  655.96  4784.7  648.50
  4910.3  647.73  4910.7  647.23  4915.7  647.73  5100.7  648.54  5145.7  648.48
  5325.6  648.77  5552.4  650.51  5642.0  658.09  6095.9  657.99  6499.3  651.98
  6520.2  649.47  6538.1  653.59  6543.2  649.79  6592.3  661.04  6597.4  655.83
  6623.9  662.02  6679.3  661.68  6800.7  660.99  7024.6  664.20  7183.3  664.40
#Mann=17,-1,0
  3916.6   0.094       0  3987.6   0.063       0  4058.7   0.094       0
  4115.9   0.035       0  4226.5   0.063       0  4612.8   0.035       0
  4910.3   0.035       0  4915.7   0.035       0  5100.7   0.063       0
  5145.7   0.035       0  5325.6   0.094       0  5552.4   0.063       0
  6499.3   0.094       0  6520.2     0.1       0  6679.3   0.094       0
  6800.7     0.1       0  7024.6   0.094       0
Bank Sta=4910.3,4915.7
Exp/Cntr=0.3,0.1

Type RM Length L Ch R = 1,2302,372,372,372
BEGIN DESCRIPTION:
Stream0067 3.0
END DESCRIPTION:
XS GIS Cut Line= 5
      2229541.59     13794601.05      2230217.36     13793965.04
      2230519.47     13793734.48      2230424.06     13793440.32
      2227800.50     13793050.76
#Sta/Elev= 30
  3894.8  677.67  3935.7  677.30  3946.2  677.23  4074.8  671.06  4184.0  668.08
  4311.6  665.00  4339.9  655.78  4432.2  660.30  4533.0  656.17  4620.2  653.44
  4770.7  653.62  4781.3  652.25  4959.4  647.72  5004.5  647.31  5005.0  646.81
  5010.1  647.31  5092.9  647.53  5257.5  647.75  6150.0  653.63  6218.8  648.59
  6309.8  657.87  6388.2  650.15  6894.1  648.05  7118.6  649.12  7215.5  657.60
  7370.7  653.82  7725.1  653.80  7828.5  658.07  7956.0  660.73  8164.4  664.47
#Mann=20,-1,0
  3894.8   0.094       0  3935.7   0.063       0  3946.2   0.094       0
  4074.8   0.035       0  4184.0   0.063       0  4533.0   0.035       0
  4620.2   0.063       0  4770.7   0.035       0  4781.3   0.063       0
  4959.4   0.035       0  5004.5   0.035       0  5010.1   0.035       0
  5092.9   0.063       0  5257.5   0.035       0  6150.0   0.063       0
  6388.2   0.035       0  6894.1   0.063       0  7370.7   0.094       0
  7828.5   0.063       0  7956.0   0.094       0
Bank Sta=5004.5,5010.1
Exp/Cntr=0.3,0.1

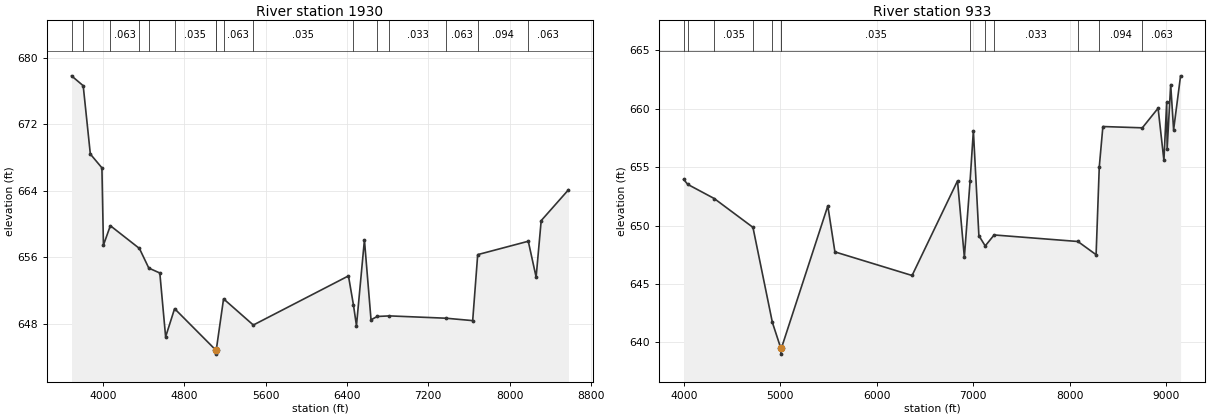
Type RM Length L Ch R = 1,1930,997,997,997
BEGIN DESCRIPTION:
Stream0067 2.0
END DESCRIPTION:
XS GIS Cut Line= 5
      2229581.33     13794656.71      2230678.47     13793917.33
      2230861.33     13793702.68      2230465.08     13793359.36
      2227729.51     13792995.18
#Sta/Elev= 30
  3691.1  677.85  3806.1  676.66  3876.2  668.44  3990.2  666.78  4005.2  657.48
  4073.1  659.82  4359.2  657.08  4451.5  654.72  4559.9  654.13  4616.9  646.45
  4705.2  649.84  5109.6  644.87  5110.0  644.37  5115.2  644.87  5186.9  651.02
  5479.6  647.87  6415.7  653.78  6465.1  650.26  6494.4  647.79  6572.7  658.11
  6637.6  648.50  6698.6  648.90  6818.9  648.97  7376.4  648.69  7637.8  648.40
  7687.1  656.34  8184.7  657.95  8261.8  653.64  8311.7  660.43  8580.1  664.14
#Mann=16,-1,0
  3691.1   0.063       0  3806.1   0.035       0  4073.1   0.063       0
  4359.2   0.035       0  4451.5   0.063       0  4705.2   0.035       0
  5109.6   0.035       0  5115.2   0.035       0  5186.9   0.063       0
  5479.6   0.035       0  6465.1   0.063       0  6698.6   0.035       0
  6818.9   0.033       0  7376.4   0.063       0  7687.1   0.094       0
  8184.7   0.063       0
Bank Sta=5109.6,5115.2
Exp/Cntr=0.3,0.1

Type RM Length L Ch R = 1,933,0,0,0
BEGIN DESCRIPTION:
Stream0067 1.0
END DESCRIPTION:
XS GIS Cut Line= 4
      2231386.04     13794839.59      2231640.45     13793766.28
      2230010.65     13793154.11      2227713.05     13792947.41
#Sta/Elev= 30
  3998.4  653.96  4041.0  653.53  4315.4  652.32  4717.1  649.85  4918.6  641.71
  5006.1  639.50  5006.6  639.00  5011.8  639.50  5493.1  651.69  5566.6  647.75
  6366.5  645.73  6837.4  653.83  6908.3  647.29  6967.6  653.81  7001.8  658.12
  7058.9  649.14  7124.5  648.26  7216.8  649.20  8085.3  648.64  8273.8  647.51
  8306.6  655.01  8344.1  658.48  8753.1  658.37  8916.4  660.05  8976.7  655.58
  9005.3  660.55  9010.3  656.57  9046.9  662.07  9077.1  658.20  9149.3  662.82
#Mann=13,-1,0
  3998.4   0.035       0  4041.0   0.094       0  4315.4   0.035       0
  4717.1    0.05       0  4918.6   0.035       0  5006.1   0.035       0
  5011.8   0.035       0  6967.6   0.063       0  7124.5   0.035       0
  7216.8   0.033       0  8085.3   0.063       0  8306.6   0.094       0
  8753.1   0.063       0
Bank Sta=5006.1,5011.8
Exp/Cntr=0.3,0.1

Chan Stop Cuts=-1