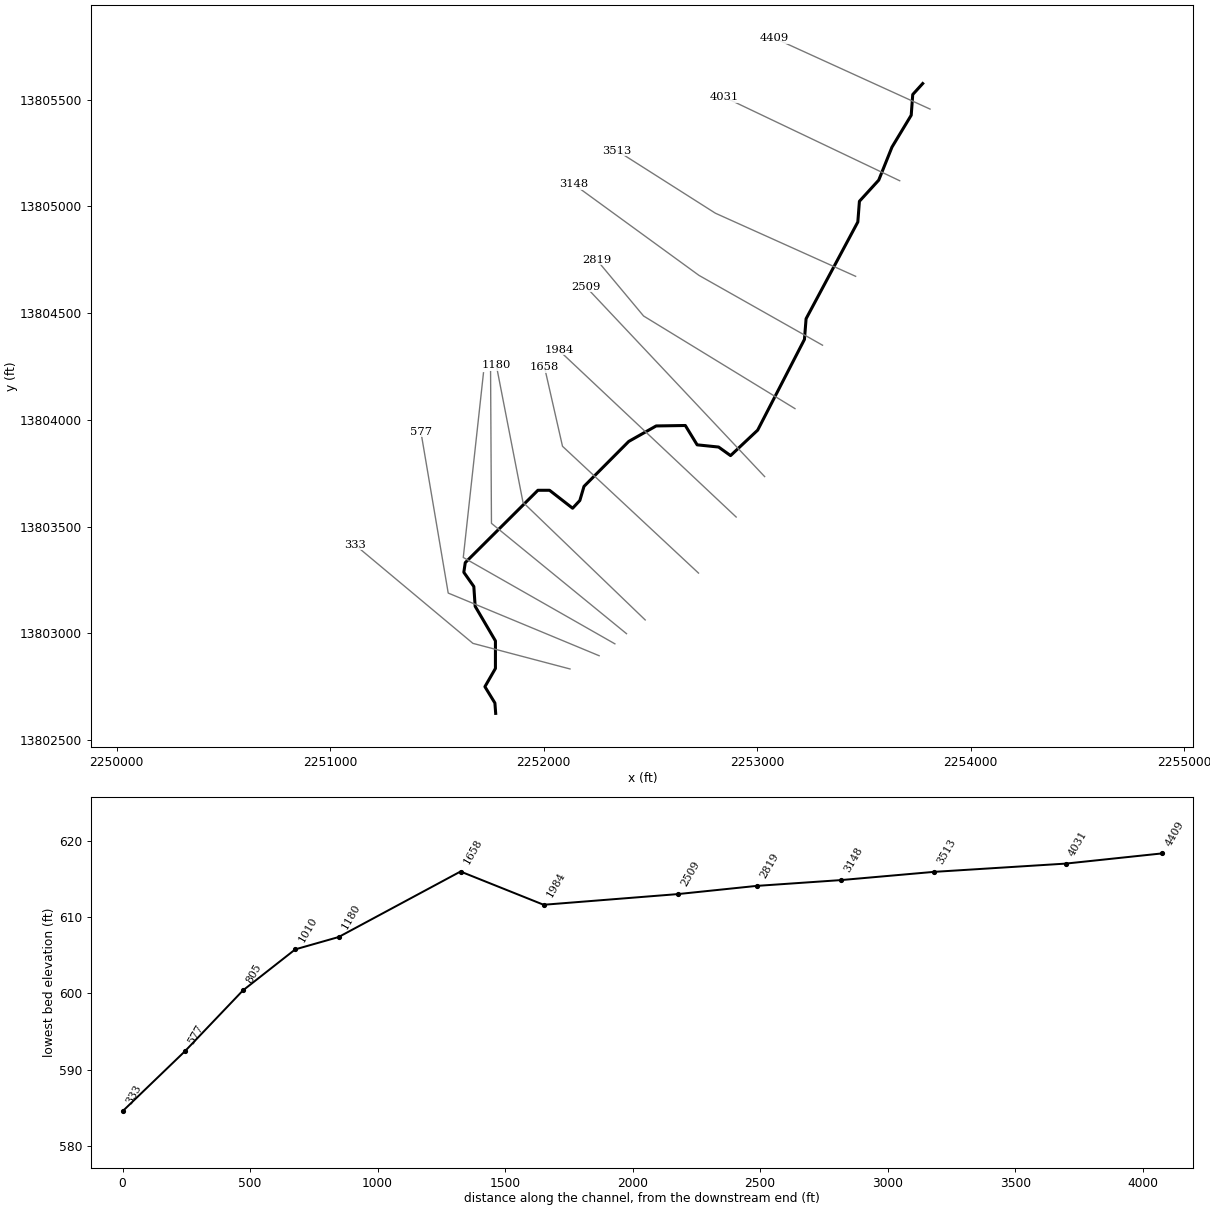
--- Stream0110.prj (project) ---

Proj Title=Stream0110 Base Level Engineering
Current Plan=p01
Default Exp/Contr=0.3,0.1
English Units
Geom File=g01
Flow File=f01
Plan File=p01
Y Axis Title=Elevation
X Axis Title(PF)=Main Channel Distance
X Axis Title(XS)=Station
BEGIN DESCRIPTION:
Stream0110
END DESCRIPTION:
DSS Export Rating Curves= 0
DSS Export Rating Curve Sorted= 0
DSS Export Volume Flow Curves= 0
DXF OffsetX= 0
DXF OffsetY= 0
DXF ScaleX= 1
DXF ScaleY= 10

--- Stream0110.p01 (plan) ---

Plan Title=Multiple Run
Short Identifier=Multiple
Geom File=g01
Flow File=f01
Subcritical Flow
K Sum by GR= 0
Std Step Tol= 0.01
Critical Tol= 0.01
Num of Std Step Trials= 20
Max Error Tol= 0.3
Flow Tol Ratio= 0.001
Split Flow NTrial= 30
Split Flow Tol= 0.02
Split Flow Ratio= 0.02
Log Output Level= 0
Friction Slope Method= 1
Unsteady Friction Slope Method= 2
Unsteady Bridges Friction Slope Method= 1
Parabolic Critical Depth
Global Vel Dist=  1 , 1 , 1
Global Log Level= 0
CheckData=True
Encroach Param= -1, 0, 0, 0
BEGIN DESCRIPTION:
Multiple Run
END DESCRIPTION:

--- Stream0110.f01 (steady flow) ---

Flow Title=Multiple
Number of Profiles=7
Profile Names=10-year,25-year,50-year,1pct_min,100-year,1pct_plu,500-year
River Rch & RM= Stream0110,Reach-1,4409
     650    1035    1376     885    1767    3525    2880
Boundary for River Rch & Prof#=Stream0110,Reach-1,1
Up Type=0
Dn Type=3
Dn Slope=0.005
Boundary for River Rch & Prof#=Stream0110,Reach-1,2
Up Type=0
Dn Type=3
Dn Slope=0.005
Boundary for River Rch & Prof#=Stream0110,Reach-1,3
Up Type=0
Dn Type=3
Dn Slope=0.005
Boundary for River Rch & Prof#=Stream0110,Reach-1,4
Up Type=0
Dn Type=3
Dn Slope=0.005
Boundary for River Rch & Prof#=Stream0110,Reach-1,5
Up Type=0
Dn Type=3
Dn Slope=0.005
Boundary for River Rch & Prof#=Stream0110,Reach-1,6
Up Type=0
Dn Type=3
Dn Slope=0.005
Boundary for River Rch & Prof#=Stream0110,Reach-1,7
Up Type=0
Dn Type=3
Dn Slope=0.005

--- Stream0110.g01 (geometry) ---

Geom Title=Existing Conditions

River Reach=Stream0110,Reach-1
Reach XY= 30
      2253775.00     13805575.00      2253728.39     13805523.60
      2253721.20     13805426.57      2253631.08     13805277.20
      2253569.15     13805122.71      2253478.62     13805023.50
      2253471.17     13804926.59      2253228.83     13804473.42
      2253221.17     13804376.58      2253001.99     13803951.53
      2252875.10     13803832.31      2252819.10     13803872.43
      2252718.57     13803882.79      2252663.16     13803973.37
      2252526.56     13803971.26      2252398.18     13803898.71
      2252188.63     13803688.18      2252169.14     13803622.14
      2252135.32     13803585.83      2252027.29     13803669.91
      2251972.71     13803669.93      2251632.48     13803331.06
      2251625.72     13803285.71      2251672.62     13803219.03
      2251678.83     13803126.58      2251773.81     13802964.50
      2251773.78     13802835.50      2251724.53     13802750.00
      2251771.31     13802673.51      2251775.00     13802625.00

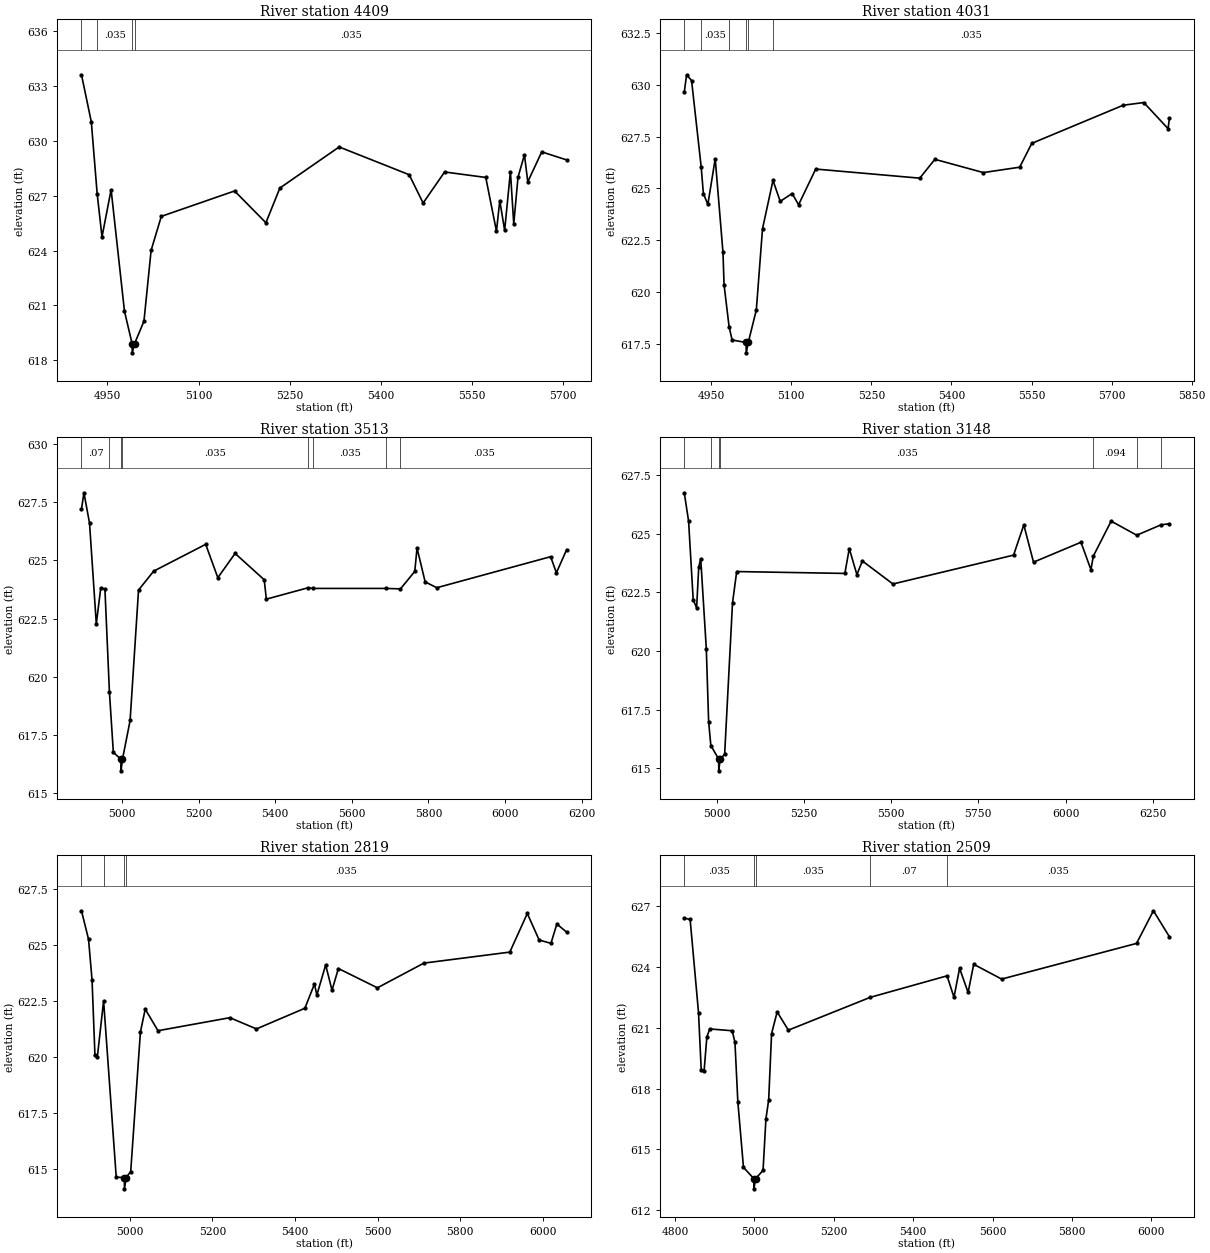
Type RM Length L Ch R = 1,4409,378,378,378
BEGIN DESCRIPTION:
XS6208
END DESCRIPTION:
XS GIS Cut Line= 2
      2253809.39     13805455.38      2253082.12     13805786.74
#Sta/Elev= 30
  4907.2  633.62  4923.4  631.04  4933.0  627.12  4941.0  624.75  4956.0  627.33
  4978.0  620.68  4990.6  618.90  4990.8  618.40  4994.6  618.90  5010.1  620.13
  5021.9  624.01  5038.7  625.87  5159.4  627.26  5211.0  625.52  5234.0  627.42
  5331.7  629.67  5447.0  628.15  5470.0  626.60  5505.4  628.30  5573.2  628.00
  5590.8  625.06  5596.3  626.73  5604.3  625.10  5613.8  628.32  5619.3  625.46
  5626.3  628.01  5636.9  629.24  5642.4  627.76  5665.4  629.40  5706.4  628.96
#Mann=4,-1,0
  4907.2   0.063       0  4933.0   0.035       0  4990.6   0.035       0
  4994.6   0.035       0
Bank Sta=4990.6,4994.6
Exp/Cntr=0.3,0.1

Type RM Length L Ch R = 1,4031,518,518,518
BEGIN DESCRIPTION:
XS6207
END DESCRIPTION:
XS GIS Cut Line= 2
      2253667.32     13805119.73      2252846.79     13805510.67
#Sta/Elev= 30
  4899.4  629.64  4903.8  630.48  4913.1  630.20  4931.1  626.03  4935.2  624.75
  4943.6  624.22  4957.4  626.43  4971.9  621.91  4974.0  620.33  4983.4  618.32
  4989.0  617.68  5015.2  617.56  5015.5  617.06  5019.3  617.56  5034.4  619.13
  5046.0  623.05  5065.6  625.38  5079.2  624.37  5101.4  624.75  5113.6  624.21
  5145.7  625.93  5340.6  625.49  5368.9  626.40  5459.7  625.76  5527.8  626.02
  5550.5  627.17  5721.7  629.01  5760.3  629.14  5805.8  627.88  5808.3  628.38
#Mann=6,-1,0
  4899.4   0.094       0  4931.1   0.035       0  4983.4    0.07       0
  5015.2    0.05       0  5019.3    0.07       0  5065.6   0.035       0
Bank Sta=5015.2,5019.3
Exp/Cntr=0.3,0.1

Type RM Length L Ch R = 1,3513,365,365,365
BEGIN DESCRIPTION:
XS6206
END DESCRIPTION:
XS GIS Cut Line= 3
      2253460.83     13804672.13      2252803.87     13804967.76
      2252342.50     13805261.02
#Sta/Elev= 30
  4893.9  627.19  4900.3  627.89  4914.9  626.59  4932.6  622.27  4944.2  623.81
  4955.1  623.77  4966.9  619.34  4977.1  616.76  4996.9  616.47  4997.2  615.97
  5001.0  616.47  5020.9  618.13  5042.9  623.72  5082.4  624.53  5218.3  625.68
  5250.0  624.25  5295.1  625.29  5371.2  624.16  5376.7  623.33  5486.1  623.82
  5499.0  623.79  5689.7  623.79  5727.0  623.77  5764.4  624.52  5770.3  625.52
  5791.5  624.07  5821.9  623.82  6119.2  625.15  6134.3  624.46  6161.0  625.45
#Mann=8,-1,0
  4893.9    0.07       0  4966.9   0.035       0  4996.9   0.035       0
  5001.0   0.035       0  5486.1    0.07       0  5499.0   0.035       0
  5689.7    0.07       0  5727.0   0.035       0
Bank Sta=4996.9,5001
Exp/Cntr=0.3,0.1

Type RM Length L Ch R = 1,3148,329,329,329
BEGIN DESCRIPTION:
XS6205
END DESCRIPTION:
XS GIS Cut Line= 3
      2253305.83     13804349.40      2252727.08     13804676.52
      2252140.01     13805103.82
#Sta/Elev= 30
  4906.9  626.75  4919.3  625.54  4932.5  622.19  4942.3  621.84  4948.4  623.58
  4954.1  623.94  4970.1  620.09  4976.8  616.98  4983.1  615.97  5005.6  615.39
  5005.8  614.89  5009.7  615.39  5022.7  615.60  5045.2  622.05  5057.2  623.39
  5367.3  623.31  5380.0  624.37  5401.8  623.26  5417.6  623.84  5505.2  622.86
  5851.0  624.09  5880.4  625.38  5908.2  623.79  6044.3  624.64  6072.8  623.47
  6079.7  624.05  6130.8  625.54  6204.2  624.94  6273.2  625.38  6297.8  625.43
#Mann=7,-1,0
  4906.9   0.063       0  4983.1   0.035       0  5005.6   0.035       0
  5009.7   0.035       0  6079.7   0.094       0  6204.2    0.05       0
  6273.2   0.035       0
Bank Sta=5005.6,5009.7
Exp/Cntr=0.3,0.1

Type RM Length L Ch R = 1,2819,310,310,310
BEGIN DESCRIPTION:
XS6204
END DESCRIPTION:
XS GIS Cut Line= 3
      2253176.80     13804052.41      2252467.66     13804486.24
      2252246.95     13804750.73
#Sta/Elev= 30
  4882.5  626.51  4899.6  625.24  4908.1  623.43  4915.1  620.09  4920.9  619.99
  4936.1  622.50  4966.7  614.65  4986.4  614.63  4986.7  614.13  4990.6  614.63
  5001.8  614.90  5025.3  621.11  5037.0  622.13  5067.9  621.17  5242.1  621.75
  5306.6  621.25  5423.9  622.17  5447.1  623.25  5453.0  622.76  5474.3  624.10
  5489.7  622.97  5505.1  623.94  5599.7  623.08  5712.4  624.18  5920.6  624.67
  5963.0  626.39  5991.7  625.21  6020.3  625.06  6034.6  625.92  6058.3  625.56
#Mann=4,-1,0
  4882.5   0.063       0  4936.1   0.035       0  4986.4   0.035       0
  4990.6   0.035       0
Bank Sta=4986.4,4990.6
Exp/Cntr=0.3,0.1

Type RM Length L Ch R = 1,2509,525,525,525
BEGIN DESCRIPTION:
XS6203
END DESCRIPTION:
XS GIS Cut Line= 2
      2253034.71     13803734.01      2252196.70     13804623.96
#Sta/Elev= 30
  4823.2  626.41  4838.0  626.34  4859.1  621.75  4865.9  618.93  4873.2  618.88
  4880.1  620.54  4887.4  620.94  4944.0  620.85  4950.9  620.28  4958.2  617.34
  4972.4  614.11  4998.6  613.55  4998.8  613.05  5002.8  613.55  5021.7  613.96
  5029.0  616.51  5035.9  617.44  5043.2  620.71  5057.3  621.78  5085.5  620.88
  5292.0  622.50  5485.4  623.56  5502.8  622.50  5516.9  623.93  5538.4  622.74
  5552.5  624.13  5622.9  623.40  5962.8  625.16  6005.3  626.77  6045.6  625.49
#Mann=5,-1,0
  4823.2   0.035       0  4998.6   0.035       0  5002.8   0.035       0
  5292.0    0.07       0  5485.4   0.035       0
Bank Sta=4998.6,5002.8
Exp/Cntr=0.3,0.1

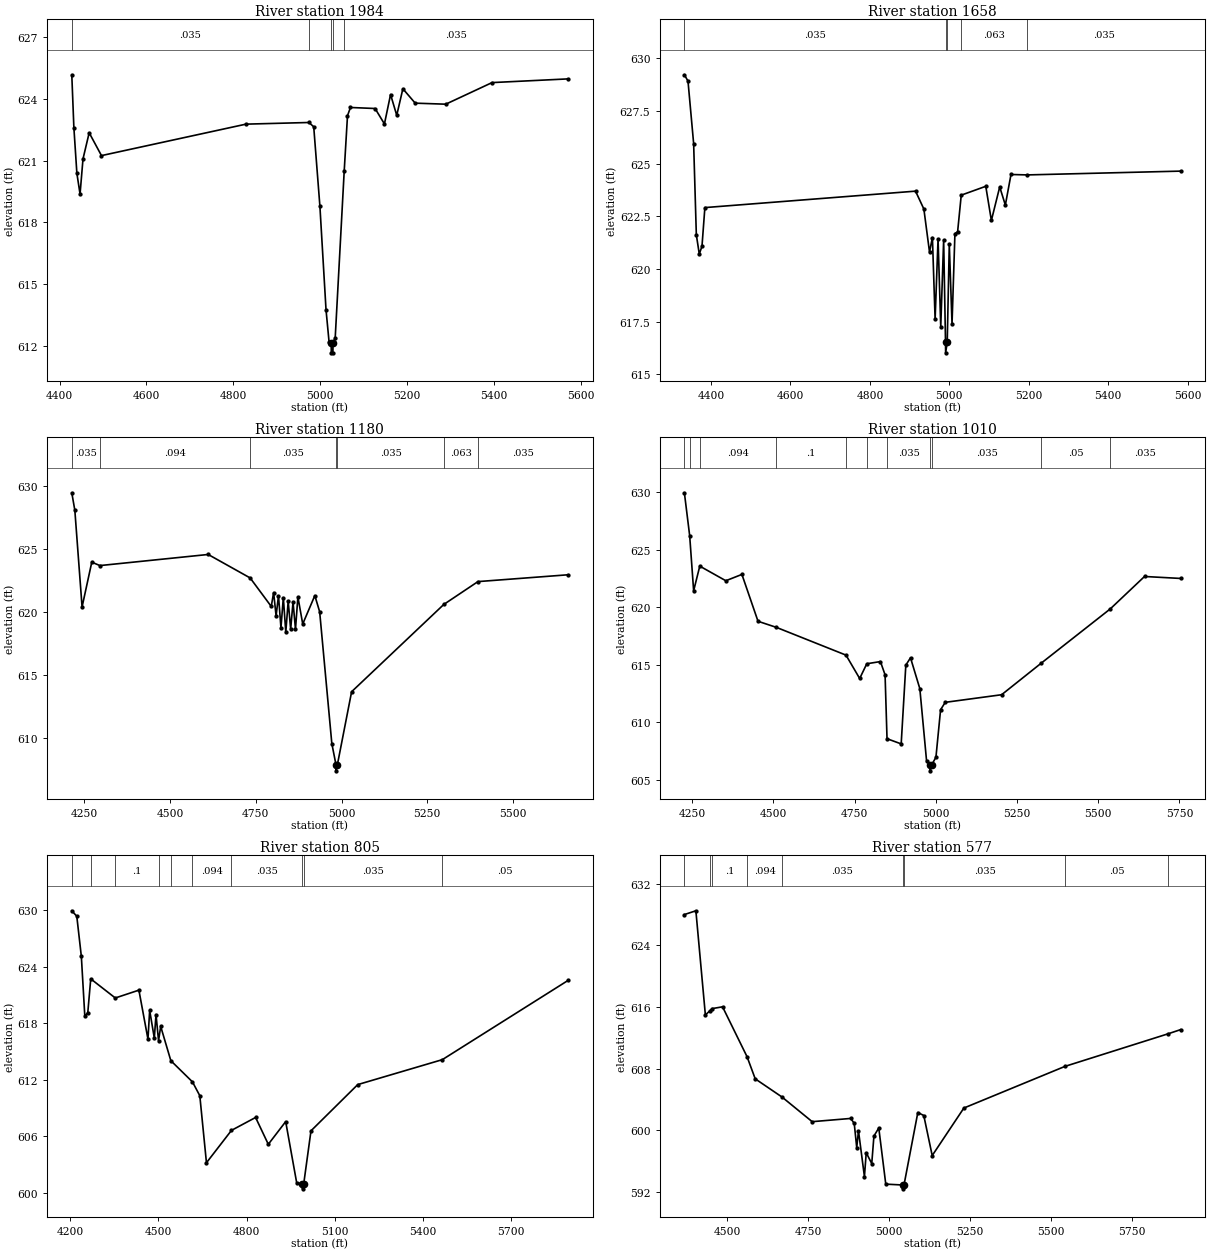
Type RM Length L Ch R = 1,1984,326,326,326
BEGIN DESCRIPTION:
XS6202
END DESCRIPTION:
XS GIS Cut Line= 3
      2252901.32     13803544.64      2252073.98     13804322.83
      2252072.24     13804328.55
#Sta/Elev= 30
  4428.2  625.17  4433.0  622.60  4439.9  620.38  4447.2  619.37  4454.0  621.08
  4468.2  622.35  4496.5  621.24  4829.1  622.77  4974.0  622.85  4984.9  622.64
  4999.1  618.78  5013.2  613.74  5020.1  612.20  5025.1  612.15  5025.3  611.65
  5029.0  611.65  5029.3  612.15  5034.3  612.37  5055.0  620.48  5062.6  623.18
  5069.4  623.58  5126.1  623.53  5147.6  622.78  5161.7  624.21  5175.9  623.20
  5190.0  624.49  5218.4  623.79  5288.7  623.74  5395.2  624.79  5570.0  624.97
#Mann=5,-1,0
  4428.2   0.035       0  4974.0    0.07       0  5025.1    0.05       0
  5029.3    0.07       0  5055.0   0.035       0
Bank Sta=5025.1,5029.3
Exp/Cntr=0.3,0.1

Type RM Length L Ch R = 1,1658,478,478,478
BEGIN DESCRIPTION:
XS6201
END DESCRIPTION:
XS GIS Cut Line= 3
      2252724.90     13803282.10      2252087.96     13803875.99
      2252003.93     13804245.50
#Sta/Elev= 30
  4332.8  629.21  4341.9  628.91  4356.1  625.95  4362.9  621.62  4370.3  620.71
  4377.1  621.07  4384.4  622.91  4915.0  623.69  4936.0  622.84  4950.2  620.80
  4957.5  621.49  4964.3  617.61  4971.7  621.43  4978.5  617.26  4985.8  621.38
  4990.5  616.52  4990.8  616.02  4994.8  616.52  5000.0  621.17  5006.9  617.39
  5014.2  621.67  5021.0  621.77  5030.1  623.50  5091.9  623.92  5106.0  622.30
  5127.0  623.89  5141.2  623.03  5155.4  624.48  5196.3  624.46  5582.6  624.64
#Mann=5,-1,0
  4332.8   0.035       0  4990.5   0.035       0  4994.8   0.035       0
  5030.1   0.063       0  5196.3   0.035       0
Bank Sta=4990.5,4994.8
Exp/Cntr=0.3,0.1

Type RM Length L Ch R = 1,1180,170,170,170
BEGIN DESCRIPTION:
XS6199
END DESCRIPTION:
XS GIS Cut Line= 3
      2252475.26     13803062.65      2251902.91     13803613.48
      2251778.11     13804254.69
#Sta/Elev= 30
  4213.0  629.45  4221.9  628.06  4243.0  620.40  4271.3  623.95  4295.0  623.68
  4610.9  624.56  4733.3  622.70  4794.9  620.44  4801.8  621.54  4809.0  619.69
  4816.0  621.29  4823.2  618.75  4830.1  621.14  4837.3  618.40  4844.3  620.86
  4851.5  618.64  4858.4  620.79  4865.6  618.64  4872.6  621.20  4886.7  619.05
  4922.0  621.30  4936.1  620.02  4971.6  609.57  4983.6  607.91  4983.9  607.41
  4987.9  607.91  5029.3  613.68  5298.3  620.60  5397.9  622.41  5660.6  622.95
#Mann=7,-1,0
  4213.0   0.035       0  4295.0   0.094       0  4733.3   0.035       0
  4983.6   0.035       0  4987.9   0.035       0  5298.3   0.063       0
  5397.9   0.035       0
Bank Sta=4983.6,4987.9
Exp/Cntr=0.3,0.1

Type RM Length L Ch R = 1,1010,205,205,205
BEGIN DESCRIPTION:
E20839
END DESCRIPTION:
XS GIS Cut Line= 3
      2252387.68     13802998.33      2251755.19     13803515.07
      2251751.05     13804226.12
#Sta/Elev= 30
  4225.8  629.94  4242.1  626.21  4254.3  621.43  4273.2  623.57  4353.4  622.30
  4402.9  622.85  4452.5  618.78  4509.1  618.25  4723.4  615.84  4765.5  613.81
  4787.4  615.09  4829.4  615.28  4843.7  614.13  4849.7  608.58  4893.3  608.13
  4907.6  614.97  4922.0  615.61  4950.7  612.93  4971.5  606.64  4982.5  606.29
  4982.8  605.79  4986.8  606.29  5000.3  606.97  5014.6  611.10  5029.0  611.74
  5202.5  612.40  5325.3  615.16  5536.9  619.85  5642.5  622.67  5753.6  622.50
#Mann=11,-1,0
  4225.8   0.094       0  4242.1   0.035       0  4273.2   0.094       0
  4509.1     0.1       0  4723.4   0.035       0  4787.4   0.094       0
  4849.7   0.035       0  4982.5   0.035       0  4986.8   0.035       0
  5325.3    0.05       0  5536.9   0.035       0
Bank Sta=4982.5,4986.8
Exp/Cntr=0.3,0.1

Type RM Length L Ch R = 1,805,228,228,228
BEGIN DESCRIPTION:
XS6198
END DESCRIPTION:
XS GIS Cut Line= 3
      2252333.26     13802950.74      2251623.18     13803355.27
      2251717.85     13804220.18
#Sta/Elev= 30
  4205.9  629.93  4222.9  629.35  4238.4  625.08  4250.2  618.74  4260.3  619.11
  4270.3  622.70  4353.8  620.67  4434.1  621.50  4464.9  616.30  4470.7  619.35
  4486.5  616.41  4492.3  618.91  4500.9  616.13  4508.2  617.65  4542.7  614.01
  4616.2  611.76  4641.2  610.29  4663.8  603.17  4748.9  606.61  4830.9  607.98
  4874.1  605.13  4933.2  607.54  4970.7  601.03  4990.1  600.90  4990.4  600.40
  4994.4  600.90  5019.2  606.56  5178.2  611.47  5465.9  614.12  5893.2  622.53
#Mann=10,-1,0
  4205.9   0.035       0  4270.3   0.094       0  4353.8     0.1       0
  4500.9   0.094       0  4542.7     0.1       0  4616.2   0.094       0
  4748.9   0.035       0  4990.1   0.035       0  4994.4   0.035       0
  5465.9    0.05       0
Bank Sta=4990.1,4994.4
Exp/Cntr=0.3,0.1

Type RM Length L Ch R = 1,577,244,244,244
BEGIN DESCRIPTION:
E20838
END DESCRIPTION:
XS GIS Cut Line= 3
      2252259.48     13802895.02      2251552.63     13803188.51
      2251424.49     13803944.97
#Sta/Elev= 30
  4368.3  628.00  4403.8  628.49  4433.1  614.97  4446.5  615.48  4453.9  615.79
  4486.2  616.02  4561.9  609.54  4587.1  606.67  4669.8  604.31  4763.0  601.11
  4882.1  601.53  4892.9  600.88  4900.6  597.74  4906.0  599.92  4924.4  593.98
  4929.9  597.08  4947.0  595.67  4953.7  599.24  4968.7  600.29  4990.3  593.00
  5042.3  592.89  5042.6  592.39  5046.6  592.89  5089.3  602.30  5107.7  601.91
  5133.7  596.71  5231.5  602.88  5543.9  608.29  5862.4  612.52  5900.9  613.06
#Mann=9,-1,0
  4368.3   0.063       0  4446.5   0.094       0  4453.9     0.1       0
  4561.9   0.094       0  4669.8   0.035       0  5042.3   0.035       0
  5046.6   0.035       0  5543.9    0.05       0  5862.4     0.1       0
Bank Sta=5042.3,5046.6
Exp/Cntr=0.3,0.1

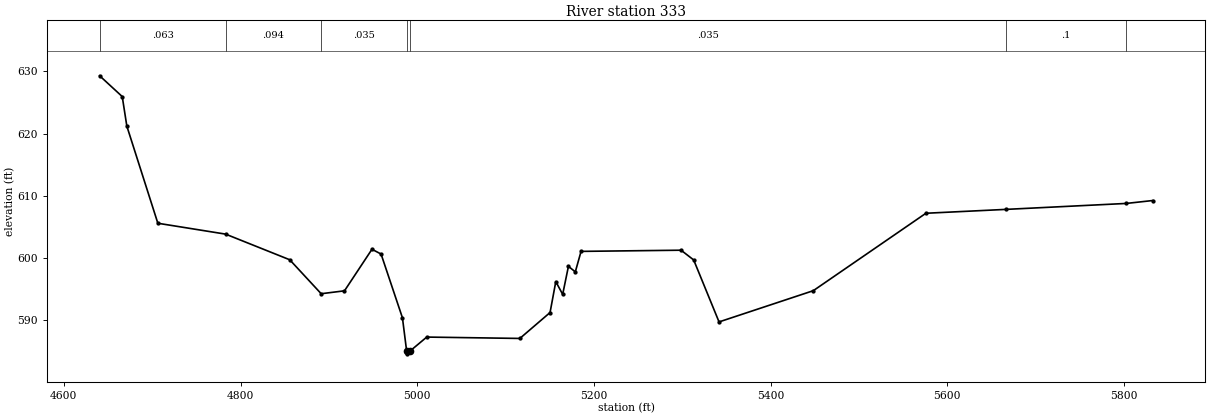
Type RM Length L Ch R = 1,333,0,0,0
BEGIN DESCRIPTION:
E20837
END DESCRIPTION:
XS GIS Cut Line= 3
      2252123.07     13802833.01      2251668.38     13802952.88
      2251114.42     13803415.89
#Sta/Elev= 30
  4640.5  629.30  4666.1  625.95  4671.3  621.19  4706.4  605.55  4783.1  603.80
  4855.7  599.67  4891.3  594.20  4917.7  594.67  4948.8  601.36  4959.1  600.59
  4983.3  590.32  4988.0  585.02  4988.3  584.52  4992.3  585.02  5010.8  587.22
  5116.2  587.00  5150.4  591.17  5156.9  596.15  5164.7  594.10  5171.2  598.61
  5179.0  597.72  5185.5  601.02  5298.7  601.21  5313.0  599.64  5341.7  589.66
  5448.4  594.69  5575.9  607.16  5666.1  607.78  5802.6  608.74  5832.7  609.21
#Mann=7,-1,0
  4640.5   0.063       0  4783.1   0.094       0  4891.3   0.035       0
  4988.0   0.035       0  4992.3   0.035       0  5666.1     0.1       0
  5802.6   0.035       0
Bank Sta=4988,4992.3
Exp/Cntr=0.3,0.1

Chan Stop Cuts=-1