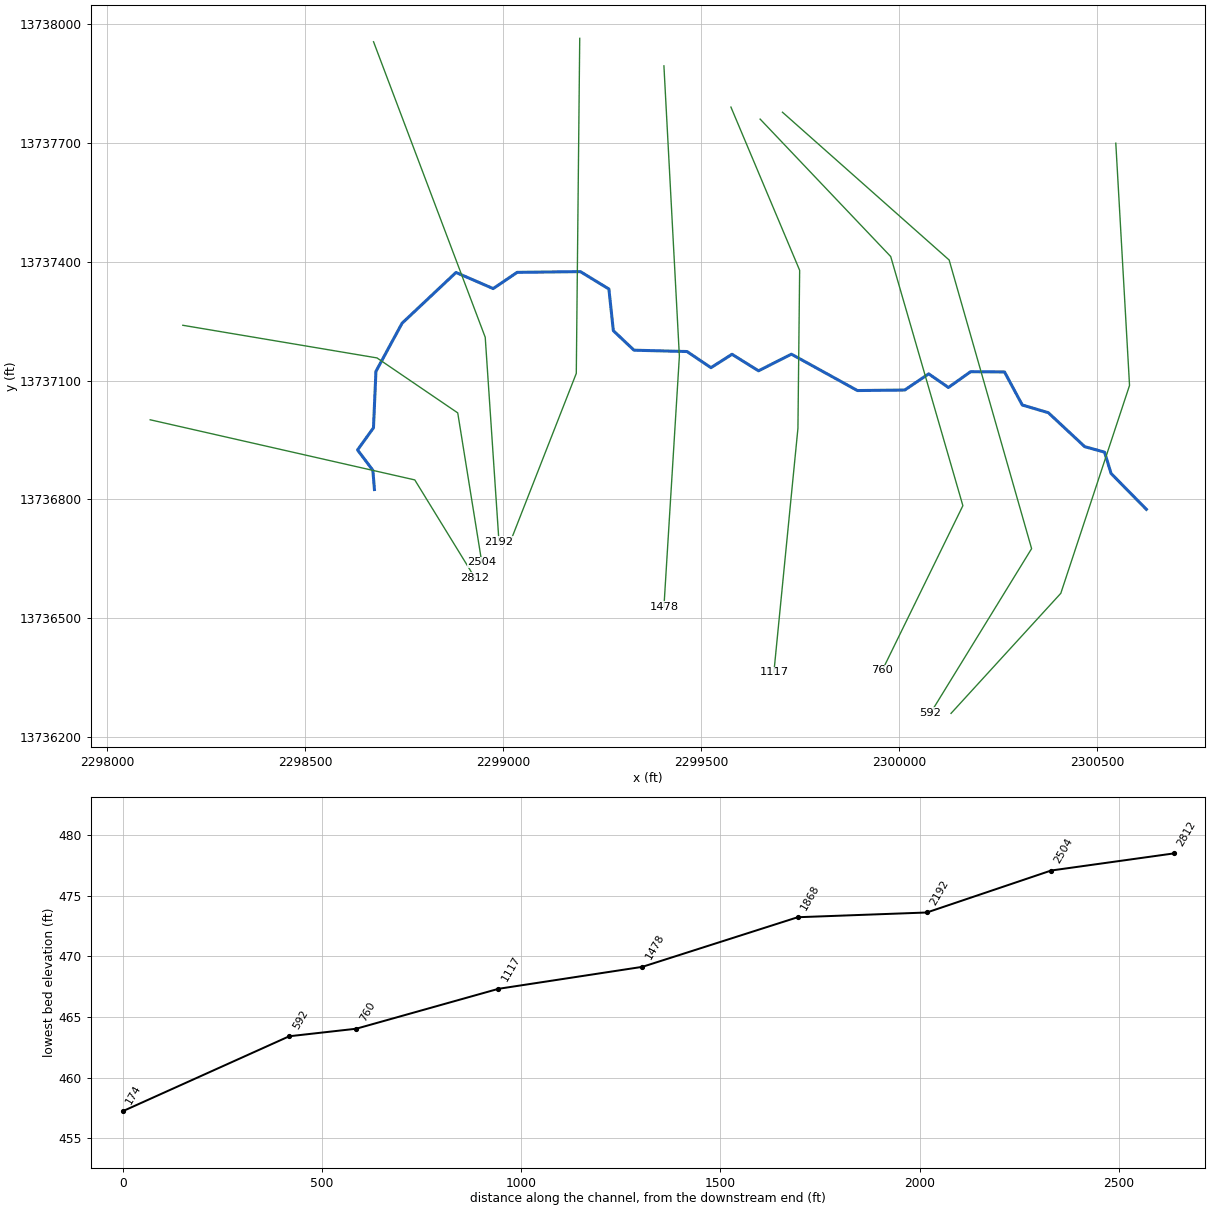
--- Stream0162.prj (project) ---

Proj Title=Stream0162 Base Level Engineering
Current Plan=p01
Default Exp/Contr=0.3,0.1
English Units
Geom File=g01
Flow File=f01
Plan File=p01
BEGIN DESCRIPTION:
Stream0162
END DESCRIPTION:

--- Stream0162.p01 (plan) ---

Plan Title=Multiple Run
Short Identifier=Multiple
Geom File=g01
Flow File=f01
Subcritical Flow
K Sum by GR= 0
Std Step Tol= 0.01
Critical Tol= 0.01
Num of Std Step Trials= 20
Max Error Tol= 0.3
Flow Tol Ratio= 0.001
Split Flow NTrial= 30
Split Flow Tol= 0.02
Split Flow Ratio= 0.02
Log Output Level= 0
Friction Slope Method= 1
Unsteady Friction Slope Method= 2
Unsteady Bridges Friction Slope Method= 1
Parabolic Critical Depth
Global Vel Dist=  1 , 1 , 1
Global Log Level= 0
CheckData=True
Encroach Param= -1, 0, 0, 0
BEGIN DESCRIPTION:
Multiple Run
END DESCRIPTION:

--- Stream0162.f01 (steady flow) ---

Flow Title=Multiple
Number of Profiles=7
Profile Names=10-year,25-year,50-year,1pct_min,100-year,1pct_plu,500-year
River Rch & RM= Stream0162,Reach-1,2812
     672    1091    1472     962    1919    3829    3232
Boundary for River Rch & Prof#=Stream0162,Reach-1,1
Up Type=0
Dn Type=3
Dn Slope=0.005
Boundary for River Rch & Prof#=Stream0162,Reach-1,2
Up Type=0
Dn Type=3
Dn Slope=0.005
Boundary for River Rch & Prof#=Stream0162,Reach-1,3
Up Type=0
Dn Type=3
Dn Slope=0.005
Boundary for River Rch & Prof#=Stream0162,Reach-1,4
Up Type=0
Dn Type=3
Dn Slope=0.005
Boundary for River Rch & Prof#=Stream0162,Reach-1,5
Up Type=0
Dn Type=3
Dn Slope=0.005
Boundary for River Rch & Prof#=Stream0162,Reach-1,6
Up Type=0
Dn Type=3
Dn Slope=0.005
Boundary for River Rch & Prof#=Stream0162,Reach-1,7
Up Type=0
Dn Type=3
Dn Slope=0.005

--- Stream0162.g01 (geometry) ---

Geom Title=Existing Conditions

River Reach=Stream0162,Reach-1
Reach XY= 30
      2298675.00     13736825.00      2298671.00     13736873.64
      2298632.31     13736924.96      2298672.54     13736980.86
      2298678.76     13737123.44      2298744.78     13737245.09
      2298881.05     13737373.34      2298974.99     13737332.59
      2299035.44     13737373.62      2299195.25     13737375.47
      2299267.27     13737331.50      2299278.51     13737226.25
      2299330.65     13737176.98      2299464.56     13737173.61
      2299525.10     13737132.79      2299578.23     13737166.68
      2299645.16     13737124.90      2299728.31     13737166.93
      2299895.03     13737075.04      2300014.56     13737076.36
      2300075.10     13737117.21      2300124.91     13737082.80
      2300180.98     13737122.68      2300266.65     13737122.00
      2300311.47     13737038.56      2300377.26     13737019.12
      2300469.26     13736933.30      2300519.39     13736919.39
      2300535.83     13736865.58      2300625.00     13736775.00

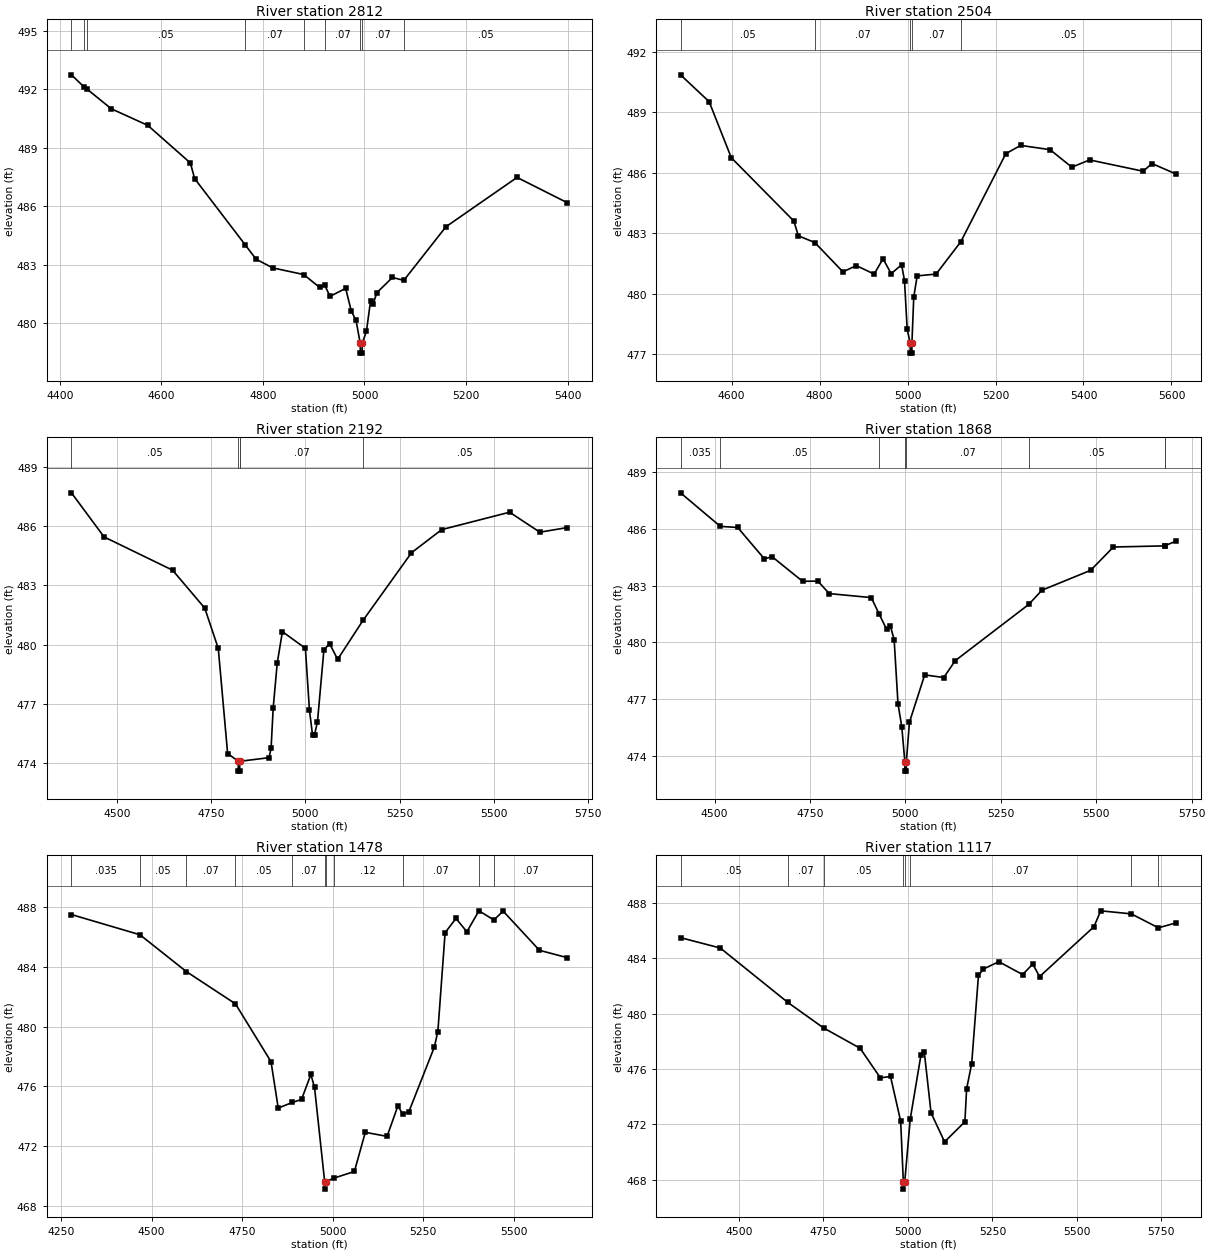
Type RM Length L Ch R = 1,2812,308,308,308
BEGIN DESCRIPTION:
XS6217
END DESCRIPTION:
XS GIS Cut Line= 3
      2298108.55     13737001.21      2298776.91     13736849.31
      2298928.81     13736601.93
#Sta/Elev= 30
  4423.1  492.74  4447.4  492.13  4453.7  492.01  4501.5  491.00  4573.3  490.15
  4657.3  488.22  4665.6  487.42  4765.0  484.03  4786.5  483.29  4819.4  482.84
  4880.4  482.50  4911.7  481.84  4921.6  481.97  4932.2  481.38  4963.0  481.79
  4974.2  480.62  4983.5  480.15  4991.7  478.97  4992.0  478.47  4995.5  478.47
  4995.7  478.97  5004.0  479.60  5012.1  481.16  5017.3  481.01  5024.5  481.57
  5055.2  482.35  5077.5  482.20  5160.5  484.95  5300.5  487.48  5398.8  486.19
#Mann=9,-1,0
  4423.1    0.05       0  4447.4    0.07       0  4453.7    0.05       0
  4765.0    0.07       0  4880.4    0.05       0  4921.6    0.07       0
  4991.7    0.05       0  4995.7    0.07       0  5077.5    0.05       0
Bank Sta=4991.7,4995.7
Exp/Cntr=0.3,0.1

Type RM Length L Ch R = 1,2504,312,312,312
BEGIN DESCRIPTION:
XS6216
END DESCRIPTION:
XS GIS Cut Line= 4
      2298190.92     13737239.94      2298681.42     13737157.47
      2298885.42     13737018.58      2298946.18     13736641.00
#Sta/Elev= 30
  4483.9  490.86  4548.9  489.53  4599.3  486.75  4741.5  483.61  4751.7  482.88
  4789.4  482.54  4853.1  481.09  4883.5  481.40  4924.1  480.98  4944.3  481.74
  4962.8  481.00  4986.5  481.44  4993.1  480.66  4999.2  478.24  5006.0  477.56
  5006.3  477.06  5009.8  477.06  5010.0  477.56  5014.1  479.84  5021.9  480.89
  5064.9  480.98  5121.0  482.58  5223.5  486.95  5257.0  487.36  5323.9  487.15
  5373.5  486.28  5414.0  486.64  5535.6  486.08  5555.8  486.46  5610.5  485.94
#Mann=5,-1,0
  4483.9    0.05       0  4789.4    0.07       0  5006.0    0.05       0
  5010.0    0.07       0  5121.0    0.05       0
Bank Sta=5006,5010
Exp/Cntr=0.3,0.1

Type RM Length L Ch R = 1,2192,324,324,324
BEGIN DESCRIPTION:
XS6215
END DESCRIPTION:
XS GIS Cut Line= 3
      2298672.73     13737956.12      2298954.86     13737209.55
      2298989.59     13736693.02
#Sta/Elev= 30
  4378.9  487.67  4465.6  485.44  4647.4  483.76  4732.9  481.84  4768.8  479.80
  4793.6  474.49  4821.8  474.10  4822.0  473.60  4825.5  473.60  4825.8  474.10
  4827.2  474.10  4903.6  474.28  4909.0  474.75  4914.6  476.80  4925.3  479.06
  4939.1  480.65  5000.1  479.81  5010.8  476.70  5019.0  475.43  5024.3  475.43
  5032.2  476.10  5049.2  479.72  5064.3  480.05  5085.7  479.25  5153.1  481.22
  5281.8  484.64  5362.0  485.81  5542.4  486.69  5622.6  485.68  5694.7  485.91
#Mann=5,-1,0
  4378.9    0.05       0  4821.8    0.05       0  4825.8    0.05       0
  4827.2    0.07       0  5153.1    0.05       0
Bank Sta=4821.8,4825.8
Exp/Cntr=0.3,0.1

Type RM Length L Ch R = 1,1868,390,390,390
BEGIN DESCRIPTION:
XS6214
END DESCRIPTION:
XS GIS Cut Line= 3
      2299193.58     13737964.78      2299184.90     13737118.40
      2299020.00     13736697.47
#Sta/Elev= 30
  4410.7  487.90  4514.9  486.13  4560.5  486.07  4630.5  484.41  4650.5  484.53
  4730.5  483.23  4770.5  483.24  4800.5  482.58  4910.5  482.37  4931.7  481.48
  4950.5  480.70  4960.5  480.88  4970.5  480.14  4980.5  476.77  4990.5  475.54
  4998.5  473.71  4998.8  473.21  5002.3  473.21  5002.5  473.71  5010.5  475.79
  5050.5  478.29  5100.5  478.15  5130.5  479.04  5323.2  482.01  5357.8  482.76
  5485.4  483.81  5545.0  485.04  5679.2  485.10  5679.9  485.11  5709.2  485.35
#Mann=8,-1,0
  4410.7   0.035       0  4514.9    0.05       0  4931.7    0.07       0
  4998.5    0.05       0  5002.5    0.07       0  5323.2    0.05       0
  5679.2    0.07       0  5679.9    0.05       0
Bank Sta=4998.5,5002.5
Exp/Cntr=0.3,0.1

Type RM Length L Ch R = 1,1478,361,361,361
BEGIN DESCRIPTION:
XS6213
END DESCRIPTION:
XS GIS Cut Line= 3
      2299406.25     13737895.30      2299445.31     13737161.81
      2299406.31     13736529.04
#Sta/Elev= 30
  4278.9  487.49  4468.0  486.14  4596.0  483.68  4731.7  481.52  4830.0  477.65
  4850.0  474.54  4888.7  474.92  4914.3  475.12  4940.1  476.79  4950.2  475.93
  4978.2  469.62  4978.4  469.12  4982.2  469.62  5003.0  469.85  5060.3  470.30
  5090.4  472.92  5150.5  472.65  5180.6  474.70  5193.5  474.14  5210.6  474.29
  5280.7  478.60  5290.8  479.66  5310.8  486.28  5340.9  487.23  5370.9  486.34
  5404.3  487.74  5445.6  487.13  5471.1  487.72  5571.3  485.10  5647.4  484.61
#Mann=11,-1,0
  4278.9   0.035       0  4468.0    0.05       0  4596.0    0.07       0
  4731.7    0.05       0  4888.7    0.07       0  4978.2    0.05       0
  4982.2    0.07       0  5003.0    0.12       0  5193.5    0.07       0
  5404.3    0.05       0  5445.6    0.07       0
Bank Sta=4978.2,4982.2
Exp/Cntr=0.3,0.1

Type RM Length L Ch R = 1,1117,357,357,357
BEGIN DESCRIPTION:
XS6212
END DESCRIPTION:
XS GIS Cut Line= 4
      2299575.53     13737791.11      2299749.13     13737378.82
      2299744.79     13736979.51      2299684.03     13736363.18
#Sta/Elev= 30
  4327.4  485.50  4445.0  484.75  4645.0  480.81  4750.5  478.97  4858.6  477.50
  4918.6  475.36  4948.6  475.46  4978.6  472.23  4986.6  467.81  4986.8  467.31
  4990.6  467.81  5006.9  472.37  5038.6  477.00  5048.6  477.20  5068.6  472.82
  5108.6  470.73  5168.6  472.18  5173.8  474.57  5188.7  476.38  5208.8  482.77
  5223.4  483.23  5269.1  483.76  5339.4  482.83  5369.5  483.59  5389.6  482.68
  5550.4  486.29  5570.5  487.44  5661.0  487.22  5741.1  486.21  5793.4  486.57
#Mann=8,-1,0
  4327.4    0.05       0  4645.0    0.07       0  4750.5    0.05       0
  4986.6    0.05       0  4990.6    0.05       0  5006.9    0.07       0
  5661.0   0.035       0  5741.1    0.07       0
Bank Sta=4986.6,4990.6
Exp/Cntr=0.3,0.1

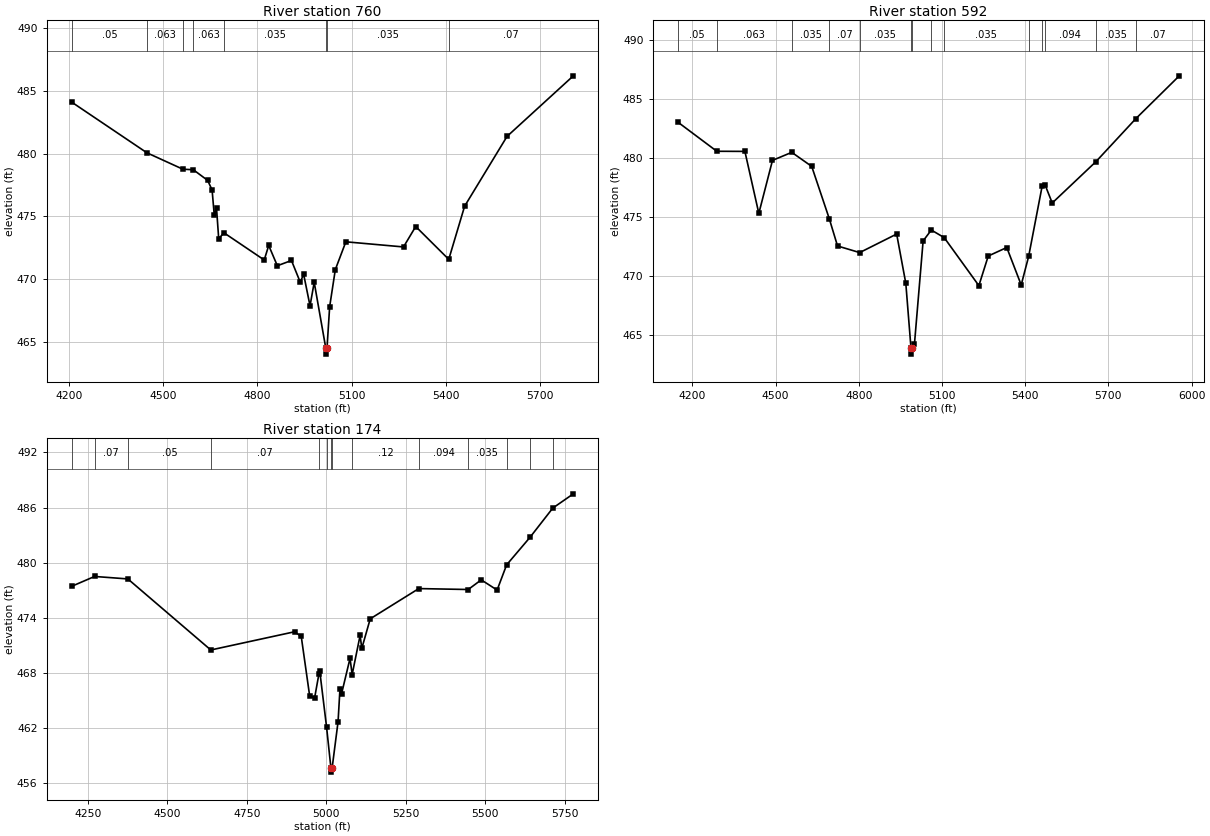
Type RM Length L Ch R = 1,760,168,168,168
BEGIN DESCRIPTION:
XS6211
END DESCRIPTION:
XS GIS Cut Line= 4
      2299649.32     13737760.75      2299979.17     13737413.54
      2300161.46     13736784.20      2299958.06     13736368.74
#Sta/Elev= 30
  4209.1  484.12  4448.4  480.08  4563.0  478.77  4596.0  478.73  4641.7  477.88
  4655.9  477.11  4662.7  475.12  4670.0  475.65  4676.9  473.22  4693.5  473.70
  4821.8  471.53  4836.1  472.69  4863.5  471.07  4908.5  471.49  4936.4  469.76
  4947.3  470.39  4967.6  467.87  4980.9  469.75  5017.6  464.52  5017.9  464.02
  5021.7  464.52  5030.1  467.81  5048.1  470.76  5081.6  472.98  5265.2  472.57
  5304.0  474.20  5409.2  471.58  5459.7  475.82  5594.8  481.39  5805.8  486.22
#Mann=8,-1,0
  4209.1    0.05       0  4448.4   0.063       0  4563.0    0.07       0
  4596.0   0.063       0  4693.5   0.035       0  5017.6   0.035       0
  5021.7   0.035       0  5409.2    0.07       0
Bank Sta=5017.6,5021.7
Exp/Cntr=0.3,0.1

Type RM Length L Ch R = 1,592,418,418,418
BEGIN DESCRIPTION:
XS6210
END DESCRIPTION:
XS GIS Cut Line= 4
      2299705.75     13737778.11      2300126.74     13737404.86
      2300335.07     13736675.69      2300079.80     13736260.34
#Sta/Elev= 30
  4147.0  483.06  4288.1  480.58  4389.3  480.57  4439.5  475.32  4488.8  479.81
  4558.3  480.49  4630.2  479.30  4693.4  474.88  4723.3  472.56  4803.2  472.00
  4936.5  473.57  4969.5  469.39  4988.2  463.90  4988.5  463.40  4992.3  463.90
  5000.7  464.27  5031.9  472.99  5061.4  473.91  5107.8  473.27  5232.9  469.20
  5266.7  471.71  5333.5  472.43  5385.5  469.26  5412.4  471.68  5461.1  477.64
  5471.1  477.76  5497.4  476.20  5654.9  479.70  5799.1  483.35  5955.5  486.97
#Mann=14,-1,0
  4147.0    0.05       0  4288.1   0.063       0  4558.3   0.035       0
  4693.4    0.07       0  4803.2   0.035       0  4988.2   0.035       0
  4992.3   0.035       0  5061.4    0.12       0  5107.8   0.035       0
  5412.4   0.094       0  5461.1    0.12       0  5471.1   0.094       0
  5654.9   0.035       0  5799.1    0.07       0
Bank Sta=4988.2,4992.3
Exp/Cntr=0.3,0.1

Type RM Length L Ch R = 1,174,0,0,0
BEGIN DESCRIPTION:
XS6209
END DESCRIPTION:
XS GIS Cut Line= 4
      2300547.75     13737699.95      2300582.47     13737088.02
      2300408.85     13736562.85      2300131.55     13736259.55
#Sta/Elev= 30
  4199.6  477.44  4271.4  478.51  4376.0  478.24  4636.8  470.51  4900.0  472.49
  4921.1  471.99  4947.6  465.51  4963.2  465.30  4976.5  467.87  4979.3  468.22
  5000.7  462.14  5014.3  457.72  5014.5  457.22  5018.4  457.72  5036.9  462.71
  5042.8  466.24  5048.0  465.76  5074.5  469.60  5081.2  467.84  5106.2  472.10
  5111.5  470.68  5138.0  473.90  5290.7  477.19  5446.1  477.09  5487.0  478.14
  5536.9  477.03  5566.8  479.77  5640.4  482.77  5712.0  485.95  5776.6  487.50
#Mann=14,-1,0
  4199.6    0.05       0  4271.4    0.07       0  4376.0    0.05       0
  4636.8    0.07       0  4976.5    0.12       0  5000.7     0.1       0
  5014.3    0.05       0  5018.4     0.1       0  5081.2    0.12       0
  5290.7   0.094       0  5446.1   0.035       0  5566.8   0.094       0
  5640.4   0.035       0  5712.0    0.07       0
Bank Sta=5014.3,5018.4
Exp/Cntr=0.3,0.1

Chan Stop Cuts=-1