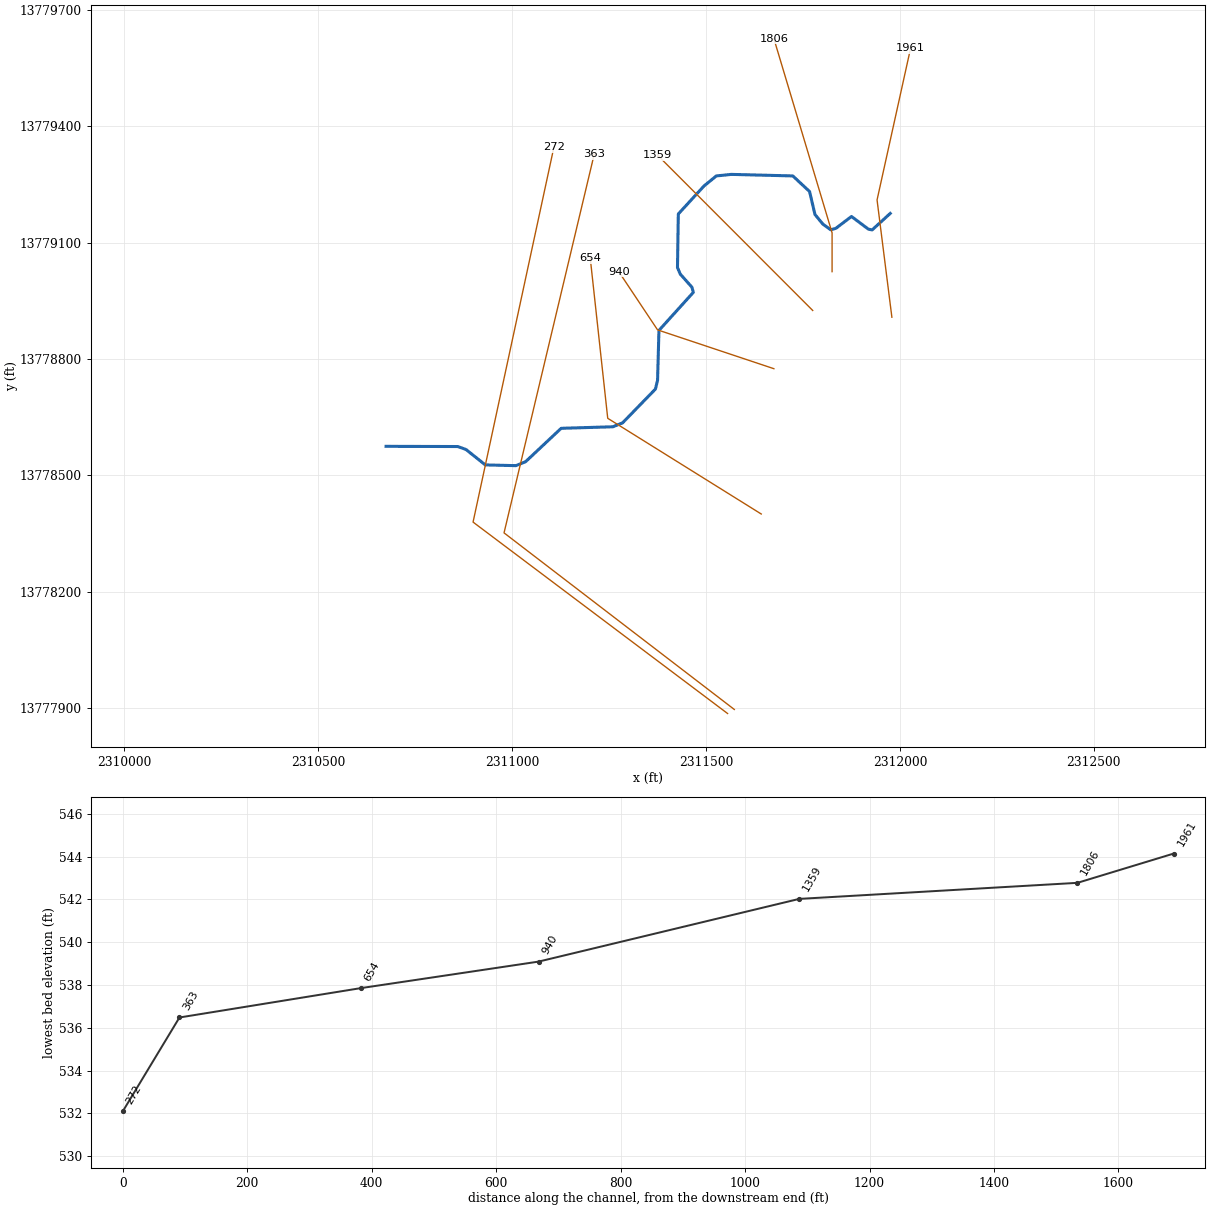
--- Stream0215.prj (project) ---

Proj Title=Stream0215 Base Level Engineering
Current Plan=p01
Default Exp/Contr=0.3,0.1
English Units
Geom File=g01
Flow File=f01
Plan File=p01
BEGIN DESCRIPTION:
Stream0215
END DESCRIPTION:

--- Stream0215.p01 (plan) ---

Plan Title=Multiple Run
Short Identifier=Multiple
Geom File=g01
Flow File=f01
Subcritical Flow
K Sum by GR= 0
Std Step Tol= 0.01
Critical Tol= 0.01
Num of Std Step Trials= 20
Max Error Tol= 0.3
Flow Tol Ratio= 0.001
Split Flow NTrial= 30
Split Flow Tol= 0.02
Split Flow Ratio= 0.02
Log Output Level= 0
Friction Slope Method= 1
Unsteady Friction Slope Method= 2
Unsteady Bridges Friction Slope Method= 1
Parabolic Critical Depth
Global Vel Dist=  1 , 1 , 1
Global Log Level= 0
CheckData=True
Encroach Param= -1, 0, 0, 0
BEGIN DESCRIPTION:
Multiple Run
END DESCRIPTION:

--- Stream0215.f01 (steady flow) ---

Flow Title=Multiple
Number of Profiles=7
Profile Names=10-year,25-year,50-year,1pct_min,100-year,1pct_plu,500-year
River Rch & RM= Stream0215,Reach-1,1961
     279     427     555     350     698    1393    1094
Boundary for River Rch & Prof#=Stream0215,Reach-1,1
Up Type=0
Dn Type=3
Dn Slope=0.005
Boundary for River Rch & Prof#=Stream0215,Reach-1,2
Up Type=0
Dn Type=3
Dn Slope=0.005
Boundary for River Rch & Prof#=Stream0215,Reach-1,3
Up Type=0
Dn Type=3
Dn Slope=0.005
Boundary for River Rch & Prof#=Stream0215,Reach-1,4
Up Type=0
Dn Type=3
Dn Slope=0.005
Boundary for River Rch & Prof#=Stream0215,Reach-1,5
Up Type=0
Dn Type=3
Dn Slope=0.005
Boundary for River Rch & Prof#=Stream0215,Reach-1,6
Up Type=0
Dn Type=3
Dn Slope=0.005
Boundary for River Rch & Prof#=Stream0215,Reach-1,7
Up Type=0
Dn Type=3
Dn Slope=0.005

--- Stream0215.g01 (geometry) ---

Geom Title=Existing Conditions

River Reach=Stream0215,Reach-1
Reach XY= 30
      2311975.00     13779175.00      2311928.33     13779132.50
      2311918.33     13779134.58      2311874.99     13779167.10
      2311834.87     13779136.59      2311821.42     13779132.87
      2311801.30     13779147.36      2311780.87     13779172.19
      2311766.98     13779231.34      2311723.75     13779271.55
      2311564.79     13779275.51      2311526.45     13779271.47
      2311494.71     13779245.53      2311428.52     13779173.54
      2311426.38     13779035.44      2311433.47     13779018.81
      2311463.66     13778984.85      2311467.19     13778971.59
      2311378.57     13778873.53      2311375.02     13778744.99
      2311369.54     13778722.53      2311284.82     13778635.47
      2311259.84     13778625.39      2311126.47     13778621.44
      2311034.78     13778535.46      2311009.78     13778525.25
      2310930.98     13778527.16      2310881.06     13778566.86
      2310859.79     13778574.49      2310675.00     13778575.00

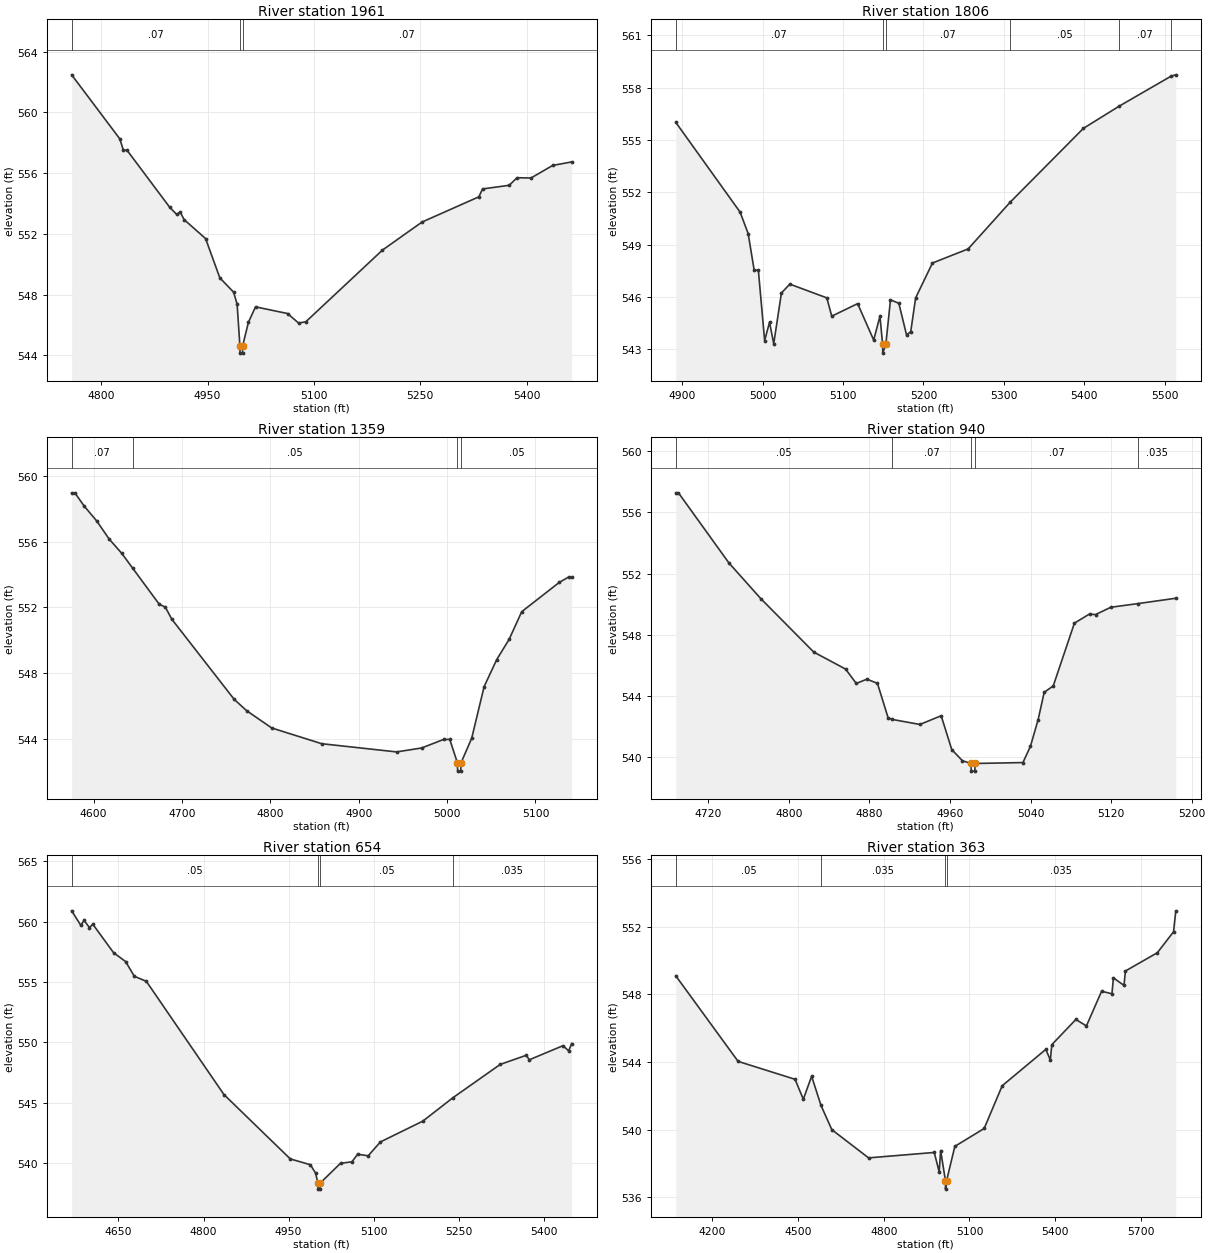
Type RM Length L Ch R = 1,1961,155,155,155
BEGIN DESCRIPTION:
XS6228
END DESCRIPTION:
XS GIS Cut Line= 3
      2311979.17     13778907.60      2311940.97     13779209.72
      2312027.55     13779601.04
#Sta/Elev= 30
  4758.3  562.48  4826.2  558.26  4831.3  557.51  4836.4  557.51  4896.8  553.74
  4906.5  553.28  4911.5  553.43  4916.9  552.94  4947.2  551.69  4967.3  549.10
  4986.7  548.16  4991.7  547.37  4995.6  544.64  4995.8  544.14  4999.3  544.14
  4999.6  544.64  5007.7  546.18  5017.7  547.19  5062.8  546.75  5078.5  546.12
  5088.7  546.21  5196.7  550.93  5252.6  552.78  5332.7  554.44  5337.9  554.96
  5375.5  555.20  5386.6  555.70  5406.2  555.68  5436.9  556.51  5463.6  556.74
#Mann=3,-1,0
  4758.3    0.07       0  4995.6    0.05       0  4999.6    0.07       0
Bank Sta=4995.6,4999.6
Exp/Cntr=0.3,0.1

Type RM Length L Ch R = 1,1806,447,447,447
BEGIN DESCRIPTION:
Stream0215 4.0
END DESCRIPTION:
XS GIS Cut Line= 3
      2311825.00     13779024.95      2311825.00     13779125.00
      2311674.99     13779625.03
#Sta/Elev= 30
  4891.9  556.01  4971.9  550.86  4981.9  549.63  4989.4  547.53  4994.6  547.53
  5002.4  543.49  5008.5  544.54  5013.7  543.31  5023.3  546.22  5033.7  546.73
  5079.8  545.94  5085.9  544.89  5118.1  545.61  5138.1  543.52  5145.9  544.89
  5149.2  543.27  5149.4  542.77  5153.2  543.27  5159.0  545.83  5169.4  545.63
  5179.0  543.81  5184.2  544.01  5190.3  545.94  5211.2  547.94  5255.6  548.75
  5308.1  551.44  5399.1  555.67  5443.5  556.94  5508.0  558.66  5514.0  558.74
#Mann=6,-1,0
  4891.9    0.07       0  5149.2    0.05       0  5153.2    0.07       0
  5308.1    0.05       0  5443.5    0.07       0  5508.0    0.05       0
Bank Sta=5149.2,5153.2
Exp/Cntr=0.3,0.1

Type RM Length L Ch R = 1,1359,419,419,419
BEGIN DESCRIPTION:
Stream0215 3.0
END DESCRIPTION:
XS GIS Cut Line= 3
      2311775.03     13778924.97      2311475.00     13779225.00
      2311375.02     13779324.98
#Sta/Elev= 30
  4575.2  558.97  4578.8  558.97  4589.4  558.16  4603.5  557.26  4617.7  556.15
  4631.8  555.29  4644.1  554.39  4674.2  552.19  4681.3  552.00  4688.4  551.28
  4759.1  546.39  4773.2  545.70  4801.5  544.65  4858.1  543.69  4942.9  543.19
  4971.2  543.43  4996.0  543.95  5003.0  543.95  5011.7  542.52  5011.9  542.02
  5015.4  542.02  5015.7  542.52  5027.8  544.02  5041.9  547.17  5056.1  548.81
  5070.2  550.05  5084.4  551.73  5126.8  553.51  5137.4  553.84  5140.9  553.84
#Mann=4,-1,0
  4575.2    0.07       0  4644.1    0.05       0  5011.7    0.05       0
  5015.7    0.05       0
Bank Sta=5011.7,5015.7
Exp/Cntr=0.3,0.1

Type RM Length L Ch R = 1,940,286,286,286
BEGIN DESCRIPTION:
Stream0215 2.0
END DESCRIPTION:
XS GIS Cut Line= 3
      2311674.96     13778775.01      2311375.00     13778875.00
      2311274.98     13779025.03
#Sta/Elev= 30
  4687.7  557.28  4690.3  557.28  4740.4  552.70  4772.0  550.37  4824.7  546.87
  4856.3  545.76  4866.9  544.82  4877.4  545.10  4887.9  544.83  4898.5  542.58
  4902.5  542.47  4930.1  542.14  4951.2  542.71  4961.7  540.50  4972.3  539.77
  4980.8  539.59  4981.1  539.09  4984.6  539.09  4984.8  539.59  5032.4  539.65
  5039.9  540.72  5047.5  542.46  5053.5  544.24  5062.5  544.66  5083.5  548.76
  5098.5  549.36  5104.5  549.32  5119.6  549.80  5146.6  550.04  5184.2  550.39
#Mann=5,-1,0
  4687.7    0.05       0  4902.5    0.07       0  4980.8    0.05       0
  4984.8    0.07       0  5146.6   0.035       0
Bank Sta=4980.8,4984.8
Exp/Cntr=0.3,0.1

Type RM Length L Ch R = 1,654,291,291,291
BEGIN DESCRIPTION:
XS6227
END DESCRIPTION:
XS GIS Cut Line= 3
      2311642.33     13778400.71      2311246.53     13778647.22
      2311201.42     13779060.17
#Sta/Elev= 30
  4567.5  560.90  4583.6  559.70  4589.4  560.11  4598.9  559.51  4604.8  559.79
  4641.4  557.43  4662.6  556.70  4678.0  555.48  4699.2  555.06  4836.1  545.68
  4953.1  540.35  4988.5  539.87  4997.8  539.16  5001.7  538.35  5001.9  537.85
  5005.4  537.85  5005.7  538.35  5041.6  539.99  5061.7  540.11  5071.8  540.74
  5090.4  540.61  5112.0  541.76  5186.7  543.48  5240.1  545.43  5323.3  548.18
  5369.4  548.94  5374.4  548.56  5433.9  549.73  5444.0  549.30  5449.2  549.91
#Mann=4,-1,0
  4567.5    0.05       0  5001.7    0.05       0  5005.7    0.05       0
  5240.1   0.035       0
Bank Sta=5001.7,5005.7
Exp/Cntr=0.3,0.1

Type RM Length L Ch R = 1,363,91,91,91
BEGIN DESCRIPTION:
XS6226
END DESCRIPTION:
XS GIS Cut Line= 3
      2311572.90     13777897.23      2310979.17     13778352.08
      2311211.81     13779327.80
#Sta/Elev= 30
  4071.6  549.10  4289.7  544.04  4489.1  542.98  4518.1  541.80  4547.2  543.16
  4579.9  541.44  4617.9  540.00  4746.6  538.33  4976.7  538.65  4993.9  537.50
  4999.0  538.76  5015.9  536.98  5016.1  536.48  5019.9  536.98  5048.7  539.01
  5151.5  540.07  5214.7  542.60  5367.4  544.75  5383.2  544.12  5388.4  545.03
  5472.6  546.52  5509.6  546.14  5562.7  548.19  5599.0  548.04  5604.1  548.98
  5641.1  548.54  5646.2  549.39  5758.0  550.47  5814.7  551.71  5822.6  552.95
#Mann=4,-1,0
  4071.6    0.05       0  4579.9   0.035       0  5015.9   0.035       0
  5019.9   0.035       0
Bank Sta=5015.9,5019.9
Exp/Cntr=0.3,0.1

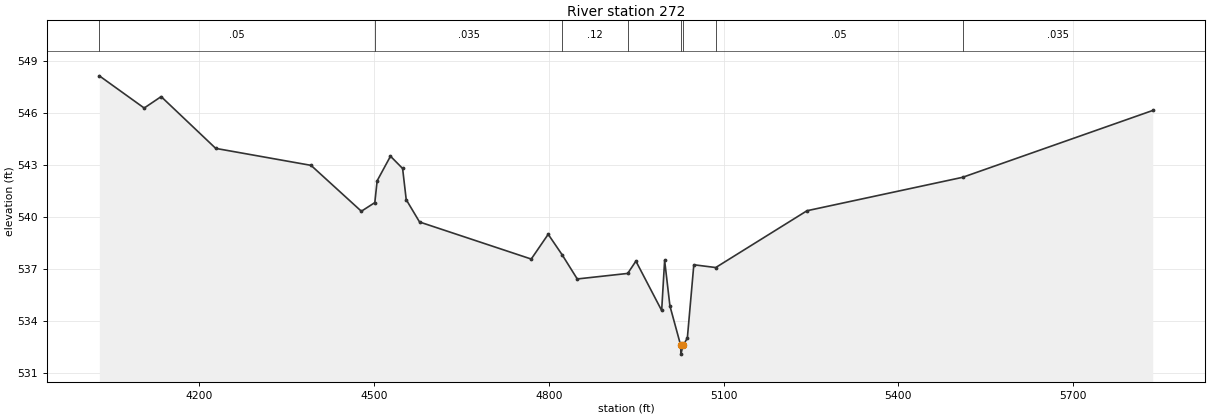
Type RM Length L Ch R = 1,272,0,0,0
BEGIN DESCRIPTION:
Stream0215 1.0
END DESCRIPTION:
XS GIS Cut Line= 3
      2311555.55     13777886.81      2310899.31     13778379.86
      2311107.63     13779345.10
#Sta/Elev= 30
  4028.5  548.17  4105.5  546.31  4134.6  546.97  4228.3  543.98  4391.9  543.00
  4478.3  540.35  4501.4  540.85  4505.4  542.11  4528.3  543.53  4549.1  542.82
  4555.3  541.02  4578.2  539.73  4769.9  537.59  4799.0  539.02  4822.9  537.84
  4848.9  536.44  4935.5  536.76  4949.6  537.47  4993.8  534.62  4998.9  537.51
  5008.0  534.88  5026.5  532.60  5026.8  532.10  5030.5  532.60  5037.9  533.03
  5049.0  537.26  5086.6  537.10  5243.3  540.38  5510.4  542.31  5836.8  546.17
#Mann=8,-1,0
  4028.5    0.05       0  4501.4   0.035       0  4822.9    0.12       0
  4935.5   0.035       0  5026.5   0.035       0  5030.5   0.035       0
  5086.6    0.05       0  5510.4   0.035       0
Bank Sta=5026.5,5030.5
Exp/Cntr=0.3,0.1

Chan Stop Cuts=-1