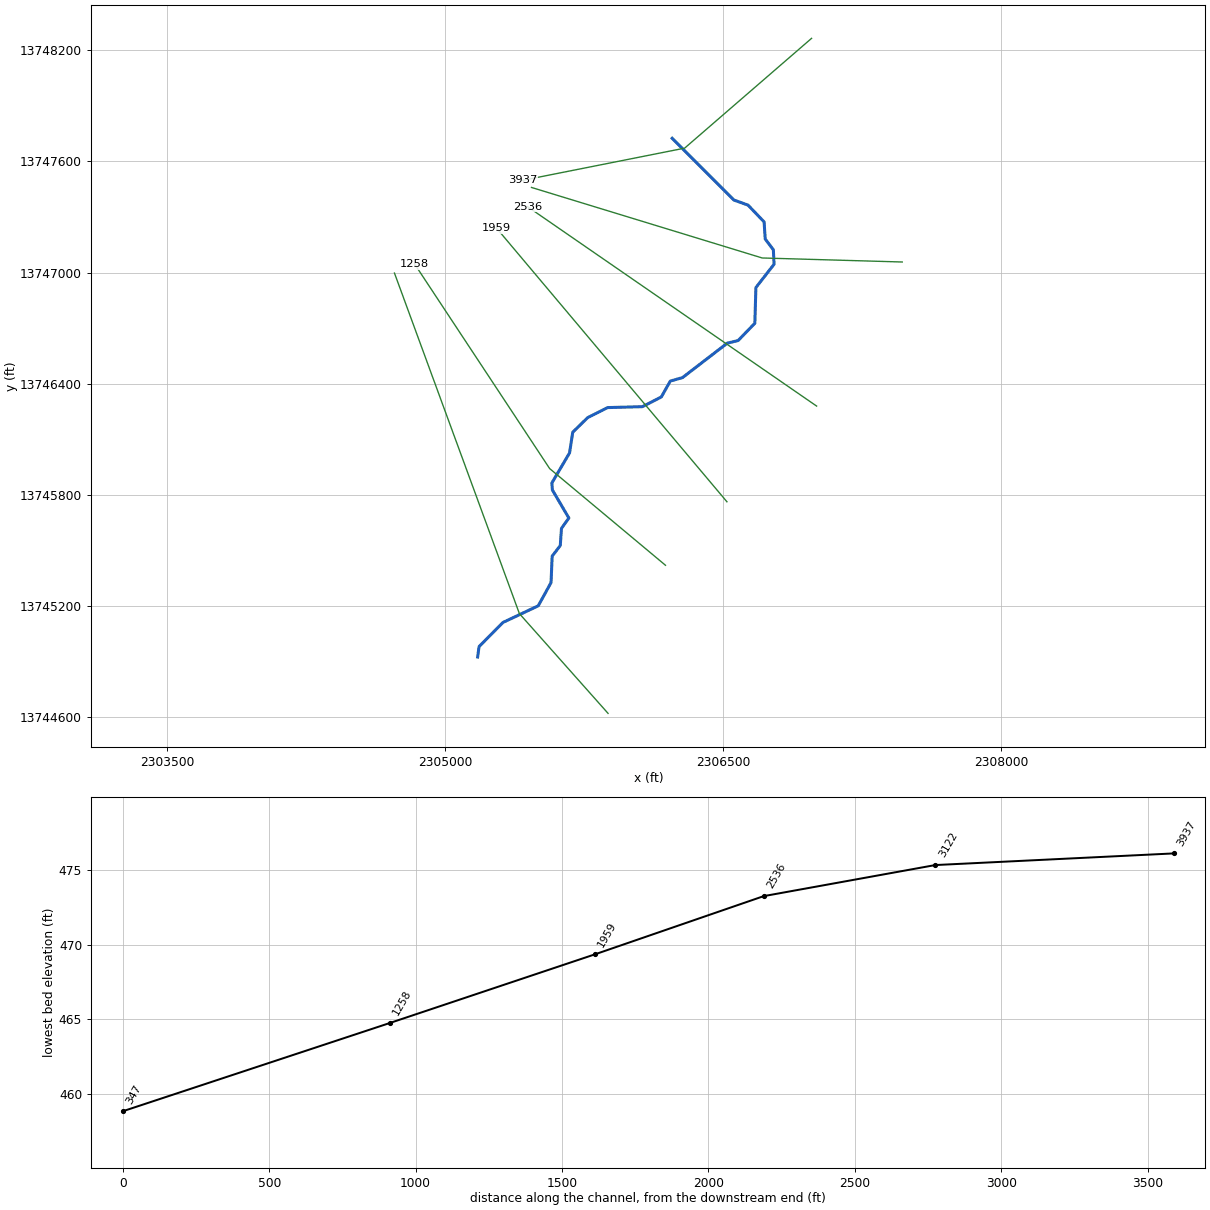
--- Stream0230.prj (project) ---

Proj Title=Stream0230 Base Level Engineering
Current Plan=p01
Default Exp/Contr=0.3,0.1
English Units
Geom File=g01
Flow File=f01
Plan File=p01
BEGIN DESCRIPTION:
Stream0230
END DESCRIPTION:

--- Stream0230.p01 (plan) ---

Plan Title=Multiple Run
Short Identifier=Multiple
Geom File=g01
Flow File=f01
Subcritical Flow
K Sum by GR= 0
Std Step Tol= 0.01
Critical Tol= 0.01
Num of Std Step Trials= 20
Max Error Tol= 0.3
Flow Tol Ratio= 0.001
Split Flow NTrial= 30
Split Flow Tol= 0.02
Split Flow Ratio= 0.02
Log Output Level= 0
Friction Slope Method= 1
Unsteady Friction Slope Method= 2
Unsteady Bridges Friction Slope Method= 1
Parabolic Critical Depth
Global Vel Dist=  1 , 1 , 1
Global Log Level= 0
CheckData=True
Encroach Param= -1, 0, 0, 0
BEGIN DESCRIPTION:
Multiple Run
END DESCRIPTION:

--- Stream0230.f01 (steady flow) ---

Flow Title=Multiple
Number of Profiles=7
Profile Names=10-year,25-year,50-year,1pct_min,100-year,1pct_plu,500-year
River Rch & RM= Stream0230,Reach-1,3937
     625    1004    1343     870    1736    3463    2873
Boundary for River Rch & Prof#=Stream0230,Reach-1,1
Up Type=0
Dn Type=3
Dn Slope=0.005
Boundary for River Rch & Prof#=Stream0230,Reach-1,2
Up Type=0
Dn Type=3
Dn Slope=0.005
Boundary for River Rch & Prof#=Stream0230,Reach-1,3
Up Type=0
Dn Type=3
Dn Slope=0.005
Boundary for River Rch & Prof#=Stream0230,Reach-1,4
Up Type=0
Dn Type=3
Dn Slope=0.005
Boundary for River Rch & Prof#=Stream0230,Reach-1,5
Up Type=0
Dn Type=3
Dn Slope=0.005
Boundary for River Rch & Prof#=Stream0230,Reach-1,6
Up Type=0
Dn Type=3
Dn Slope=0.005
Boundary for River Rch & Prof#=Stream0230,Reach-1,7
Up Type=0
Dn Type=3
Dn Slope=0.005

--- Stream0230.g01 (geometry) ---

Geom Title=Existing Conditions

River Reach=Stream0230,Reach-1
Reach XY= 30
      2306225.00     13747725.00      2306558.33     13747391.65
      2306634.70     13747364.23      2306721.39     13747273.52
      2306727.36     13747180.98      2306771.30     13747123.40
      2306775.21     13747045.05      2306677.07     13746919.14
      2306671.47     13746726.45      2306581.07     13746633.15
      2306522.72     13746619.13      2306281.02     13746433.18
      2306215.03     13746414.30      2306166.51     13746328.53
      2306064.52     13746276.19      2305876.55     13746271.25
      2305768.92     13746216.87      2305688.39     13746138.33
      2305671.17     13746026.59      2305575.74     13745864.31
      2305578.34     13745826.72      2305667.47     13745675.01
      2305627.55     13745619.11      2305621.15     13745526.60
      2305577.27     13745469.06      2305571.24     13745326.56
      2305502.15     13745201.16      2305311.78     13745111.38
      2305182.76     13744981.21      2305175.00     13744925.00

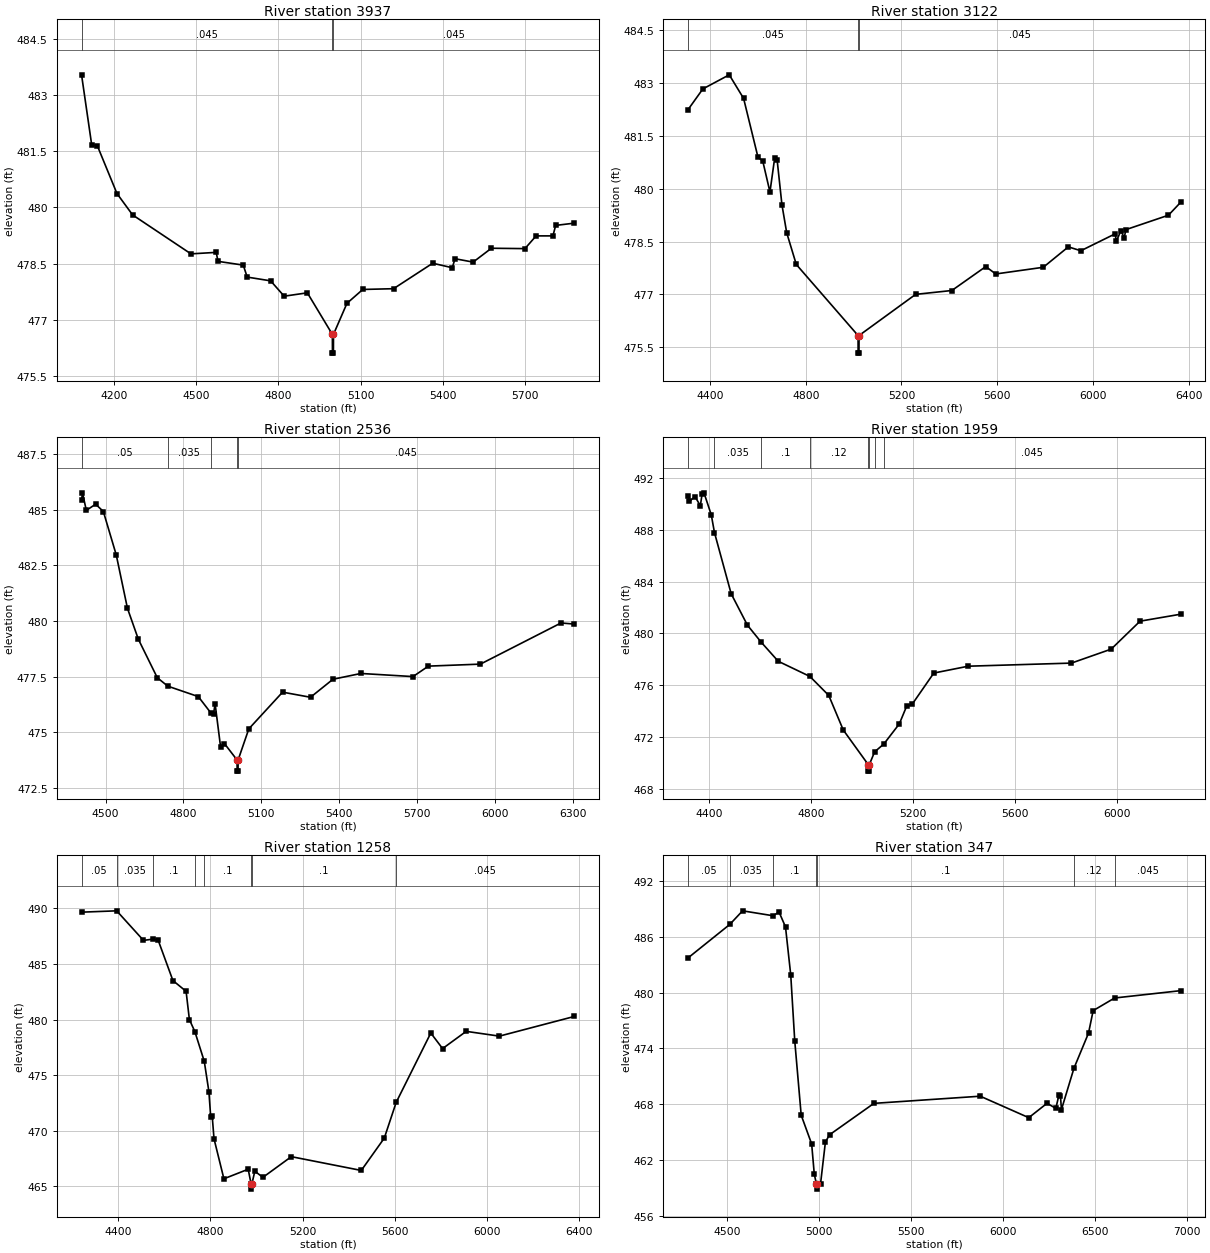
Type RM Length L Ch R = 1,3937,815,815,815
BEGIN DESCRIPTION:
XS6234
END DESCRIPTION:
XS GIS Cut Line= 3
      2306977.65     13748264.53      2306292.38     13747671.72
      2305418.38     13747498.01
#Sta/Elev= 30
  4081.9  483.54  4118.9  481.67  4139.8  481.64  4211.1  480.37  4268.1  479.80
  4480.9  478.76  4573.0  478.80  4579.6  478.56  4671.7  478.46  4686.0  478.14
  4771.5  478.04  4820.9  477.63  4905.4  477.72  4996.7  476.61  4997.0  476.11
  5000.5  476.11  5000.7  476.61  5049.9  477.44  5107.7  477.81  5219.8  477.83
  5362.6  478.51  5433.9  478.39  5444.1  478.63  5510.1  478.54  5576.7  478.91
  5699.0  478.90  5739.8  479.24  5801.0  479.24  5811.2  479.52  5879.1  479.58
#Mann=3,-1,0
  4081.9   0.045       0  4996.7   0.045       0  5000.7   0.045       0
Bank Sta=4996.7,5000.7
Exp/Cntr=0.3,0.1

Type RM Length L Ch R = 1,3122,586,586,586
BEGIN DESCRIPTION:
XS6233
END DESCRIPTION:
XS GIS Cut Line= 3
      2307467.12     13747057.14      2306711.17     13747078.89
      2305465.72     13747459.60
#Sta/Elev= 30
  4308.4  482.25  4370.5  482.84  4480.6  483.24  4540.6  482.57  4600.6  480.90
  4620.6  480.79  4650.7  479.91  4670.7  480.89  4680.7  480.82  4700.7  479.55
  4720.7  478.75  4760.7  477.85  5018.8  475.83  5019.1  475.33  5022.6  475.33
  5022.8  475.83  5259.3  477.00  5410.7  477.11  5552.4  477.79  5593.9  477.58
  5792.6  477.77  5897.2  478.35  5949.5  478.24  6092.7  478.72  6097.9  478.51
  6116.8  478.81  6130.7  478.61  6137.7  478.84  6315.5  479.25  6367.0  479.62
#Mann=3,-1,0
  4308.4   0.045       0  5018.8   0.045       0  5022.8   0.045       0
Bank Sta=5018.8,5022.8
Exp/Cntr=0.3,0.1

Type RM Length L Ch R = 1,2536,577,577,577
BEGIN DESCRIPTION:
XS6232
END DESCRIPTION:
XS GIS Cut Line= 2
      2307004.85     13746279.40      2305443.97     13747356.25
#Sta/Elev= 30
  4407.8  485.42  4411.3  485.76  4426.2  484.97  4462.0  485.25  4491.7  484.92
  4541.3  482.97  4584.4  480.57  4626.3  479.18  4699.2  477.45  4739.6  477.07
  4857.1  476.60  4905.8  475.86  4915.7  475.81  4921.7  476.28  4942.7  474.35
  4957.6  474.49  5006.3  473.75  5006.5  473.25  5010.0  473.25  5010.3  473.75
  5051.5  475.15  5181.4  476.80  5288.9  476.57  5375.4  477.38  5482.9  477.64
  5683.3  477.50  5742.6  477.97  5942.7  478.06  6253.0  479.91  6304.1  479.86
#Mann=5,-1,0
  4407.8    0.05       0  4739.6   0.035       0  4905.8   0.045       0
  5006.3   0.045       0  5010.3   0.045       0
Bank Sta=5006.3,5010.3
Exp/Cntr=0.3,0.1

Type RM Length L Ch R = 1,1959,701,701,701
BEGIN DESCRIPTION:
XS6231
END DESCRIPTION:
XS GIS Cut Line= 2
      2306520.82     13745762.70      2305276.20     13747241.03
#Sta/Elev= 30
  4318.8  490.65  4324.2  490.20  4346.3  490.57  4367.1  489.86  4374.1  490.78
  4381.4  490.86  4410.0  489.16  4422.5  487.79  4488.0  483.06  4551.8  480.63
  4606.0  479.31  4672.7  477.84  4796.7  476.67  4870.8  475.20  4927.6  472.53
  5025.7  469.85  5025.9  469.35  5029.5  469.35  5029.8  469.85  5050.6  470.84
  5086.9  471.45  5147.4  473.00  5176.0  474.36  5197.6  474.51  5282.7  476.93
  5417.9  477.46  5822.4  477.70  5978.4  478.78  6091.6  480.94  6251.3  481.48
#Mann=8,-1,0
  4318.8    0.05       0  4422.5   0.035       0  4606.0     0.1       0
  4796.7    0.12       0  5025.7    0.05       0  5029.8    0.12       0
  5050.6     0.1       0  5086.9   0.045       0
Bank Sta=5025.7,5029.8
Exp/Cntr=0.3,0.1

Type RM Length L Ch R = 1,1258,911,911,911
BEGIN DESCRIPTION:
XS6230
END DESCRIPTION:
XS GIS Cut Line= 3
      2306189.02     13745420.09      2305563.58     13745942.19
      2304834.81     13747046.23
#Sta/Elev= 30
  4240.7  489.66  4393.1  489.78  4509.4  487.12  4548.9  487.23  4573.2  487.13
  4637.0  483.51  4694.2  482.54  4708.5  480.00  4732.2  478.92  4773.1  476.24
  4793.1  473.52  4800.9  471.27  4807.5  471.31  4815.3  469.28  4858.2  465.68
  4963.6  466.54  4975.9  465.25  4976.1  464.75  4980.0  465.25  4992.3  466.36
  5027.5  465.81  5150.7  467.67  5454.2  466.43  5554.0  469.34  5605.5  472.55
  5755.7  478.79  5806.9  477.39  5909.3  478.94  6053.3  478.51  6378.3  480.28
#Mann=8,-1,0
  4240.7    0.05       0  4393.1   0.035       0  4548.9     0.1       0
  4732.2    0.07       0  4773.1     0.1       0  4975.9    0.05       0
  4980.0     0.1       0  5605.5   0.045       0
Bank Sta=4975.9,4980
Exp/Cntr=0.3,0.1

Type RM Length L Ch R = 1,347,0,0,0
BEGIN DESCRIPTION:
XS6229
END DESCRIPTION:
XS GIS Cut Line= 3
      2305879.06     13744620.54      2305400.42     13745159.01
      2304726.00     13746997.35
#Sta/Elev= 30
  4285.8  483.73  4512.5  487.33  4582.4  488.80  4748.1  488.27  4780.6  488.67
  4815.7  487.07  4844.2  481.90  4865.9  474.82  4901.0  466.81  4957.9  463.71
  4972.1  460.47  4984.2  459.35  4984.5  458.85  4988.5  459.35  5006.2  459.43
  5032.6  463.92  5055.2  464.70  5296.4  468.08  5874.3  468.85  6138.1  466.54
  6237.6  468.09  6285.2  467.54  6301.5  468.93  6310.4  468.88  6315.7  467.41
  6383.7  471.86  6462.9  475.64  6488.1  478.06  6604.8  479.42  6964.4  480.21
#Mann=7,-1,0
  4285.8    0.05       0  4512.5   0.035       0  4748.1     0.1       0
  4984.2    0.05       0  4988.5     0.1       0  6383.7    0.12       0
  6604.8   0.045       0
Bank Sta=4984.2,4988.5
Exp/Cntr=0.3,0.1

Chan Stop Cuts=-1