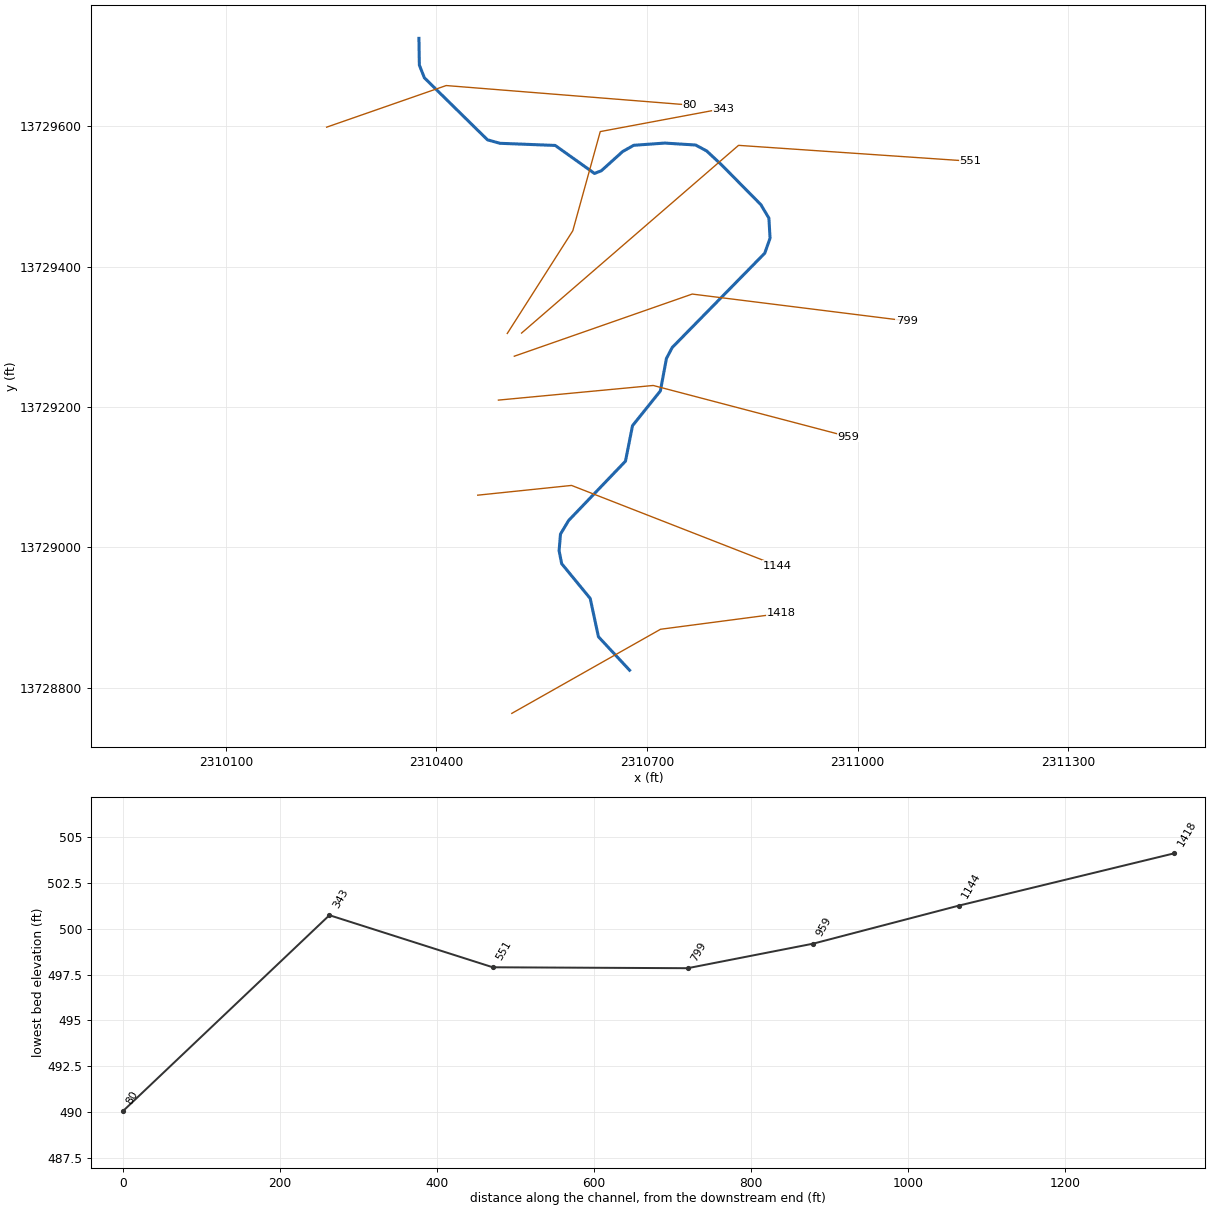
--- Stream0240.prj (project) ---

Proj Title=Stream0240 Base Level Engineering
Current Plan=p01
Default Exp/Contr=0.3,0.1
English Units
Geom File=g01
Flow File=f01
Plan File=p01
Y Axis Title=Elevation
X Axis Title(PF)=Main Channel Distance
X Axis Title(XS)=Station
BEGIN DESCRIPTION:
Stream0240
END DESCRIPTION:
DSS Export Rating Curves= 0
DSS Export Rating Curve Sorted= 0
DSS Export Volume Flow Curves= 0
DXF OffsetX= 0
DXF OffsetY= 0
DXF ScaleX= 1
DXF ScaleY= 10

--- Stream0240.p01 (plan) ---

Plan Title=Multiple Run
Short Identifier=Multiple
Geom File=g01
Flow File=f01
Subcritical Flow
K Sum by GR= 0
Std Step Tol= 0.01
Critical Tol= 0.01
Num of Std Step Trials= 20
Max Error Tol= 0.3
Flow Tol Ratio= 0.001
Split Flow NTrial= 30
Split Flow Tol= 0.02
Split Flow Ratio= 0.02
Log Output Level= 0
Friction Slope Method= 1
Unsteady Friction Slope Method= 2
Unsteady Bridges Friction Slope Method= 1
Parabolic Critical Depth
Global Vel Dist=  1 , 1 , 1
Global Log Level= 0
CheckData=True
Encroach Param= -1, 0, 0, 0
BEGIN DESCRIPTION:
Multiple Run
END DESCRIPTION:

--- Stream0240.f01 (steady flow) ---

Flow Title=Multiple
Number of Profiles=7
Profile Names=10-year,25-year,50-year,1pct_min,100-year,1pct_plu,500-year
River Rch & RM= Stream0240,Reach-1,1418
     213     322     413     258     515    1029     792
Boundary for River Rch & Prof#=Stream0240,Reach-1,1
Up Type=0
Dn Type=3
Dn Slope=0.005
Boundary for River Rch & Prof#=Stream0240,Reach-1,2
Up Type=0
Dn Type=3
Dn Slope=0.005
Boundary for River Rch & Prof#=Stream0240,Reach-1,3
Up Type=0
Dn Type=3
Dn Slope=0.005
Boundary for River Rch & Prof#=Stream0240,Reach-1,4
Up Type=0
Dn Type=3
Dn Slope=0.005
Boundary for River Rch & Prof#=Stream0240,Reach-1,5
Up Type=0
Dn Type=3
Dn Slope=0.005
Boundary for River Rch & Prof#=Stream0240,Reach-1,6
Up Type=0
Dn Type=3
Dn Slope=0.005
Boundary for River Rch & Prof#=Stream0240,Reach-1,7
Up Type=0
Dn Type=3
Dn Slope=0.005

--- Stream0240.g01 (geometry) ---

Geom Title=Existing Conditions

River Reach=Stream0240,Reach-1
Reach XY= 30
      2310675.00     13728825.00      2310630.67     13728872.64
      2310618.93     13728927.23      2310578.30     13728976.73
      2310574.63     13728995.20      2310576.62     13729018.96
      2310588.15     13729038.20      2310669.15     13729122.71
      2310679.19     13729173.27      2310718.90     13729222.81
      2310727.50     13729268.96      2310735.77     13729284.68
      2310867.54     13729418.95      2310875.11     13729440.36
      2310873.43     13729468.96      2310861.90     13729488.24
      2310805.29     13729545.53      2310784.81     13729564.57
      2310769.12     13729573.04      2310725.00     13729575.82
      2310680.90     13729572.64      2310665.22     13729563.83
      2310634.91     13729536.48      2310625.00     13729532.56
      2310569.10     13729572.44      2310490.21     13729575.51
      2310472.56     13729580.50      2310382.75     13729668.76
      2310375.59     13729686.83      2310375.00     13729725.00

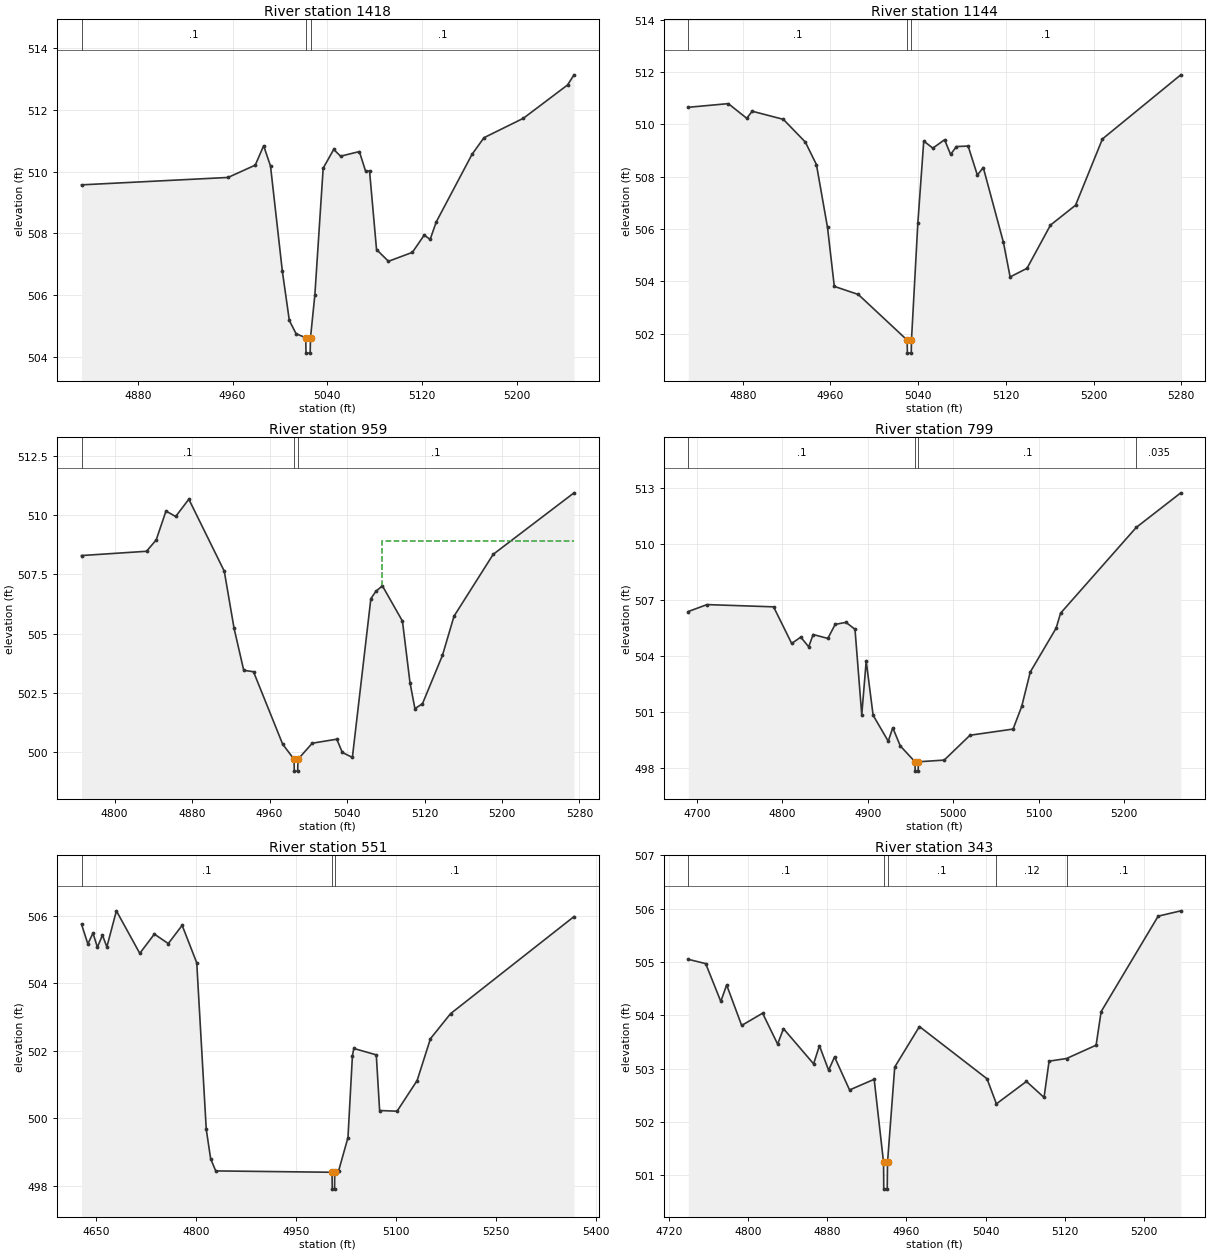
Type RM Length L Ch R = 1,1418,274,274,274
BEGIN DESCRIPTION:
XS6245
END DESCRIPTION:
XS GIS Cut Line= 3
      2310507.26     13728763.52      2310719.10     13728883.33
      2310890.45     13728905.83
#Sta/Elev= 30
  4832.4  509.57  4956.2  509.81  4979.2  510.21  4986.3  510.84  4992.1  510.18
  5002.1  506.77  5008.0  505.17  5013.7  504.74  5021.9  504.61  5022.1  504.11
  5025.6  504.11  5025.9  504.61  5029.6  506.01  5036.6  510.11  5045.5  510.72
  5051.3  510.50  5067.2  510.65  5072.4  510.02  5075.8  510.02  5081.7  507.47
  5091.8  507.09  5112.0  507.38  5122.0  507.94  5127.0  507.80  5132.2  508.37
  5162.4  510.56  5172.5  511.10  5205.8  511.73  5243.1  512.81  5248.6  513.14
#Mann=3,-1,0
  4832.4     0.1       0  5021.9    0.05       0  5025.9     0.1       0
Bank Sta=5021.9,5025.9
Exp/Cntr=0.3,0.1

Type RM Length L Ch R = 1,1144,185,185,185
BEGIN DESCRIPTION:
XS6244
END DESCRIPTION:
XS GIS Cut Line= 3
      2310458.72     13729074.31      2310592.36     13729088.19
      2310885.73     13728973.63
#Sta/Elev= 30
  4830.3  510.65  4866.8  510.79  4883.6  510.23  4888.6  510.50  4917.0  510.19
  4937.1  509.32  4947.2  508.46  4957.3  506.06  4963.5  503.81  4985.4  503.50
  5029.9  501.76  5030.2  501.26  5033.7  501.26  5033.9  501.76  5039.7  506.22
  5045.1  509.36  5053.4  509.09  5064.1  509.41  5069.6  508.85  5074.9  509.15
  5085.6  509.17  5094.0  508.06  5099.4  508.35  5117.8  505.49  5123.9  504.17
  5139.3  504.50  5160.7  506.15  5183.6  506.91  5208.1  509.44  5279.6  511.89
#Mann=3,-1,0
  4830.3     0.1       0  5029.9    0.05       0  5033.9     0.1       0
Bank Sta=5029.9,5033.9
Exp/Cntr=0.3,0.1

Type RM Length L Ch R = 1,959,160,160,160
BEGIN DESCRIPTION:
XS6243
END DESCRIPTION:
XS GIS Cut Line= 3
      2310488.21     13729209.72      2310708.68     13729230.56
      2310986.42     13729157.65
#Sta/Elev= 30
  4765.8  508.30  4832.9  508.48  4842.9  508.96  4853.0  510.18  4863.0  509.95
  4876.6  510.68  4913.2  507.64  4923.3  505.23  4933.3  503.45  4943.4  503.39
  4973.5  500.33  4985.3  499.69  4985.5  499.19  4989.0  499.19  4989.3  499.69
  5004.1  500.37  5029.4  500.54  5035.1  499.98  5045.5  499.77  5064.6  506.48
  5069.8  506.79  5076.5  507.02  5097.2  505.53  5105.0  502.93  5110.1  501.83
  5117.9  502.04  5138.5  504.08  5150.5  505.74  5190.9  508.35  5274.4  510.95
#Mann=3,-1,0
  4765.8     0.1       0  4985.3    0.05       0  4989.3     0.1       0
#XS Ineff=2,0
       0                 5076.60    0.00  508.90
Permanent Ineff=
       F       F
Bank Sta=4985.3,4989.3
Exp/Cntr=0.3,0.1

Type RM Length L Ch R = 1,799,248,248,248
BEGIN DESCRIPTION:
XS6242
END DESCRIPTION:
XS GIS Cut Line= 3
      2310510.80     13729272.23      2310764.24     13729360.76
      2311069.80     13729322.57
#Sta/Elev= 30
  4689.8  506.39  4711.7  506.76  4789.6  506.64  4810.8  504.68  4821.4  505.02
  4830.7  504.50  4835.9  505.16  4853.1  504.95  4861.7  505.70  4874.3  505.81
  4884.9  505.44  4892.8  500.86  4898.0  503.74  4906.1  500.84  4923.8  499.45
  4929.1  500.17  4937.9  499.20  4955.1  498.35  4955.3  497.85  4958.8  497.85
  4959.1  498.35  4989.3  498.44  5019.5  499.77  5069.9  500.10  5080.0  501.31
  5090.0  503.15  5120.3  505.50  5125.5  506.30  5214.1  510.89  5266.2  512.74
#Mann=4,-1,0
  4689.8     0.1       0  4955.1    0.05       0  4959.1     0.1       0
  5214.1   0.035       0
Bank Sta=4955.1,4959.1
Exp/Cntr=0.3,0.1

Type RM Length L Ch R = 1,551,208,208,208
BEGIN DESCRIPTION:
XS6241
END DESCRIPTION:
XS GIS Cut Line= 3
      2310521.17     13729305.20      2310830.21     13729572.57
      2311159.99     13729550.01
#Sta/Elev= 30
  4628.2  505.75  4637.7  505.17  4645.4  505.49  4652.0  505.07  4659.6  505.43
  4666.2  505.08  4680.5  506.15  4715.6  504.89  4737.5  505.46  4758.4  505.18
  4779.2  505.72  4801.1  504.61  4815.4  499.67  4822.0  498.80  4829.6  498.44
  5004.2  498.40  5004.5  497.90  5008.0  497.90  5008.2  498.40  5013.9  498.43
  5028.1  499.43  5034.8  501.86  5036.9  502.07  5070.6  501.88  5075.6  500.23
  5101.8  500.21  5131.9  501.12  5151.9  502.36  5182.0  503.10  5367.4  505.98
#Mann=3,-1,0
  4628.2     0.1       0  5004.2    0.05       0  5008.2     0.1       0
Bank Sta=5004.2,5008.2
Exp/Cntr=0.3,0.1

Type RM Length L Ch R = 1,343,263,263,263
BEGIN DESCRIPTION:
E20841
END DESCRIPTION:
XS GIS Cut Line= 4
      2310500.83     13729304.64      2310594.15     13729450.93
      2310633.24     13729592.18      2310808.52     13729624.96
#Sta/Elev= 30
  4739.2  505.05  4756.8  504.97  4772.1  504.26  4778.0  504.57  4793.2  503.81
  4814.4  504.04  4829.6  503.46  4835.5  503.75  4866.0  503.09  4871.9  503.43
  4881.2  502.97  4887.2  503.22  4902.4  502.60  4927.3  502.80  4936.8  501.24
  4937.0  500.74  4940.5  500.74  4940.8  501.24  4948.1  503.03  4973.1  503.79
  5041.5  502.81  5051.0  502.34  5081.4  502.76  5099.2  502.46  5104.3  503.14
  5122.0  503.19  5151.9  503.44  5157.0  504.07  5214.7  505.86  5237.6  505.96
#Mann=5,-1,0
  4739.2     0.1       0  4936.8    0.05       0  4940.8     0.1       0
  5051.0    0.12       0  5122.0     0.1       0
Bank Sta=4936.8,4940.8
Exp/Cntr=0.3,0.1

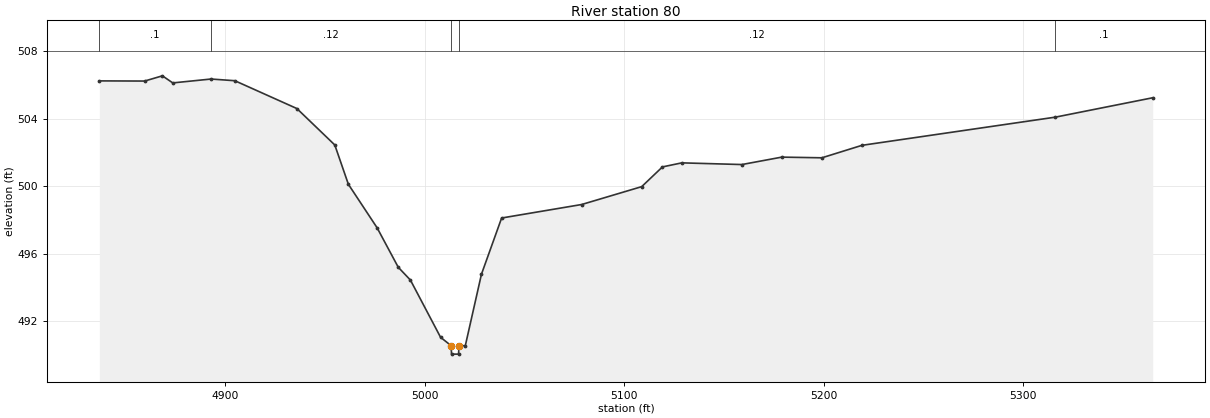
Type RM Length L Ch R = 1,80,0,0,0
BEGIN DESCRIPTION:
E20840
END DESCRIPTION:
XS GIS Cut Line= 3
      2310243.52     13729598.47      2310413.80     13729657.76
      2310760.28     13729630.04
#Sta/Elev= 30
  4837.0  506.25  4859.7  506.24  4868.6  506.55  4873.8  506.13  4893.0  506.36
  4904.9  506.26  4936.0  504.61  4955.0  502.45  4961.8  500.12  4976.2  497.54
  4986.8  495.20  4992.9  494.44  5008.0  491.05  5013.3  490.55  5013.5  490.05
  5017.0  490.05  5017.3  490.55  5020.4  490.55  5028.5  494.79  5038.6  498.12
  5078.7  498.92  5108.8  499.98  5119.2  501.15  5128.9  501.39  5159.0  501.29
  5179.0  501.73  5199.1  501.69  5219.2  502.43  5316.1  504.10  5364.9  505.25
#Mann=5,-1,0
  4837.0     0.1       0  4893.0    0.12       0  5013.3    0.05       0
  5017.3    0.12       0  5316.1     0.1       0
Bank Sta=5013.3,5017.3
Exp/Cntr=0.3,0.1

Chan Stop Cuts=-1