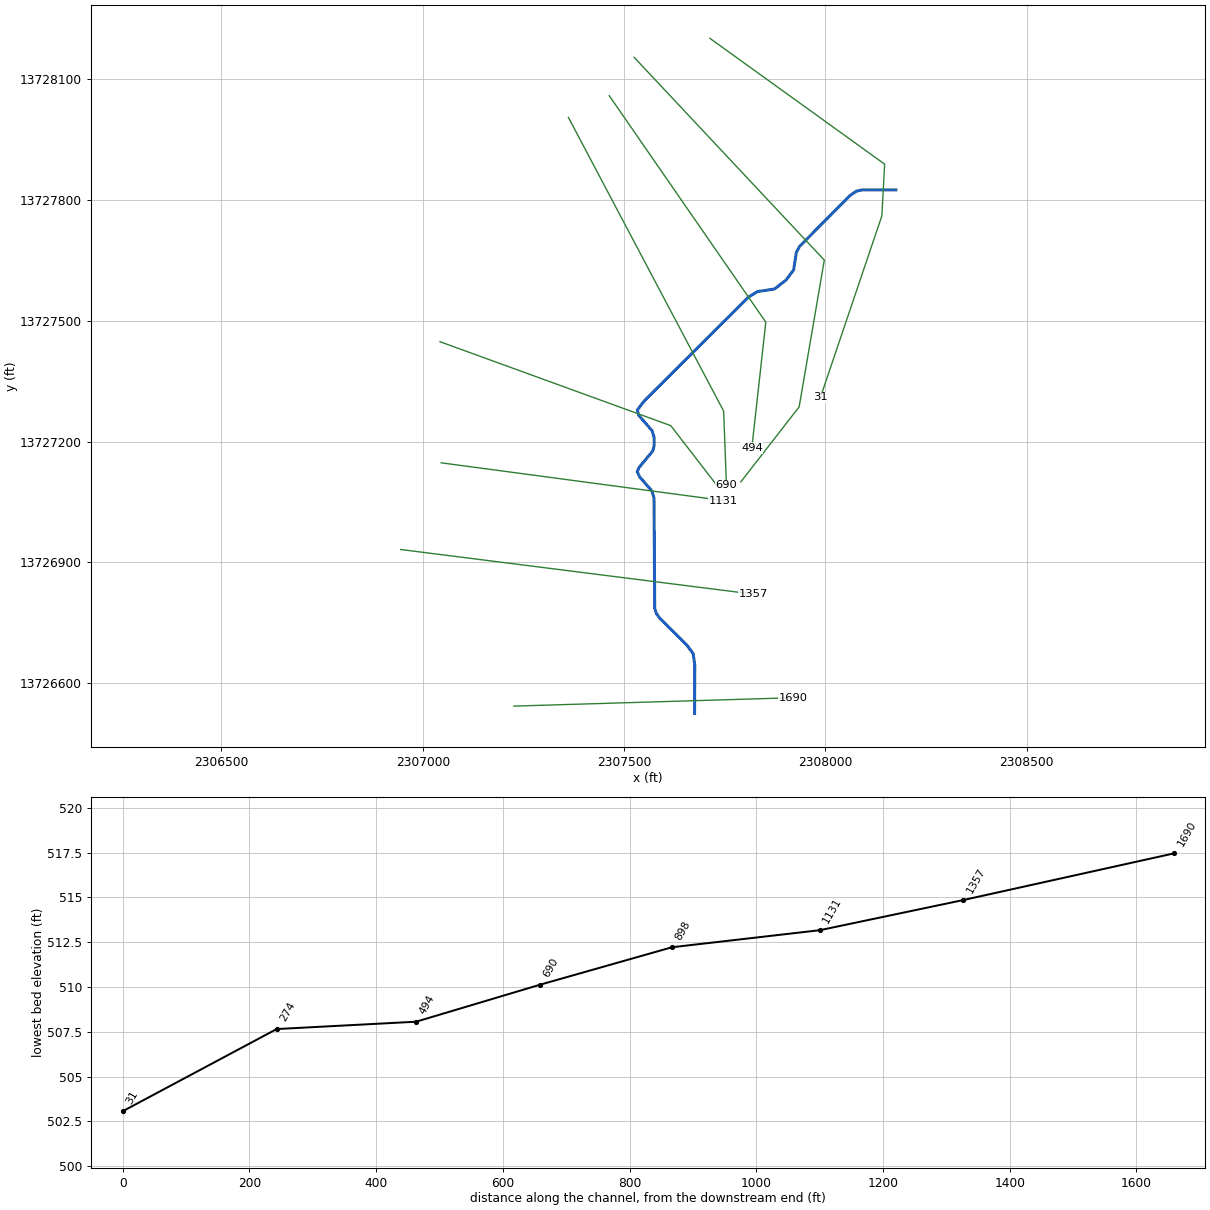
--- Stream0242.prj (project) ---

Proj Title=Stream0242 Base Level Engineering
Current Plan=p01
Default Exp/Contr=0.3,0.1
English Units
Geom File=g01
Flow File=f01
Plan File=p01
BEGIN DESCRIPTION:
Stream0242
END DESCRIPTION:

--- Stream0242.p01 (plan) ---

Plan Title=Multiple Run
Short Identifier=Multiple
Geom File=g01
Flow File=f01
Subcritical Flow
K Sum by GR= 0
Std Step Tol= 0.01
Critical Tol= 0.01
Num of Std Step Trials= 20
Max Error Tol= 0.3
Flow Tol Ratio= 0.001
Split Flow NTrial= 30
Split Flow Tol= 0.02
Split Flow Ratio= 0.02
Log Output Level= 0
Friction Slope Method= 1
Unsteady Friction Slope Method= 2
Unsteady Bridges Friction Slope Method= 1
Parabolic Critical Depth
Global Vel Dist=  1 , 1 , 1
Global Log Level= 0
CheckData=True
Encroach Param= -1, 0, 0, 0
BEGIN DESCRIPTION:
Multiple Run
END DESCRIPTION:

--- Stream0242.f01 (steady flow) ---

Flow Title=Multiple
Number of Profiles=7
Profile Names=10-year,25-year,50-year,1pct_min,100-year,1pct_plu,500-year
River Rch & RM= Stream0242,Reach-1,1690
     150     220     277     170     340     678     504
River Rch & RM= Stream0242,Reach-1,31
    1092    1827    2514    1673    3339    6662    5839
Boundary for River Rch & Prof#=Stream0242,Reach-1,1
Up Type=0
Dn Type=3
Dn Slope=0.005
Boundary for River Rch & Prof#=Stream0242,Reach-1,2
Up Type=0
Dn Type=3
Dn Slope=0.005
Boundary for River Rch & Prof#=Stream0242,Reach-1,3
Up Type=0
Dn Type=3
Dn Slope=0.005
Boundary for River Rch & Prof#=Stream0242,Reach-1,4
Up Type=0
Dn Type=3
Dn Slope=0.005
Boundary for River Rch & Prof#=Stream0242,Reach-1,5
Up Type=0
Dn Type=3
Dn Slope=0.005
Boundary for River Rch & Prof#=Stream0242,Reach-1,6
Up Type=0
Dn Type=3
Dn Slope=0.005
Boundary for River Rch & Prof#=Stream0242,Reach-1,7
Up Type=0
Dn Type=3
Dn Slope=0.005

--- Stream0242.g01 (geometry) ---

Geom Title=Existing Conditions

River Reach=Stream0242,Reach-1
Reach XY= 30
      2307675.00     13726525.00      2307675.51     13726645.21
      2307671.49     13726673.55      2307655.35     13726695.15
      2307588.40     13726761.69      2307580.47     13726772.55
      2307576.06     13726785.44      2307574.34     13727059.84
      2307568.98     13727077.45      2307538.96     13727111.80
      2307532.59     13727125.01      2307536.53     13727134.93
      2307571.36     13727176.65      2307574.71     13727190.36
      2307574.71     13727209.64      2307569.31     13727227.29
      2307536.38     13727265.13      2307532.82     13727278.41
      2307550.72     13727301.69      2307808.34     13727558.34
      2307831.09     13727572.45      2307873.57     13727578.89
      2307902.14     13727601.16      2307921.11     13727626.43
      2307927.55     13727668.91      2307935.79     13727684.66
      2308061.67     13727811.65      2308076.40     13727821.62
      2308090.05     13727824.88      2308175.00     13727825.00

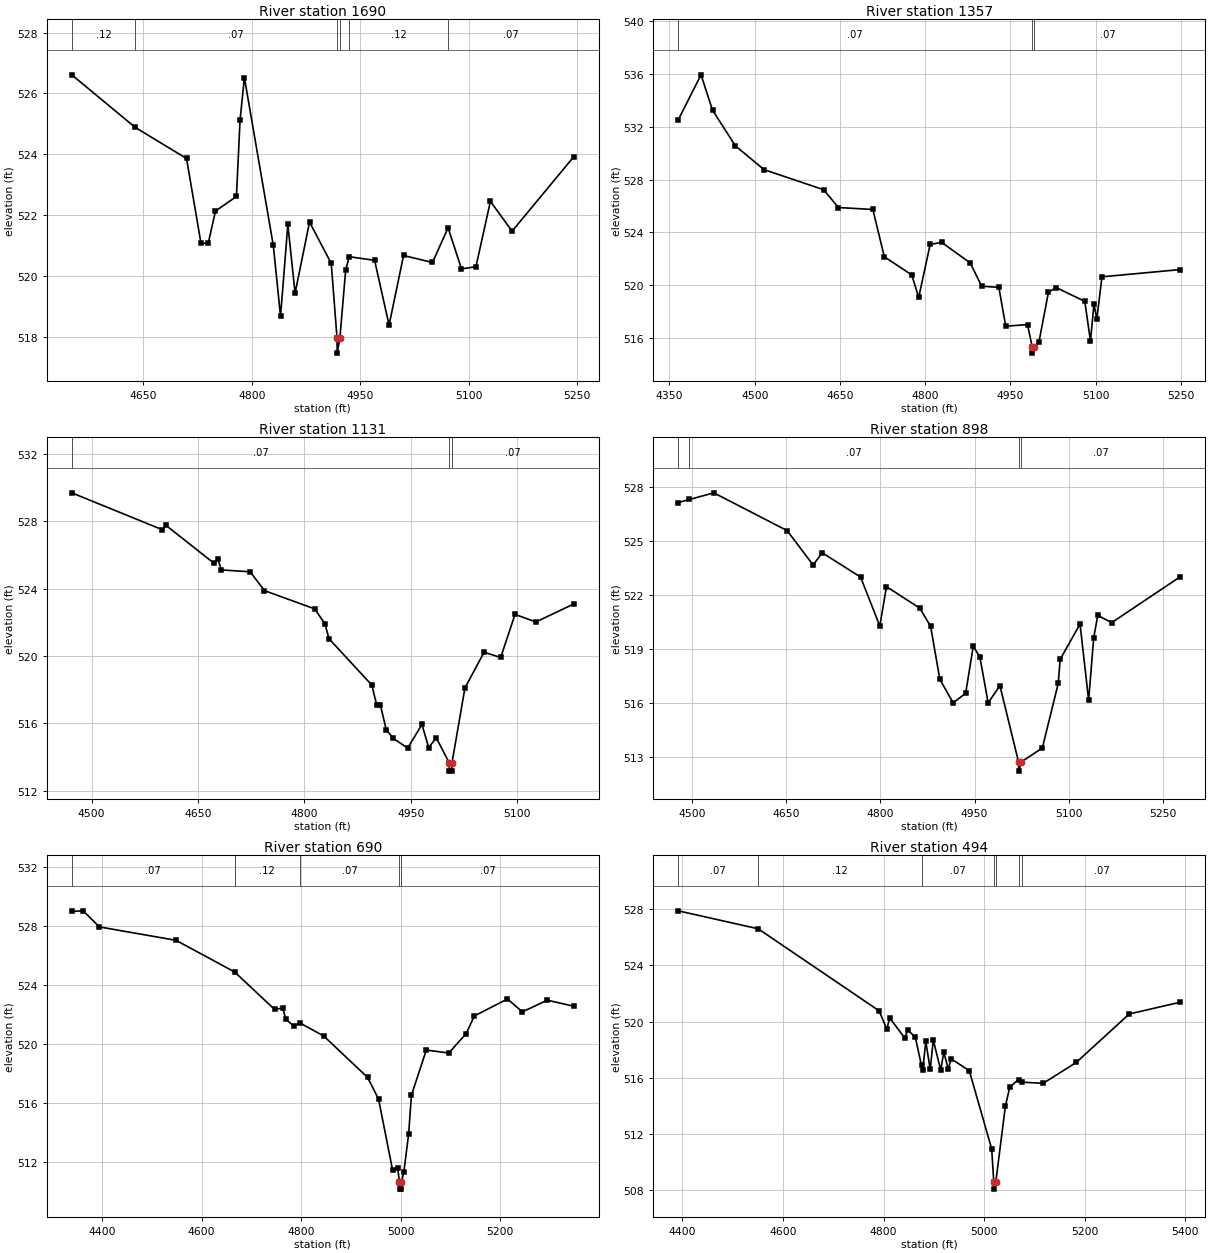
Type RM Length L Ch R = 1,1690,333,333,333
BEGIN DESCRIPTION:
XS6250
END DESCRIPTION:
XS GIS Cut Line= 2
      2307226.38     13726543.06      2307920.37     13726563.88
#Sta/Elev= 30
  4551.1  526.61  4638.9  524.88  4709.8  523.86  4729.8  521.07  4739.8  521.07
  4749.8  522.13  4778.8  522.61  4783.8  525.11  4789.8  526.52  4829.8  521.00
  4839.8  518.67  4849.9  521.69  4859.9  519.43  4879.9  521.77  4909.9  520.41
  4917.9  517.96  4918.1  517.46  4921.9  517.96  4929.9  520.20  4934.9  520.63
  4969.9  520.51  4989.9  518.38  5009.9  520.67  5049.9  520.44  5071.5  521.58
  5090.0  520.23  5110.0  520.30  5130.0  522.45  5160.0  521.47  5245.4  523.92
#Mann=6,-1,0
  4551.1    0.12       0  4638.9    0.07       0  4917.9    0.05       0
  4921.9    0.07       0  4934.9    0.12       0  5071.5    0.07       0
Bank Sta=4917.9,4921.9
Exp/Cntr=0.3,0.1

Type RM Length L Ch R = 1,1357,226,226,226
BEGIN DESCRIPTION:
XS6249
END DESCRIPTION:
XS GIS Cut Line= 2
      2306945.19     13726931.94      2307821.80     13726821.06
#Sta/Elev= 30
  4365.4  532.52  4405.5  535.93  4425.7  533.26  4466.0  530.55  4516.4  528.75
  4621.1  527.23  4647.4  525.88  4707.9  525.73  4728.1  522.15  4776.4  520.77
  4788.6  519.07  4808.7  523.08  4828.9  523.24  4879.3  521.68  4899.4  519.92
  4929.7  519.83  4941.7  516.89  4980.1  517.01  4988.2  515.35  4988.4  514.85
  4992.2  515.35  5000.2  515.68  5016.9  519.46  5030.5  519.82  5080.9  518.77
  5090.9  515.76  5097.0  518.55  5102.1  517.43  5111.1  520.63  5249.0  521.18
#Mann=3,-1,0
  4365.4    0.07       0  4988.2    0.05       0  4992.2    0.07       0
Bank Sta=4988.2,4992.2
Exp/Cntr=0.3,0.1

Type RM Length L Ch R = 1,1131,233,233,233
BEGIN DESCRIPTION:
XS6248
END DESCRIPTION:
XS GIS Cut Line= 2
      2307045.82     13727147.22      2307747.18     13727053.48
#Sta/Elev= 30
  4472.1  529.70  4599.7  527.51  4604.8  527.77  4672.8  525.51  4677.8  525.76
  4683.1  525.12  4723.5  525.01  4743.7  523.89  4814.3  522.81  4829.0  521.92
  4834.5  521.04  4895.0  518.28  4902.0  517.07  4907.1  517.09  4915.2  515.64
  4925.3  515.11  4945.5  514.54  4965.6  515.94  4975.1  514.57  4985.8  515.15
  5004.0  513.67  5004.2  513.17  5007.7  513.17  5008.0  513.67  5026.2  518.11
  5053.2  520.23  5076.6  519.92  5096.8  522.48  5126.2  522.03  5179.7  523.10
#Mann=3,-1,0
  4472.1    0.07       0  5004.0    0.05       0  5008.0    0.07       0
Bank Sta=5004,5008
Exp/Cntr=0.3,0.1

Type RM Length L Ch R = 1,898,208,208,208
BEGIN DESCRIPTION:
E20844
END DESCRIPTION:
XS GIS Cut Line= 3
      2307042.87     13727447.98      2307615.83     13727239.63
      2307732.64     13727088.46
#Sta/Elev= 30
  4477.5  527.14  4495.4  527.31  4534.2  527.68  4651.2  525.58  4692.6  523.67
  4707.1  524.35  4768.3  523.00  4799.0  520.28  4809.6  522.47  4862.8  521.27
  4880.0  520.26  4894.7  517.32  4916.0  516.01  4935.9  516.55  4948.0  519.16
  4958.6  518.55  4971.8  516.01  4990.5  516.97  5020.3  512.72  5020.6  512.22
  5024.3  512.72  5058.2  513.51  5083.5  517.09  5086.6  518.43  5118.3  520.39
  5132.0  516.16  5140.1  519.63  5146.5  520.87  5168.8  520.47  5278.2  523.02
#Mann=4,-1,0
  4477.5    0.12       0  4495.4    0.07       0  5020.3    0.05       0
  5024.3    0.07       0
Bank Sta=5020.3,5024.3
Exp/Cntr=0.3,0.1

Type RM Length L Ch R = 1,690,196,196,196
BEGIN DESCRIPTION:
XS6247
END DESCRIPTION:
XS GIS Cut Line= 3
      2307361.81     13728004.86      2307747.22     13727275.69
      2307754.17     13727091.69
#Sta/Elev= 30
  4339.2  528.96  4362.0  529.00  4394.7  527.91  4548.8  527.00  4666.6  524.85
  4746.9  522.31  4763.3  522.42  4768.9  521.67  4785.3  521.18  4797.0  521.41
  4845.6  520.51  4933.7  517.70  4955.7  516.23  4983.8  511.43  4994.1  511.54
  4997.7  510.63  4998.0  510.13  5001.5  510.13  5001.7  510.63  5006.4  511.27
  5016.1  513.86  5021.7  516.49  5051.6  519.56  5096.9  519.36  5131.8  520.68
  5148.1  521.87  5214.7  523.02  5244.7  522.15  5294.7  522.94  5348.1  522.53
#Mann=5,-1,0
  4339.2    0.07       0  4666.6    0.12       0  4797.0    0.07       0
  4997.7    0.05       0  5001.7    0.07       0
Bank Sta=4997.7,5001.7
Exp/Cntr=0.3,0.1

Type RM Length L Ch R = 1,494,220,220,220
BEGIN DESCRIPTION:
E20843
END DESCRIPTION:
XS GIS Cut Line= 3
      2307463.02     13728059.11      2307851.94     13727496.58
      2307817.22     13727184.08
#Sta/Elev= 30
  4391.8  527.89  4550.8  526.61  4791.4  520.76  4806.3  519.46  4812.4  520.25
  4842.1  518.83  4848.2  519.40  4863.1  518.89  4875.5  516.87  4877.9  516.54
  4884.0  518.59  4892.8  516.59  4898.9  518.68  4913.7  516.54  4919.8  517.82
  4928.6  516.64  4934.7  517.34  4970.5  516.50  5015.1  510.92  5019.2  508.56
  5019.5  508.06  5023.2  508.56  5042.2  513.95  5051.0  515.33  5068.6  515.87
  5076.1  515.68  5117.5  515.60  5183.3  517.09  5288.6  520.54  5390.1  521.38
#Mann=7,-1,0
  4391.8    0.07       0  4550.8    0.12       0  4875.5    0.07       0
  5019.2    0.05       0  5023.2    0.07       0  5068.6    0.12       0
  5076.1    0.07       0
Bank Sta=5019.2,5023.2
Exp/Cntr=0.3,0.1

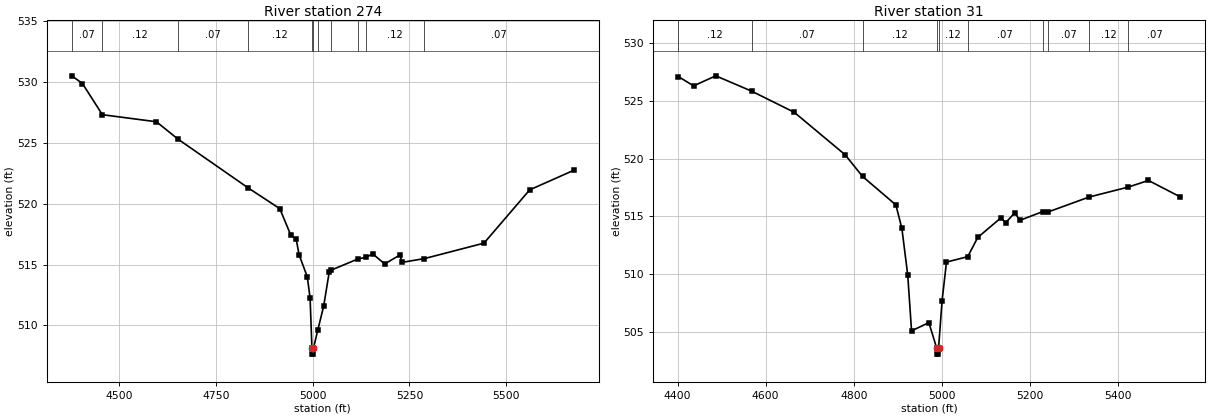
Type RM Length L Ch R = 1,274,243,243,243
BEGIN DESCRIPTION:
XS6246
END DESCRIPTION:
XS GIS Cut Line= 4
      2307525.03     13728154.14      2307997.22     13727650.69
      2307934.72     13727286.11      2307789.98     13727100.01
#Sta/Elev= 30
  4378.4  530.49  4405.9  529.86  4457.4  527.30  4596.9  526.72  4652.4  525.30
  4833.3  521.30  4915.3  519.59  4943.7  517.42  4957.8  517.06  4965.1  515.81
  4986.2  514.00  4993.5  512.28  4998.3  508.15  4998.6  507.65  5002.1  507.65
  5002.3  508.15  5013.6  509.65  5028.6  511.59  5042.8  514.37  5048.3  514.55
  5117.8  515.47  5136.8  515.59  5155.6  515.87  5186.0  515.05  5225.6  515.79
  5230.7  515.18  5288.6  515.49  5442.4  516.76  5560.3  521.13  5674.3  522.74
#Mann=11,-1,0
  4378.4    0.07       0  4457.4    0.12       0  4652.4    0.07       0
  4833.3    0.12       0  4998.3    0.05       0  5002.3    0.12       0
  5013.6    0.07       0  5048.3    0.12       0  5117.8    0.07       0
  5136.8    0.12       0  5288.6    0.07       0
Bank Sta=4998.3,5002.3
Exp/Cntr=0.3,0.1

Type RM Length L Ch R = 1,31,0,0,0
BEGIN DESCRIPTION:
E20842
END DESCRIPTION:
XS GIS Cut Line= 4
      2307713.09     13728201.41      2308147.08     13727888.94
      2308140.13     13727760.47      2307987.51     13727309.53
#Sta/Elev= 30
  4401.6  527.13  4436.5  526.32  4486.8  527.19  4568.8  525.85  4664.8  524.03
  4780.2  520.35  4819.8  518.47  4895.5  516.00  4909.2  513.96  4922.5  509.90
  4931.1  505.08  4970.4  505.79  4988.4  503.56  4988.6  503.06  4992.1  503.06
  4992.4  503.56  5000.4  507.69  5010.4  511.04  5058.6  511.51  5081.4  513.18
  5134.1  514.88  5144.7  514.45  5165.8  515.33  5176.4  514.65  5229.0  515.42
  5240.6  515.38  5334.0  516.68  5423.5  517.55  5468.8  518.12  5541.1  516.69
#Mann=10,-1,0
  4401.6    0.12       0  4568.8    0.07       0  4819.8    0.12       0
  4988.4    0.05       0  4992.4    0.12       0  5058.6    0.07       0
  5229.0    0.12       0  5240.6    0.07       0  5334.0    0.12       0
  5423.5    0.07       0
Bank Sta=4988.4,4992.4
Exp/Cntr=0.3,0.1

Chan Stop Cuts=-1