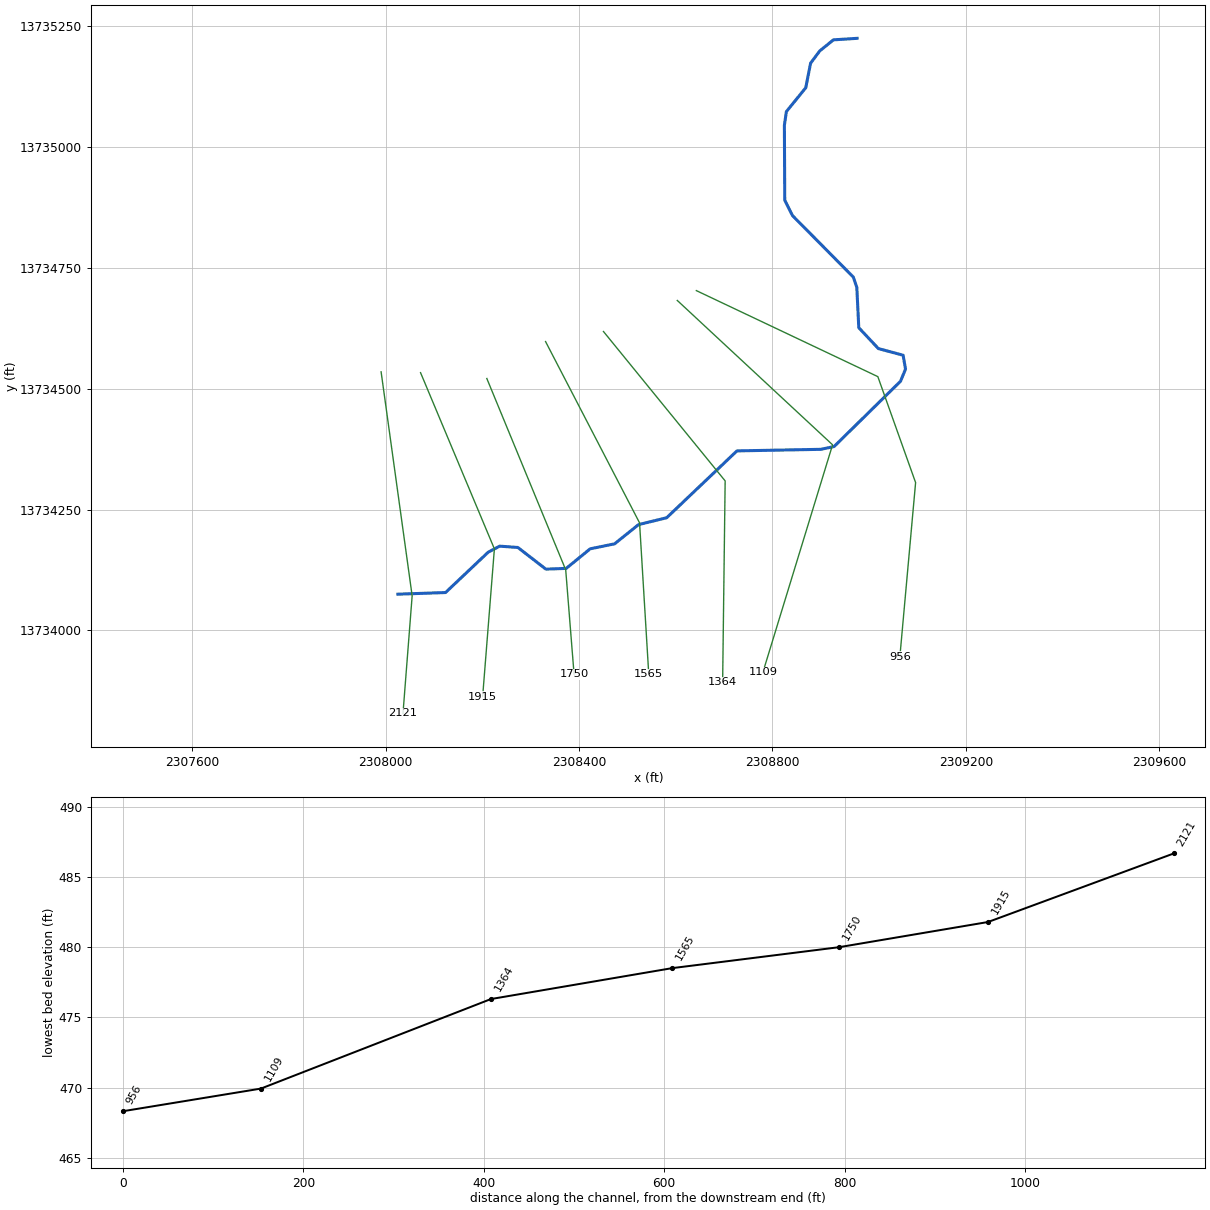
--- Stream0243.prj (project) ---

Proj Title=Stream0243 Base Level Engineering
Current Plan=p01
Default Exp/Contr=0.3,0.1
English Units
Geom File=g01
Flow File=f01
Plan File=p01
BEGIN DESCRIPTION:
Stream0243
END DESCRIPTION:

--- Stream0243.p01 (plan) ---

Plan Title=Multiple Run
Short Identifier=Multiple
Geom File=g01
Flow File=f01
Subcritical Flow
K Sum by GR= 0
Std Step Tol= 0.01
Critical Tol= 0.01
Num of Std Step Trials= 20
Max Error Tol= 0.3
Flow Tol Ratio= 0.001
Split Flow NTrial= 30
Split Flow Tol= 0.02
Split Flow Ratio= 0.02
Log Output Level= 0
Friction Slope Method= 1
Unsteady Friction Slope Method= 2
Unsteady Bridges Friction Slope Method= 1
Parabolic Critical Depth
Global Vel Dist=  1 , 1 , 1
Global Log Level= 0
CheckData=True
Encroach Param= -1, 0, 0, 0
BEGIN DESCRIPTION:
Multiple Run
END DESCRIPTION:

--- Stream0243.f01 (steady flow) ---

Flow Title=Multiple
Number of Profiles=7
Profile Names=10-year,25-year,50-year,1pct_min,100-year,1pct_plu,500-year
River Rch & RM= Stream0243,Reach-1,2121
     227     345     446     281     562    1120     876
Boundary for River Rch & Prof#=Stream0243,Reach-1,1
Up Type=0
Dn Type=3
Dn Slope=0.005
Boundary for River Rch & Prof#=Stream0243,Reach-1,2
Up Type=0
Dn Type=3
Dn Slope=0.005
Boundary for River Rch & Prof#=Stream0243,Reach-1,3
Up Type=0
Dn Type=3
Dn Slope=0.005
Boundary for River Rch & Prof#=Stream0243,Reach-1,4
Up Type=0
Dn Type=3
Dn Slope=0.005
Boundary for River Rch & Prof#=Stream0243,Reach-1,5
Up Type=0
Dn Type=3
Dn Slope=0.005
Boundary for River Rch & Prof#=Stream0243,Reach-1,6
Up Type=0
Dn Type=3
Dn Slope=0.005
Boundary for River Rch & Prof#=Stream0243,Reach-1,7
Up Type=0
Dn Type=3
Dn Slope=0.005

--- Stream0243.g01 (geometry) ---

Geom Title=Existing Conditions

River Reach=Stream0243,Reach-1
Reach XY= 30
      2308025.00     13734075.00      2308123.59     13734078.40
      2308211.80     13734161.85      2308235.63     13734174.39
      2308273.26     13734171.63      2308331.11     13734126.84
      2308373.28     13734128.34      2308422.80     13734168.84
      2308473.28     13734179.15      2308522.81     13734218.90
      2308581.06     13734233.14      2308726.46     13734371.46
      2308900.12     13734374.71      2308927.45     13734380.46
      2309064.94     13734515.58      2309075.25     13734540.70
      2309070.23     13734569.36      2309019.03     13734583.15
      2308978.56     13734626.30      2308974.47     13734709.78
      2308967.14     13734731.17      2308841.43     13734858.24
      2308825.38     13734890.16      2308824.63     13735045.15
      2308828.75     13735073.45      2308868.87     13735122.84
      2308878.83     13735173.55      2308897.72     13735198.85
      2308926.03     13735221.86      2308975.00     13735225.00

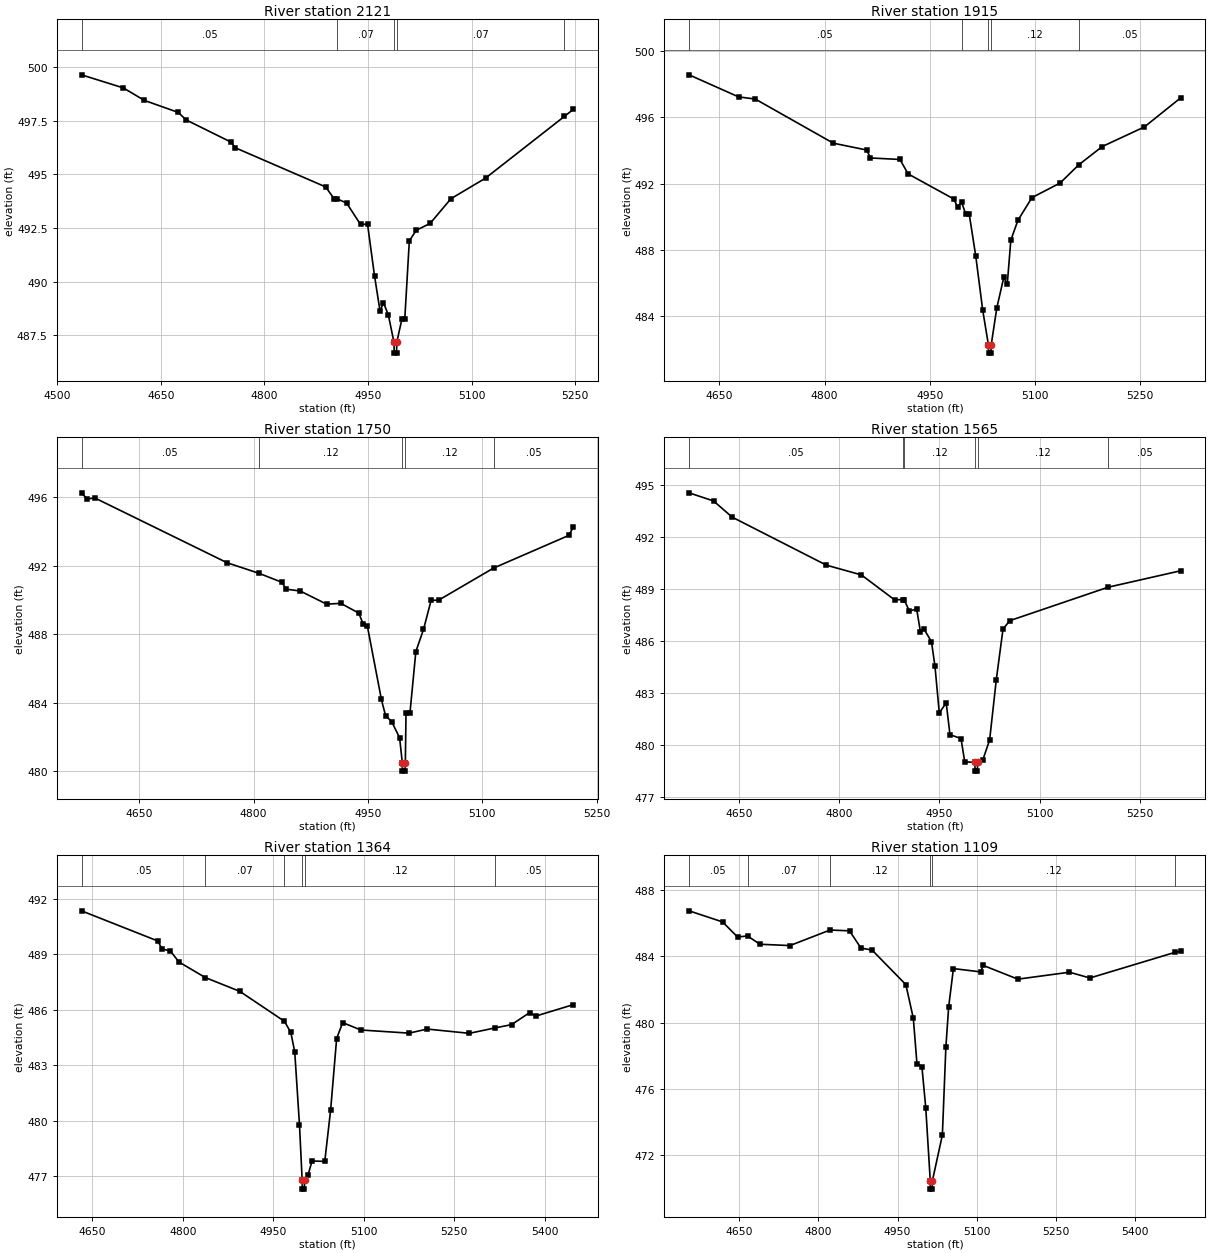
Type RM Length L Ch R = 1,2121,206,206,206
BEGIN DESCRIPTION:
XS6256
END DESCRIPTION:
XS GIS Cut Line= 3
      2307990.28     13734535.04      2308054.51     13734071.53
      2308035.55     13733828.41
#Sta/Elev= 30
  4535.2  499.63  4595.8  499.02  4626.1  498.44  4675.2  497.88  4686.7  497.53
  4752.0  496.49  4757.3  496.24  4888.6  494.41  4900.6  493.87  4905.5  493.85
  4918.9  493.66  4939.1  492.66  4949.2  492.68  4959.3  490.27  4967.3  488.63
  4972.3  489.02  4979.4  488.44  4987.5  487.17  4987.8  486.67  4991.3  486.67
  4991.5  487.17  4998.9  488.25  5003.1  488.25  5009.7  491.90  5019.7  492.39
  5039.8  492.71  5069.9  493.86  5120.0  494.82  5234.0  497.69  5247.0  498.02
#Mann=5,-1,0
  4535.2    0.05       0  4905.5    0.07       0  4987.5    0.05       0
  4991.5    0.07       0  5234.0    0.05       0
Bank Sta=4987.5,4991.5
Exp/Cntr=0.3,0.1

Type RM Length L Ch R = 1,1915,165,165,165
BEGIN DESCRIPTION:
XS6255
END DESCRIPTION:
XS GIS Cut Line= 3
      2308071.88     13734533.33      2308224.65     13734168.75
      2308200.35     13733863.21
#Sta/Elev= 30
  4606.6  498.56  4677.3  497.23  4701.1  497.10  4812.5  494.44  4860.0  494.03
  4865.5  493.55  4907.6  493.46  4919.2  492.59  4984.3  491.08  4989.8  490.60
  4995.4  490.90  5001.2  490.20  5006.3  490.20  5015.7  487.65  5025.7  484.37
  5033.8  482.29  5034.0  481.79  5037.5  481.79  5037.8  482.29  5045.8  484.52
  5055.7  486.35  5060.7  485.94  5065.8  488.60  5075.9  489.79  5095.9  491.16
  5136.1  492.04  5162.8  493.14  5196.3  494.24  5256.4  495.42  5308.4  497.18
#Mann=5,-1,0
  4606.6    0.05       0  4995.4    0.12       0  5033.8    0.05       0
  5037.8    0.12       0  5162.8    0.05       0
Bank Sta=5033.8,5037.8
Exp/Cntr=0.3,0.1

Type RM Length L Ch R = 1,1750,185,185,185
BEGIN DESCRIPTION:
XS6254
END DESCRIPTION:
XS GIS Cut Line= 3
      2308209.02     13734521.21      2308372.22     13734125.35
      2308389.52     13733909.12
#Sta/Elev= 30
  4574.3  496.27  4581.6  495.91  4591.8  495.97  4765.4  492.18  4806.8  491.57
  4837.2  491.04  4842.6  490.64  4861.2  490.53  4895.9  489.76  4914.4  489.81
  4938.0  489.24  4943.8  488.60  4949.2  488.50  4967.7  484.19  4973.1  483.25
  4981.2  482.89  4991.6  481.95  4995.1  480.50  4995.3  480.00  4998.8  480.00
  4999.1  480.50  5000.0  483.42  5005.2  483.42  5012.9  486.99  5022.9  488.28
  5032.9  489.98  5043.0  490.00  5114.8  491.87  5213.5  493.78  5219.4  494.26
#Mann=5,-1,0
  4574.3    0.05       0  4806.8    0.12       0  4995.1    0.05       0
  4999.1    0.12       0  5114.8    0.05       0
Bank Sta=4995.1,4999.1
Exp/Cntr=0.3,0.1

Type RM Length L Ch R = 1,1565,201,201,201
BEGIN DESCRIPTION:
XS6253
END DESCRIPTION:
XS GIS Cut Line= 3
      2308330.53     13734597.61      2308525.00     13734222.57
      2308544.04     13733909.21
#Sta/Elev= 30
  4575.0  494.55  4611.7  494.08  4639.5  493.15  4780.7  490.38  4833.0  489.82
  4882.8  488.38  4895.2  488.40  4896.9  488.40  4905.0  487.73  4915.8  487.86
  4921.5  486.53  4927.1  486.68  4938.0  485.97  4943.2  484.57  4949.7  481.87
  4960.1  482.44  4965.7  480.61  4982.2  480.39  4987.8  479.05  5003.0  479.01
  5003.3  478.51  5006.8  478.51  5007.0  479.01  5015.1  479.18  5025.1  480.31
  5035.1  483.79  5045.1  486.69  5055.1  487.18  5202.5  489.11  5311.4  490.06
#Mann=6,-1,0
  4575.0    0.05       0  4895.2    0.07       0  4896.9    0.12       0
  5003.0    0.05       0  5007.0    0.12       0  5202.5    0.05       0
Bank Sta=5003,5007
Exp/Cntr=0.3,0.1

Type RM Length L Ch R = 1,1364,255,255,255
BEGIN DESCRIPTION:
XS6252
END DESCRIPTION:
XS GIS Cut Line= 3
      2308450.34     13734618.42      2308702.08     13734309.38
      2308696.87     13733892.71
#Sta/Elev= 30
  4632.1  491.35  4758.6  489.72  4765.5  489.29  4779.4  489.18  4793.8  488.58
  4837.6  487.74  4894.4  487.00  4968.5  485.38  4979.1  484.78  4985.6  483.73
  4993.5  479.78  4997.9  476.81  4998.2  476.31  5001.7  476.31  5001.9  476.81
  5007.8  477.09  5014.3  477.83  5035.4  477.81  5045.1  480.58  5055.1  484.45
  5065.1  485.31  5095.1  484.91  5175.1  484.74  5205.1  484.96  5275.1  484.73
  5317.4  485.02  5345.1  485.20  5375.1  485.85  5385.1  485.66  5447.4  486.28
#Mann=6,-1,0
  4632.1    0.05       0  4837.6    0.07       0  4968.5    0.12       0
  4997.9    0.05       0  5001.9    0.12       0  5317.4    0.05       0
Bank Sta=4997.9,5001.9
Exp/Cntr=0.3,0.1

Type RM Length L Ch R = 1,1109,153,153,153
BEGIN DESCRIPTION:
XS6251
END DESCRIPTION:
XS GIS Cut Line= 3
      2308603.09     13734682.67      2308924.31     13734384.03
      2308780.20     13733913.50
#Sta/Elev= 30
  4555.3  486.76  4618.7  486.09  4647.0  485.18  4666.0  485.24  4689.5  484.74
  4746.2  484.66  4822.2  485.60  4859.0  485.55  4880.6  484.51  4901.6  484.39
  4965.6  482.30  4979.7  480.27  4986.6  477.53  4996.0  477.34  5003.3  474.84
  5011.8  470.44  5012.1  469.94  5015.6  469.94  5015.8  470.44  5034.7  473.21
  5041.3  478.50  5046.6  480.95  5055.6  483.27  5106.9  483.07  5112.1  483.46
  5177.6  482.63  5275.3  483.05  5313.9  482.70  5475.0  484.25  5486.0  484.31
#Mann=6,-1,0
  4555.3    0.05       0  4666.0    0.07       0  4822.2    0.12       0
  5011.8    0.05       0  5015.8    0.12       0  5475.0    0.07       0
Bank Sta=5011.8,5015.8
Exp/Cntr=0.3,0.1

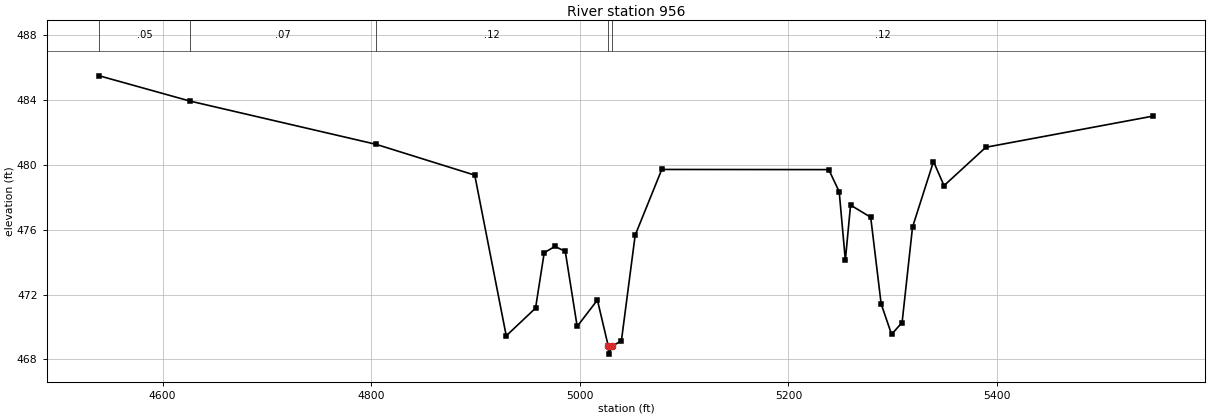
Type RM Length L Ch R = 1,956,0,0,0
BEGIN DESCRIPTION:
E20845
END DESCRIPTION:
XS GIS Cut Line= 4
      2308642.51     13734703.05      2309017.97     13734525.09
      2309096.10     13734305.90      2309063.55     13733945.66
#Sta/Elev= 30
  4539.4  485.51  4626.4  483.95  4804.8  481.28  4899.3  479.38  4929.5  469.46
  4957.6  471.17  4965.9  474.59  4976.2  474.98  4986.1  474.67  4997.5  470.04
  5016.9  471.67  5027.3  468.83  5027.6  468.33  5031.3  468.83  5039.9  469.15
  5053.1  475.67  5078.6  479.73  5238.7  479.72  5248.7  478.36  5254.6  474.13
  5259.6  477.53  5278.9  476.78  5288.9  471.44  5298.9  469.55  5309.0  470.28
  5319.0  476.17  5339.1  480.22  5349.2  478.73  5389.3  481.10  5549.3  483.02
#Mann=5,-1,0
  4539.4    0.05       0  4626.4    0.07       0  4804.8    0.12       0
  5027.3    0.05       0  5031.3    0.12       0
Bank Sta=5027.3,5031.3
Exp/Cntr=0.3,0.1

Chan Stop Cuts=-1