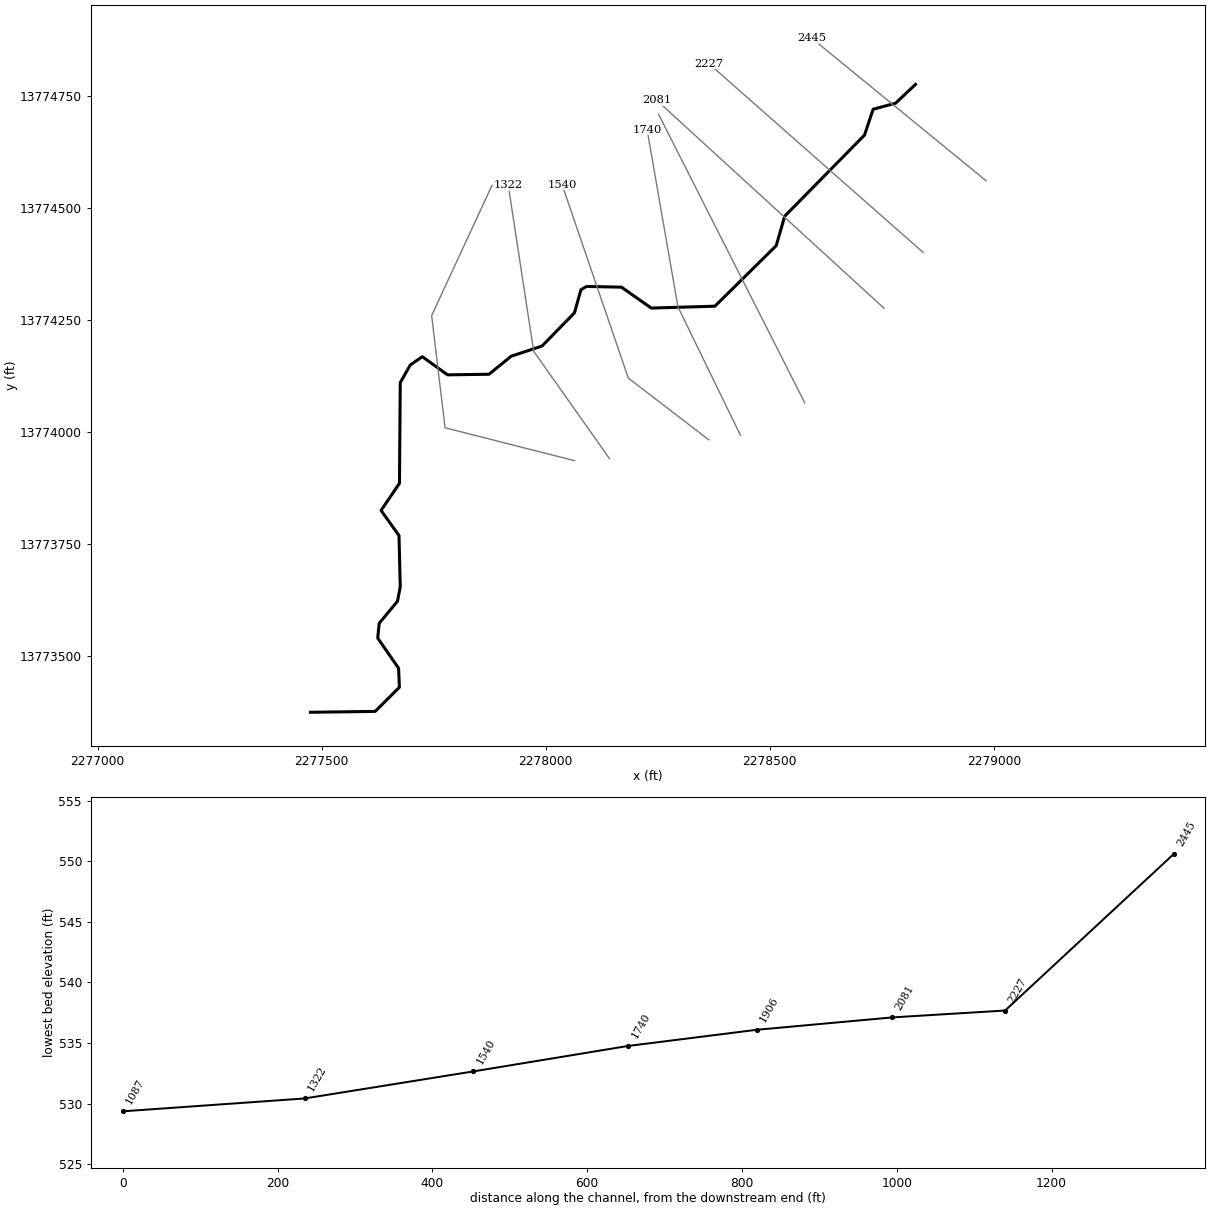
--- Stream0253.prj (project) ---

Proj Title=Stream0253 Base Level Engineering
Current Plan=p01
Default Exp/Contr=0.3,0.1
English Units
Geom File=g01
Flow File=f01
Plan File=p01
BEGIN DESCRIPTION:
Stream0253
END DESCRIPTION:

--- Stream0253.p01 (plan) ---

Plan Title=Multiple Run
Short Identifier=Multiple
Geom File=g01
Flow File=f01
Subcritical Flow
K Sum by GR= 0
Std Step Tol= 0.01
Critical Tol= 0.01
Num of Std Step Trials= 20
Max Error Tol= 0.3
Flow Tol Ratio= 0.001
Split Flow NTrial= 30
Split Flow Tol= 0.02
Split Flow Ratio= 0.02
Log Output Level= 0
Friction Slope Method= 1
Unsteady Friction Slope Method= 2
Unsteady Bridges Friction Slope Method= 1
Parabolic Critical Depth
Global Vel Dist=  1 , 1 , 1
Global Log Level= 0
CheckData=True
Encroach Param= -1, 0, 0, 0
BEGIN DESCRIPTION:
Multiple Run
END DESCRIPTION:

--- Stream0253.f01 (steady flow) ---

Flow Title=Multiple
Number of Profiles=7
Profile Names=10-year,25-year,50-year,1pct_min,100-year,1pct_plu,500-year
River Rch & RM= Stream0253,Reach-1,2445
     515     811    1070     684    1364    2721    2192
Boundary for River Rch & Prof#=Stream0253,Reach-1,1
Up Type=0
Dn Type=3
Dn Slope=0.005
Boundary for River Rch & Prof#=Stream0253,Reach-1,2
Up Type=0
Dn Type=3
Dn Slope=0.005
Boundary for River Rch & Prof#=Stream0253,Reach-1,3
Up Type=0
Dn Type=3
Dn Slope=0.005
Boundary for River Rch & Prof#=Stream0253,Reach-1,4
Up Type=0
Dn Type=3
Dn Slope=0.005
Boundary for River Rch & Prof#=Stream0253,Reach-1,5
Up Type=0
Dn Type=3
Dn Slope=0.005
Boundary for River Rch & Prof#=Stream0253,Reach-1,6
Up Type=0
Dn Type=3
Dn Slope=0.005
Boundary for River Rch & Prof#=Stream0253,Reach-1,7
Up Type=0
Dn Type=3
Dn Slope=0.005

--- Stream0253.g01 (geometry) ---

Geom Title=Existing Conditions

River Reach=Stream0253,Reach-1
Reach XY= 30
      2278825.00     13774775.00      2278780.70     13774733.12
      2278730.51     13774719.56      2278711.28     13774662.01
      2278533.16     13774481.05      2278514.22     13774415.32
      2278377.45     13774280.45      2278235.51     13774276.21
      2278168.94     13774322.87      2278090.89     13774324.48
      2278078.41     13774316.95      2278064.10     13774265.61
      2277991.71     13774191.63      2277922.83     13774168.85
      2277873.41     13774128.68      2277780.88     13774127.38
      2277724.65     13774167.78      2277697.84     13774149.48
      2277675.38     13774110.12      2277673.62     13773885.44
      2277632.56     13773825.00      2277672.55     13773769.14
      2277675.38     13773654.86      2277669.22     13773622.65
      2277628.38     13773573.26      2277625.11     13773540.39
      2277671.64     13773473.23      2277673.47     13773430.83
      2277619.41     13773376.93      2277475.00     13773375.00

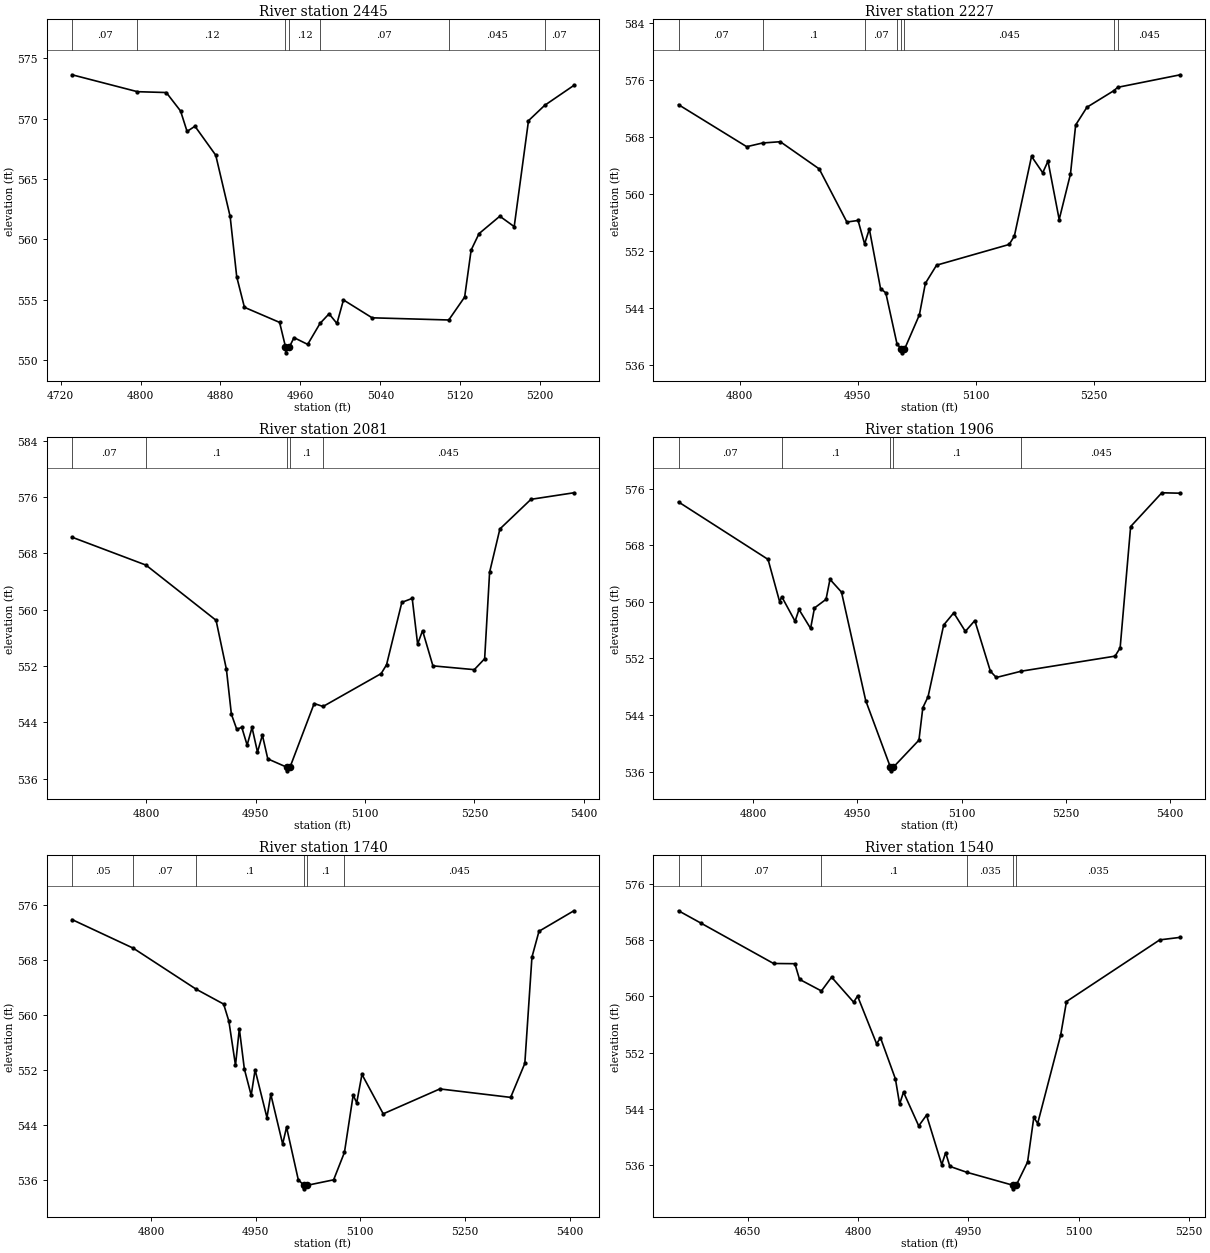
Type RM Length L Ch R = 1,2445,218,218,218
BEGIN DESCRIPTION:
XS6264
END DESCRIPTION:
XS GIS Cut Line= 2
      2278982.64     13774560.07      2278593.73     13774877.80
#Sta/Elev= 30
  4731.5  573.62  4796.9  572.22  4825.8  572.15  4840.1  570.62  4846.6  568.93
  4854.5  569.36  4875.3  566.96  4889.7  561.89  4896.3  556.89  4904.0  554.37
  4939.2  553.12  4945.1  551.10  4945.3  550.60  4949.1  551.10  4953.6  551.86
  4967.3  551.30  4979.7  553.04  4988.7  553.83  4996.6  553.03  5003.1  554.98
  5031.8  553.50  5108.5  553.32  5124.4  555.22  5130.9  559.11  5138.8  560.47
  5159.6  561.91  5174.0  561.05  5188.3  569.82  5204.5  571.09  5233.7  572.74
#Mann=7,-1,0
  4731.5    0.07       0  4796.9    0.12       0  4945.1    0.05       0
  4949.1    0.12       0  4979.7    0.07       0  5108.5   0.045       0
  5204.5    0.07       0
Bank Sta=4945.1,4949.1
Exp/Cntr=0.3,0.1

Type RM Length L Ch R = 1,2227,146,146,146
BEGIN DESCRIPTION:
XS6263
END DESCRIPTION:
XS GIS Cut Line= 2
      2278842.02     13774400.34      2278364.14     13774821.08
#Sta/Elev= 30
  4722.5  572.54  4809.0  566.64  4829.1  567.16  4851.6  567.34  4901.0  563.52
  4936.1  556.06  4950.3  556.28  4958.6  552.98  4964.6  555.08  4978.8  546.72
  4985.5  546.11  4999.6  538.99  5005.2  538.19  5005.5  537.69  5009.2  538.19
  5028.1  543.02  5035.7  547.45  5049.9  550.00  5142.0  552.91  5148.6  554.08
  5170.4  565.28  5184.6  562.98  5191.3  564.61  5205.5  556.41  5219.8  562.80
  5226.4  569.69  5240.7  572.18  5274.6  574.49  5279.8  574.98  5359.2  576.74
#Mann=8,-1,0
  4722.5    0.07       0  4829.1     0.1       0  4958.6    0.07       0
  4999.6   0.045       0  5005.2   0.045       0  5009.2   0.045       0
  5274.6    0.07       0  5279.8   0.045       0
Bank Sta=5005.2,5009.2
Exp/Cntr=0.3,0.1

Type RM Length L Ch R = 1,2081,175,175,175
BEGIN DESCRIPTION:
XS6262
END DESCRIPTION:
XS GIS Cut Line= 2
      2278754.75     13774275.92      2278247.10     13774740.14
#Sta/Elev= 30
  4698.4  570.30  4799.7  566.34  4895.8  558.50  4910.0  551.53  4916.8  545.17
  4924.2  543.01  4931.0  543.31  4938.4  540.78  4945.1  543.28  4952.6  539.78
  4959.3  542.20  4966.7  538.82  4993.1  537.62  4993.4  537.12  4997.1  537.62
  5030.3  546.68  5042.5  546.26  5122.1  550.93  5129.5  552.18  5150.5  561.05
  5164.7  561.61  5172.1  555.13  5178.9  557.03  5193.1  552.03  5249.8  551.49
  5264.0  553.04  5270.8  565.33  5284.9  571.47  5327.5  575.68  5386.3  576.61
#Mann=5,-1,0
  4698.4    0.07       0  4799.7     0.1       0  4993.1    0.05       0
  4997.1     0.1       0  5042.5   0.045       0
Bank Sta=4993.1,4997.1
Exp/Cntr=0.3,0.1

Type RM Length L Ch R = 1,1906,166,166,166
BEGIN DESCRIPTION:
XS6261
END DESCRIPTION:
XS GIS Cut Line= 2
      2278578.04     13774064.77      2278251.56     13774708.74
#Sta/Elev= 30
  4692.7  574.12  4821.5  566.00  4838.1  560.04  4841.3  560.71  4860.4  557.25
  4866.0  558.92  4882.7  556.24  4888.3  559.13  4904.9  560.35  4910.6  563.18
  4927.2  561.37  4962.0  546.04  4997.6  536.60  4997.9  536.10  5001.6  536.60
  5038.6  540.44  5044.2  545.03  5051.7  546.57  5074.2  556.72  5088.7  558.44
  5105.4  555.82  5119.0  557.35  5141.4  550.19  5149.9  549.30  5185.8  550.19
  5320.8  552.32  5328.1  553.49  5343.2  570.64  5388.1  575.42  5414.7  575.36
#Mann=5,-1,0
  4692.7    0.07       0  4841.3     0.1       0  4997.6    0.05       0
  5001.6     0.1       0  5185.8   0.045       0
Bank Sta=4997.6,5001.6
Exp/Cntr=0.3,0.1

Type RM Length L Ch R = 1,1740,200,200,200
BEGIN DESCRIPTION:
XS6260
END DESCRIPTION:
XS GIS Cut Line= 3
      2278434.27     13773992.90      2278295.01     13774278.91
      2278226.13     13774674.24
#Sta/Elev= 30
  4686.7  573.90  4774.5  569.74  4864.5  563.79  4904.0  561.62  4911.5  559.14
  4921.0  552.73  4926.5  558.04  4933.7  552.19  4943.5  548.37  4949.1  552.06
  4966.1  545.12  4971.6  548.51  4988.6  541.29  4994.2  543.73  5011.0  536.10
  5019.1  535.27  5019.4  534.77  5023.1  535.27  5061.7  536.08  5077.2  540.07
  5089.7  548.38  5094.8  547.28  5102.3  551.40  5132.8  545.67  5214.0  549.29
  5315.5  548.06  5335.8  553.00  5346.0  568.44  5356.1  572.20  5406.1  575.18
#Mann=6,-1,0
  4686.7    0.05       0  4774.5    0.07       0  4864.5     0.1       0
  5019.1    0.05       0  5023.1     0.1       0  5077.2   0.045       0
Bank Sta=5019.1,5023.1
Exp/Cntr=0.3,0.1

Type RM Length L Ch R = 1,1540,218,218,218
BEGIN DESCRIPTION:
XS6259
END DESCRIPTION:
XS GIS Cut Line= 3
      2278363.87     13773982.43      2278184.20     13774120.17
      2278036.45     13774551.47
#Sta/Elev= 30
  4556.1  572.13  4586.7  570.37  4685.3  564.65  4714.3  564.62  4720.6  562.40
  4750.4  560.75  4764.2  562.71  4794.2  559.16  4799.5  560.03  4825.4  553.26
  4830.7  554.11  4851.0  548.27  4856.7  544.70  4862.0  546.39  4882.7  541.60
  4893.3  543.13  4914.0  536.11  4919.3  537.80  4925.0  535.86  4947.7  535.03
  5011.2  533.17  5011.4  532.67  5015.2  533.17  5030.7  536.48  5039.2  542.82
  5044.4  541.94  5075.7  554.49  5083.6  559.25  5210.4  568.00  5238.4  568.36
#Mann=6,-1,0
  4556.1    0.05       0  4586.7    0.07       0  4750.4     0.1       0
  4947.7   0.035       0  5011.2   0.035       0  5015.2   0.035       0
Bank Sta=5011.2,5015.2
Exp/Cntr=0.3,0.1

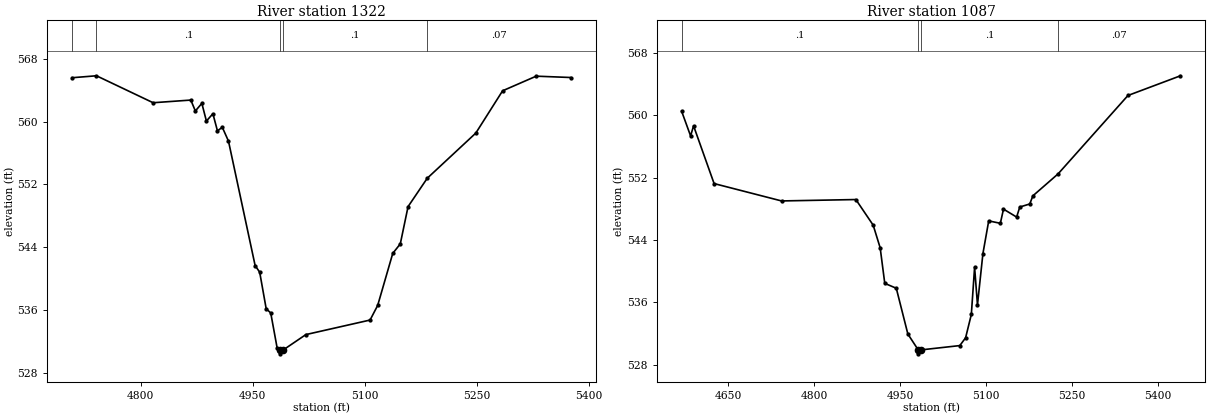
Type RM Length L Ch R = 1,1322,235,235,235
BEGIN DESCRIPTION:
XS6258
END DESCRIPTION:
XS GIS Cut Line= 3
      2278142.29     13773940.43      2277973.04     13774180.07
      2277916.25     13774550.76
#Sta/Elev= 30
  4707.8  565.57  4740.7  565.82  4816.6  562.39  4867.1  562.73  4873.2  561.34
  4881.9  562.31  4888.0  560.06  4896.7  560.99  4902.8  558.81  4909.3  559.27
  4917.6  557.50  4953.3  541.67  4959.4  540.83  4968.1  536.18  4974.2  535.64
  4982.7  531.23  4987.0  530.94  4987.2  530.44  4991.0  530.94  5021.3  532.89
  5107.3  534.74  5117.5  536.60  5137.7  543.22  5147.8  544.43  5158.2  549.17
  5183.9  552.78  5249.0  558.53  5284.9  563.91  5329.9  565.77  5376.2  565.60
#Mann=5,-1,0
  4707.8    0.07       0  4740.7     0.1       0  4987.0    0.05       0
  4991.0     0.1       0  5183.9    0.07       0
Bank Sta=4987,4991
Exp/Cntr=0.3,0.1

Type RM Length L Ch R = 1,1087,0,0,0
BEGIN DESCRIPTION:
XS6257
END DESCRIPTION:
XS GIS Cut Line= 4
      2278064.43     13773935.97      2277775.37     13774009.36
      2277745.42     13774259.44      2277880.09     13774549.72
#Sta/Elev= 30
  4569.1  560.52  4584.7  557.36  4589.9  558.65  4625.7  551.24  4743.4  549.01
  4873.0  549.19  4903.2  545.90  4915.4  542.99  4923.4  538.43  4943.5  537.80
  4963.7  531.92  4981.8  529.88  4982.1  529.38  4985.8  529.88  5054.3  530.44
  5064.4  531.44  5074.4  534.44  5080.1  540.50  5085.1  535.67  5094.6  542.25
  5104.7  546.45  5125.0  546.14  5130.5  547.96  5153.4  546.94  5158.9  548.23
  5176.3  548.62  5181.8  549.67  5225.8  552.49  5347.6  562.55  5439.2  565.08
#Mann=4,-1,0
  4569.1     0.1       0  4981.8    0.05       0  4985.8     0.1       0
  5225.8    0.07       0
Bank Sta=4981.8,4985.8
Exp/Cntr=0.3,0.1

Chan Stop Cuts=-1