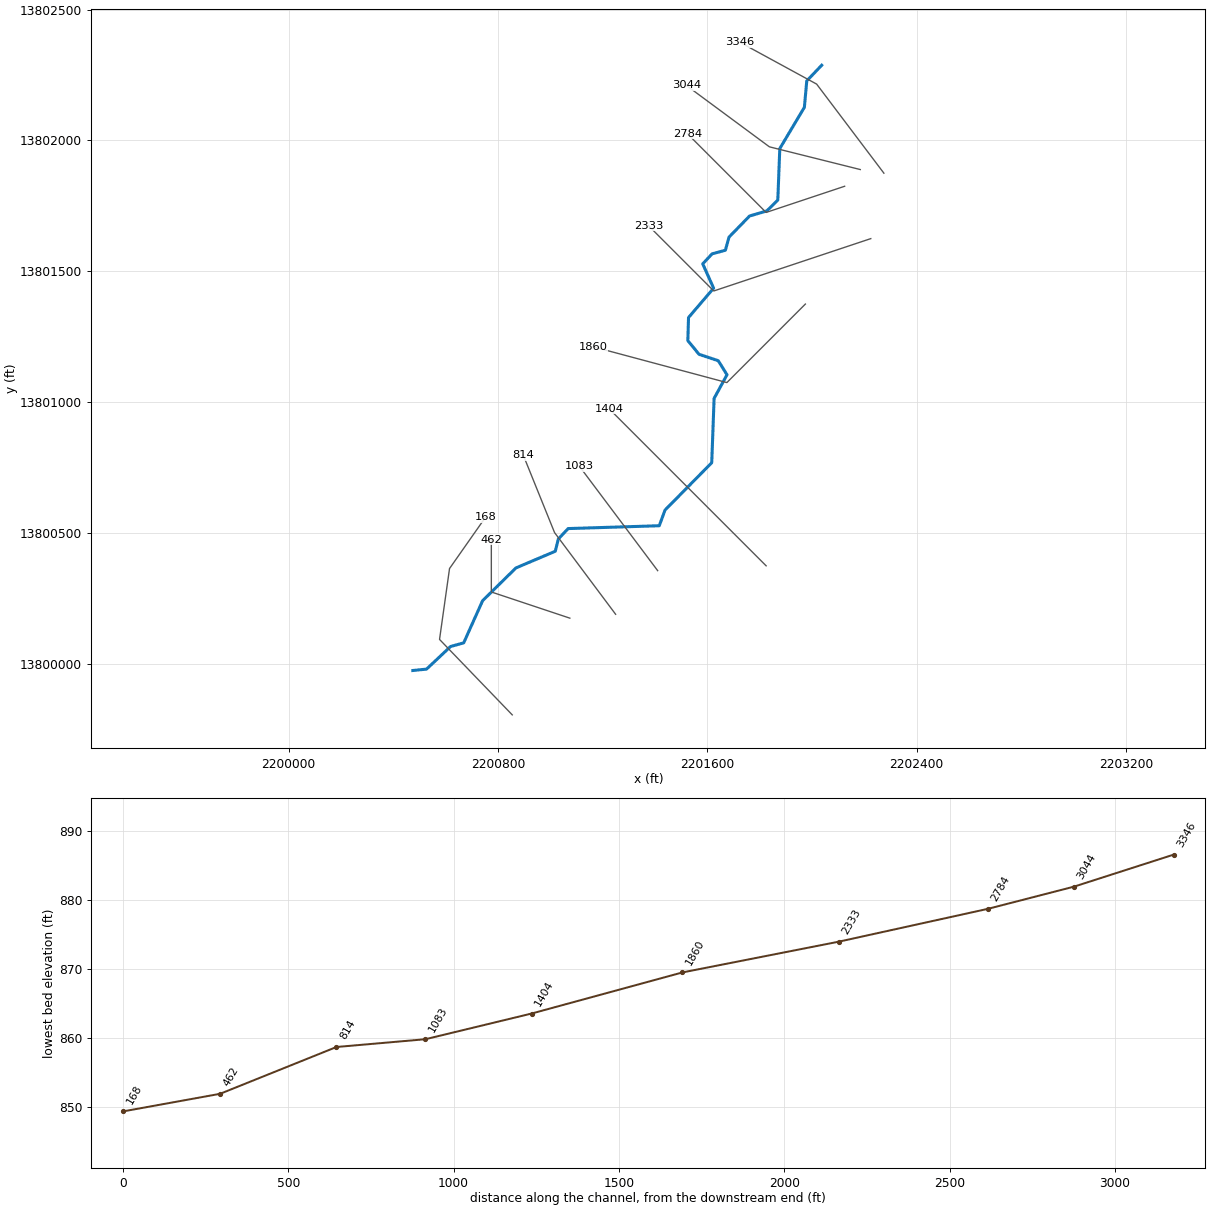
--- Tributary 1 of West Fork Trib.prj (project) ---

Proj Title=Tributary 1 of West Fork Trib Base Level Engineering
Current Plan=p01
Default Exp/Contr=0.3,0.1
English Units
Geom File=g01
Flow File=f01
Plan File=p01
BEGIN DESCRIPTION:
Tributary 1 of West Fork Trib
END DESCRIPTION:

--- Tributary 1 of West Fork Trib.p01 (plan) ---

Plan Title=Multiple Run
Short Identifier=Multiple
Geom File=g01
Flow File=f01
Subcritical Flow
K Sum by GR= 0
Std Step Tol= 0.01
Critical Tol= 0.01
Num of Std Step Trials= 20
Max Error Tol= 0.3
Flow Tol Ratio= 0.001
Split Flow NTrial= 30
Split Flow Tol= 0.02
Split Flow Ratio= 0.02
Log Output Level= 0
Friction Slope Method= 1
Unsteady Friction Slope Method= 2
Unsteady Bridges Friction Slope Method= 1
Parabolic Critical Depth
Global Vel Dist=  1 , 1 , 1
Global Log Level= 0
CheckData=True
Encroach Param= -1, 0, 0, 0
BEGIN DESCRIPTION:
Multiple Run
END DESCRIPTION:

--- Tributary 1 of West Fork Trib.f01 (steady flow) ---

Flow Title=Multiple
Number of Profiles=7
Profile Names=10-year,25-year,50-year,1pct_min,100-year,1pct_plu,500-year
River Rch & RM= Tributary 1 of W,Reach-1,3346
     276     425     554     351     700    1396    1102
Boundary for River Rch & Prof#=Tributary 1 of W,Reach-1,1
Up Type=0
Dn Type=3
Dn Slope=0.005
Boundary for River Rch & Prof#=Tributary 1 of W,Reach-1,2
Up Type=0
Dn Type=3
Dn Slope=0.005
Boundary for River Rch & Prof#=Tributary 1 of W,Reach-1,3
Up Type=0
Dn Type=3
Dn Slope=0.005
Boundary for River Rch & Prof#=Tributary 1 of W,Reach-1,4
Up Type=0
Dn Type=3
Dn Slope=0.005
Boundary for River Rch & Prof#=Tributary 1 of W,Reach-1,5
Up Type=0
Dn Type=3
Dn Slope=0.005
Boundary for River Rch & Prof#=Tributary 1 of W,Reach-1,6
Up Type=0
Dn Type=3
Dn Slope=0.005
Boundary for River Rch & Prof#=Tributary 1 of W,Reach-1,7
Up Type=0
Dn Type=3
Dn Slope=0.005

--- Tributary 1 of West Fork Trib.g01 (geometry) ---

Geom Title=Existing Conditions

River Reach=Tributary 1 of W,Reach-1
Reach XY= 30
      2202037.31     13802287.31      2201980.29     13802227.52
      2201971.19     13802126.58      2201877.24     13801969.07
      2201869.64     13801772.30      2201827.57     13801730.74
      2201761.78     13801711.37      2201683.27     13801630.77
      2201669.31     13801580.62      2201618.61     13801566.72
      2201582.75     13801528.64      2201624.35     13801435.65
      2201528.47     13801323.50      2201525.87     13801235.33
      2201568.64     13801183.03      2201642.21     13801158.50
      2201675.44     13801104.97      2201626.24     13801014.50
      2201617.19     13800768.81      2201438.74     13800587.95
      2201416.70     13800528.07      2201068.54     13800517.26
      2201030.88     13800477.24      2201019.38     13800430.63
      2200868.95     13800366.86      2200741.64     13800241.68
      2200669.41     13800080.61      2200619.26     13800066.71
      2200527.51     13799980.33      2200475.00     13799975.00

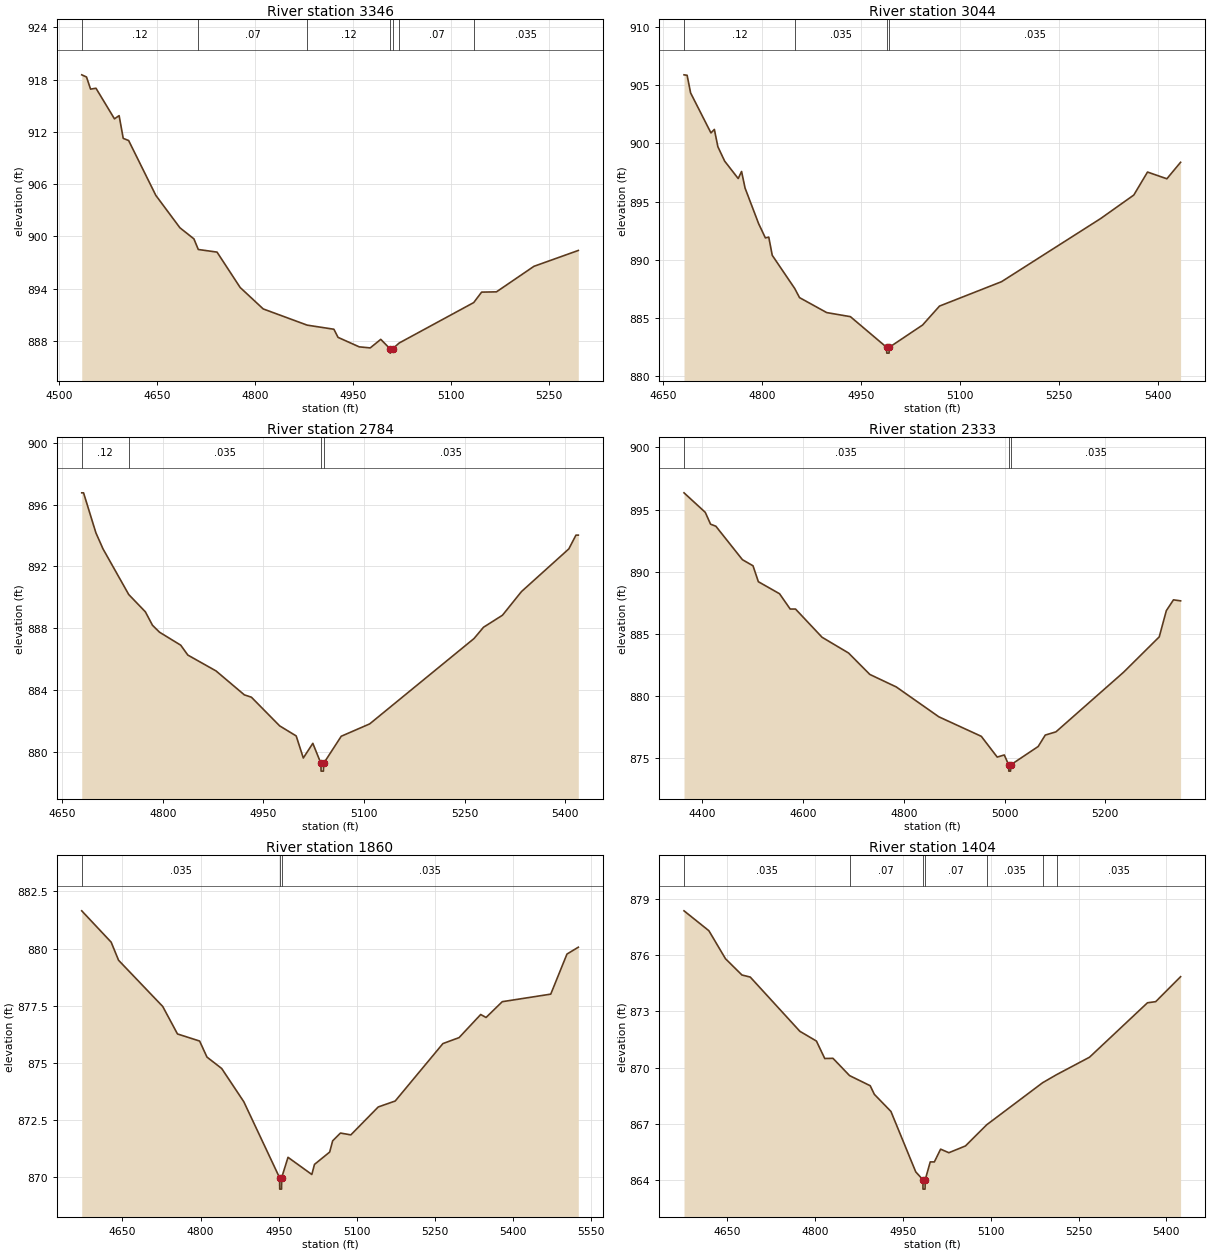
Type RM Length L Ch R = 1,3346,302,302,302
BEGIN DESCRIPTION:
Tributary 1 of West Fork Tributary 7.0
END DESCRIPTION:
XS GIS Cut Line= 3
      2202274.98     13801875.02      2202018.06     13802215.28
      2201725.01     13802374.99
#Sta/Elev= 30
  4535.2  918.54  4542.5  918.29  4548.7  916.90  4557.0  917.00  4585.3  913.49
  4592.4  913.86  4598.7  911.25  4607.0  911.00  4648.6  904.71  4685.5  900.99
  4706.9  899.72  4713.6  898.50  4742.3  898.20  4777.7  894.14  4813.0  891.68
  4880.3  889.82  4921.2  889.35  4927.5  888.42  4959.9  887.33  4976.8  887.21
  4992.9  888.19  5007.1  887.11  5007.3  886.61  5011.1  887.11  5021.1  887.77
  5135.2  892.41  5147.3  893.61  5170.0  893.64  5227.4  896.57  5295.3  898.39
#Mann=7,-1,0
  4535.2    0.12       0  4713.6    0.07       0  4880.3    0.12       0
  5007.1    0.05       0  5011.1    0.12       0  5021.1    0.07       0
  5135.2   0.035       0
Bank Sta=5007.1,5011.1
Exp/Cntr=0.3,0.1

Type RM Length L Ch R = 1,3044,260,260,260
BEGIN DESCRIPTION:
XS7856
END DESCRIPTION:
XS GIS Cut Line= 3
      2202184.74     13801888.88      2201837.50     13801975.69
      2201520.27     13802210.17
#Sta/Elev= 30
  4682.3  905.91  4687.0  905.87  4692.3  904.35  4723.1  900.91  4728.3  901.21
  4733.6  899.72  4743.9  898.48  4764.4  896.98  4769.5  897.59  4774.8  896.16
  4795.4  893.09  4805.6  891.87  4810.7  891.94  4816.0  890.37  4850.1  887.51
  4857.3  886.73  4898.5  885.44  4934.4  885.09  4989.3  882.45  4989.5  881.95
  4993.0  881.95  4993.3  882.45  5043.8  884.37  5069.4  886.00  5163.4  888.10
  5313.7  893.54  5363.8  895.56  5384.6  897.54  5413.9  896.96  5434.7  898.38
#Mann=4,-1,0
  4682.3    0.12       0  4850.1   0.035       0  4989.3   0.035       0
  4993.3   0.035       0
Bank Sta=4989.3,4993.3
Exp/Cntr=0.3,0.1

Type RM Length L Ch R = 1,2784,451,451,451
BEGIN DESCRIPTION:
Tributary 1 of West Fork Tributary 6.0
END DESCRIPTION:
XS GIS Cut Line= 3
      2202125.04     13801825.01      2201825.00     13801725.00
      2201525.02     13802024.98
#Sta/Elev= 30
  4679.1  896.76  4681.8  896.76  4700.2  894.17  4710.8  893.13  4749.2  890.17
  4774.0  889.05  4784.6  888.18  4795.1  887.73  4826.7  886.89  4837.3  886.25
  4879.4  885.22  4921.6  883.67  4932.1  883.52  4974.3  881.66  4998.9  881.01
  5009.5  879.58  5023.7  880.53  5035.8  879.23  5036.0  878.73  5039.5  878.73
  5039.8  879.23  5066.1  880.99  5108.5  881.79  5264.1  887.32  5278.2  888.05
  5306.5  888.83  5334.8  890.36  5405.5  893.13  5416.1  894.02  5419.6  894.02
#Mann=4,-1,0
  4679.1    0.12       0  4749.2   0.035       0  5035.8   0.035       0
  5039.8   0.035       0
Bank Sta=5035.8,5039.8
Exp/Cntr=0.3,0.1

Type RM Length L Ch R = 1,2333,473,473,473
BEGIN DESCRIPTION:
Tributary 1 of West Fork Tributary 5.0
END DESCRIPTION:
XS GIS Cut Line= 3
      2202225.01     13801625.00      2201625.00     13801425.00
      2201375.01     13801674.99
#Sta/Elev= 30
  4363.6  896.35  4405.8  894.78  4416.3  893.83  4426.9  893.66  4479.6  890.97
  4500.6  890.48  4511.2  889.20  4553.3  888.23  4574.4  887.00  4585.0  887.00
  4637.7  884.73  4690.4  883.46  4732.5  881.74  4785.2  880.73  4869.6  878.33
  4953.9  876.76  4985.5  875.09  4999.6  875.26  5008.2  874.46  5008.5  873.96
  5012.0  873.96  5012.2  874.46  5066.8  875.94  5080.9  876.86  5102.1  877.12
  5236.5  881.92  5307.2  884.76  5321.3  886.87  5335.5  887.74  5349.6  887.66
#Mann=3,-1,0
  4363.6   0.035       0  5008.2   0.035       0  5012.2   0.035       0
Bank Sta=5008.2,5012.2
Exp/Cntr=0.3,0.1

Type RM Length L Ch R = 1,1860,456,456,456
BEGIN DESCRIPTION:
Tributary 1 of West Fork Tributary 4.0
END DESCRIPTION:
XS GIS Cut Line= 3
      2201974.98     13801374.98      2201675.00     13801075.00
      2201163.93     13801211.79
#Sta/Elev= 30
  4571.9  881.65  4628.4  880.28  4642.6  879.49  4727.4  877.47  4755.7  876.27
  4798.2  875.96  4812.3  875.26  4840.6  874.76  4883.0  873.31  4951.7  869.99
  4952.0  869.49  4955.5  869.49  4955.7  869.99  4967.9  870.88  5013.6  870.13
  5018.7  870.57  5047.9  871.11  5053.6  871.60  5068.6  871.94  5088.5  871.86
  5141.1  873.08  5173.7  873.34  5265.3  875.85  5296.3  876.11  5337.8  877.12
  5348.1  876.99  5379.2  877.68  5472.3  878.01  5503.4  879.76  5525.2  880.06
#Mann=3,-1,0
  4571.9   0.035       0  4951.7   0.035       0  4955.7   0.035       0
Bank Sta=4951.7,4955.7
Exp/Cntr=0.3,0.1

Type RM Length L Ch R = 1,1404,321,321,321
BEGIN DESCRIPTION:
Tributary 1 of West Fork Tributary 3.0
END DESCRIPTION:
XS GIS Cut Line= 3
      2201825.03     13800374.97      2201525.00     13800675.00
      2201224.98     13800975.02
#Sta/Elev= 30
  4575.7  878.35  4618.2  877.29  4646.5  875.80  4674.7  874.93  4688.9  874.82
  4773.7  871.93  4802.0  871.41  4816.2  870.48  4830.3  870.49  4858.6  869.57
  4893.9  869.03  4901.0  868.57  4929.3  867.66  4971.7  864.44  4983.9  864.02
  4984.1  863.52  4987.6  863.52  4987.9  864.02  4996.5  864.97  5003.5  864.97
  5014.2  865.65  5028.3  865.46  5056.6  865.82  5093.0  866.95  5188.5  869.19
  5212.4  869.62  5268.7  870.55  5367.7  873.45  5381.8  873.51  5424.3  874.84
#Mann=7,-1,0
  4575.7   0.035       0  4858.6    0.07       0  4983.9    0.05       0
  4987.9    0.07       0  5093.0   0.035       0  5188.5    0.07       0
  5212.4   0.035       0
Bank Sta=4983.9,4987.9
Exp/Cntr=0.3,0.1

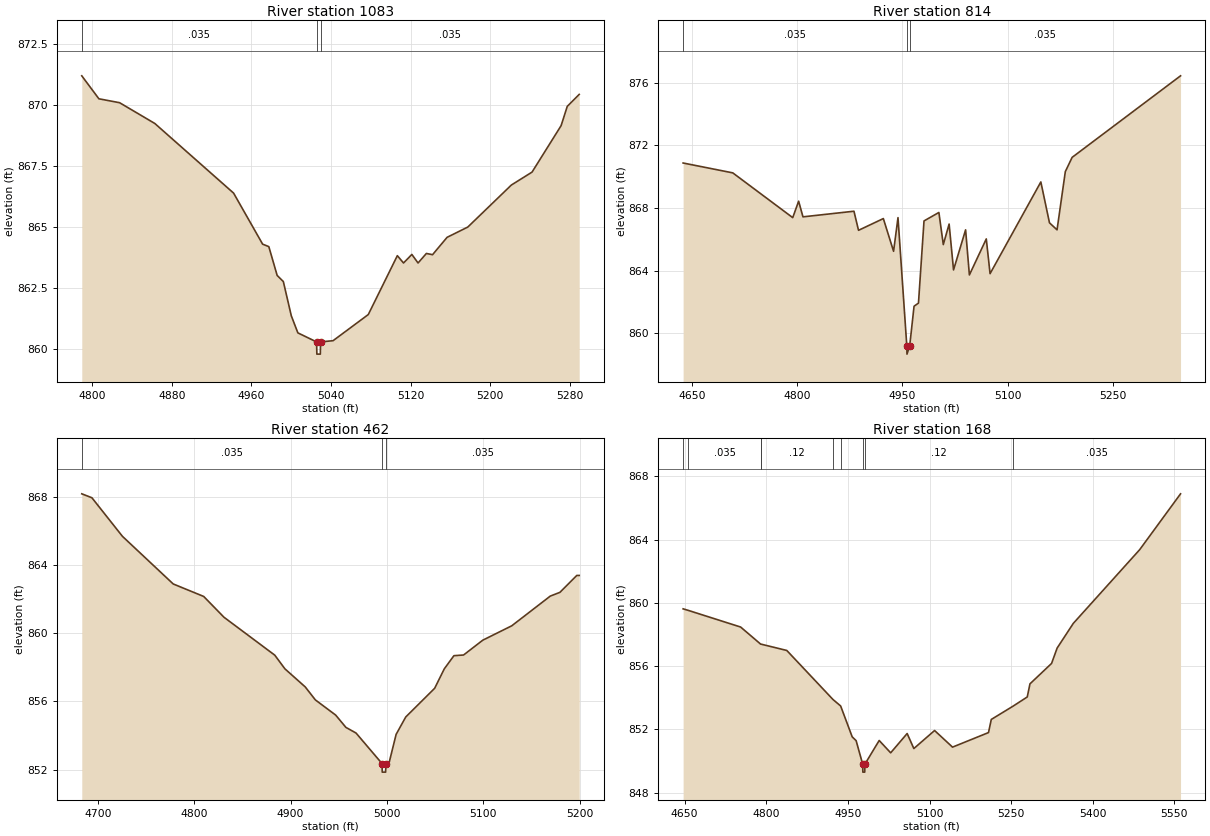
Type RM Length L Ch R = 1,1083,269,269,269
BEGIN DESCRIPTION:
Tributary 1 of West Fork Tributary 2.0
END DESCRIPTION:
XS GIS Cut Line= 3
      2201410.54     13800356.55      2201260.56     13800556.53
      2201110.54     13800756.55
#Sta/Elev= 30
  4789.5  871.18  4806.7  870.24  4827.5  870.08  4862.9  869.23  4942.1  866.38
  4971.3  864.29  4977.5  864.19  4985.9  863.01  4992.1  862.76  5000.1  861.36
  5006.7  860.66  5025.5  860.29  5025.8  859.79  5029.3  859.79  5029.5  860.29
  5042.1  860.34  5077.5  861.41  5106.7  863.82  5112.9  863.52  5121.3  863.87
  5127.5  863.52  5135.9  863.91  5142.1  863.86  5156.7  864.57  5177.5  864.99
  5221.3  866.71  5242.1  867.24  5271.3  869.14  5277.5  869.93  5289.5  870.42
#Mann=3,-1,0
  4789.5   0.035       0  5025.5   0.035       0  5029.5   0.035       0
Bank Sta=5025.5,5029.5
Exp/Cntr=0.3,0.1

Type RM Length L Ch R = 1,814,352,352,352
BEGIN DESCRIPTION:
H21499
END DESCRIPTION:
XS GIS Cut Line= 3
      2201249.88     13800189.86      2201016.56     13800501.99
      2200896.78     13800798.30
#Sta/Elev= 30
  4637.3  870.87  4708.1  870.24  4793.6  867.38  4802.0  868.43  4808.2  867.43
  4880.9  867.79  4887.4  866.57  4922.8  867.32  4937.4  865.23  4943.7  867.38
  4956.3  859.16  4956.5  858.66  4960.3  859.16  4966.6  861.72  4972.9  861.92
  4980.8  867.17  5002.0  867.71  5008.3  865.66  5016.6  866.97  5022.9  864.04
  5040.1  866.60  5045.5  863.72  5069.6  866.02  5075.0  863.80  5147.4  869.66
  5159.7  867.05  5170.5  866.60  5182.3  870.32  5192.0  871.23  5346.6  876.44
#Mann=3,-1,0
  4637.3   0.035       0  4956.3   0.035       0  4960.3   0.035       0
Bank Sta=4956.3,4960.3
Exp/Cntr=0.3,0.1

Type RM Length L Ch R = 1,462,294,294,294
BEGIN DESCRIPTION:
Tributary 1 of West Fork Tributary 1.0
END DESCRIPTION:
XS GIS Cut Line= 3
      2201075.00     13800175.00      2200775.00     13800275.00
      2200775.00     13800474.97
#Sta/Elev= 30
  4683.4  868.16  4693.9  867.93  4725.6  865.67  4778.3  862.88  4809.9  862.15
  4831.0  860.93  4883.7  858.71  4894.2  857.91  4915.3  856.85  4925.8  856.09
  4946.9  855.20  4957.5  854.48  4968.0  854.15  4995.0  852.36  4995.2  851.86
  4998.7  851.86  4999.0  852.36  5002.1  852.36  5009.6  854.07  5019.6  855.09
  5049.6  856.77  5059.6  857.91  5069.6  858.68  5079.6  858.72  5099.6  859.59
  5129.6  860.43  5169.6  862.17  5179.6  862.39  5197.1  863.38  5199.6  863.38
#Mann=3,-1,0
  4683.4   0.035       0  4995.0   0.035       0  4999.0   0.035       0
Bank Sta=4995,4999
Exp/Cntr=0.3,0.1

Type RM Length L Ch R = 1,168,0,0,0
BEGIN DESCRIPTION:
XS7857
END DESCRIPTION:
XS GIS Cut Line= 4
      2200854.87     13799805.54      2200577.08     13800093.75
      2200615.28     13800364.58      2200753.31     13800561.28
#Sta/Elev= 30
  4647.2  859.62  4656.9  859.52  4752.9  858.47  4789.7  857.39  4790.2  857.39
  4837.7  856.99  4922.6  853.89  4936.7  853.48  4957.9  851.53  4965.1  851.29
  4977.2  849.80  4977.5  849.30  4981.0  849.30  4981.2  849.80  5007.5  851.30
  5028.6  850.52  5058.9  851.74  5071.2  850.79  5109.3  851.93  5142.3  850.88
  5208.4  851.80  5213.5  852.63  5253.1  853.46  5279.6  854.05  5284.6  854.88
  5324.3  856.17  5334.5  857.14  5364.2  858.70  5486.2  863.36  5561.3  866.89
#Mann=9,-1,0
  4647.2    0.12       0  4656.9   0.035       0  4789.7    0.07       0
  4790.2    0.12       0  4922.6   0.035       0  4936.7    0.12       0
  4977.2    0.05       0  4981.2    0.12       0  5253.1   0.035       0
Bank Sta=4977.2,4981.2
Exp/Cntr=0.3,0.1

Chan Stop Cuts=-1