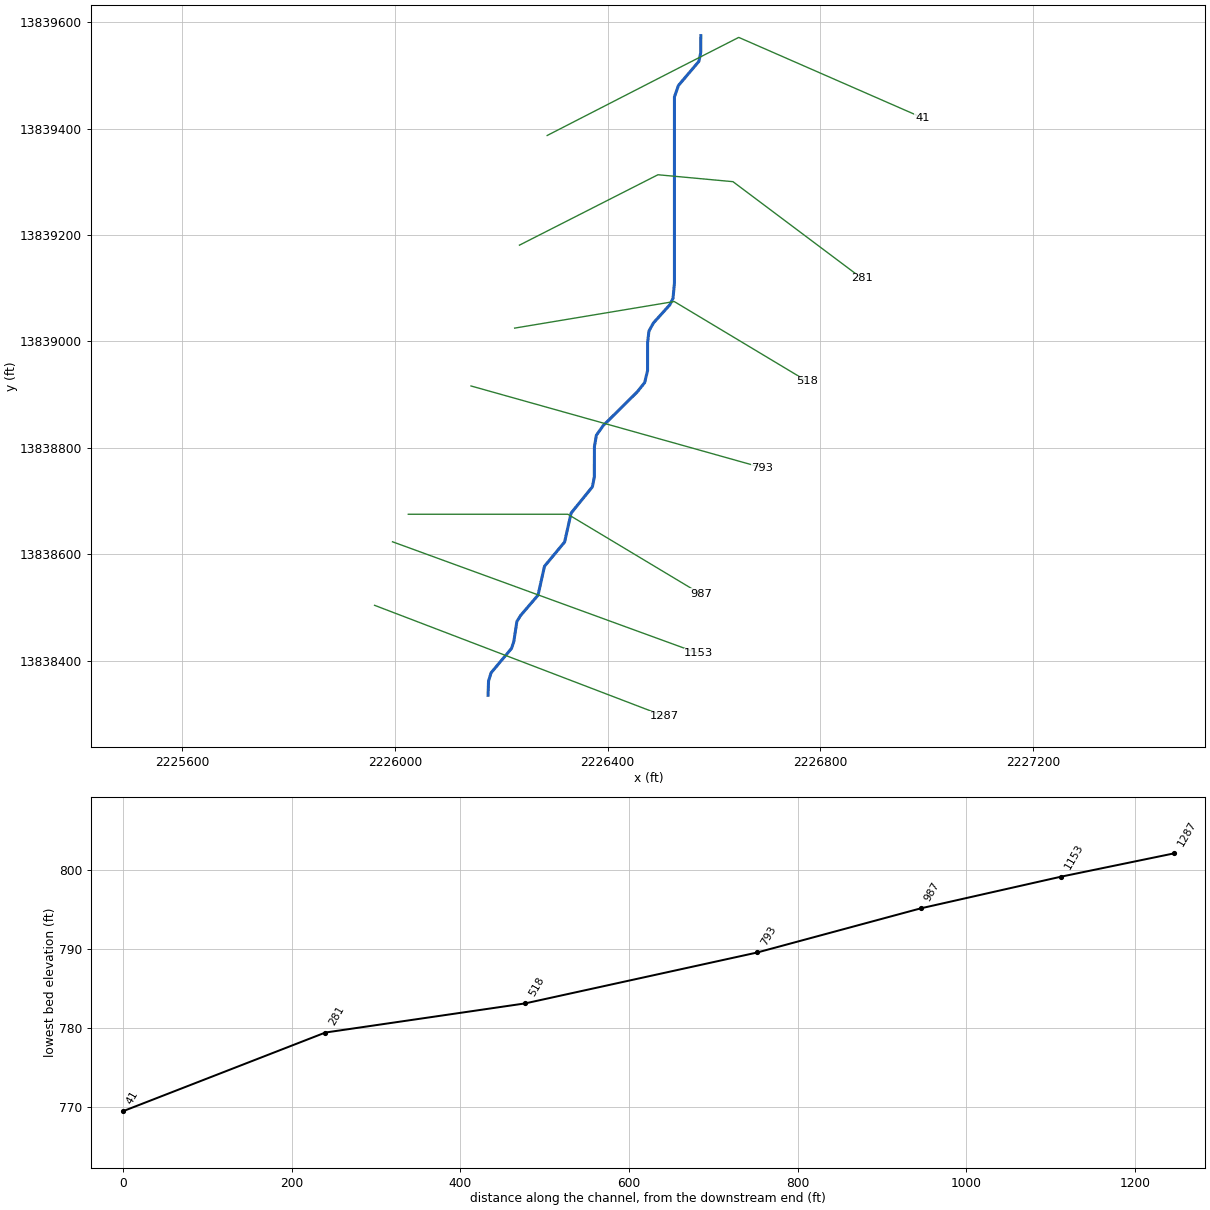
--- Turkey Creek 1.prj (project) ---

Proj Title=Turkey Creek 1 Base Level Engineering
Current Plan=p01
Default Exp/Contr=0.3,0.1
English Units
Geom File=g01
Flow File=f01
Plan File=p01
BEGIN DESCRIPTION:
Turkey Creek 1
END DESCRIPTION:

--- Turkey Creek 1.p01 (plan) ---

Plan Title=Multiple Run
Short Identifier=Multiple
Geom File=g01
Flow File=f01
Subcritical Flow
K Sum by GR= 0
Std Step Tol= 0.01
Critical Tol= 0.01
Num of Std Step Trials= 20
Max Error Tol= 0.3
Flow Tol Ratio= 0.001
Split Flow NTrial= 30
Split Flow Tol= 0.02
Split Flow Ratio= 0.02
Log Output Level= 0
Friction Slope Method= 1
Unsteady Friction Slope Method= 2
Unsteady Bridges Friction Slope Method= 1
Parabolic Critical Depth
Global Vel Dist=  1 , 1 , 1
Global Log Level= 0
CheckData=True
Encroach Param= -1, 0, 0, 0
BEGIN DESCRIPTION:
Multiple Run
END DESCRIPTION:

--- Turkey Creek 1.f01 (steady flow) ---

Flow Title=Multiple
Number of Profiles=7
Profile Names=10-year,25-year,50-year,1pct_min,100-year,1pct_plu,500-year
River Rch & RM= Turkey Creek 1,Reach-1,1287
     662    1100    1510    1010    2016    4022    3540
River Rch & RM= Turkey Creek 1,Reach-1,41
    1818    3150    4443    3031    6048   12068   11093
Boundary for River Rch & Prof#=Turkey Creek 1,Reach-1,1
Up Type=0
Dn Type=3
Dn Slope=0.005
Boundary for River Rch & Prof#=Turkey Creek 1,Reach-1,2
Up Type=0
Dn Type=3
Dn Slope=0.005
Boundary for River Rch & Prof#=Turkey Creek 1,Reach-1,3
Up Type=0
Dn Type=3
Dn Slope=0.005
Boundary for River Rch & Prof#=Turkey Creek 1,Reach-1,4
Up Type=0
Dn Type=3
Dn Slope=0.005
Boundary for River Rch & Prof#=Turkey Creek 1,Reach-1,5
Up Type=0
Dn Type=3
Dn Slope=0.005
Boundary for River Rch & Prof#=Turkey Creek 1,Reach-1,6
Up Type=0
Dn Type=3
Dn Slope=0.005
Boundary for River Rch & Prof#=Turkey Creek 1,Reach-1,7
Up Type=0
Dn Type=3
Dn Slope=0.005

--- Turkey Creek 1.g01 (geometry) ---

Geom Title=Existing Conditions

River Reach=Turkey Creek 1,Reach-1
Reach XY= 30
      2226175.00     13838334.71      2226175.89     13838361.31
      2226180.66     13838376.92      2226219.10     13838422.73
      2226223.40     13838435.66      2226229.14     13838473.29
      2226236.08     13838484.55      2226268.92     13838522.80
      2226281.08     13838577.20      2226318.92     13838622.80
      2226331.12     13838677.18      2226371.17     13838726.59
      2226374.76     13838745.10      2226374.99     13838802.28
      2226378.62     13838823.50      2226391.49     13838841.74
      2226455.33     13838904.86      2226469.46     13838922.58
      2226474.87     13838945.05      2226474.94     13838997.75
      2226477.47     13839019.43      2226485.90     13839034.63
      2226516.86     13839068.94      2226522.74     13839080.94
      2226525.43     13839109.82      2226525.45     13839459.81
      2226532.89     13839481.16      2226571.35     13839526.51
      2226574.88     13839543.20      2226575.00     13839575.00

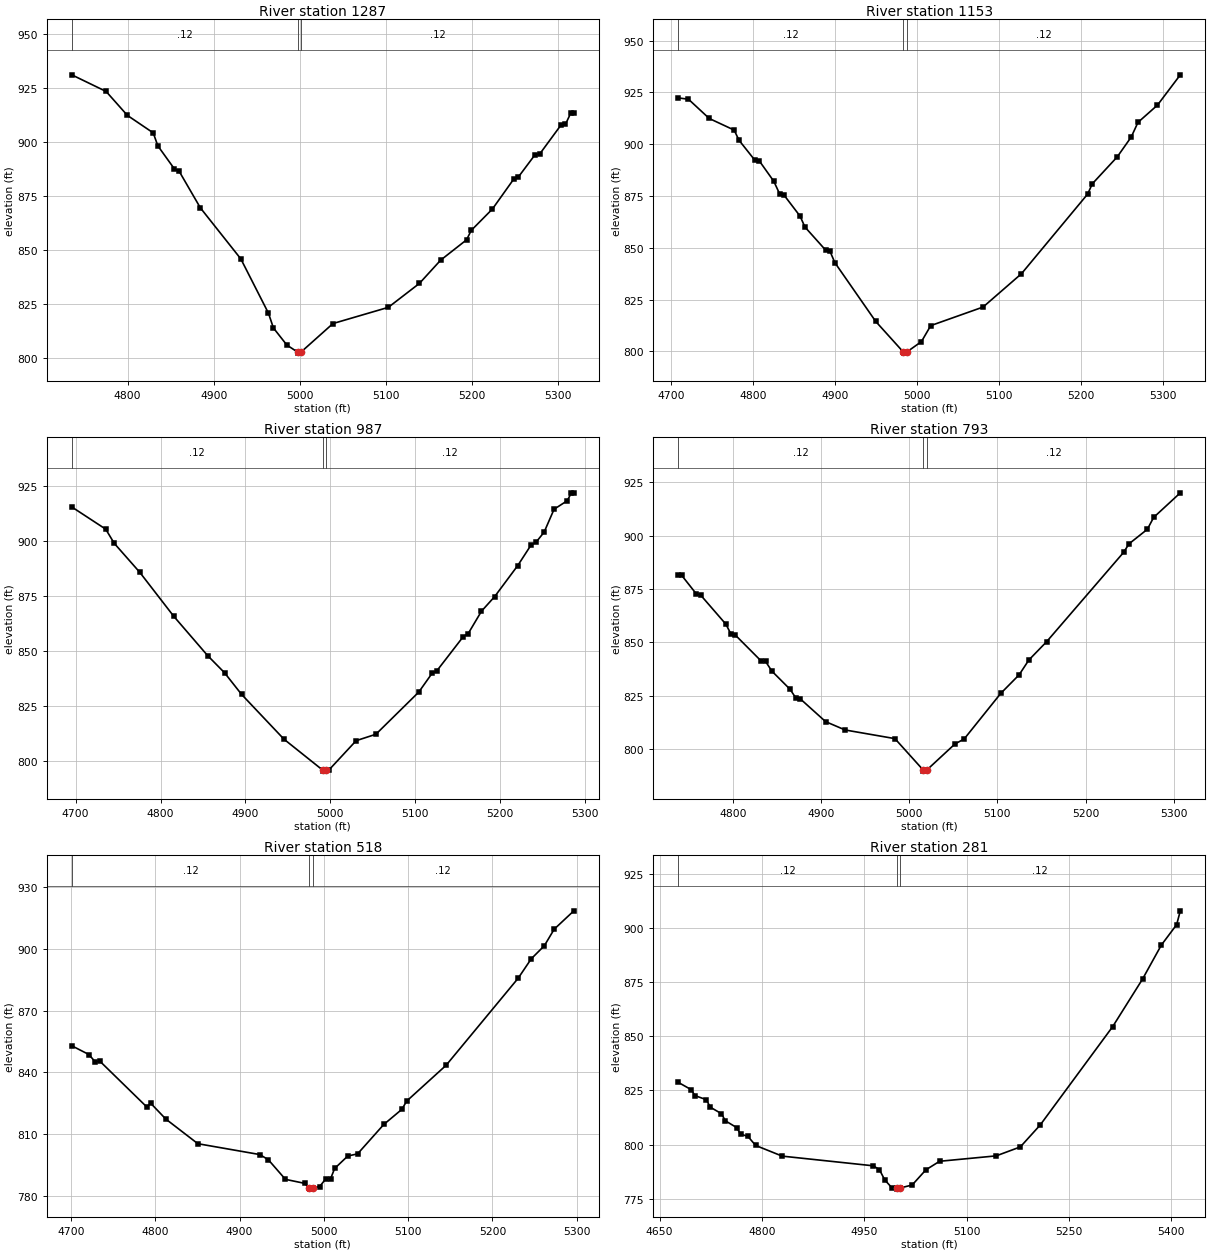
Type RM Length L Ch R = 1,1287,134,134,134
BEGIN DESCRIPTION:
XS7869
END DESCRIPTION:
XS GIS Cut Line= 2
      2225961.59     13838503.79      2226506.31     13838295.45
#Sta/Elev= 30
  4735.1  931.10  4775.0  923.39  4799.7  912.30  4829.7  904.20  4835.1  898.17
  4854.4  887.44  4859.8  886.43  4884.5  869.43  4931.5  845.77  4963.6  820.60
  4969.3  813.79  4985.0  805.83  4997.4  802.61  4997.6  802.11  5001.4  802.61
  5038.5  815.82  5102.8  823.33  5138.9  834.42  5163.6  845.21  5193.7  854.63
  5199.1  858.99  5223.7  868.90  5248.5  882.79  5253.8  883.72  5273.2  894.06
  5278.5  894.32  5303.2  907.73  5308.6  908.21  5314.9  913.51  5318.3  913.51
#Mann=3,-1,0
  4735.1    0.12       0  4997.4    0.05       0  5001.4    0.12       0
Bank Sta=4997.4,5001.4
Exp/Cntr=0.3,0.1

Type RM Length L Ch R = 1,1153,166,166,166
BEGIN DESCRIPTION:
H21504
END DESCRIPTION:
XS GIS Cut Line= 2
      2225995.34     13838623.24      2226571.25     13838413.23
#Sta/Elev= 30
  4708.5  922.33  4721.0  921.68  4746.3  912.41  4776.8  906.79  4782.6  901.95
  4802.1  892.23  4807.4  891.97  4825.2  882.07  4832.6  875.75  4838.0  875.25
  4857.2  865.30  4863.2  860.01  4888.4  848.89  4893.8  848.29  4899.7  842.84
  4949.6  814.46  4983.4  799.66  4983.7  799.16  4987.4  799.66  5005.4  804.71
  5016.8  812.44  5080.7  821.40  5127.6  837.50  5208.4  875.93  5214.0  880.85
  5244.5  893.87  5261.6  903.47  5269.8  910.51  5293.6  918.84  5321.5  933.46
#Mann=3,-1,0
  4708.5    0.12       0  4983.4    0.05       0  4987.4    0.12       0
Bank Sta=4983.4,4987.4
Exp/Cntr=0.3,0.1

Type RM Length L Ch R = 1,987,194,194,194
BEGIN DESCRIPTION:
Turkey Creek 1 2.0
END DESCRIPTION:
XS GIS Cut Line= 3
      2226025.03     13838675.00      2226325.00     13838675.00
      2226574.98     13838525.01
#Sta/Elev= 30
  4695.4  915.61  4735.4  905.48  4745.4  899.04  4775.4  885.86  4815.4  865.83
  4855.4  847.86  4875.4  840.00  4895.4  830.17  4945.4  809.72  4990.9  795.66
  4991.1  795.16  4994.9  795.66  4998.3  795.66  5030.4  809.04  5053.7  811.97
  5104.2  831.20  5119.8  839.72  5125.6  840.95  5156.7  856.52  5162.5  857.91
  5178.1  868.09  5193.6  874.73  5220.8  888.88  5236.4  898.20  5242.2  899.46
  5251.9  904.13  5263.6  914.57  5279.1  918.44  5284.0  922.05  5286.9  922.05
#Mann=3,-1,0
  4695.4    0.12       0  4990.9    0.05       0  4994.9    0.12       0
Bank Sta=4990.9,4994.9
Exp/Cntr=0.3,0.1

Type RM Length L Ch R = 1,793,275,275,275
BEGIN DESCRIPTION:
H21503
END DESCRIPTION:
XS GIS Cut Line= 2
      2226142.88     13838916.23      2226691.00     13838762.40
#Sta/Elev= 30
  4738.1  881.47  4741.8  881.47  4758.5  872.72  4763.7  872.02  4792.2  858.43
  4797.8  853.89  4803.0  853.30  4831.9  841.30  4837.1  841.03  4844.2  836.50
  4864.9  827.94  4871.2  824.02  4876.3  823.53  4905.2  812.78  4927.3  808.87
  4983.8  804.81  5015.9  790.07  5016.1  789.57  5019.9  790.07  5051.9  802.32
  5062.3  804.63  5103.8  826.02  5124.6  834.71  5135.7  841.69  5155.8  850.25
  5243.2  892.19  5249.2  896.13  5270.0  902.96  5277.2  908.54  5307.4  920.06
#Mann=3,-1,0
  4738.1    0.12       0  5015.9    0.05       0  5019.9    0.12       0
Bank Sta=5015.9,5019.9
Exp/Cntr=0.3,0.1

Type RM Length L Ch R = 1,518,237,237,237
BEGIN DESCRIPTION:
Turkey Creek 1 1.0
END DESCRIPTION:
XS GIS Cut Line= 3
      2226224.98     13839025.00      2226525.00     13839075.00
      2226775.00     13838925.00
#Sta/Elev= 30
  4700.9  852.88  4721.2  848.63  4728.8  845.01  4733.9  845.52  4789.6  823.23
  4794.7  824.85  4812.4  817.25  4850.5  805.23  4924.0  799.95  4934.1  797.44
  4954.4  787.89  4977.2  785.94  4982.8  783.63  4983.0  783.13  4986.8  783.63
  4994.9  784.37  5002.5  788.22  5008.0  788.22  5012.8  793.18  5028.4  799.25
  5040.0  800.28  5071.1  814.59  5092.5  821.93  5098.3  825.98  5145.0  843.37
  5230.5  885.73  5246.1  895.21  5261.6  901.56  5273.3  909.61  5296.6  918.54
#Mann=3,-1,0
  4700.9    0.12       0  4982.8    0.05       0  4986.8    0.12       0
Bank Sta=4982.8,4986.8
Exp/Cntr=0.3,0.1

Type RM Length L Ch R = 1,281,240,240,240
BEGIN DESCRIPTION:
H21502
END DESCRIPTION:
XS GIS Cut Line= 4
      2226234.02     13839180.98      2226494.44     13839313.36
      2226635.50     13839300.34      2226877.26     13839119.02
#Sta/Elev= 30
  4677.2  828.75  4696.1  825.40  4701.7  822.62  4718.4  820.75  4724.0  817.32
  4740.6  814.27  4746.2  811.01  4762.9  807.85  4768.5  804.86  4779.3  803.80
  4790.7  799.61  4829.6  794.68  4963.1  790.21  4972.1  788.44  4979.9  783.72
  4990.0  780.19  4998.0  779.94  4998.3  779.44  5002.0  779.94  5020.1  781.34
  5040.2  788.34  5060.3  792.30  5143.3  794.80  5178.7  798.94  5207.8  809.05
  5314.1  854.51  5357.8  876.43  5385.4  892.15  5407.8  901.57  5413.2  907.96
#Mann=3,-1,0
  4677.2    0.12       0  4998.0    0.05       0  5002.0    0.12       0
Bank Sta=4998,5002
Exp/Cntr=0.3,0.1

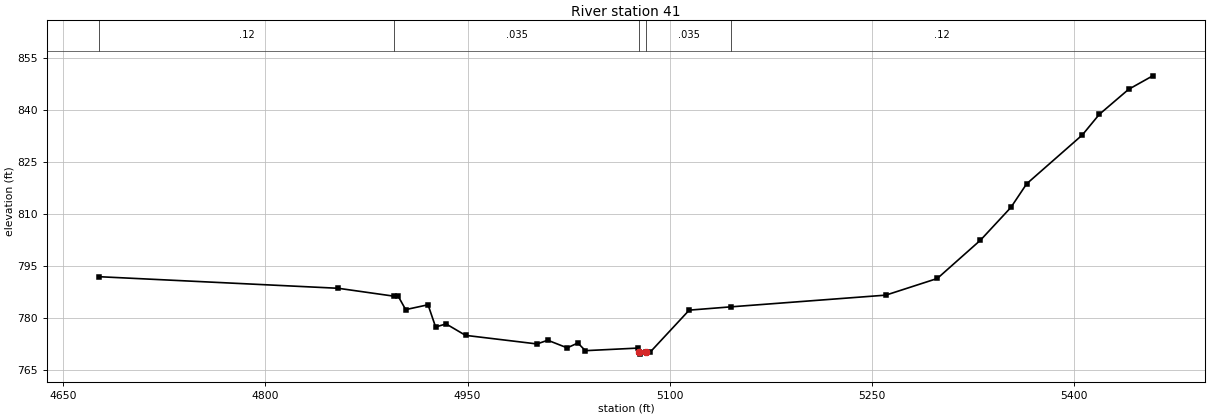
Type RM Length L Ch R = 1,41,0,0,0
BEGIN DESCRIPTION:
XS7868
END DESCRIPTION:
XS GIS Cut Line= 4
      2226286.15     13839387.17      2226535.67     13839515.18
      2226646.35     13839571.61      2226991.40     13839420.65
#Sta/Elev= 30
  4676.9  791.83  4854.1  788.49  4895.6  786.20  4898.5  786.24  4904.1  782.33
  4920.7  783.73  4926.3  777.32  4934.1  778.20  4948.5  774.90  5001.5  772.42
  5009.5  773.49  5023.9  771.29  5031.8  772.69  5037.4  770.48  5076.2  771.22
  5077.4  769.98  5077.8  769.48  5082.2  769.98  5085.6  770.12  5114.4  782.18
  5145.6  783.14  5260.2  786.51  5298.4  791.32  5330.4  802.37  5353.0  811.84
  5364.7  818.66  5406.0  832.77  5418.5  838.68  5440.3  845.93  5458.2  849.83
#Mann=5,-1,0
  4676.9    0.12       0  4895.6   0.035       0  5077.4   0.035       0
  5082.2   0.035       0  5145.6    0.12       0
Bank Sta=5077.4,5082.2
Exp/Cntr=0.3,0.1

Chan Stop Cuts=-1