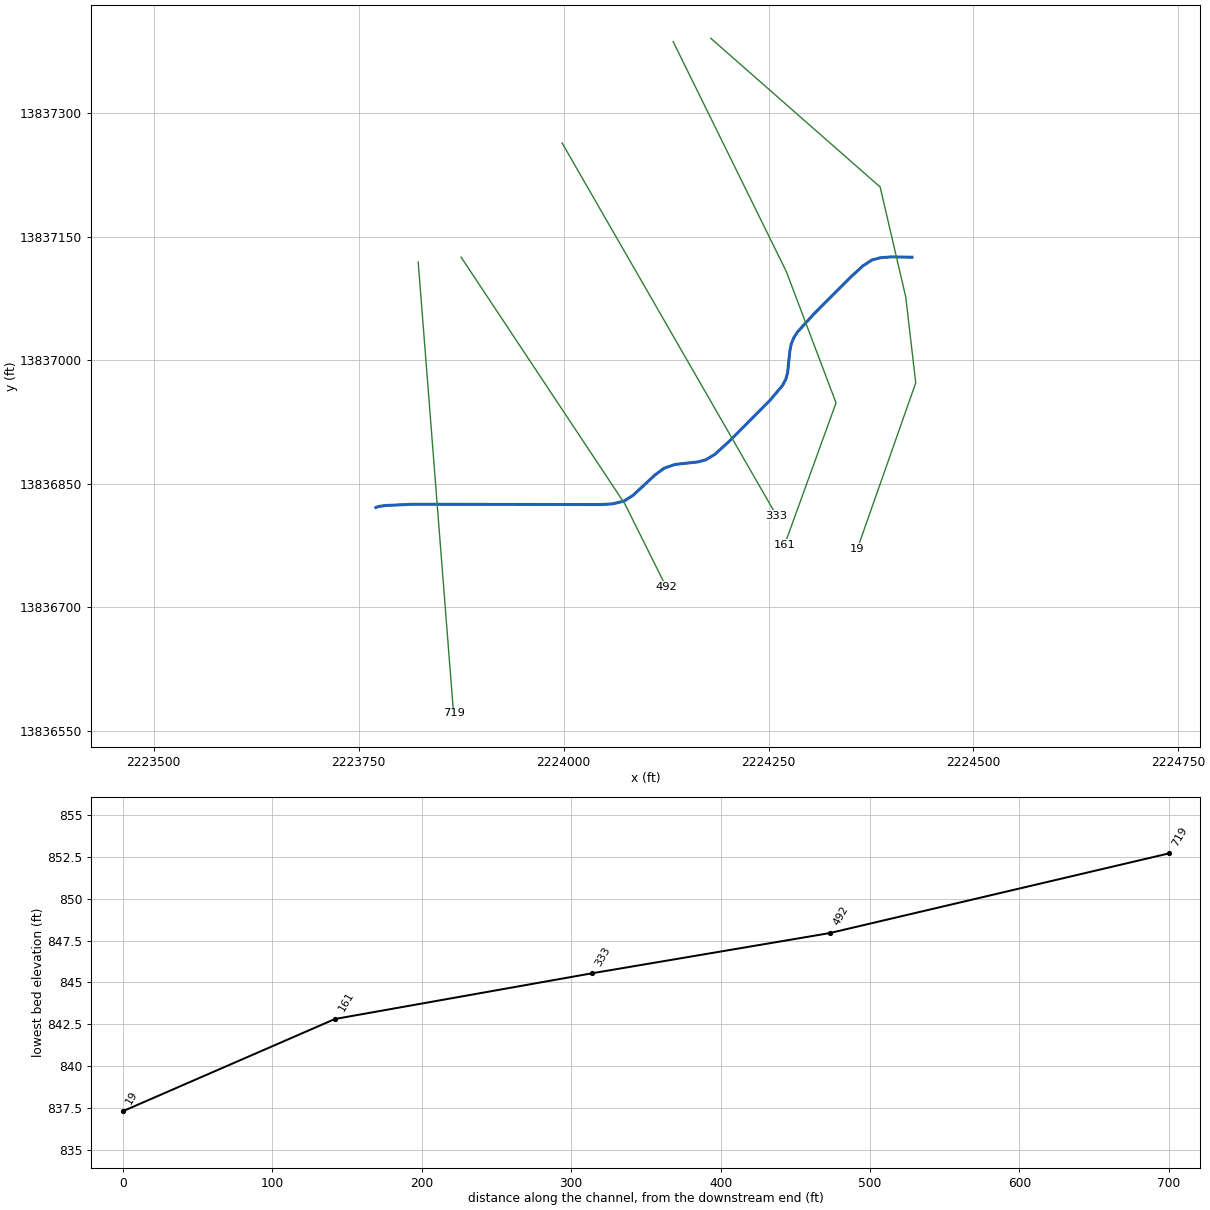
--- Turkey Creek 2.prj (project) ---

Proj Title=Turkey Creek 2 Base Level Engineering
Current Plan=p01
Default Exp/Contr=0.3,0.1
English Units
Geom File=g01
Flow File=f01
Plan File=p01
BEGIN DESCRIPTION:
Turkey Creek 2
END DESCRIPTION:

--- Turkey Creek 2.p01 (plan) ---

Plan Title=Multiple Run
Short Identifier=Multiple
Geom File=g01
Flow File=f01
Subcritical Flow
K Sum by GR= 0
Std Step Tol= 0.01
Critical Tol= 0.01
Num of Std Step Trials= 20
Max Error Tol= 0.3
Flow Tol Ratio= 0.001
Split Flow NTrial= 30
Split Flow Tol= 0.02
Split Flow Ratio= 0.02
Log Output Level= 0
Friction Slope Method= 1
Unsteady Friction Slope Method= 2
Unsteady Bridges Friction Slope Method= 1
Parabolic Critical Depth
Global Vel Dist=  1 , 1 , 1
Global Log Level= 0
CheckData=True
Encroach Param= -1, 0, 0, 0
BEGIN DESCRIPTION:
Multiple Run
END DESCRIPTION:

--- Turkey Creek 2.f01 (steady flow) ---

Flow Title=Multiple
Number of Profiles=7
Profile Names=10-year,25-year,50-year,1pct_min,100-year,1pct_plu,500-year
River Rch & RM= Turkey Creek 2,Reach-1,719
     851    1429    1976    1328    2650    5288    4707
River Rch & RM= Turkey Creek 2,Reach-1,19
    1374    2360    3313    2253    4496    8971    8188
Boundary for River Rch & Prof#=Turkey Creek 2,Reach-1,1
Up Type=0
Dn Type=3
Dn Slope=0.005
Boundary for River Rch & Prof#=Turkey Creek 2,Reach-1,2
Up Type=0
Dn Type=3
Dn Slope=0.005
Boundary for River Rch & Prof#=Turkey Creek 2,Reach-1,3
Up Type=0
Dn Type=3
Dn Slope=0.005
Boundary for River Rch & Prof#=Turkey Creek 2,Reach-1,4
Up Type=0
Dn Type=3
Dn Slope=0.005
Boundary for River Rch & Prof#=Turkey Creek 2,Reach-1,5
Up Type=0
Dn Type=3
Dn Slope=0.005
Boundary for River Rch & Prof#=Turkey Creek 2,Reach-1,6
Up Type=0
Dn Type=3
Dn Slope=0.005
Boundary for River Rch & Prof#=Turkey Creek 2,Reach-1,7
Up Type=0
Dn Type=3
Dn Slope=0.005

--- Turkey Creek 2.g01 (geometry) ---

Geom Title=Existing Conditions

River Reach=Turkey Creek 2,Reach-1
Reach XY= 30
      2223771.06     13836821.06      2223774.52     13836822.36
      2223783.48     13836823.53      2223814.65     13836824.97
      2224045.15     13836824.64      2224059.79     13836825.51
      2224073.45     13836828.75      2224084.67     13836835.79
      2224111.97     13836860.95      2224122.83     13836868.86
      2224135.71     13836873.28      2224164.39     13836876.50
      2224173.38     13836878.94      2224184.71     13836885.75
      2224201.88     13836901.27      2224252.01     13836951.49
      2224266.85     13836968.93      2224271.03     13836976.64
      2224273.30     13836984.79      2224276.03     13837010.94
      2224277.64     13837019.37      2224280.84     13837027.30
      2224285.76     13837034.70      2224304.57     13837055.22
      2224351.48     13837101.98      2224365.18     13837114.50
      2224376.34     13837121.73      2224386.83     13837124.41
      2224399.63     13837125.41      2224425.00     13837125.00

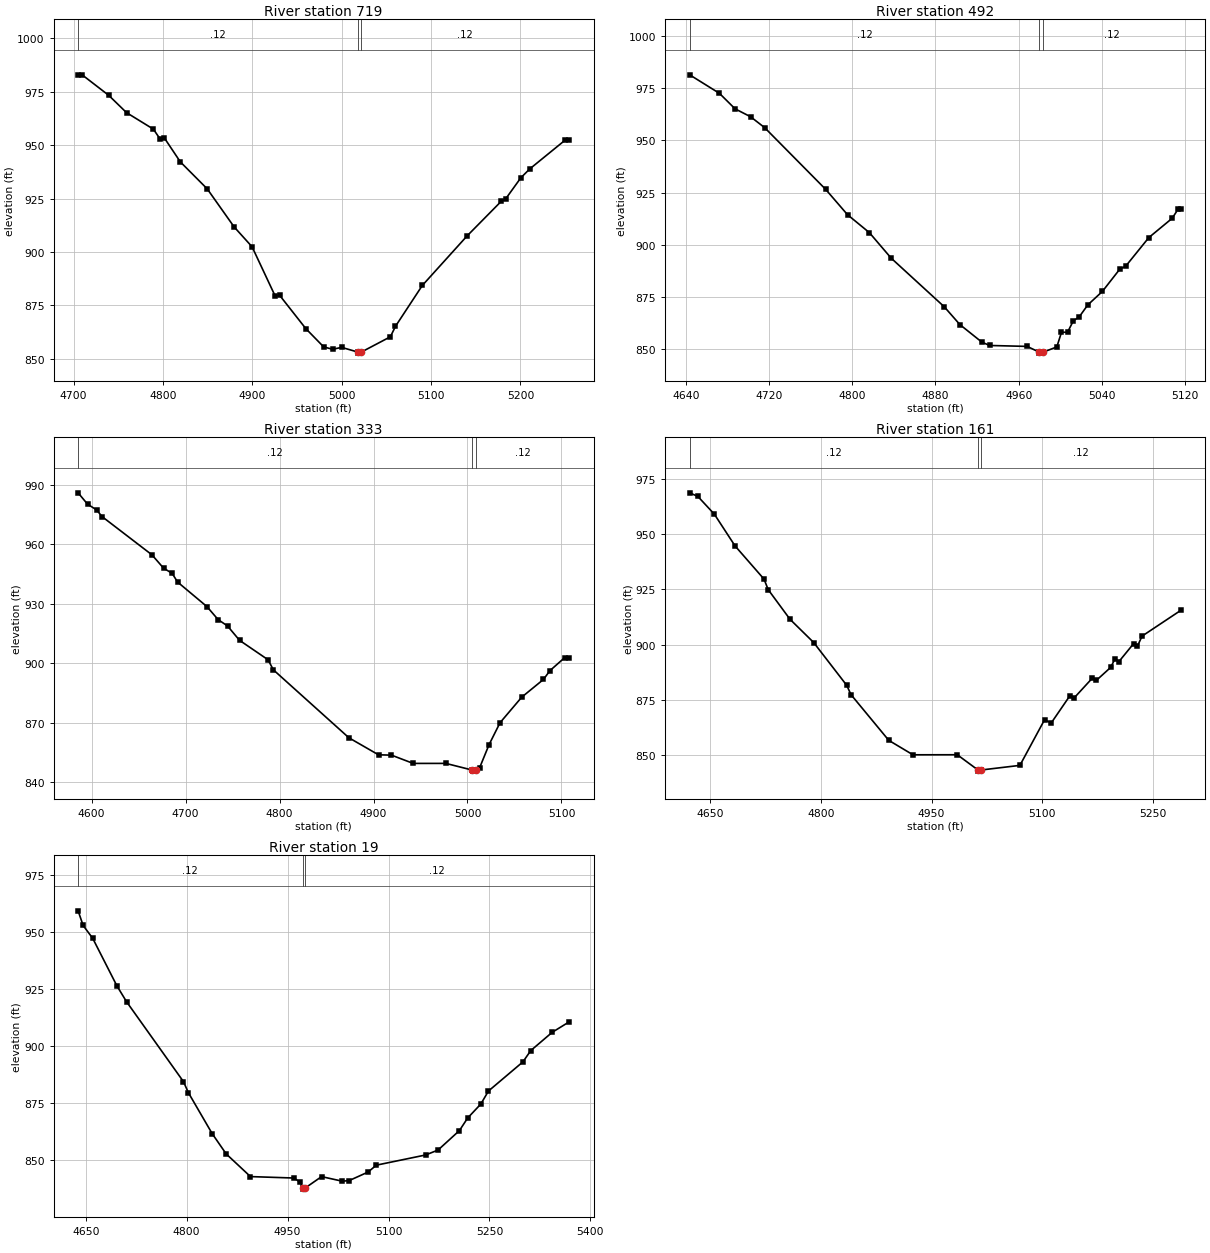
Type RM Length L Ch R = 1,719,227,227,227
BEGIN DESCRIPTION:
XS7867
END DESCRIPTION:
XS GIS Cut Line= 2
      2223822.65     13837119.06      2223865.75     13836571.06
#Sta/Elev= 30
  4705.0  982.91  4709.5  982.91  4739.2  973.34  4759.2  965.22  4789.3  957.48
  4796.5  953.04  4801.6  953.34  4819.4  942.19  4849.5  929.56  4879.6  911.77
  4899.7  902.46  4925.5  879.46  4930.5  879.79  4959.8  864.20  4979.9  855.60
  4989.9  854.52  5000.0  855.40  5018.0  853.21  5018.3  852.71  5022.0  853.21
  5054.5  860.36  5060.2  865.25  5090.2  884.35  5140.4  907.57  5178.4  923.67
  5183.4  924.80  5200.6  934.79  5210.6  938.93  5250.2  952.40  5254.7  952.40
#Mann=3,-1,0
  4705.0    0.12       0  5018.0    0.05       0  5022.0    0.12       0
Bank Sta=5018,5022
Exp/Cntr=0.3,0.1

Type RM Length L Ch R = 1,492,159,159,159
BEGIN DESCRIPTION:
Turkey Creek 2 1.0
END DESCRIPTION:
XS GIS Cut Line= 3
      2223874.98     13837125.03      2224075.00     13836825.00
      2224125.00     13836724.99
#Sta/Elev= 30
  4643.6  981.50  4672.2  972.62  4687.2  965.20  4702.2  961.37  4715.7  956.15
  4774.3  926.58  4795.4  914.37  4816.4  905.78  4837.4  893.52  4888.5  870.16
  4903.5  861.63  4924.6  853.23  4932.1  851.62  4968.1  851.18  4979.7  848.45
  4979.9  847.95  4983.7  848.45  4996.7  850.92  5001.2  857.97  5007.0  857.97
  5012.6  863.46  5018.2  865.32  5026.5  871.09  5040.5  877.55  5057.3  888.27
  5062.9  889.64  5085.2  903.40  5107.6  912.63  5113.2  916.91  5116.0  916.91
#Mann=3,-1,0
  4643.6    0.12       0  4979.7    0.05       0  4983.7    0.12       0
Bank Sta=4979.7,4983.7
Exp/Cntr=0.3,0.1

Type RM Length L Ch R = 1,333,172,172,172
BEGIN DESCRIPTION:
XS7866
END DESCRIPTION:
XS GIS Cut Line= 2
      2223998.16     13837263.72      2224259.81     13836811.22
#Sta/Elev= 30
  4585.6  985.88  4595.7  980.14  4605.3  977.26  4611.1  973.89  4664.2  954.61
  4676.5  947.92  4685.7  945.26  4691.5  940.88  4722.7  928.52  4734.6  921.95
  4744.6  918.76  4757.4  911.51  4787.7  901.72  4793.4  896.63  4873.8  862.36
  4905.3  853.78  4919.1  853.61  4942.2  849.44  4976.9  849.45  5005.3  846.05
  5005.5  845.55  5009.3  846.05  5013.0  847.37  5023.0  858.96  5034.6  869.94
  5057.7  882.84  5080.8  891.77  5087.7  896.20  5103.3  902.74  5108.3  902.74
#Mann=3,-1,0
  4585.6    0.12       0  5005.3    0.05       0  5009.3    0.12       0
Bank Sta=5005.3,5009.3
Exp/Cntr=0.3,0.1

Type RM Length L Ch R = 1,161,142,142,142
BEGIN DESCRIPTION:
XS7865
END DESCRIPTION:
XS GIS Cut Line= 4
      2224133.60     13837386.92      2224271.64     13837107.83
      2224332.40     13836948.11      2224269.55     13836775.55
#Sta/Elev= 30
  4622.1  968.60  4633.2  966.96  4655.6  958.92  4683.6  944.60  4722.9  929.59
  4728.5  924.86  4758.1  911.45  4790.2  900.95  4835.1  881.55  4840.7  877.43
  4892.0  856.73  4924.8  850.20  4984.9  850.22  5013.0  843.32  5013.2  842.82
  5017.0  843.32  5069.8  845.42  5103.3  866.09  5112.2  864.55  5137.4  876.81
  5142.8  875.71  5168.0  884.86  5173.3  883.79  5192.8  889.69  5198.6  893.51
  5203.9  892.27  5223.8  900.39  5229.1  899.27  5235.4  903.84  5288.0  915.50
#Mann=3,-1,0
  4622.1    0.12       0  5013.0    0.05       0  5017.0    0.12       0
Bank Sta=5013,5017
Exp/Cntr=0.3,0.1

Type RM Length L Ch R = 1,19,0,0,0
BEGIN DESCRIPTION:
H21505
END DESCRIPTION:
XS GIS Cut Line= 5
      2224179.64     13837390.80      2224386.22     13837210.26
      2224417.47     13837076.58      2224429.63     13836972.41
      2224358.45     13836771.03
#Sta/Elev= 30
  4638.6  959.19  4646.1  952.77  4660.3  947.16  4696.4  926.27  4710.6  919.39
  4795.1  884.43  4802.7  879.46  4837.8  861.66  4858.7  852.74  4894.8  842.80
  4959.4  842.17  4969.0  840.28  4972.2  837.81  4972.4  837.31  4976.2  837.81
  5000.5  842.79  5031.3  840.78  5041.6  841.06  5069.5  844.77  5082.0  847.81
  5155.1  852.26  5173.6  854.42  5205.4  862.94  5217.7  868.47  5237.2  874.56
  5248.6  880.28  5299.8  893.04  5311.5  897.99  5343.3  905.98  5368.7  910.59
#Mann=3,-1,0
  4638.6    0.12       0  4972.2    0.05       0  4976.2    0.12       0
Bank Sta=4972.2,4976.2
Exp/Cntr=0.3,0.1

Chan Stop Cuts=-1