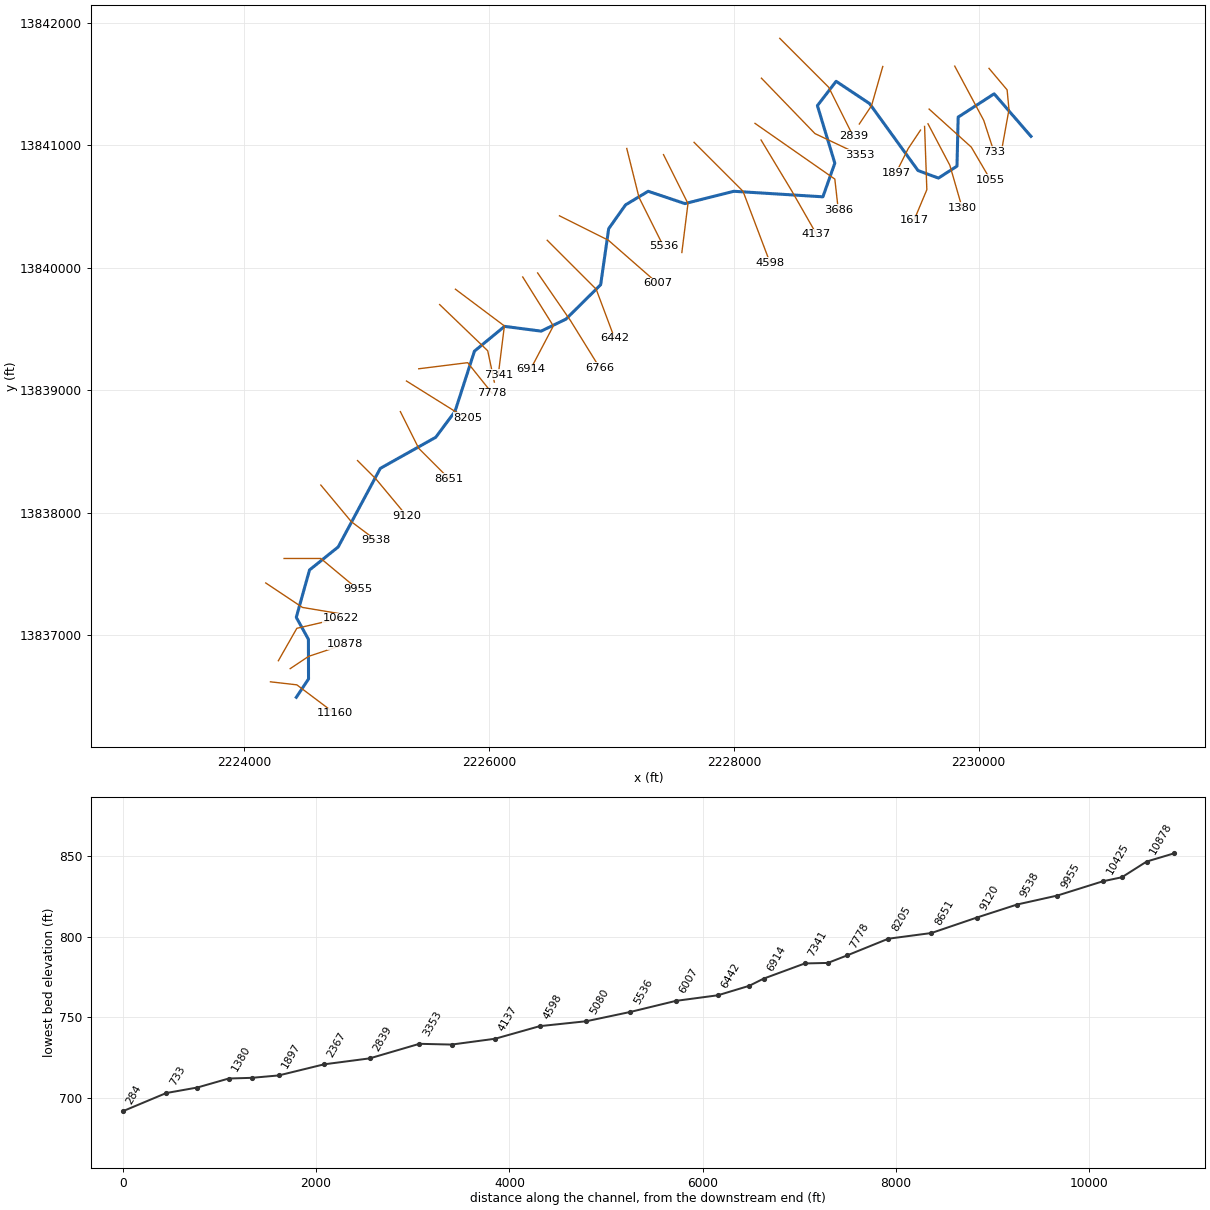
--- Turkey Creek.prj (project) ---

Proj Title=Turkey Creek Base Level Engineering
Current Plan=p01
Default Exp/Contr=0.3,0.1
English Units
Geom File=g01
Flow File=f01
Plan File=p01
BEGIN DESCRIPTION:
Turkey Creek
END DESCRIPTION:

--- Turkey Creek.p01 (plan) ---

Plan Title=Multiple Run
Short Identifier=Multiple
Geom File=g01
Flow File=f01
Subcritical Flow
K Sum by GR= 0
Std Step Tol= 0.01
Critical Tol= 0.01
Num of Std Step Trials= 20
Max Error Tol= 0.3
Flow Tol Ratio= 0.001
Split Flow NTrial= 30
Split Flow Tol= 0.02
Split Flow Ratio= 0.02
Log Output Level= 0
Friction Slope Method= 1
Unsteady Friction Slope Method= 2
Unsteady Bridges Friction Slope Method= 1
Parabolic Critical Depth
Global Vel Dist=  1 , 1 , 1
Global Log Level= 0
CheckData=True
Encroach Param= -1, 0, 0, 0
BEGIN DESCRIPTION:
Multiple Run
END DESCRIPTION:

--- Turkey Creek.f01 (steady flow) ---

Flow Title=Multiple
Number of Profiles=7
Profile Names=10-year,25-year,50-year,1pct_min,100-year,1pct_plu,500-year
River Rch & RM= Turkey Creek,Reach-1,11160
     710    1185    1632    1095    2185    4360    3862
River Rch & RM= Turkey Creek,Reach-1,10425
    1374    2360    3313    2253    4496    8971    8188
River Rch & RM= Turkey Creek,Reach-1,6766
    1818    3150    4443    3031    6048   12068   11093
Boundary for River Rch & Prof#=Turkey Creek,Reach-1,1
Up Type=0
Dn Type=3
Dn Slope=0.005
Boundary for River Rch & Prof#=Turkey Creek,Reach-1,2
Up Type=0
Dn Type=3
Dn Slope=0.005
Boundary for River Rch & Prof#=Turkey Creek,Reach-1,3
Up Type=0
Dn Type=3
Dn Slope=0.005
Boundary for River Rch & Prof#=Turkey Creek,Reach-1,4
Up Type=0
Dn Type=3
Dn Slope=0.005
Boundary for River Rch & Prof#=Turkey Creek,Reach-1,5
Up Type=0
Dn Type=3
Dn Slope=0.005
Boundary for River Rch & Prof#=Turkey Creek,Reach-1,6
Up Type=0
Dn Type=3
Dn Slope=0.005
Boundary for River Rch & Prof#=Turkey Creek,Reach-1,7
Up Type=0
Dn Type=3
Dn Slope=0.005

--- Turkey Creek.g01 (geometry) ---

Geom Title=Existing Conditions

River Reach=Turkey Creek,Reach-1
Reach XY= 30
      2224425.00     13836490.98      2224524.62     13836640.16
      2224523.81     13836964.51      2224424.59     13837143.92
      2224532.87     13837531.14      2224766.87     13837718.93
      2225110.96     13838360.99      2225564.23     13838615.30
      2225721.46     13838826.47      2225880.59     13839319.39
      2226126.46     13839521.46      2226425.01     13839482.51
      2226627.52     13839580.31      2226911.63     13839861.68
      2226977.18     13840319.55      2227115.00     13840514.35
      2227299.88     13840625.29      2227599.88     13840524.71
      2227999.93     13840625.23      2228727.55     13840579.99
      2228824.95     13840854.96      2228682.56     13841325.00
      2228835.53     13841523.93      2229108.50     13841342.05
      2229504.80     13840794.61      2229671.71     13840733.05
      2229823.02     13840830.67      2229832.80     13841231.21
      2230126.80     13841421.69      2230427.64     13841074.02

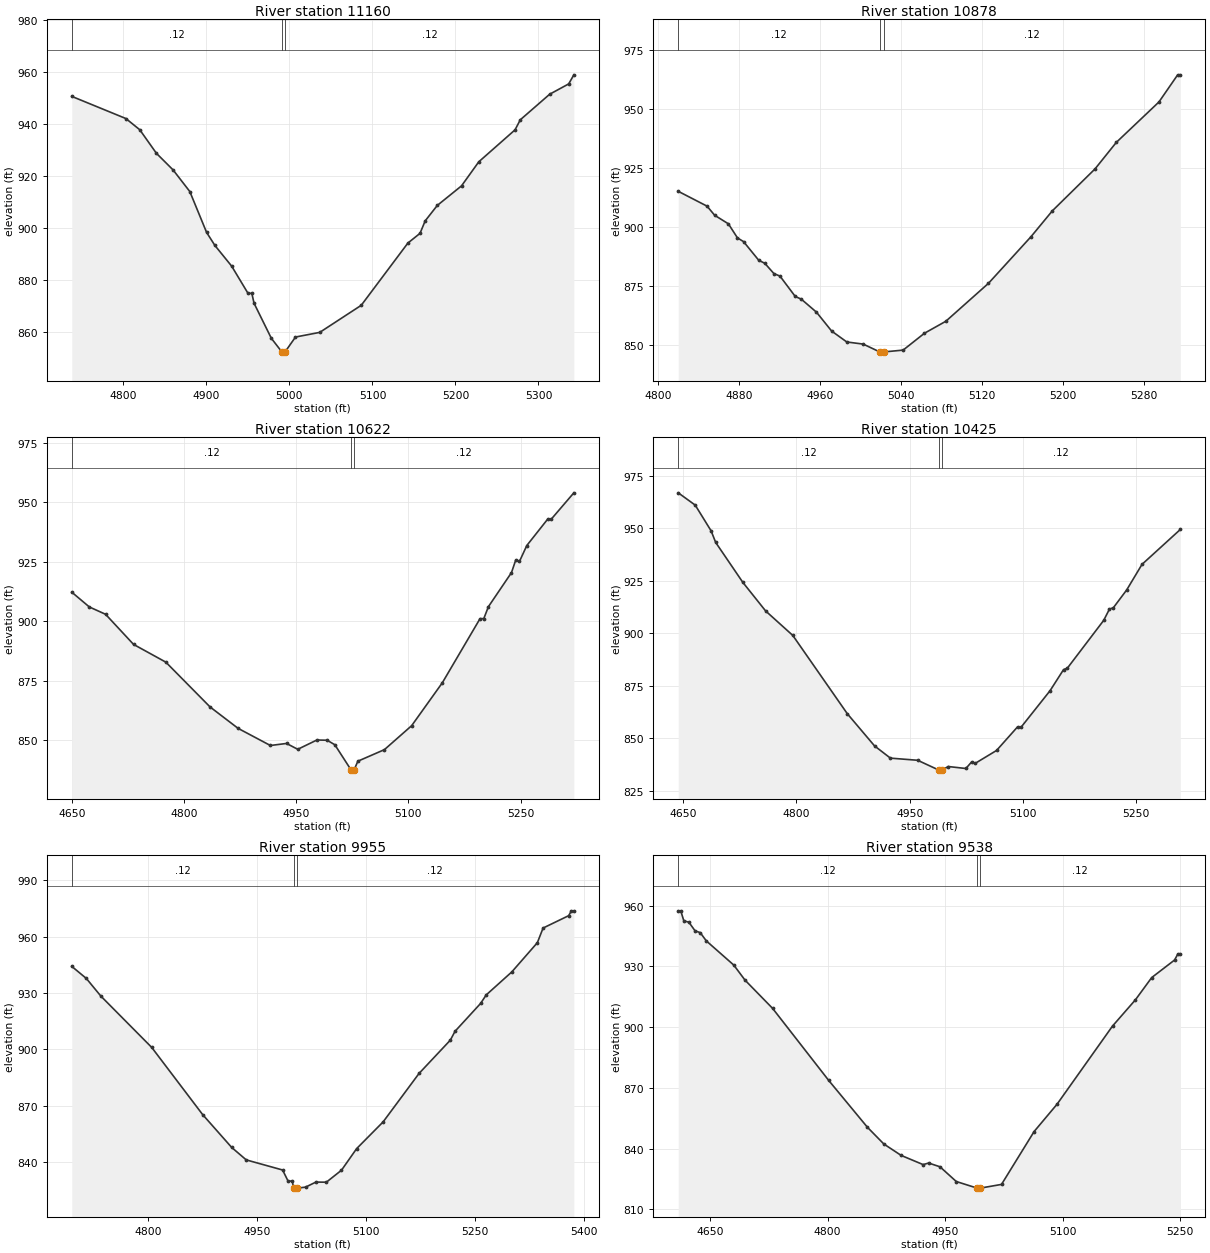
Type RM Length L Ch R = 1,11160,282,282,282
BEGIN DESCRIPTION:
XS7864
END DESCRIPTION:
XS GIS Cut Line= 3
      2224213.68     13836617.22      2224429.16     13836592.59
      2224739.12     13836359.35
#Sta/Elev= 30
  4737.8  950.62  4803.0  942.08  4819.7  937.77  4839.8  928.68  4859.9  922.27
  4880.0  913.96  4900.2  898.23  4910.2  893.20  4930.4  885.23  4950.1  874.75
  4954.7  874.75  4957.4  870.92  4978.2  857.43  4990.8  852.22  4991.0  851.72
  4994.8  852.22  5007.3  857.92  5036.5  859.71  5086.5  870.14  5142.7  894.12
  5157.3  897.86  5163.5  902.65  5178.1  908.61  5207.3  916.15  5228.1  925.42
  5271.8  937.74  5278.1  941.60  5313.5  951.45  5336.4  955.42  5342.6  958.92
#Mann=3,-1,0
  4737.8    0.12       0  4990.8    0.05       0  4994.8    0.12       0
Bank Sta=4990.8,4994.8
Exp/Cntr=0.3,0.1

Type RM Length L Ch R = 1,10878,256,256,256
BEGIN DESCRIPTION:
Turkey Creek 24.0
END DESCRIPTION:
XS GIS Cut Line= 3
      2224375.01     13836725.01      2224525.00     13836825.00
      2224825.01     13836925.00
#Sta/Elev= 30
  4819.7  915.07  4848.2  908.79  4855.7  904.95  4869.3  901.32  4878.3  895.36
  4884.3  893.80  4899.3  885.92  4905.3  884.64  4914.3  880.30  4920.3  879.23
  4935.4  870.63  4941.4  869.48  4956.4  863.98  4971.4  856.00  4986.4  851.38
  5002.6  850.49  5019.0  847.17  5019.3  846.67  5023.0  847.17  5042.1  847.95
  5063.2  855.08  5084.3  860.13  5126.5  876.18  5168.6  895.91  5189.7  906.83
  5231.9  924.55  5252.9  935.74  5295.1  952.84  5313.6  964.30  5316.2  964.30
#Mann=3,-1,0
  4819.7    0.12       0  5019.0    0.05       0  5023.0    0.12       0
Bank Sta=5019,5023
Exp/Cntr=0.3,0.1

Type RM Length L Ch R = 1,10622,197,197,197
BEGIN DESCRIPTION:
XS7863
END DESCRIPTION:
XS GIS Cut Line= 3
      2224278.30     13836789.62      2224429.16     13837054.40
      2224786.27     13837137.53
#Sta/Elev= 30
  4649.9  912.19  4673.4  905.97  4695.1  902.89  4732.5  890.23  4775.7  882.76
  4834.8  863.93  4872.3  854.92  4915.5  847.71  4937.1  848.57  4952.1  846.11
  4977.7  850.02  4991.4  849.92  5001.7  848.02  5023.4  837.43  5023.7  836.93
  5027.4  837.43  5032.5  841.11  5068.0  845.97  5104.4  856.04  5145.4  874.07
  5195.8  901.03  5200.9  901.09  5207.1  906.11  5237.9  920.41  5243.5  925.61
  5248.6  925.13  5258.4  931.81  5286.1  942.82  5291.2  942.93  5321.3  953.97
#Mann=3,-1,0
  4649.9    0.12       0  5023.4    0.05       0  5027.4    0.12       0
Bank Sta=5023.4,5027.4
Exp/Cntr=0.3,0.1

Type RM Length L Ch R = 1,10425,470,470,470
BEGIN DESCRIPTION:
Turkey Creek 23.0
END DESCRIPTION:
XS GIS Cut Line= 3
      2224175.02     13837424.99      2224475.00     13837225.00
      2224775.03     13837175.00
#Sta/Elev= 30
  4643.5  966.78  4666.0  960.93  4687.0  948.71  4693.1  943.17  4729.1  924.16
  4759.2  910.61  4795.2  898.95  4867.3  861.75  4903.4  846.42  4924.4  840.61
  4960.5  839.59  4988.5  834.93  4988.8  834.43  4992.5  834.93  5001.0  836.62
  5024.3  835.68  5031.9  838.79  5037.0  838.20  5064.9  844.25  5092.7  855.47
  5097.8  855.51  5135.8  872.70  5153.6  882.70  5158.6  883.37  5206.8  906.14
  5214.4  911.50  5219.5  912.11  5237.2  920.59  5257.5  932.76  5308.2  949.35
#Mann=3,-1,0
  4643.5    0.12       0  4988.5    0.05       0  4992.5    0.12       0
Bank Sta=4988.5,4992.5
Exp/Cntr=0.3,0.1

Type RM Length L Ch R = 1,9955,417,417,417
BEGIN DESCRIPTION:
Turkey Creek 22.0
END DESCRIPTION:
XS GIS Cut Line= 3
      2224324.96     13837625.00      2224625.00     13837625.00
      2224925.03     13837374.97
#Sta/Elev= 30
  4694.9  944.19  4714.9  937.77  4734.9  928.37  4804.9  901.03  4874.9  865.29
  4914.9  847.78  4934.9  841.16  4984.9  835.78  4992.4  829.89  4998.2  829.89
  5000.1  826.10  5000.4  825.60  5004.1  826.10  5016.4  826.65  5030.7  829.35
  5045.1  829.29  5065.9  835.67  5086.7  847.15  5123.2  861.41  5172.6  887.20
  5215.6  904.91  5222.1  909.64  5257.2  924.44  5265.0  929.00  5300.2  941.25
  5335.3  956.79  5343.2  964.60  5378.3  971.16  5382.2  973.76  5385.5  973.76
#Mann=3,-1,0
  4694.9    0.12       0  5000.1    0.05       0  5004.1    0.12       0
Bank Sta=5000.1,5004.1
Exp/Cntr=0.3,0.1

Type RM Length L Ch R = 1,9538,418,418,418
BEGIN DESCRIPTION:
Turkey Creek 21.0
END DESCRIPTION:
XS GIS Cut Line= 3
      2224625.02     13838224.98      2224875.00     13837925.00
      2225075.01     13837774.99
#Sta/Elev= 30
  4609.5  957.49  4612.7  957.49  4616.6  952.61  4623.1  951.85  4631.0  947.59
  4637.5  946.74  4645.3  942.65  4680.4  930.68  4694.7  923.26  4729.9  909.30
  4801.5  873.70  4850.9  850.56  4871.8  842.32  4893.9  836.68  4921.9  832.15
  4929.0  832.91  4943.4  831.07  4964.2  823.79  4990.8  820.53  4991.1  820.03
  4994.8  820.53  5021.9  822.36  5063.5  848.48  5092.7  861.94  5163.5  900.57
  5192.7  913.52  5213.5  924.52  5242.7  933.20  5246.9  936.21  5250.0  936.21
#Mann=3,-1,0
  4609.5    0.12       0  4990.8    0.05       0  4994.8    0.12       0
Bank Sta=4990.8,4994.8
Exp/Cntr=0.3,0.1

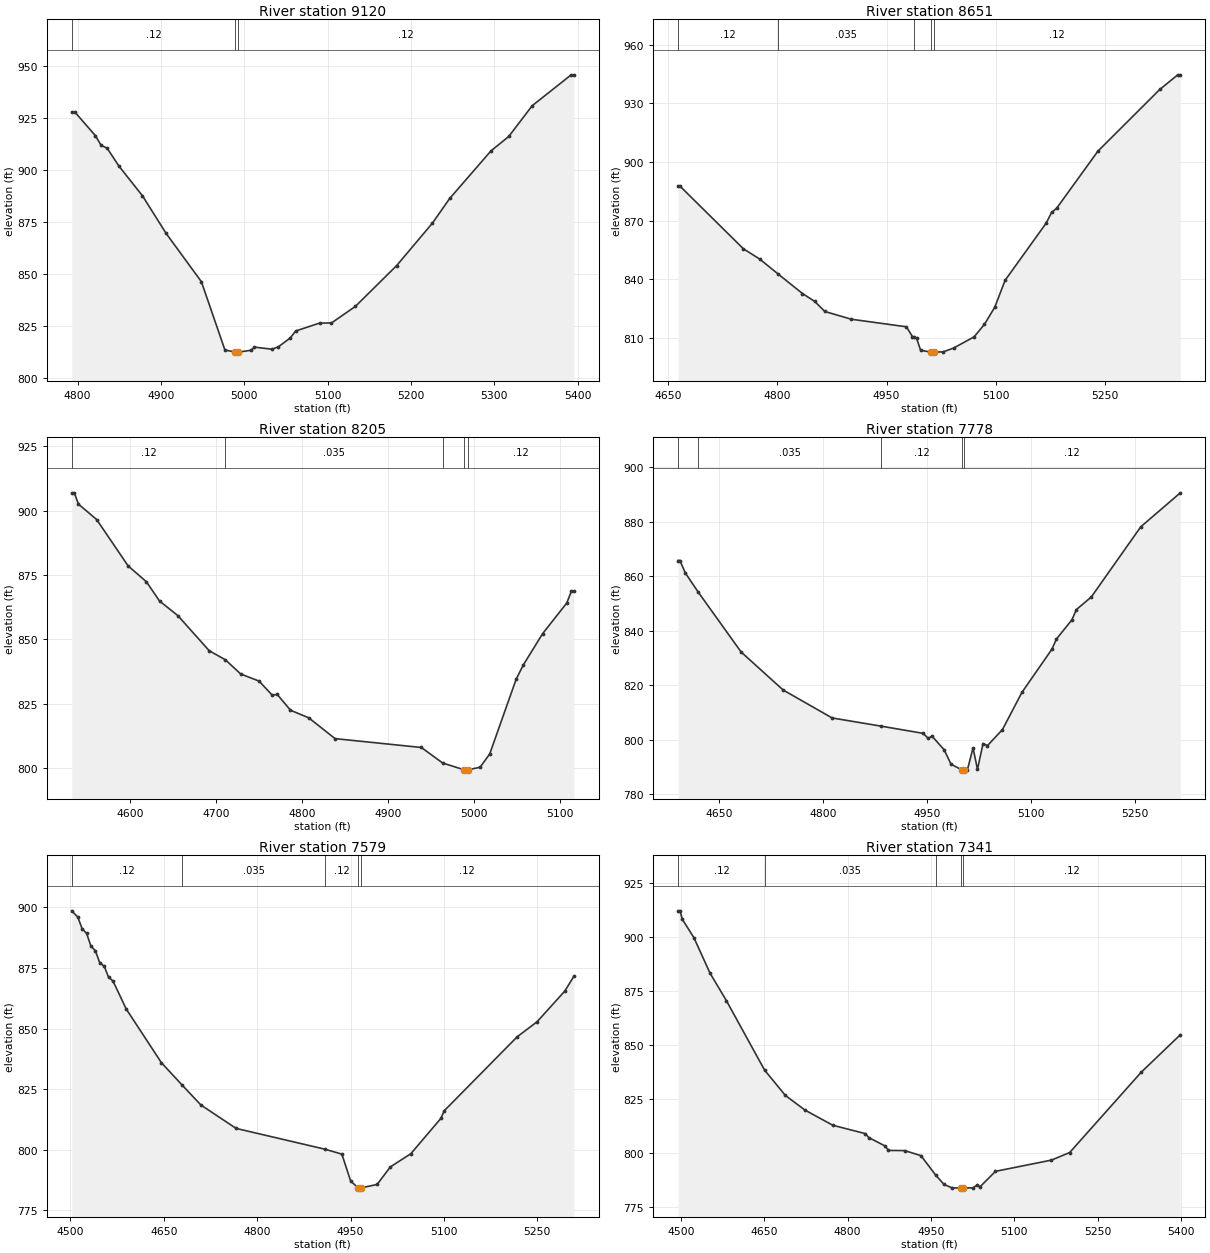
Type RM Length L Ch R = 1,9120,469,469,469
BEGIN DESCRIPTION:
Turkey Creek 20.0
END DESCRIPTION:
XS GIS Cut Line= 3
      2224925.01     13838424.99      2225075.00     13838275.00
      2225324.98     13837975.03
#Sta/Elev= 30
  4792.9  927.99  4796.4  927.99  4821.2  916.57  4828.2  911.86  4835.3  910.56
  4849.5  901.91  4877.7  887.64  4906.0  869.61  4948.5  846.27  4976.7  813.44
  4988.9  812.42  4989.1  811.92  4992.9  812.42  5008.3  813.30  5012.2  814.81
  5033.0  813.81  5040.8  814.94  5055.1  819.22  5061.6  822.56  5090.3  826.38
  5104.6  826.43  5133.2  834.37  5182.7  853.98  5225.7  874.42  5246.5  886.33
  5296.0  909.20  5317.4  916.16  5345.4  930.91  5392.3  945.81  5395.5  945.81
#Mann=3,-1,0
  4792.9    0.12       0  4988.9    0.05       0  4992.9    0.12       0
Bank Sta=4988.9,4992.9
Exp/Cntr=0.3,0.1

Type RM Length L Ch R = 1,8651,446,446,446
BEGIN DESCRIPTION:
Turkey Creek 19.0
END DESCRIPTION:
XS GIS Cut Line= 3
      2225275.01     13838824.98      2225425.00     13838525.00
      2225674.97     13838275.03
#Sta/Elev= 30
  4664.1  887.53  4666.9  887.53  4753.5  855.66  4775.9  850.41  4801.0  842.82
  4834.6  832.79  4851.3  828.79  4865.3  823.62  4901.7  819.66  4977.1  815.81
  4985.5  810.79  4988.1  810.42  4991.1  809.99  4996.7  803.77  5011.6  802.85
  5011.9  802.35  5015.6  802.85  5027.8  803.01  5041.9  804.93  5070.2  810.71
  5084.3  817.10  5098.5  825.86  5112.6  839.56  5169.2  868.90  5176.3  874.20
  5183.3  876.36  5239.9  905.52  5324.8  937.05  5349.5  944.54  5353.0  944.54
#Mann=5,-1,0
  4664.1    0.12       0  4801.0   0.035       0  4988.1    0.12       0
  5011.6    0.05       0  5015.6    0.12       0
Bank Sta=5011.6,5015.6
Exp/Cntr=0.3,0.1

Type RM Length L Ch R = 1,8205,427,427,427
BEGIN DESCRIPTION:
Turkey Creek 18.0
END DESCRIPTION:
XS GIS Cut Line= 3
      2225324.97     13839075.02      2225725.00     13838825.00
      2225824.97     13838775.02
#Sta/Elev= 30
  4532.2  906.89  4535.2  906.89  4539.9  902.52  4561.1  896.53  4597.7  878.51
  4618.9  872.37  4634.2  864.89  4655.5  859.20  4692.0  845.55  4710.8  842.04
  4728.6  836.52  4749.8  833.80  4765.1  828.35  4771.0  828.59  4786.4  822.47
  4807.6  819.52  4838.2  811.44  4938.5  808.00  4963.3  801.96  4988.4  799.32
  4988.6  798.82  4992.4  799.32  5006.7  800.33  5017.9  805.47  5048.7  834.55
  5057.0  840.06  5079.4  852.21  5107.4  864.07  5112.9  868.70  5115.7  868.70
#Mann=5,-1,0
  4532.2    0.12       0  4710.8   0.035       0  4963.3    0.12       0
  4988.4    0.05       0  4992.4    0.12       0
Bank Sta=4988.4,4992.4
Exp/Cntr=0.3,0.1

Type RM Length L Ch R = 1,7778,199,199,199
BEGIN DESCRIPTION:
Turkey Creek 17.0
END DESCRIPTION:
XS GIS Cut Line= 3
      2225425.01     13839175.00      2225825.00     13839225.00
      2226025.02     13838974.97
#Sta/Elev= 30
  4591.6  865.79  4594.1  865.79  4601.7  861.27  4620.7  854.09  4682.3  832.17
  4742.8  818.23  4813.3  807.98  4884.1  804.96  4944.3  802.33  4951.9  800.45
  4956.9  801.36  4974.5  796.36  4984.6  790.99  4999.9  788.95  5000.2  788.45
  5003.9  788.95  5008.3  789.03  5016.3  796.98  5022.7  789.11  5030.7  798.57
  5037.1  797.83  5058.7  803.72  5086.7  817.36  5130.0  833.26  5136.4  836.95
  5158.8  844.04  5165.2  847.78  5186.8  852.45  5258.0  878.20  5314.9  890.66
#Mann=5,-1,0
  4591.6    0.12       0  4620.7   0.035       0  4884.1    0.12       0
  4999.9    0.05       0  5003.9    0.12       0
Bank Sta=4999.9,5003.9
Exp/Cntr=0.3,0.1

Type RM Length L Ch R = 1,7579,238,238,238
BEGIN DESCRIPTION:
H21501
END DESCRIPTION:
XS GIS Cut Line= 3
      2225596.02     13839699.63      2225988.80     13839322.04
      2226043.05     13839065.96
#Sta/Elev= 30
  4502.1  898.61  4511.8  896.00  4518.7  891.27  4526.0  889.26  4532.9  884.02
  4540.1  882.13  4547.0  877.21  4554.3  875.72  4561.2  871.23  4568.4  869.63
  4589.5  858.15  4646.1  835.96  4679.0  826.83  4709.6  818.50  4766.2  808.84
  4909.2  800.25  4936.0  798.24  4950.2  787.11  4962.3  784.30  4962.5  783.80
  4966.4  784.30  4992.6  785.72  5013.9  792.96  5046.9  798.43  5095.0  812.95
  5100.6  816.16  5217.7  846.65  5249.6  852.84  5294.2  865.52  5308.7  871.59
#Mann=5,-1,0
  4502.1    0.12       0  4679.0   0.035       0  4909.2    0.12       0
  4962.3    0.05       0  4966.4    0.12       0
Bank Sta=4962.3,4966.4
Exp/Cntr=0.3,0.1

Type RM Length L Ch R = 1,7341,427,427,427
BEGIN DESCRIPTION:
Turkey Creek 16.0
END DESCRIPTION:
XS GIS Cut Line= 3
      2225724.97     13839825.02      2226125.00     13839525.00
      2226075.01     13839125.04
#Sta/Elev= 30
  4495.4  912.31  4498.6  912.31  4502.7  908.40  4523.6  899.88  4552.7  883.41
  4581.9  870.80  4650.7  838.59  4688.1  826.86  4723.6  820.04  4773.6  813.04
  4831.9  809.19  4838.1  807.36  4867.3  803.49  4873.6  801.40  4902.7  801.32
  4931.9  799.00  4958.8  789.89  4973.6  785.64  4988.1  784.07  5003.5  783.99
  5003.7  783.49  5007.6  783.99  5025.7  784.07  5033.2  785.45  5038.3  784.58
  5066.0  791.72  5166.8  796.93  5199.5  800.43  5328.0  837.56  5398.5  854.94
#Mann=5,-1,0
  4495.4    0.12       0  4650.7   0.035       0  4958.8    0.12       0
  5003.5    0.05       0  5007.6    0.12       0
Bank Sta=5003.5,5007.6
Exp/Cntr=0.3,0.1

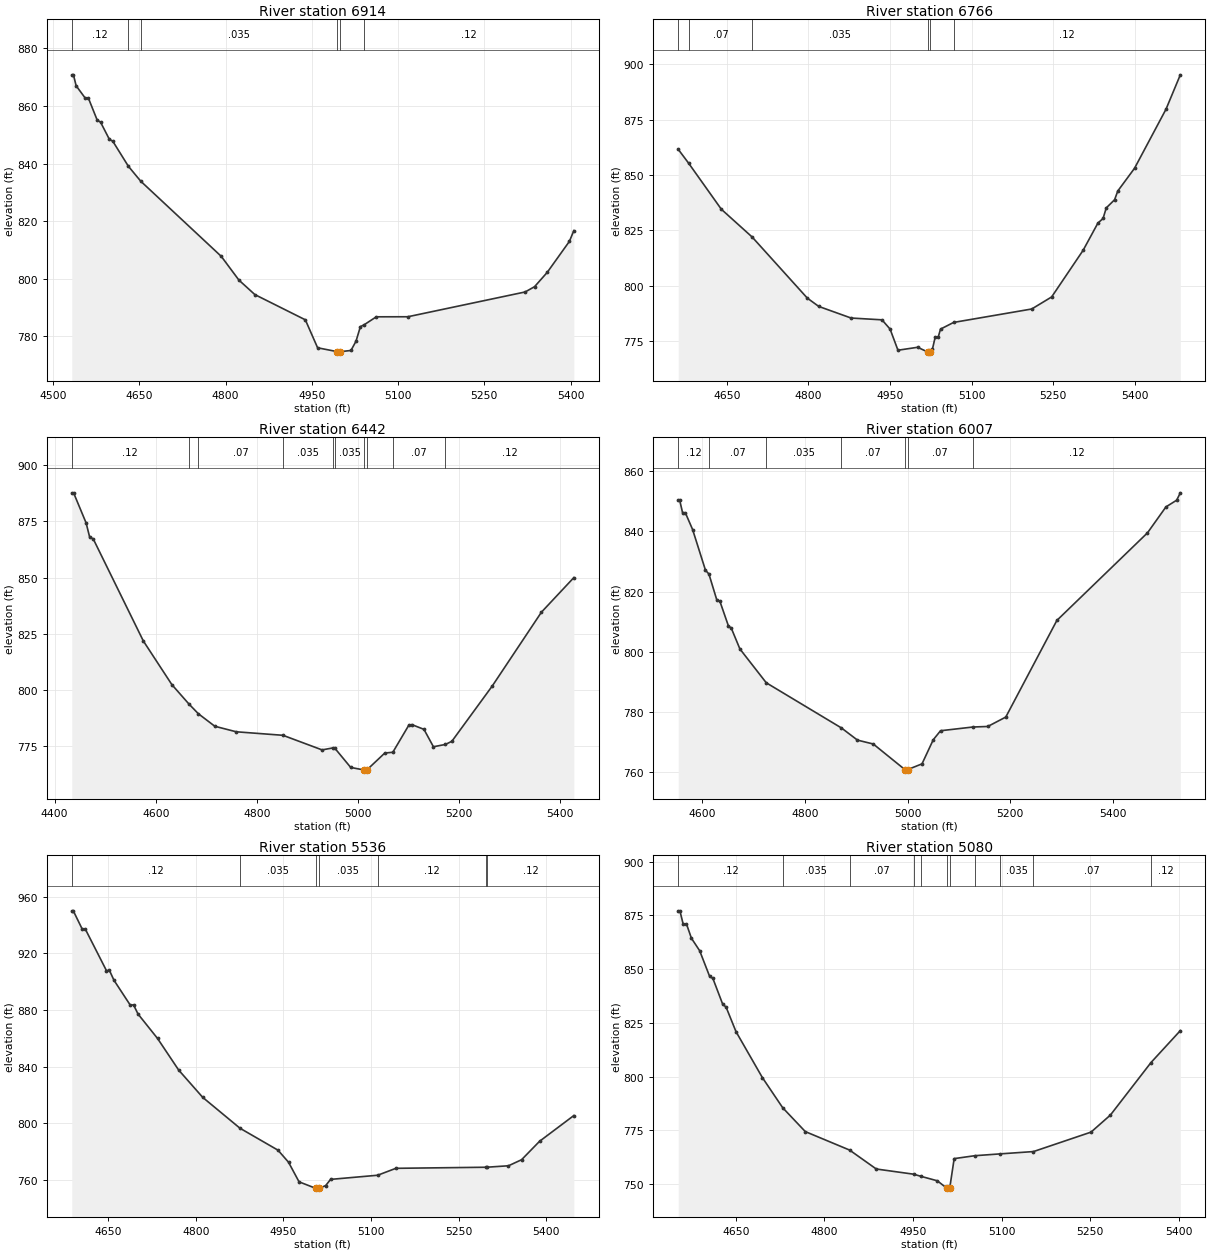
Type RM Length L Ch R = 1,6914,148,148,148
BEGIN DESCRIPTION:
Turkey Creek 15.0
END DESCRIPTION:
XS GIS Cut Line= 3
      2226275.01     13839924.98      2226525.00     13839525.00
      2226338.11     13839169.74
#Sta/Elev= 30
  4532.6  870.84  4535.5  870.84  4540.2  867.04  4555.6  862.85  4561.5  862.74
  4576.8  855.10  4582.7  854.36  4598.0  848.40  4603.9  847.76  4631.0  839.05
  4652.6  833.83  4792.6  807.70  4823.3  799.44  4851.0  794.41  4938.8  785.63
  4960.1  775.91  4994.5  774.55  4994.8  774.05  4998.7  774.55  5018.1  774.97
  5026.9  778.20  5034.5  783.25  5041.5  783.97  5062.2  786.68  5117.0  786.70
  5321.0  795.32  5337.4  797.16  5359.4  802.13  5397.9  812.90  5405.7  816.65
#Mann=6,-1,0
  4532.6    0.12       0  4631.0    0.07       0  4652.6   0.035       0
  4994.5   0.035       0  4998.7   0.035       0  5041.5    0.12       0
Bank Sta=4994.5,4998.7
Exp/Cntr=0.3,0.1

Type RM Length L Ch R = 1,6766,324,324,324
BEGIN DESCRIPTION:
H21500
END DESCRIPTION:
XS GIS Cut Line= 3
      2226396.80     13839957.87      2226665.88     13839567.27
      2226902.44     13839185.30
#Sta/Elev= 30
  4560.4  861.61  4579.3  855.42  4639.7  834.56  4696.4  822.02  4797.9  794.44
  4818.9  790.70  4878.4  785.46  4935.2  784.65  4950.1  780.48  4964.6  770.93
  5000.8  772.26  5019.4  770.12  5019.7  769.62  5024.2  770.12  5027.9  771.32
  5033.1  776.83  5038.6  776.83  5042.9  780.46  5067.0  783.48  5210.7  789.54
  5247.3  794.98  5305.2  816.03  5332.4  828.32  5341.9  830.40  5347.8  835.18
  5363.1  838.85  5369.0  842.81  5399.8  853.06  5457.7  879.73  5484.0  895.24
#Mann=6,-1,0
  4560.4    0.12       0  4579.3    0.07       0  4696.4   0.035       0
  5019.4   0.035       0  5024.2   0.035       0  5067.0    0.12       0
Bank Sta=5019.4,5024.2
Exp/Cntr=0.3,0.1

Type RM Length L Ch R = 1,6442,435,435,435
BEGIN DESCRIPTION:
Turkey Creek 14.0
END DESCRIPTION:
XS GIS Cut Line= 3
      2226474.98     13840225.02      2226875.00     13839825.00
      2227024.99     13839425.02
#Sta/Elev= 30
  4434.0  887.75  4437.6  887.75  4462.3  874.37  4469.4  868.01  4476.5  867.20
  4575.5  821.75  4632.0  802.28  4665.4  793.73  4684.3  789.33  4716.9  783.74
  4759.3  781.28  4851.7  779.71  4929.0  773.21  4951.3  774.13  4954.5  773.88
  4985.6  765.40  5012.3  764.25  5012.7  763.75  5017.4  764.25  5053.1  771.82
  5068.9  772.15  5100.3  784.12  5106.5  784.48  5130.5  782.36  5149.2  774.61
  5172.8  775.63  5185.7  777.05  5265.8  801.76  5362.8  834.57  5426.9  849.98
#Mann=10,-1,0
  4434.0    0.12       0  4665.4   0.035       0  4684.3    0.07       0
  4851.7   0.035       0  4951.3    0.07       0  4954.5   0.035       0
  5012.3   0.035       0  5017.4   0.035       0  5068.9    0.07       0
  5172.8    0.12       0
Bank Sta=5012.3,5017.4
Exp/Cntr=0.3,0.1

Type RM Length L Ch R = 1,6007,471,471,471
BEGIN DESCRIPTION:
Turkey Creek 13.0
END DESCRIPTION:
XS GIS Cut Line= 3
      2226574.98     13840425.01      2226975.00     13840225.00
      2227374.97     13839875.03
#Sta/Elev= 30
  4552.8  850.40  4555.6  850.40  4561.2  846.26  4566.8  846.14  4580.8  840.63
  4605.9  827.09  4612.6  825.83  4628.3  817.03  4633.9  816.81  4650.7  808.53
  4656.2  807.83  4673.0  800.91  4724.4  789.66  4871.0  774.63  4902.2  770.59
  4933.0  769.30  4994.7  760.78  4995.1  760.28  4999.8  760.78  5028.0  762.70
  5049.9  770.71  5064.1  773.71  5127.2  774.95  5156.2  775.13  5191.3  778.26
  5290.9  810.40  5467.5  839.52  5503.5  848.15  5524.4  850.38  5531.5  852.83
#Mann=7,-1,0
  4552.8    0.12       0  4612.6    0.07       0  4724.4   0.035       0
  4871.0    0.07       0  4994.7    0.05       0  4999.8    0.07       0
  5127.2    0.12       0
Bank Sta=4994.7,4999.8
Exp/Cntr=0.3,0.1

Type RM Length L Ch R = 1,5536,456,456,456
BEGIN DESCRIPTION:
Turkey Creek 12.0
END DESCRIPTION:
XS GIS Cut Line= 3
      2227124.99     13840975.03      2227225.00     13840575.00
      2227425.02     13840174.96
#Sta/Elev= 30
  4587.7  950.03  4590.3  950.03  4605.8  936.94  4610.9  937.11  4647.0  907.85
  4652.2  907.94  4659.9  901.02  4688.2  883.19  4693.4  883.68  4701.1  877.15
  4734.6  859.84  4770.7  837.55  4811.9  818.25  4875.7  796.44  4940.8  780.93
  4958.8  772.44  4976.8  758.59  5005.8  753.92  5006.2  753.42  5011.0  753.92
  5022.4  755.92  5030.8  760.30  5111.4  763.23  5142.6  768.12  5296.4  768.88
  5298.7  768.91  5335.4  769.92  5357.8  774.19  5388.6  787.21  5447.3  805.41
#Mann=7,-1,0
  4587.7    0.12       0  4875.7   0.035       0  5005.8   0.035       0
  5011.0   0.035       0  5111.4    0.12       0  5296.4    0.07       0
  5298.7    0.12       0
Bank Sta=5005.8,5011
Exp/Cntr=0.3,0.1

Type RM Length L Ch R = 1,5080,482,482,482
BEGIN DESCRIPTION:
Turkey Creek 11.0
END DESCRIPTION:
XS GIS Cut Line= 3
      2227425.02     13840924.96      2227625.00     13840525.00
      2227575.00     13840124.98
#Sta/Elev= 30
  4552.4  877.10  4555.2  877.10  4560.7  870.99  4566.3  871.03  4574.7  864.37
  4588.7  858.54  4605.5  846.65  4611.1  845.64  4627.8  833.59  4633.4  832.35
  4650.2  820.92  4694.9  799.53  4729.3  785.51  4767.6  774.41  4842.6  765.82
  4887.8  757.01  4951.0  754.60  4963.6  753.59  4991.2  751.52  5007.0  748.15
  5007.4  747.65  5012.2  748.15  5019.7  761.84  5054.5  763.19  5097.8  764.05
  5154.0  765.12  5251.5  774.17  5284.3  782.10  5353.1  806.55  5402.7  821.37
#Mann=11,-1,0
  4552.4    0.12       0  4729.3   0.035       0  4842.6    0.07       0
  4951.0   0.035       0  4963.6    0.07       0  5007.0    0.05       0
  5012.2    0.07       0  5054.5    0.12       0  5097.8   0.035       0
  5154.0    0.07       0  5353.1    0.12       0
Bank Sta=5007,5012.2
Exp/Cntr=0.3,0.1

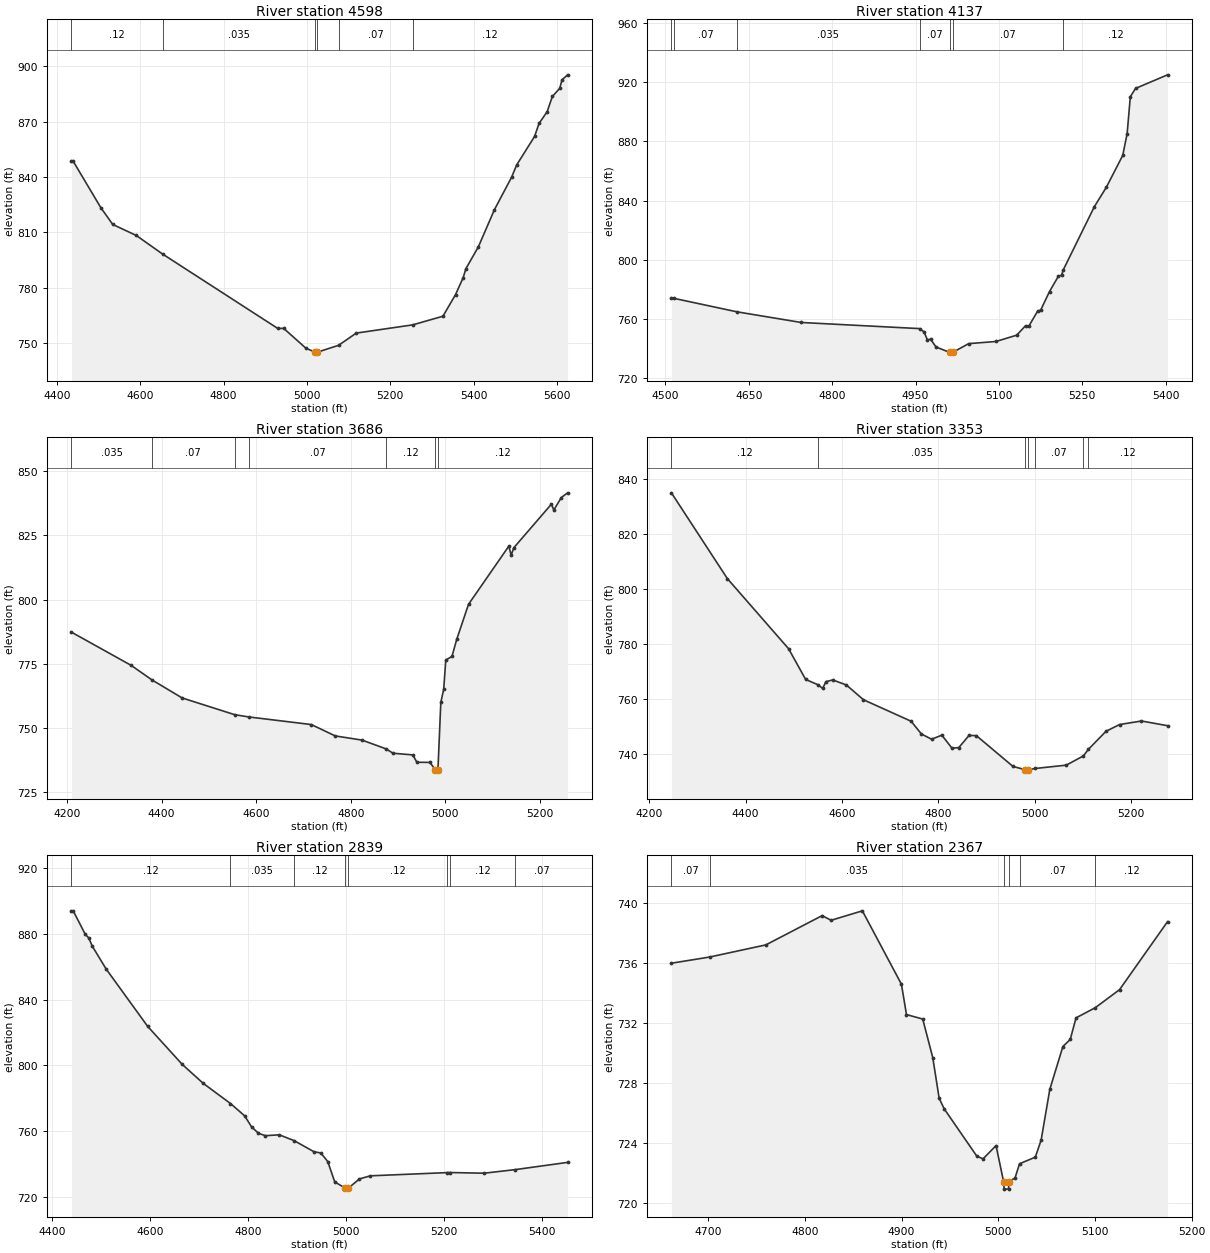
Type RM Length L Ch R = 1,4598,461,461,461
BEGIN DESCRIPTION:
Turkey Creek 10.0
END DESCRIPTION:
XS GIS Cut Line= 3
      2227675.02     13841024.98      2228075.00     13840625.00
      2228296.07     13840040.79
#Sta/Elev= 30
  4435.0  848.74  4438.5  848.74  4505.7  823.28  4534.0  814.29  4590.5  808.32
  4653.6  798.26  4930.0  757.96  4944.1  758.02  4997.1  747.34  5019.3  745.10
  5019.8  744.60  5024.7  745.10  5075.9  748.84  5118.3  755.45  5253.5  759.90
  5326.2  764.59  5356.4  776.30  5374.9  785.55  5381.2  790.30  5411.3  802.23
  5449.7  822.28  5491.1  839.96  5503.2  846.56  5546.0  861.93  5556.8  869.01
  5576.3  875.37  5588.7  883.61  5606.5  888.04  5611.8  892.60  5625.3  895.32
#Mann=6,-1,0
  4435.0    0.12       0  4653.6   0.035       0  5019.3   0.035       0
  5024.7   0.035       0  5075.9    0.07       0  5253.5    0.12       0
Bank Sta=5019.3,5024.7
Exp/Cntr=0.3,0.1

Type RM Length L Ch R = 1,4137,451,451,451
BEGIN DESCRIPTION:
Turkey Creek 9.0
END DESCRIPTION:
XS GIS Cut Line= 3
      2228222.17     13841044.47      2228475.00     13840625.00
      2228675.01     13840274.99
#Sta/Elev= 30
  4510.7  774.06  4515.0  773.88  4628.9  764.73  4744.2  757.54  4957.2  753.39
  4965.4  751.16  4971.4  745.77  4977.2  746.22  4986.9  740.94  5011.5  737.30
  5011.9  736.80  5016.9  737.30  5045.8  743.23  5094.8  744.67  5132.2  748.96
  5148.0  755.34  5153.8  754.97  5169.6  765.09  5175.4  765.99  5191.2  778.49
  5207.1  788.79  5212.8  789.60  5216.0  793.18  5271.9  835.89  5293.5  849.05
  5323.0  870.63  5330.9  885.34  5336.6  910.27  5346.0  915.91  5403.6  925.10
#Mann=7,-1,0
  4510.7   0.035       0  4515.0    0.07       0  4628.9   0.035       0
  4957.2    0.07       0  5011.5    0.05       0  5016.9    0.07       0
  5216.0    0.12       0
Bank Sta=5011.5,5016.9
Exp/Cntr=0.3,0.1

Type RM Length L Ch R = 1,3686,333,333,333
BEGIN DESCRIPTION:
Turkey Creek 8.0
END DESCRIPTION:
XS GIS Cut Line= 3
      2228172.91     13841179.93      2228825.00     13840725.00
      2228853.33     13840471.78
#Sta/Elev= 30
  4209.1  787.30  4335.5  774.36  4379.3  768.72  4443.3  761.68  4554.4  755.17
  4584.3  754.28  4716.7  751.32  4767.3  746.89  4824.0  745.26  4875.0  741.84
  4889.5  740.15  4931.3  739.50  4940.1  736.63  4967.6  736.58  4979.2  733.68
  4979.6  733.18  4984.6  733.68  4990.7  759.95  4996.8  765.06  5001.2  776.43
  5014.3  777.86  5024.3  784.46  5049.3  798.15  5134.6  820.80  5139.6  817.27
  5145.1  820.17  5224.8  837.17  5229.8  834.87  5245.7  839.74  5259.0  841.57
#Mann=7,-1,0
  4209.1   0.035       0  4379.3    0.07       0  4554.4   0.035       0
  4584.3    0.07       0  4875.0    0.12       0  4979.2    0.05       0
  4984.6    0.12       0
Bank Sta=4979.2,4984.6
Exp/Cntr=0.3,0.1

Type RM Length L Ch R = 1,3353,514,514,514
BEGIN DESCRIPTION:
Turkey Creek 7.0
END DESCRIPTION:
XS GIS Cut Line= 3
      2228225.26     13841549.37      2228662.44     13841096.80
      2229025.04     13840924.98
#Sta/Elev= 30
  4245.8  834.85  4362.0  803.66  4489.1  778.18  4524.6  767.00  4550.3  765.05
  4559.8  763.75  4567.0  766.21  4581.1  766.81  4609.4  764.95  4644.7  759.61
  4743.7  751.79  4765.1  747.15  4786.2  745.25  4807.5  746.73  4828.6  741.98
  4842.8  742.22  4863.9  746.62  4879.2  746.56  4955.3  735.35  4981.0  734.15
  4981.4  733.65  4986.4  734.15  5001.4  734.61  5066.0  735.83  5101.4  739.17
  5112.0  741.59  5148.4  748.13  5176.7  750.59  5222.2  751.88  5276.3  750.17
#Mann=7,-1,0
  4245.8    0.12       0  4550.3   0.035       0  4981.0   0.035       0
  4986.4   0.035       0  5001.4    0.07       0  5101.4   0.035       0
  5112.0    0.12       0
Bank Sta=4981,4986.4
Exp/Cntr=0.3,0.1

Type RM Length L Ch R = 1,2839,472,472,472
BEGIN DESCRIPTION:
Turkey Creek 6.0
END DESCRIPTION:
XS GIS Cut Line= 3
      2228375.03     13841874.97      2228775.00     13841475.00
      2228975.02     13841074.96
#Sta/Elev= 30
  4439.8  894.16  4443.3  894.16  4468.0  879.83  4475.1  877.62  4482.2  872.67
  4510.5  858.75  4595.3  823.79  4666.0  800.59  4708.5  789.13  4764.4  776.79
  4793.3  769.29  4807.5  762.53  4821.6  758.64  4835.7  757.18  4864.0  757.73
  4894.5  754.16  4934.7  747.43  4948.9  746.63  4963.0  741.45  4977.2  729.09
  4999.2  725.13  4999.6  724.63  5004.7  725.13  5027.8  730.87  5050.2  732.74
  5206.7  734.69  5212.9  734.74  5282.2  734.33  5345.6  736.51  5452.7  740.92
#Mann=8,-1,0
  4439.8    0.12       0  4764.4   0.035       0  4894.5    0.12       0
  4999.2    0.05       0  5004.7    0.12       0  5206.7    0.07       0
  5212.9    0.12       0  5345.6    0.07       0
Bank Sta=4999.2,5004.7
Exp/Cntr=0.3,0.1

Type RM Length L Ch R = 1,2367,470,470,470
BEGIN DESCRIPTION:
Turkey Creek 5.0
END DESCRIPTION:
XS GIS Cut Line= 3
      2229216.60     13841644.77      2229125.00     13841325.00
      2229025.01     13841175.01
#Sta/Elev= 30
  4662.1  735.98  4701.5  736.39  4759.7  737.20  4817.9  739.15  4827.2  738.84
  4859.5  739.47  4899.9  734.58  4905.1  732.56  4921.9  732.26  4932.3  729.69
  4938.9  726.98  4944.1  726.28  4977.9  723.12  4984.3  722.95  4997.7  723.83
  5005.5  721.43  5006.0  720.93  5010.6  720.93  5011.0  721.43  5017.3  721.67
  5022.0  722.62  5038.3  723.06  5044.3  724.19  5053.3  727.58  5066.8  730.43
  5074.4  730.90  5080.4  732.34  5100.4  733.02  5125.4  734.22  5175.0  738.75
#Mann=6,-1,0
  4662.1    0.07       0  4701.5   0.035       0  5005.5   0.035       0
  5011.0   0.035       0  5022.0    0.07       0  5100.4    0.12       0
Bank Sta=5005.5,5011
Exp/Cntr=0.3,0.1

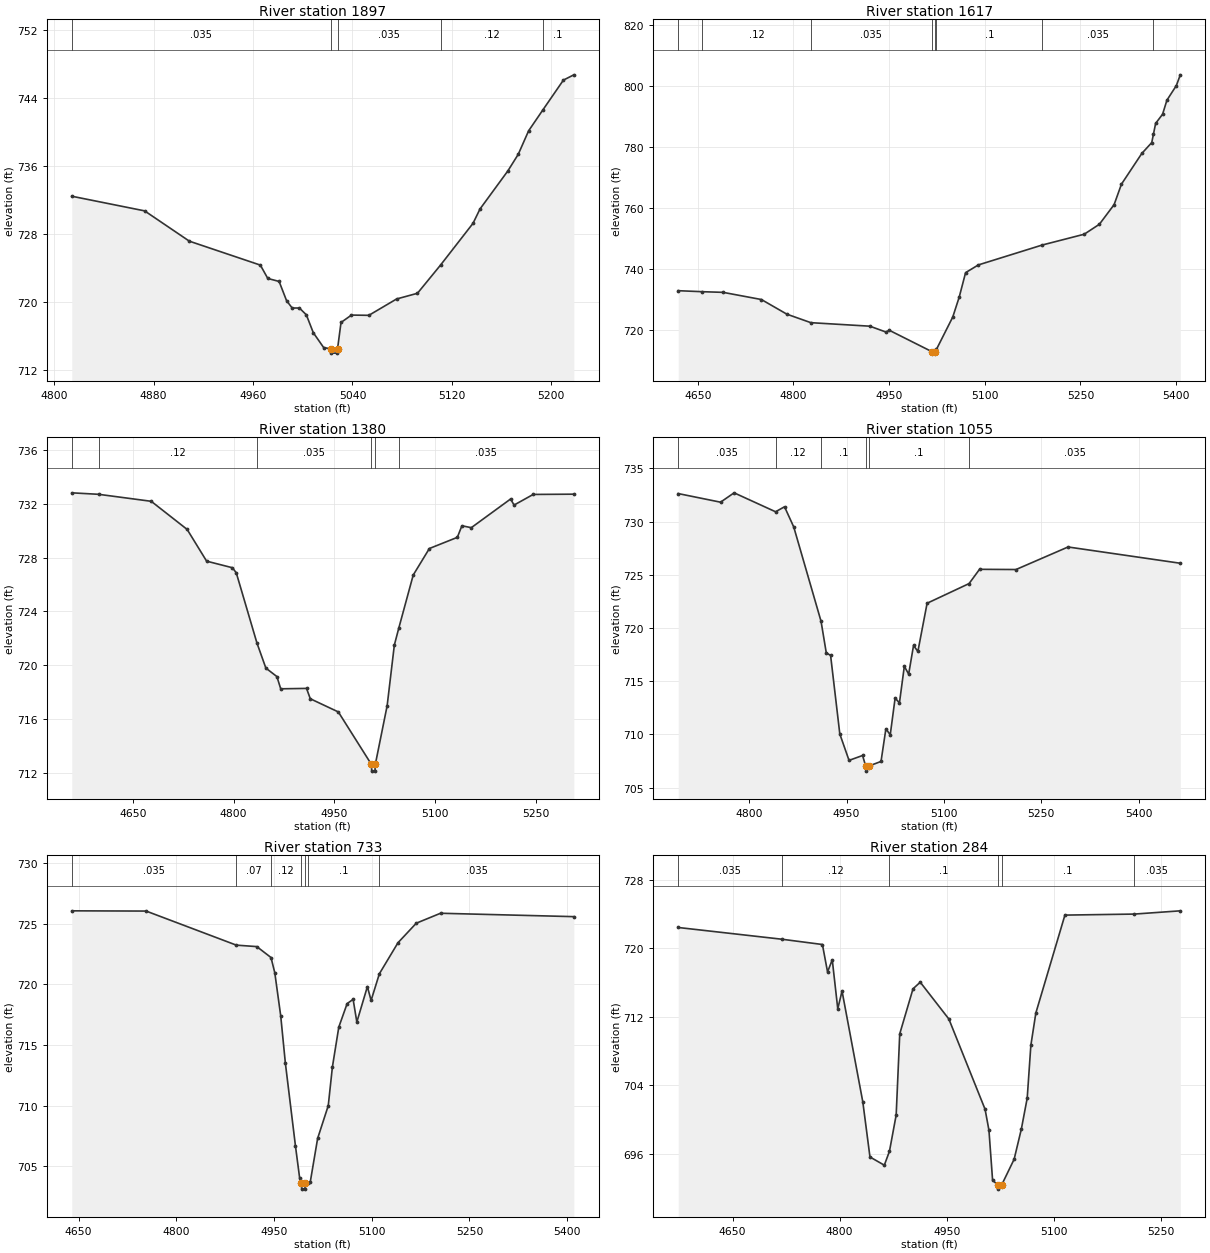
Type RM Length L Ch R = 1,1897,280,280,280
BEGIN DESCRIPTION:
Turkey Creek 4.0
END DESCRIPTION:
XS GIS Cut Line= 3
      2229525.00     13841125.00      2229425.00     13840975.00
      2229324.99     13840774.99
#Sta/Elev= 30
  4814.2  732.47  4872.8  730.75  4908.8  727.19  4965.9  724.38  4971.9  722.81
  4981.0  722.46  4987.0  720.20  4991.5  719.34  4997.3  719.34  5002.9  718.54
  5008.5  716.44  5016.8  714.70  5022.4  714.54  5022.9  714.04  5027.6  714.04
  5028.0  714.54  5030.8  717.64  5039.2  718.51  5053.2  718.48  5075.5  720.40
  5092.3  721.07  5110.9  724.39  5137.0  729.29  5142.6  730.97  5165.0  735.44
  5173.4  737.40  5181.7  740.15  5193.0  742.57  5209.7  746.11  5218.1  746.73
#Mann=5,-1,0
  4814.2   0.035       0  5022.4   0.035       0  5028.0   0.035       0
  5110.9    0.12       0  5193.0     0.1       0
Bank Sta=5022.4,5028
Exp/Cntr=0.3,0.1

Type RM Length L Ch R = 1,1617,237,237,237
BEGIN DESCRIPTION:
XS7862
END DESCRIPTION:
XS GIS Cut Line= 3
      2229558.36     13841155.27      2229576.83     13840638.07
      2229472.42     13840389.32
#Sta/Elev= 30
  4619.4  732.99  4657.4  732.66  4689.7  732.45  4749.8  730.10  4789.8  725.30
  4827.4  722.52  4919.9  721.37  4945.3  719.44  4950.3  720.04  5017.0  713.05
  5017.5  712.55  5022.8  713.05  5024.2  713.74  5049.9  724.38  5060.0  730.90
  5070.0  738.90  5090.0  741.43  5190.1  747.94  5256.0  751.48  5279.8  754.74
  5302.9  761.17  5314.4  767.87  5346.3  777.92  5361.9  781.48  5364.6  784.26
  5368.0  787.77  5378.9  790.77  5385.7  795.36  5400.5  800.16  5406.7  803.67
#Mann=8,-1,0
  4619.4   0.035       0  4657.4    0.12       0  4827.4   0.035       0
  5017.0   0.035       0  5022.8   0.035       0  5024.2     0.1       0
  5190.1   0.035       0  5364.6    0.12       0
Bank Sta=5017,5022.8
Exp/Cntr=0.3,0.1

Type RM Length L Ch R = 1,1380,325,325,325
BEGIN DESCRIPTION:
XS7861
END DESCRIPTION:
XS GIS Cut Line= 3
      2229586.08     13841176.82      2229764.63     13840838.18
      2229865.84     13840488.56
#Sta/Elev= 30
  4559.3  732.82  4599.2  732.71  4677.5  732.19  4730.9  730.10  4759.9  727.74
  4798.3  727.25  4804.0  726.87  4834.7  721.66  4848.0  719.79  4864.4  719.16
  4870.1  718.25  4908.5  718.28  4914.1  717.51  4955.8  716.53  5005.0  712.63
  5005.4  712.13  5010.3  712.13  5010.8  712.63  5028.4  716.99  5039.1  721.50
  5045.7  722.76  5067.2  726.71  5091.2  728.68  5132.8  729.51  5139.6  730.37
  5153.6  730.23  5212.0  732.36  5217.2  731.91  5245.6  732.70  5306.1  732.72
#Mann=6,-1,0
  4559.3   0.035       0  4599.2    0.12       0  4834.7   0.035       0
  5005.0   0.035       0  5010.8   0.035       0  5045.7   0.035       0
Bank Sta=5005,5010.8
Exp/Cntr=0.3,0.1

Type RM Length L Ch R = 1,1055,322,322,322
BEGIN DESCRIPTION:
XS7860
END DESCRIPTION:
XS GIS Cut Line= 3
      2229595.27     13841296.94      2229940.12     13840985.96
      2230096.56     13840719.09
#Sta/Elev= 30
  4690.7  732.64  4755.9  731.83  4776.8  732.71  4840.7  730.93  4854.5  731.40
  4868.7  729.50  4910.8  720.63  4918.8  717.68  4925.5  717.42  4939.7  710.04
  4953.9  707.56  4974.8  708.02  4979.4  707.05  4979.9  706.55  4985.3  707.05
  5003.2  707.46  5010.7  710.53  5017.4  709.96  5024.9  713.41  5031.6  712.97
  5039.1  716.40  5045.8  715.67  5053.3  718.36  5060.0  717.80  5074.2  722.33
  5138.9  724.18  5155.0  725.52  5211.2  725.50  5291.4  727.62  5464.4  726.09
#Mann=6,-1,0
  4690.7   0.035       0  4840.7    0.12       0  4910.8     0.1       0
  4979.4    0.05       0  4985.3     0.1       0  5138.9   0.035       0
Bank Sta=4979.4,4985.3
Exp/Cntr=0.3,0.1

Type RM Length L Ch R = 1,733,449,449,449
BEGIN DESCRIPTION:
XS7859
END DESCRIPTION:
XS GIS Cut Line= 3
      2229804.66     13841647.88      2230041.72     13841204.55
      2230124.68     13840949.54
#Sta/Elev= 30
  4639.4  726.07  4753.6  726.05  4892.1  723.24  4923.5  723.12  4945.3  722.22
  4951.1  720.97  4960.2  717.42  4967.3  713.54  4982.9  706.66  4989.3  704.03
  4992.0  703.62  4992.5  703.12  4997.4  703.12  4997.9  703.62  5001.9  703.65
  5005.5  703.68  5016.9  707.30  5033.2  710.00  5039.6  713.20  5049.4  716.48
  5062.2  718.42  5071.4  718.77  5077.1  716.90  5093.3  719.82  5099.0  718.68
  5111.7  720.88  5140.3  723.44  5168.4  725.05  5205.6  725.87  5410.3  725.59
#Mann=7,-1,0
  4639.4   0.035       0  4892.1    0.07       0  4945.3    0.12       0
  4992.0    0.05       0  4997.9    0.12       0  5001.9     0.1       0
  5111.7   0.035       0
Bank Sta=4992,4997.9
Exp/Cntr=0.3,0.1

Type RM Length L Ch R = 1,284,0,0,0
BEGIN DESCRIPTION:
XS7858
END DESCRIPTION:
XS GIS Cut Line= 4
      2230084.82     13841629.42      2230232.60     13841453.93
      2230247.99     13841293.84      2230192.57     13840985.94
#Sta/Elev= 30
  4574.0  722.45  4718.9  721.08  4775.9  720.46  4783.1  717.25  4789.7  718.67
  4797.4  712.94  4803.4  715.01  4832.5  702.03  4842.5  695.60  4862.6  694.64
  4869.8  696.27  4879.2  700.51  4884.2  710.01  4902.8  715.28  4912.9  716.05
  4953.0  711.74  5003.7  701.18  5009.1  698.74  5014.2  692.90  5021.1  692.34
  5021.6  691.84  5027.0  692.34  5044.4  695.34  5054.5  698.87  5062.7  702.49
  5067.8  708.66  5074.8  712.45  5115.5  723.90  5212.8  724.02  5277.1  724.40
#Mann=6,-1,0
  4574.0   0.035       0  4718.9    0.12       0  4869.8     0.1       0
  5021.1    0.05       0  5027.0     0.1       0  5212.8   0.035       0
Bank Sta=5021.1,5027
Exp/Cntr=0.3,0.1

Chan Stop Cuts=-1