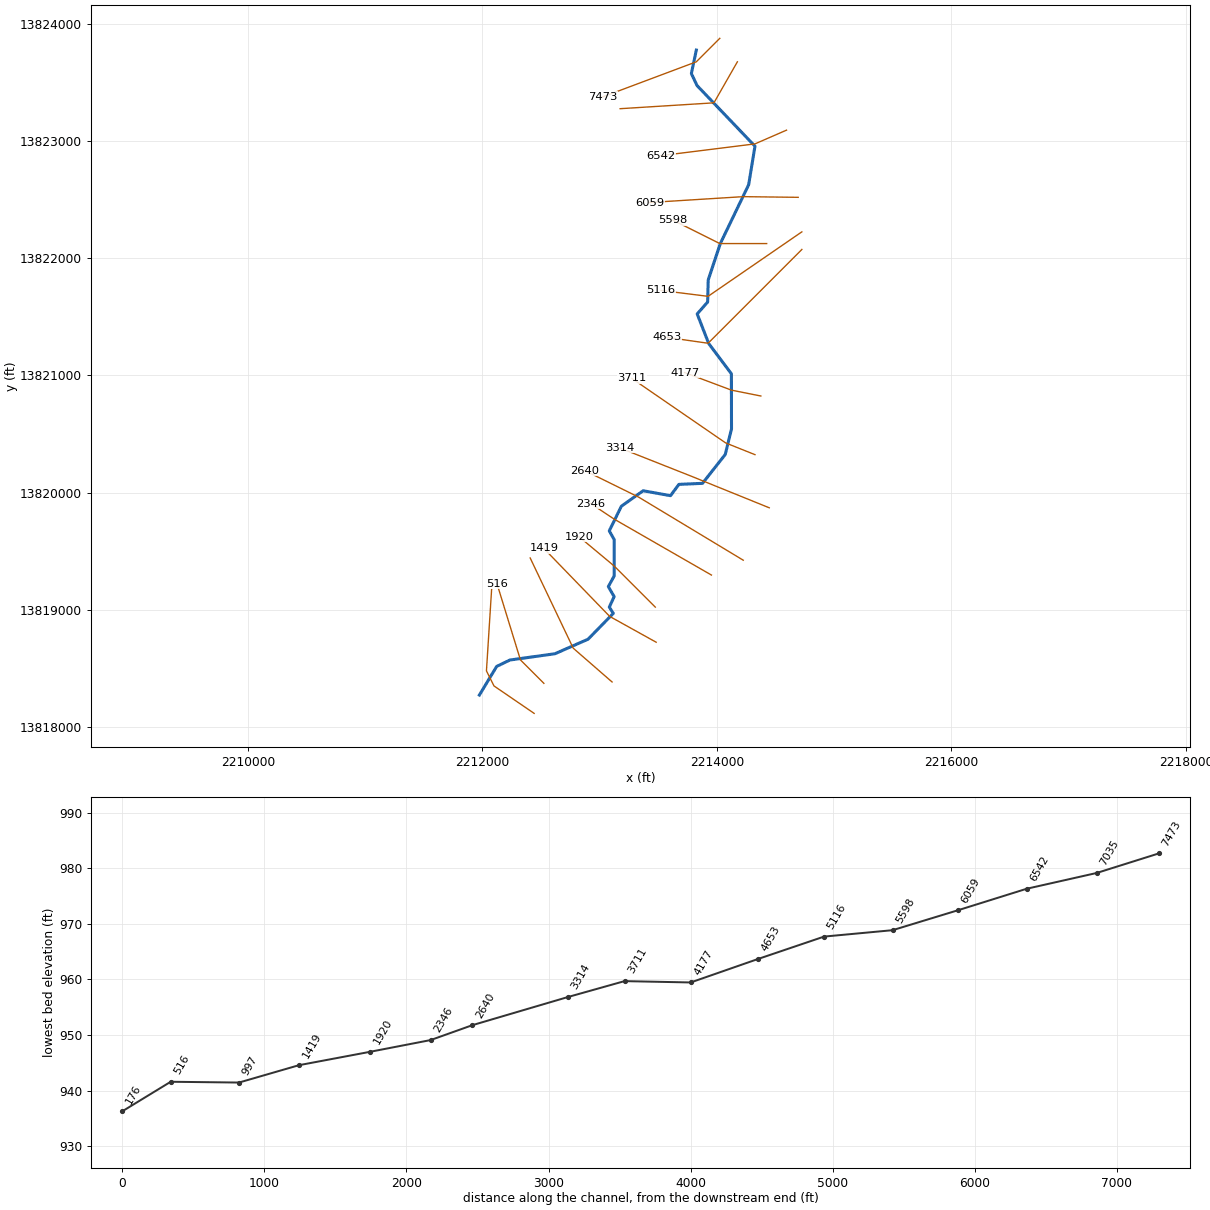
--- Upper Dry Comal Tributary 10.prj (project) ---

Proj Title=Upper Dry Comal Tributary 10 Base Level Engineering
Current Plan=p01
Default Exp/Contr=0.3,0.1
English Units
Geom File=g01
Flow File=f01
Plan File=p01
BEGIN DESCRIPTION:
Upper Dry Comal Tributary 10
END DESCRIPTION:

--- Upper Dry Comal Tributary 10.p01 (plan) ---

Plan Title=Multiple Run
Short Identifier=Multiple
Geom File=g01
Flow File=f01
Subcritical Flow
K Sum by GR= 0
Std Step Tol= 0.01
Critical Tol= 0.01
Num of Std Step Trials= 20
Max Error Tol= 0.3
Flow Tol Ratio= 0.001
Split Flow NTrial= 30
Split Flow Tol= 0.02
Split Flow Ratio= 0.02
Log Output Level= 0
Friction Slope Method= 1
Unsteady Friction Slope Method= 2
Unsteady Bridges Friction Slope Method= 1
Parabolic Critical Depth
Global Vel Dist=  1 , 1 , 1
Global Log Level= 0
CheckData=True
Encroach Param= -1, 0, 0, 0
BEGIN DESCRIPTION:
Multiple Run
END DESCRIPTION:

--- Upper Dry Comal Tributary 10.f01 (steady flow) ---

Flow Title=Multiple
Number of Profiles=7
Profile Names=10-year,25-year,50-year,1pct_min,100-year,1pct_plu,500-year
River Rch & RM= Upper Dry Comal ,Reach-1,7473
    1193    2020    2803    1884    3759    7500    6687
River Rch & RM= Upper Dry Comal ,Reach-1,5116
    1422    2411    3350    2250    4489    8956    7979
Boundary for River Rch & Prof#=Upper Dry Comal ,Reach-1,1
Up Type=0
Dn Type=3
Dn Slope=0.005
Boundary for River Rch & Prof#=Upper Dry Comal ,Reach-1,2
Up Type=0
Dn Type=3
Dn Slope=0.005
Boundary for River Rch & Prof#=Upper Dry Comal ,Reach-1,3
Up Type=0
Dn Type=3
Dn Slope=0.005
Boundary for River Rch & Prof#=Upper Dry Comal ,Reach-1,4
Up Type=0
Dn Type=3
Dn Slope=0.005
Boundary for River Rch & Prof#=Upper Dry Comal ,Reach-1,5
Up Type=0
Dn Type=3
Dn Slope=0.005
Boundary for River Rch & Prof#=Upper Dry Comal ,Reach-1,6
Up Type=0
Dn Type=3
Dn Slope=0.005
Boundary for River Rch & Prof#=Upper Dry Comal ,Reach-1,7
Up Type=0
Dn Type=3
Dn Slope=0.005

--- Upper Dry Comal Tributary 10.g01 (geometry) ---

Geom Title=Existing Conditions

River Reach=Upper Dry Comal ,Reach-1
Reach XY= 30
      2213825.00     13823775.00      2213782.52     13823574.99
      2213830.81     13823472.71      2214325.04     13822955.02
      2214271.17     13822626.58      2214028.83     13822123.42
      2213926.22     13821814.50      2213921.44     13821626.46
      2213832.30     13821525.08      2213930.52     13821272.57
      2214123.80     13821014.50      2214124.93     13820545.03
      2214071.46     13820326.47      2213877.70     13820080.36
      2213676.26     13820071.52      2213604.80     13819975.05
      2213371.59     13820017.19      2213185.63     13819885.00
      2213082.53     13819675.01      2213125.11     13819600.12
      2213124.46     13819290.21      2213074.61     13819200.00
      2213124.17     13819114.30      2213082.84     13819024.91
      2213117.01     13818971.66      2212901.82     13818751.29
      2212619.06     13818627.27      2212235.50     13818573.80
      2212122.45     13818519.27      2211975.00     13818275.00

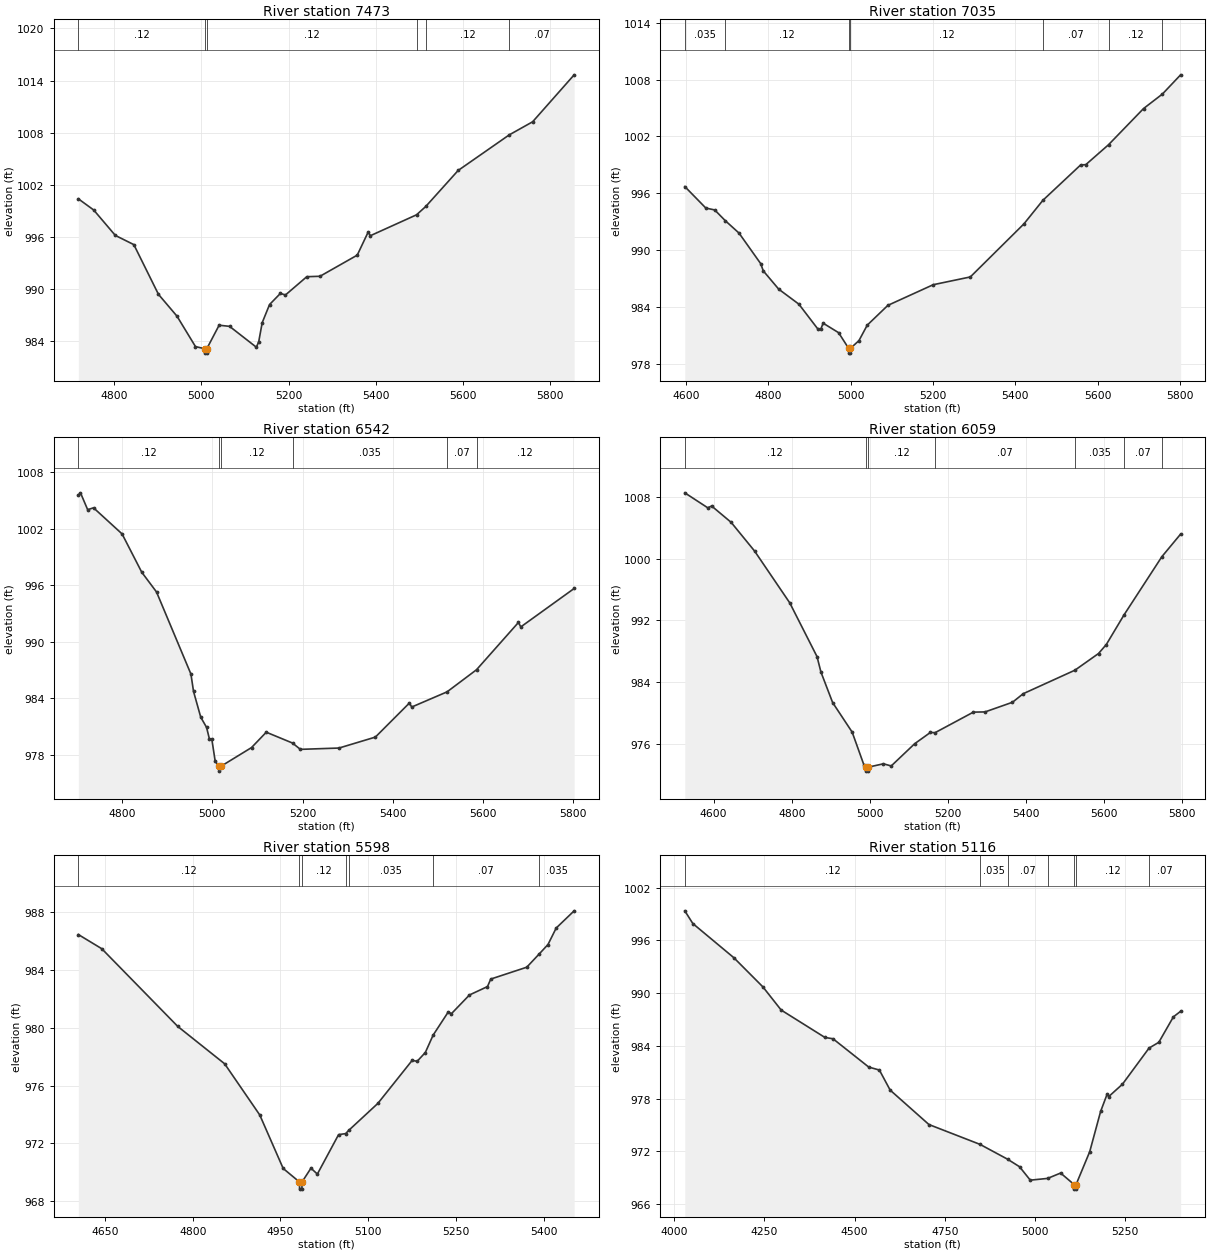
Type RM Length L Ch R = 1,7473,438,438,438
BEGIN DESCRIPTION:
Upper Dry Comal Tributary 10 16.0
END DESCRIPTION:
XS GIS Cut Line= 3
      2214025.00     13823875.00      2213825.00     13823675.00
      2213025.03     13823375.01
#Sta/Elev= 30
  4717.8 1000.40  4753.1  999.11  4802.6  996.19  4845.1  995.13  4901.6  989.41
  4944.1  986.90  4986.5  983.40  5008.4  983.15  5008.7  982.65  5012.2  982.65
  5012.4  983.15  5040.7  985.86  5064.7  985.73  5126.1  983.33  5131.5  983.95
  5139.5  986.15  5156.4  988.24  5181.3  989.52  5192.9  989.34  5241.8  991.44
  5272.1  991.49  5357.5  993.92  5382.4  996.56  5387.8  996.16  5493.5  998.56
  5514.7  999.52  5588.9 1003.66  5706.0 1007.75  5759.8 1009.26  5855.0 1014.66
#Mann=6,-1,0
  4717.8    0.12       0  5008.4    0.05       0  5012.4    0.12       0
  5493.5    0.07       0  5514.7    0.12       0  5706.0    0.07       0
Bank Sta=5008.4,5012.4
Exp/Cntr=0.3,0.1

Type RM Length L Ch R = 1,7035,493,493,493
BEGIN DESCRIPTION:
Upper Dry Comal Tributary 10 15.0
END DESCRIPTION:
XS GIS Cut Line= 3
      2214174.99     13823674.98      2213975.00     13823325.00
      2213175.05     13823275.00
#Sta/Elev= 30
  4596.9  996.71  4648.0  994.44  4669.6  994.24  4695.2  993.11  4728.6  991.80
  4781.2  988.58  4787.6  987.81  4825.1  985.88  4874.0  984.30  4919.4  981.72
  4927.3  981.66  4933.0  982.29  4970.5  981.29  4995.0  979.63  4995.3  979.13
  4999.0  979.13  4999.2  979.63  5020.0  980.45  5040.1  982.08  5090.2  984.17
  5200.4  986.35  5290.6  987.17  5420.8  992.77  5466.9  995.26  5558.6  998.99
  5571.1  999.02  5626.3 1001.12  5711.4 1004.94  5757.2 1006.47  5801.5 1008.50
#Mann=7,-1,0
  4596.9   0.035       0  4695.2    0.12       0  4995.0    0.05       0
  4999.2    0.12       0  5466.9    0.07       0  5626.3    0.12       0
  5757.2    0.07       0
Bank Sta=4995,4999.2
Exp/Cntr=0.3,0.1

Type RM Length L Ch R = 1,6542,483,483,483
BEGIN DESCRIPTION:
Upper Dry Comal Tributary 10 14.0
END DESCRIPTION:
XS GIS Cut Line= 3
      2214593.96     13823092.14      2214325.00     13822975.00
      2213524.99     13822875.00
#Sta/Elev= 30
  4702.6 1005.57  4707.4 1005.82  4723.3 1004.03  4736.3 1004.23  4799.6 1001.46
  4843.3  997.39  4876.0  995.30  4952.3  986.59  4958.1  984.74  4974.1  982.01
  4987.0  980.93  4993.2  979.72  4998.5  979.72  5006.0  977.38  5013.9  976.79
  5014.2  976.29  5018.4  976.79  5086.7  978.79  5119.4  980.42  5177.6  979.27
  5195.0  978.60  5280.7  978.74  5361.3  979.90  5436.9  983.52  5441.9  983.09
  5520.3  984.70  5585.7  987.05  5678.7  992.07  5683.8  991.59  5802.2  995.67
#Mann=6,-1,0
  4702.6    0.12       0  5013.9    0.05       0  5018.4    0.12       0
  5177.6   0.035       0  5520.3    0.07       0  5585.7    0.12       0
Bank Sta=5013.9,5018.4
Exp/Cntr=0.3,0.1

Type RM Length L Ch R = 1,6059,461,461,461
BEGIN DESCRIPTION:
Upper Dry Comal Tributary 10 13.0
END DESCRIPTION:
XS GIS Cut Line= 3
      2214693.79     13822519.21      2214225.00     13822525.00
      2213424.99     13822475.00
#Sta/Elev= 30
  4526.0 1008.52  4584.8 1006.58  4594.8 1006.81  4644.8 1004.69  4704.8 1000.97
  4794.8  994.26  4864.8  987.28  4874.8  985.28  4904.8  981.32  4954.8  977.49
  4984.8  973.25  4990.1  972.93  4990.4  972.43  4994.3  972.43  4994.6  972.93
  5034.9  973.38  5054.9  973.10  5115.1  975.99  5155.1  977.44  5167.4  977.42
  5265.4  980.08  5295.4  980.11  5365.6  981.36  5393.1  982.47  5525.6  985.52
  5586.0  987.68  5606.0  988.85  5651.5  992.70  5748.5 1000.25  5796.4 1003.17
#Mann=7,-1,0
  4526.0    0.12       0  4990.1    0.05       0  4994.6    0.12       0
  5167.4    0.07       0  5525.6   0.035       0  5651.5    0.07       0
  5748.5    0.12       0
Bank Sta=4990.1,4994.6
Exp/Cntr=0.3,0.1

Type RM Length L Ch R = 1,5598,482,482,482
BEGIN DESCRIPTION:
Upper Dry Comal Tributary 10 12.0
END DESCRIPTION:
XS GIS Cut Line= 3
      2214425.01     13822125.00      2214025.00     13822125.00
      2213625.03     13822324.99
#Sta/Elev= 30
  4604.6  986.45  4644.6  985.47  4774.6  980.09  4854.6  977.51  4914.6  973.97
  4954.6  970.27  4982.3  969.34  4982.7  968.84  4986.6  968.84  4986.9  969.34
  5002.1  970.29  5013.0  969.88  5049.3  972.61  5061.4  972.68  5066.5  972.90
  5116.4  974.77  5175.1  977.75  5183.5  977.68  5197.5  978.29  5210.8  979.49
  5236.6  981.09  5242.2  980.98  5272.9  982.27  5303.7  982.85  5309.3  983.37
  5370.8  984.19  5391.7  985.09  5407.1  985.76  5421.1  986.90  5451.8  988.09
#Mann=7,-1,0
  4604.6    0.12       0  4982.3    0.05       0  4986.9    0.12       0
  5061.4    0.07       0  5066.5   0.035       0  5210.8    0.07       0
  5391.7   0.035       0
Bank Sta=4982.3,4986.9
Exp/Cntr=0.3,0.1

Type RM Length L Ch R = 1,5116,463,463,463
BEGIN DESCRIPTION:
Upper Dry Comal Tributary 10 11.0
END DESCRIPTION:
XS GIS Cut Line= 3
      2214724.99     13822224.99      2213925.00     13821675.00
      2213525.03     13821725.00
#Sta/Elev= 30
  4029.7  999.36  4052.0  997.91  4165.7  994.02  4246.2  990.70  4296.7  988.07
  4418.0  984.95  4440.4  984.80  4539.4  981.58  4568.9  981.24  4598.7  978.96
  4706.2  975.04  4847.9  972.78  4923.9  971.10  4957.2  970.24  4987.0  968.71
  5035.0  968.91  5071.1  969.52  5109.1  968.19  5109.4  967.69  5113.4  967.69
  5113.7  968.19  5151.7  971.95  5181.9  976.53  5199.6  978.46  5204.6  978.23
  5242.4  979.63  5316.1  983.74  5343.2  984.40  5383.5  987.29  5403.6  987.93
#Mann=7,-1,0
  4029.7    0.12       0  4847.9   0.035       0  4923.9    0.07       0
  5035.0    0.12       0  5109.1    0.05       0  5113.7    0.12       0
  5316.1    0.07       0
Bank Sta=5109.1,5113.7
Exp/Cntr=0.3,0.1

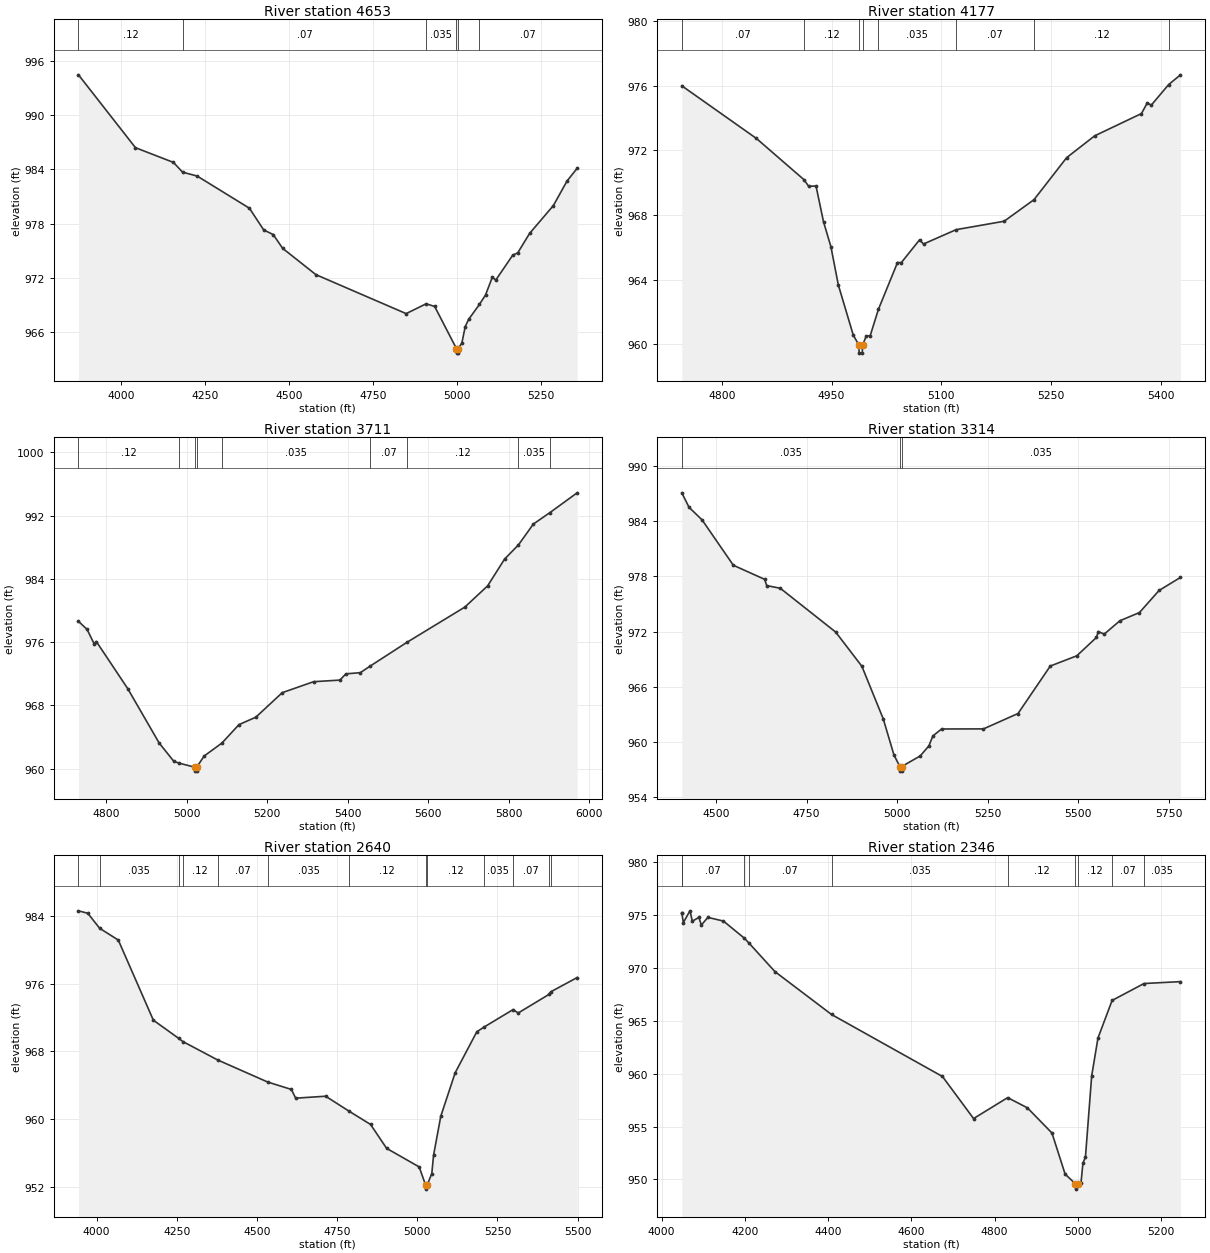
Type RM Length L Ch R = 1,4653,476,476,476
BEGIN DESCRIPTION:
Upper Dry Comal Tributary 10 10.0
END DESCRIPTION:
XS GIS Cut Line= 3
      2214724.99     13822074.99      2213925.00     13821275.00
      2213575.01     13821325.00
#Sta/Elev= 30
  3873.0  994.47  4042.7  986.41  4155.8  984.78  4183.0  983.70  4226.5  983.27
  4382.1  979.71  4424.5  977.31  4452.8  976.80  4481.1  975.27  4580.1  972.36
  4848.8  968.05  4908.3  969.14  4933.7  968.84  4998.5  964.18  4998.8  963.68
  5002.8  963.68  5003.2  964.18  5014.5  964.77  5024.6  966.61  5034.7  967.41
  5066.8  969.06  5085.2  970.12  5105.4  972.09  5115.5  971.76  5166.0  974.51
  5181.1  974.78  5216.5  976.93  5287.2  980.01  5327.6  982.71  5357.9  984.13
#Mann=6,-1,0
  3873.0    0.12       0  4183.0    0.07       0  4908.3   0.035       0
  4998.5   0.035       0  5003.2   0.035       0  5066.8    0.07       0
Bank Sta=4998.5,5003.2
Exp/Cntr=0.3,0.1

Type RM Length L Ch R = 1,4177,466,466,466
BEGIN DESCRIPTION:
Upper Dry Comal Tributary 10 9.0
END DESCRIPTION:
XS GIS Cut Line= 3
      2214374.99     13820825.00      2214125.00     13820875.00
      2213725.04     13821024.99
#Sta/Elev= 30
  4745.1  976.00  4847.1  972.74  4912.3  970.18  4918.5  969.78  4928.7  969.79
  4938.9  967.58  4949.0  966.04  4959.2  963.66  4979.6  960.56  4987.3  959.94
  4987.7  959.44  4991.9  959.44  4992.3  959.94  4997.5  960.51  5002.7  960.51
  5014.0  962.15  5040.1  965.05  5045.4  965.05  5070.3  966.46  5075.7  966.20
  5120.4  967.09  5186.0  967.61  5226.9  968.95  5271.5  971.55  5309.8  972.90
  5373.8  974.28  5381.8  974.94  5387.2  974.80  5411.1  976.08  5427.2  976.68
#Mann=8,-1,0
  4745.1    0.07       0  4912.3    0.12       0  4987.3    0.05       0
  4992.3    0.12       0  5014.0   0.035       0  5120.4    0.07       0
  5226.9    0.12       0  5411.1    0.07       0
Bank Sta=4987.3,4992.3
Exp/Cntr=0.3,0.1

Type RM Length L Ch R = 1,3711,397,397,397
BEGIN DESCRIPTION:
Upper Dry Comal Tributary 10 8.0
END DESCRIPTION:
XS GIS Cut Line= 3
      2214324.97     13820325.01      2214075.00     13820425.00
      2213275.04     13820974.97
#Sta/Elev= 30
  4730.4  978.62  4751.9  977.59  4769.4  975.77  4774.8  976.07  4852.9  970.11
  4931.0  963.24  4967.3  960.93  4980.4  960.69  5019.5  960.18  5019.8  959.68
  5024.1  959.68  5024.5  960.18  5042.9  961.59  5087.1  963.23  5129.5  965.56
  5171.4  966.50  5237.1  969.60  5315.1  970.99  5380.5  971.19  5395.4  971.98
  5431.3  972.13  5455.7  972.96  5547.3  975.97  5691.1  980.42  5747.9  983.11
  5789.8  986.48  5824.5  988.29  5861.5  990.92  5903.0  992.38  5970.4  994.87
#Mann=9,-1,0
  4730.4    0.12       0  4980.4    0.07       0  5019.5    0.05       0
  5024.5    0.07       0  5087.1   0.035       0  5455.7    0.07       0
  5547.3    0.12       0  5824.5   0.035       0  5903.0    0.12       0
Bank Sta=5019.5,5024.5
Exp/Cntr=0.3,0.1

Type RM Length L Ch R = 1,3314,674,674,674
BEGIN DESCRIPTION:
Upper Dry Comal Tributary 10 7.0
END DESCRIPTION:
XS GIS Cut Line= 3
      2214446.82     13819871.88      2213785.91     13820139.64
      2213169.49     13820383.50
#Sta/Elev= 30
  4405.8  987.07  4425.7  985.50  4461.7  984.13  4548.0  979.20  4634.3  977.67
  4640.1  976.99  4677.5  976.70  4830.4  971.94  4902.7  968.22  4961.7  962.50
  4991.2  958.58  5007.4  957.33  5007.8  956.83  5012.1  956.83  5012.5  957.33
  5063.6  958.48  5087.5  959.57  5098.5  960.65  5122.6  961.41  5238.2  961.42
  5333.5  963.09  5422.6  968.25  5495.7  969.36  5549.7  971.35  5555.1  971.99
  5571.5  971.72  5614.6  973.17  5668.6  974.06  5722.7  976.46  5781.8  977.88
#Mann=3,-1,0
  4405.8   0.035       0  5007.4   0.035       0  5012.5   0.035       0
Bank Sta=5007.4,5012.5
Exp/Cntr=0.3,0.1

Type RM Length L Ch R = 1,2640,294,294,294
BEGIN DESCRIPTION:
Upper Dry Comal Tributary 10 6.0
END DESCRIPTION:
XS GIS Cut Line= 3
      2214224.96     13819425.02      2213333.42     13819962.73
      2212872.46     13820189.82
#Sta/Elev= 30
  3943.4  984.59  3972.5  984.30  4009.5  982.53  4067.6  981.14  4176.9  971.69
  4255.7  969.55  4269.4  969.16  4377.3  967.00  4533.6  964.39  4607.3  963.52
  4620.7  962.49  4714.1  962.72  4787.4  960.95  4854.2  959.39  4904.3  956.57
  5005.8  954.38  5025.7  952.26  5026.1  951.76  5030.9  952.26  5045.2  953.60
  5050.7  955.76  5073.2  960.36  5118.1  965.49  5185.5  970.32  5207.0  970.85
  5298.6  972.94  5314.7  972.54  5410.1  974.72  5416.9  975.05  5498.4  976.72
#Mann=13,-1,0
  3943.4    0.07       0  4009.5   0.035       0  4255.7    0.07       0
  4269.4    0.12       0  4377.3    0.07       0  4533.6   0.035       0
  4787.4    0.12       0  5025.7    0.05       0  5030.9    0.12       0
  5207.0   0.035       0  5298.6    0.07       0  5410.1    0.12       0
  5416.9    0.07       0
Bank Sta=5025.7,5030.9
Exp/Cntr=0.3,0.1

Type RM Length L Ch R = 1,2346,426,426,426
BEGIN DESCRIPTION:
Upper Dry Comal Tributary 10 5.0
END DESCRIPTION:
XS GIS Cut Line= 3
      2213953.67     13819298.40      2213125.00     13819775.00
      2212923.32     13819908.48
#Sta/Elev= 30
  4048.6  975.20  4048.7  975.18  4052.3  974.31  4068.1  975.42  4073.9  974.44
  4089.7  974.80  4095.4  974.07  4111.2  974.80  4148.6  974.45  4198.8  972.83
  4209.9  972.37  4272.2  969.67  4408.2  965.61  4674.7  959.74  4749.4  955.76
  4831.3  957.74  4878.8  956.77  4937.7  954.39  4969.3  950.50  4994.1  949.58
  4994.5  949.08  4999.3  949.58  5007.5  949.70  5012.1  951.54  5018.1  952.10
  5033.1  959.80  5048.2  963.38  5082.2  966.94  5158.8  968.54  5246.4  968.72
#Mann=10,-1,0
  4048.6   0.035       0  4048.7    0.07       0  4198.8    0.12       0
  4209.9    0.07       0  4408.2   0.035       0  4831.3    0.12       0
  4994.1    0.05       0  4999.3    0.12       0  5082.2    0.07       0
  5158.8   0.035       0
Bank Sta=4994.1,4999.3
Exp/Cntr=0.3,0.1

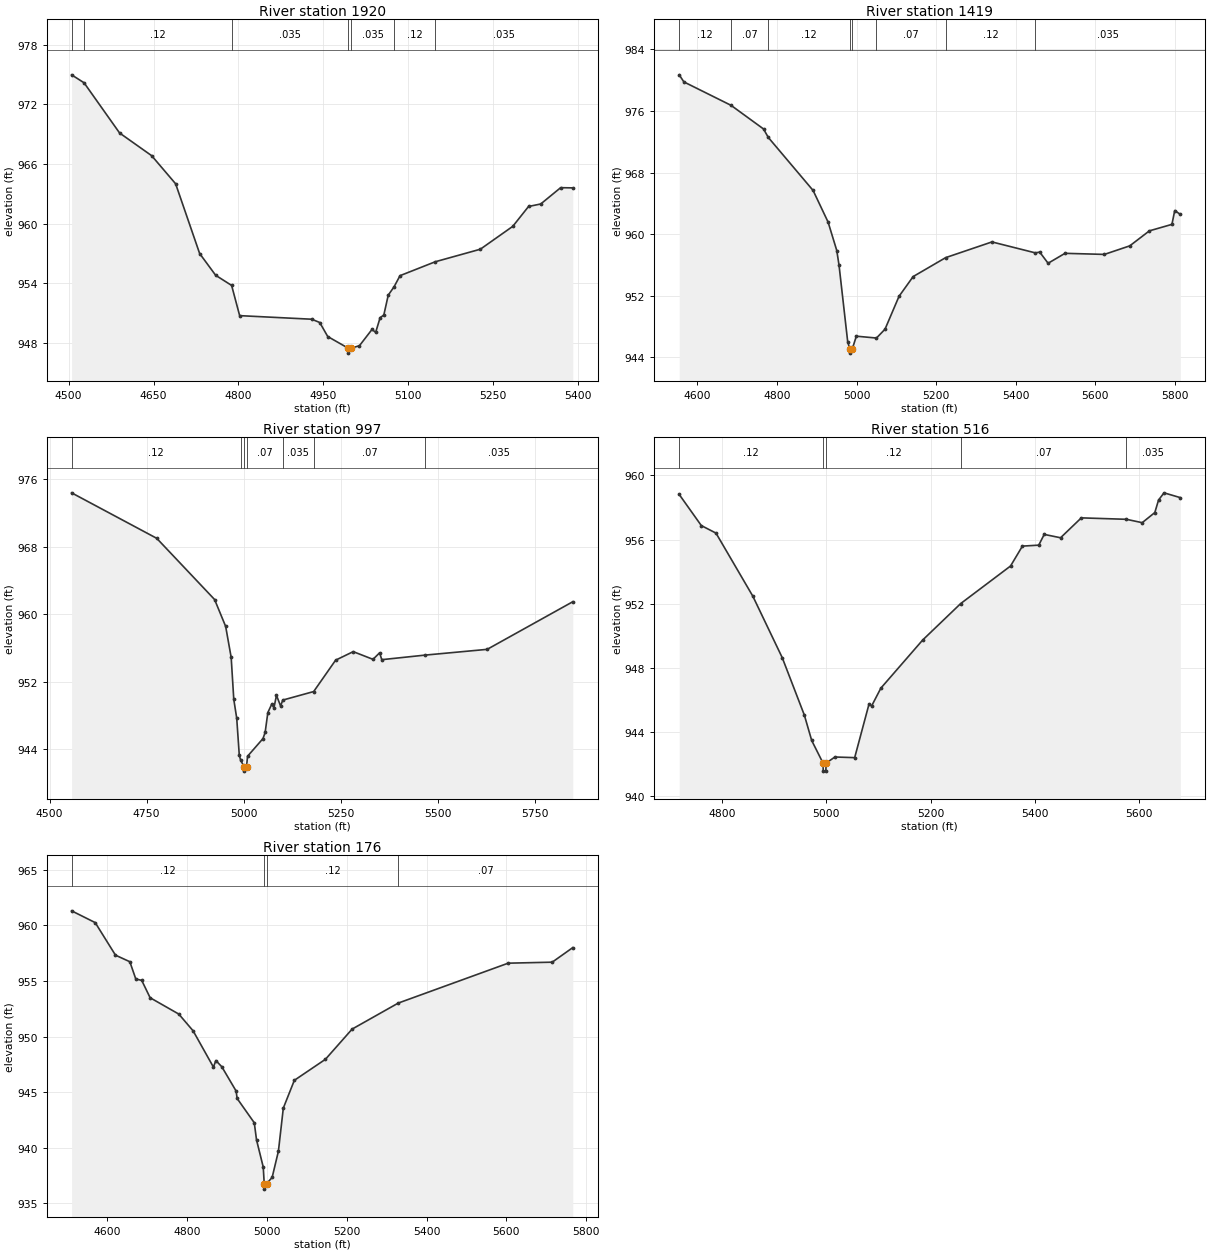
Type RM Length L Ch R = 1,1920,501,501,501
BEGIN DESCRIPTION:
Upper Dry Comal Tributary 10 4.0
END DESCRIPTION:
XS GIS Cut Line= 3
      2213474.97     13819025.03      2213125.00     13819375.00
      2212825.04     13819624.97
#Sta/Elev= 30
  4505.2  974.96  4527.2  974.16  4590.0  969.11  4646.6  966.83  4689.0  964.00
  4731.4  956.99  4759.7  954.80  4787.9  953.78  4802.1  950.74  4929.4  950.38
  4943.6  950.05  4957.7  948.64  4993.8  947.47  4994.3  946.97  4999.4  947.47
  5013.8  947.72  5035.9  949.35  5042.4  949.06  5050.3  950.54  5056.8  950.80
  5064.6  952.80  5075.0  953.65  5085.4  954.76  5147.7  956.16  5227.3  957.42
  5284.6  959.72  5312.5  961.72  5334.0  961.97  5369.2  963.61  5390.6  963.59
#Mann=7,-1,0
  4505.2    0.07       0  4527.2    0.12       0  4787.9   0.035       0
  4993.8   0.035       0  4999.4   0.035       0  5075.0    0.12       0
  5147.7   0.035       0
Bank Sta=4993.8,4999.4
Exp/Cntr=0.3,0.1

Type RM Length L Ch R = 1,1419,422,422,422
BEGIN DESCRIPTION:
Upper Dry Comal Tributary 10 3.0
END DESCRIPTION:
XS GIS Cut Line= 3
      2213482.60     13818725.54      2213085.99     13818945.88
      2212524.99     13819525.01
#Sta/Elev= 30
  4554.2  980.70  4566.0  979.78  4684.5  976.74  4766.2  973.67  4778.2  972.57
  4890.9  965.68  4928.6  961.57  4950.4  957.88  4956.1  955.96  4977.8  946.06
  4983.3  945.06  4983.8  944.56  4989.1  945.06  4999.6  946.76  5050.2  946.52
  5071.7  947.67  5106.9  951.94  5142.4  954.50  5224.1  956.96  5340.5  959.00
  5449.6  957.58  5460.6  957.68  5481.7  956.23  5524.2  957.52  5623.2  957.38
  5687.0  958.49  5736.4  960.44  5793.0  961.28  5800.1  963.08  5814.2  962.57
#Mann=8,-1,0
  4554.2    0.12       0  4684.5    0.07       0  4778.2    0.12       0
  4983.3    0.05       0  4989.1    0.12       0  5050.2    0.07       0
  5224.1    0.12       0  5449.6   0.035       0
Bank Sta=4983.3,4989.1
Exp/Cntr=0.3,0.1

Type RM Length L Ch R = 1,997,481,481,481
BEGIN DESCRIPTION:
Upper Dry Comal Tributary 10 2.0
END DESCRIPTION:
XS GIS Cut Line= 3
      2213106.31     13818386.62      2212775.00     13818675.00
      2212408.09     13819444.13
#Sta/Elev= 30
  4556.6  974.35  4776.0  968.97  4925.1  961.73  4953.6  958.55  4967.8  954.89
  4974.5  949.93  4982.1  947.69  4988.7  943.32  4992.3  942.72  5001.5  941.94
  5002.0  941.44  5007.3  941.94  5010.0  943.20  5049.8  945.29  5055.3  946.01
  5062.3  948.37  5072.5  949.37  5078.0  948.92  5084.5  950.40  5095.2  949.14
  5100.7  949.84  5180.4  950.85  5236.9  954.56  5282.3  955.57  5333.2  954.66
  5350.3  955.43  5355.9  954.62  5467.5  955.16  5627.4  955.84  5848.0  961.47
#Mann=7,-1,0
  4556.6    0.12       0  4992.3    0.07       0  5001.5    0.05       0
  5007.3    0.07       0  5100.7   0.035       0  5180.4    0.07       0
  5467.5   0.035       0
Bank Sta=5001.5,5007.3
Exp/Cntr=0.3,0.1

Type RM Length L Ch R = 1,516,340,340,340
BEGIN DESCRIPTION:
Upper Dry Comal Tributary 10 1.0
END DESCRIPTION:
XS GIS Cut Line= 3
      2212525.03     13818374.97      2212325.00     13818575.00
      2212124.99     13819225.04
#Sta/Elev= 30
  4717.1  958.82  4759.6  956.88  4787.8  956.41  4858.6  952.48  4915.1  948.65
  4957.6  945.07  4971.7  943.49  4993.5  942.08  4993.9  941.58  4998.9  941.58
  4999.4  942.08  5016.3  942.46  5054.3  942.42  5081.7  945.74  5087.0  945.65
  5104.6  946.75  5185.0  949.75  5258.0  952.02  5353.8  954.36  5376.6  955.60
  5408.0  955.66  5418.5  956.33  5449.9  956.12  5489.8  957.36  5576.5  957.27
  5606.8  957.06  5631.0  957.69  5638.2  958.47  5648.7  958.92  5680.1  958.62
#Mann=5,-1,0
  4717.1    0.12       0  4993.5    0.05       0  4999.4    0.12       0
  5258.0    0.07       0  5576.5   0.035       0
Bank Sta=4993.5,4999.4
Exp/Cntr=0.3,0.1

Type RM Length L Ch R = 1,176,0,0,0
BEGIN DESCRIPTION:
XS7883
END DESCRIPTION:
XS GIS Cut Line= 4
      2212441.97     13818118.85      2212099.64     13818352.72
      2212035.24     13818481.52      2212079.30     13819176.33
#Sta/Elev= 30
  4511.3  961.32  4570.4  960.26  4621.2  957.33  4657.1  956.74  4672.0  955.19
  4686.9  955.06  4707.9  953.50  4779.7  952.03  4815.6  950.52  4866.4  947.26
  4872.5  947.85  4887.4  947.29  4923.3  945.10  4925.7  944.44  4968.7  942.25
  4974.3  940.71  4991.1  938.27  4993.6  936.78  4994.1  936.28  4999.6  936.78
  5013.4  937.33  5029.1  939.69  5041.4  943.57  5069.0  946.07  5146.8  947.96
  5213.7  950.68  5329.2  953.02  5604.4  956.61  5714.7  956.70  5766.1  958.01
#Mann=4,-1,0
  4511.3    0.12       0  4993.6    0.05       0  4999.6    0.12       0
  5329.2    0.07       0
Bank Sta=4993.6,4999.6
Exp/Cntr=0.3,0.1

Chan Stop Cuts=-1