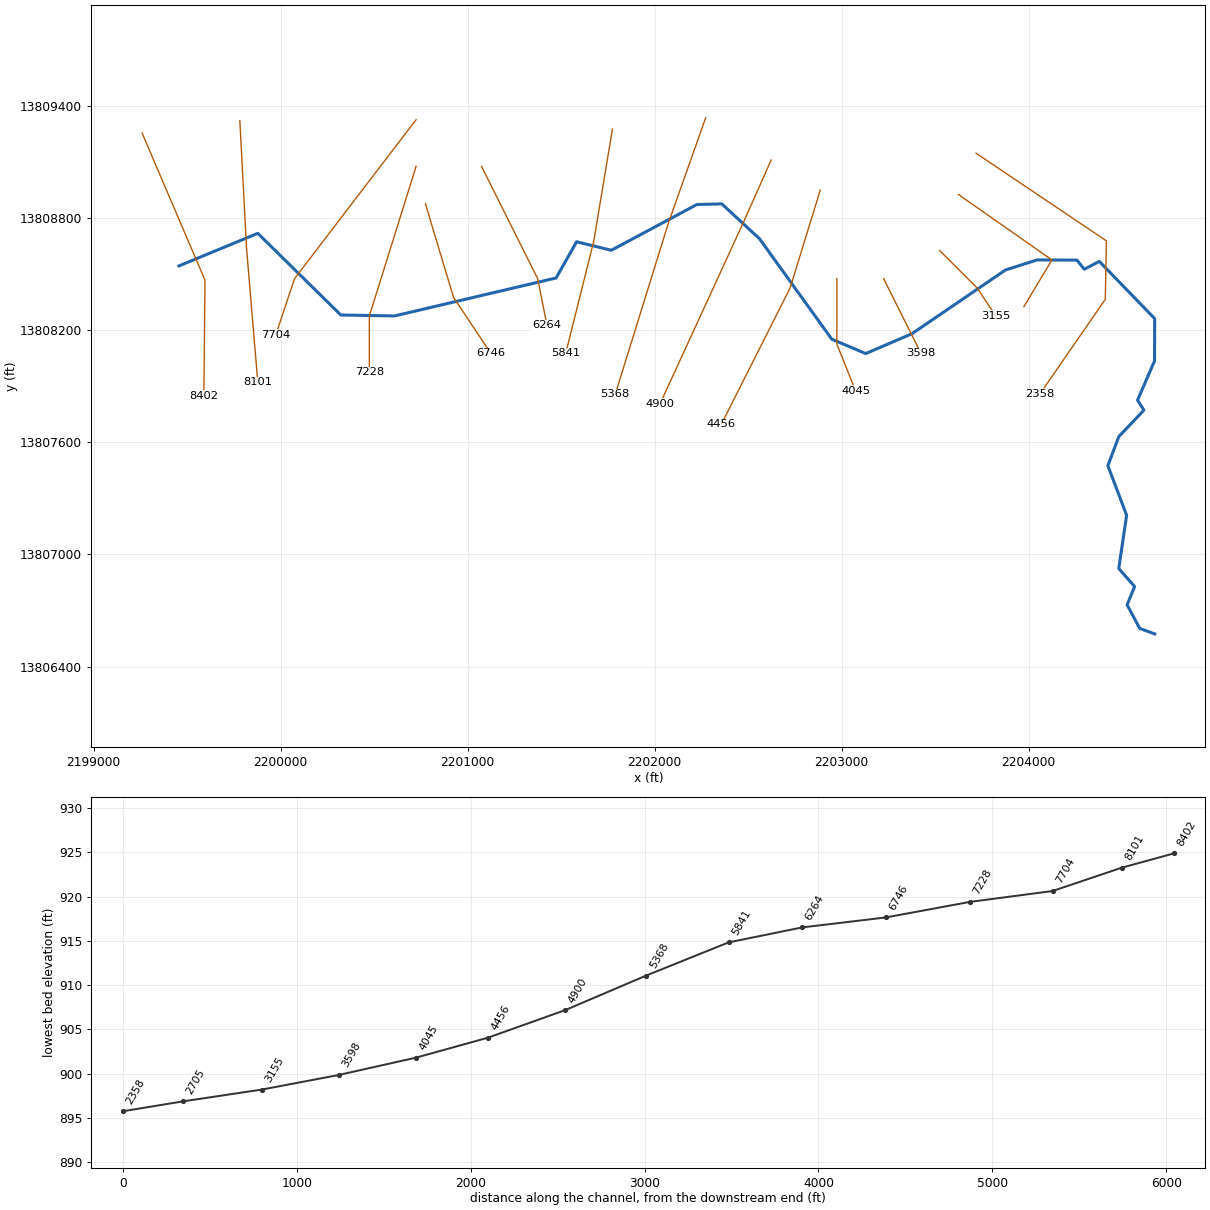
--- Upper Dry Comal Tributary 12.prj (project) ---

Proj Title=Upper Dry Comal Tributary 12 Base Level Engineering
Current Plan=p01
Default Exp/Contr=0.3,0.1
English Units
Geom File=g01
Flow File=f01
Plan File=p01
BEGIN DESCRIPTION:
Upper Dry Comal Tributary 12
END DESCRIPTION:

--- Upper Dry Comal Tributary 12.p01 (plan) ---

Plan Title=Multiple Run
Short Identifier=Multiple
Geom File=g01
Flow File=f01
Subcritical Flow
K Sum by GR= 0
Std Step Tol= 0.01
Critical Tol= 0.01
Num of Std Step Trials= 20
Max Error Tol= 0.3
Flow Tol Ratio= 0.001
Split Flow NTrial= 30
Split Flow Tol= 0.02
Split Flow Ratio= 0.02
Log Output Level= 0
Friction Slope Method= 1
Unsteady Friction Slope Method= 2
Unsteady Bridges Friction Slope Method= 1
Parabolic Critical Depth
Global Vel Dist=  1 , 1 , 1
Global Log Level= 0
CheckData=True
Encroach Param= -1, 0, 0, 0
BEGIN DESCRIPTION:
Multiple Run
END DESCRIPTION:

--- Upper Dry Comal Tributary 12.f01 (steady flow) ---

Flow Title=Multiple
Number of Profiles=7
Profile Names=10-year,25-year,50-year,1pct_min,100-year,1pct_plu,500-year
River Rch & RM= Upper Dry Comal ,Reach-1,8402
     562     894    1189     767    1530    3052    2502
Boundary for River Rch & Prof#=Upper Dry Comal ,Reach-1,1
Up Type=0
Dn Type=3
Dn Slope=0.005
Boundary for River Rch & Prof#=Upper Dry Comal ,Reach-1,2
Up Type=0
Dn Type=3
Dn Slope=0.005
Boundary for River Rch & Prof#=Upper Dry Comal ,Reach-1,3
Up Type=0
Dn Type=3
Dn Slope=0.005
Boundary for River Rch & Prof#=Upper Dry Comal ,Reach-1,4
Up Type=0
Dn Type=3
Dn Slope=0.005
Boundary for River Rch & Prof#=Upper Dry Comal ,Reach-1,5
Up Type=0
Dn Type=3
Dn Slope=0.005
Boundary for River Rch & Prof#=Upper Dry Comal ,Reach-1,6
Up Type=0
Dn Type=3
Dn Slope=0.005
Boundary for River Rch & Prof#=Upper Dry Comal ,Reach-1,7
Up Type=0
Dn Type=3
Dn Slope=0.005

--- Upper Dry Comal Tributary 12.g01 (geometry) ---

Geom Title=Existing Conditions

River Reach=Upper Dry Comal ,Reach-1
Reach XY= 30
      2199457.07     13808542.93      2199878.43     13808717.21
      2200322.55     13808280.46      2200609.78     13808275.52
      2201473.72     13808478.52      2201583.32     13808672.03
      2201768.96     13808626.63      2202226.56     13808871.26
      2202359.84     13808874.64      2202561.37     13808688.21
      2202947.86     13808151.16      2203129.57     13808074.19
      2203377.29     13808180.85      2203876.58     13808521.17
      2204045.03     13808574.93      2204259.06     13808574.00
      2204297.92     13808524.85      2204378.39     13808567.17
      2204674.47     13808261.14      2204673.62     13808034.66
      2204582.80     13807824.90      2204617.01     13807771.66
      2204483.14     13807631.06      2204424.18     13807475.00
      2204524.48     13807209.78      2204482.34     13806924.90
      2204567.15     13806828.41      2204526.95     13806730.72
      2204594.50     13806604.53      2204675.00     13806575.00

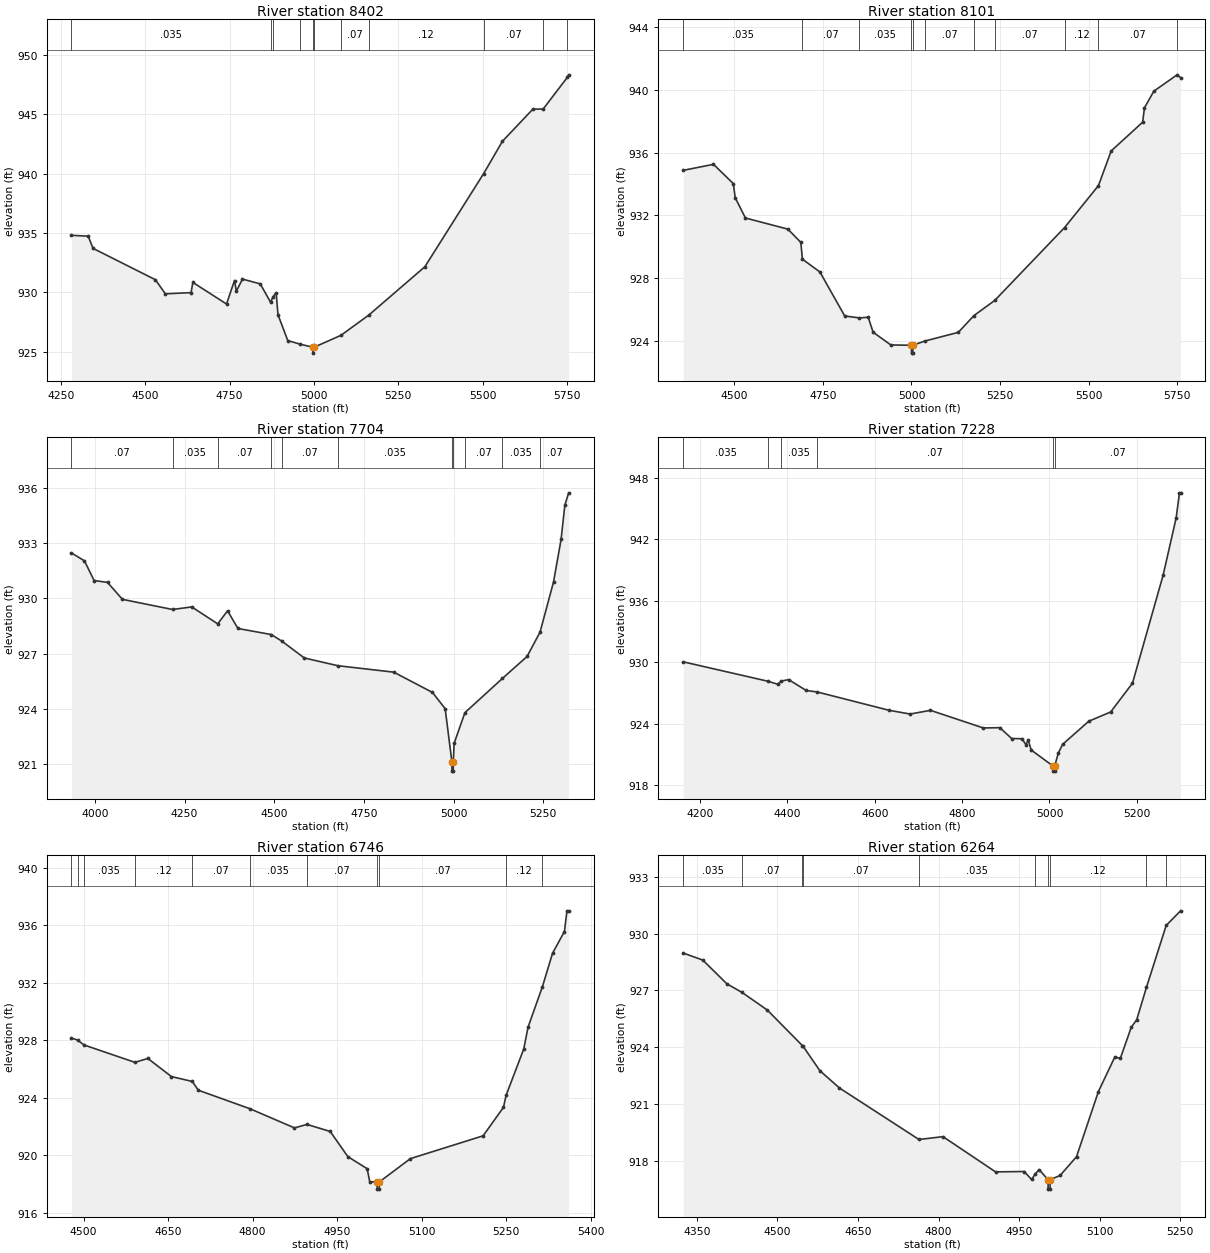
Type RM Length L Ch R = 1,8402,301,301,301
BEGIN DESCRIPTION:
XS7884
END DESCRIPTION:
XS GIS Cut Line= 3
      2199259.63     13809253.90      2199596.19     13808466.58
      2199590.19     13807848.75
#Sta/Elev= 30
  4281.0  934.80  4330.8  934.73  4345.1  933.70  4529.9  931.06  4559.5  929.87
  4635.7  929.97  4641.1  930.83  4740.9  929.01  4764.5  930.99  4770.0  930.09
  4788.1  931.11  4840.8  930.71  4871.4  929.16  4879.2  929.64  4888.0  929.96
  4893.4  928.11  4922.4  925.93  4959.5  925.62  4996.7  925.37  4996.9  924.87
  5000.7  925.37  5080.1  926.37  5162.3  928.07  5328.8  932.15  5503.0  940.00
  5558.8  942.73  5648.8  945.43  5679.6  945.45  5751.3  948.12  5755.1  948.33
#Mann=11,-1,0
  4281.0   0.035       0  4871.4    0.07       0  4879.2   0.035       0
  4959.5    0.12       0  4996.7    0.05       0  5000.7    0.12       0
  5080.1    0.07       0  5162.3    0.12       0  5503.0    0.07       0
  5679.6    0.12       0  5751.3    0.07       0
Bank Sta=4996.7,5000.7
Exp/Cntr=0.3,0.1

Type RM Length L Ch R = 1,8101,397,397,397
BEGIN DESCRIPTION:
Upper Dry Comal Tributary 12 13.0
END DESCRIPTION:
XS GIS Cut Line= 3
      2199782.50     13809320.03      2199818.56     13808634.87
      2199878.65     13807919.80
#Sta/Elev= 30
  4355.9  934.87  4441.1  935.25  4497.3  934.02  4502.3  933.14  4531.2  931.84
  4651.3  931.13  4687.6  930.29  4692.2  929.22  4741.5  928.41  4811.6  925.61
  4852.9  925.49  4877.9  925.53  4891.7  924.58  4941.7  923.77  4999.8  923.75
  5000.1  923.25  5003.6  923.25  5003.8  923.75  5038.1  924.02  5132.2  924.57
  5176.6  925.64  5235.1  926.60  5432.1  931.23  5527.9  933.90  5563.7  936.10
  5652.6  937.93  5657.7  938.84  5684.1  939.90  5749.9  940.94  5759.6  940.77
#Mann=11,-1,0
  4355.9   0.035       0  4692.2    0.07       0  4852.9   0.035       0
  4999.8   0.035       0  5003.8   0.035       0  5038.1    0.07       0
  5176.6   0.035       0  5235.1    0.07       0  5432.1    0.12       0
  5527.9    0.07       0  5749.9    0.12       0
Bank Sta=4999.8,5003.8
Exp/Cntr=0.3,0.1

Type RM Length L Ch R = 1,7704,476,476,476
BEGIN DESCRIPTION:
Upper Dry Comal Tributary 12 12.0
END DESCRIPTION:
XS GIS Cut Line= 3
      2200724.99     13809324.99      2200075.00     13808475.00
      2199974.99     13808174.97
#Sta/Elev= 30
  3934.5  932.46  3970.8  932.03  3997.9  930.96  4035.2  930.86  4076.8  929.94
  4216.5  929.39  4270.0  929.53  4342.4  928.61  4369.8  929.32  4398.8  928.36
  4491.7  928.03  4520.7  927.68  4583.8  926.76  4677.2  926.34  4833.1  925.99
  4941.1  924.89  4976.5  924.01  4995.3  921.12  4995.5  920.62  4999.0  920.62
  4999.3  921.12  5001.4  922.12  5031.5  923.79  5136.2  925.65  5204.8  926.84
  5241.0  928.16  5278.6  930.88  5299.7  933.19  5310.2  935.05  5320.8  935.72
#Mann=11,-1,0
  3934.5    0.07       0  4216.5   0.035       0  4342.4    0.07       0
  4491.7   0.035       0  4520.7    0.07       0  4677.2   0.035       0
  4995.3   0.035       0  4999.3   0.035       0  5031.5    0.07       0
  5136.2   0.035       0  5241.0    0.07       0
Bank Sta=4995.3,4999.3
Exp/Cntr=0.3,0.1

Type RM Length L Ch R = 1,7228,482,482,482
BEGIN DESCRIPTION:
Upper Dry Comal Tributary 12 11.0
END DESCRIPTION:
XS GIS Cut Line= 3
      2200725.01     13809075.03      2200475.00     13808275.00
      2200475.00     13807974.98
#Sta/Elev= 30
  4161.8  930.05  4355.4  928.16  4378.2  927.86  4386.1  928.17  4402.8  928.32
  4443.1  927.26  4468.5  927.11  4633.3  925.32  4681.0  924.96  4727.6  925.32
  4848.6  923.60  4886.3  923.63  4913.5  922.57  4937.1  922.55  4946.0  921.97
  4951.3  922.42  4958.1  921.45  5008.0  919.89  5008.2  919.39  5011.7  919.39
  5012.0  919.89  5020.0  921.13  5030.0  922.00  5090.0  924.26  5140.0  925.16
  5190.0  927.97  5260.0  938.49  5290.0  944.10  5297.5  946.54  5300.0  946.54
#Mann=6,-1,0
  4161.8   0.035       0  4355.4    0.07       0  4386.1   0.035       0
  4468.5    0.07       0  5008.0    0.05       0  5012.0    0.07       0
Bank Sta=5008,5012
Exp/Cntr=0.3,0.1

Type RM Length L Ch R = 1,6746,482,482,482
BEGIN DESCRIPTION:
Upper Dry Comal Tributary 12 10.0
END DESCRIPTION:
XS GIS Cut Line= 3
      2200775.00     13808874.99      2200925.00     13808375.00
      2201125.02     13808074.97
#Sta/Elev= 30
  4478.4  928.15  4489.3  928.01  4500.7  927.67  4591.1  926.46  4614.1  926.73
  4655.9  925.47  4693.0  925.13  4703.7  924.52  4794.8  923.24  4874.3  921.90
  4896.6  922.14  4937.8  921.65  4969.1  919.90  5003.4  919.06  5007.9  918.15
  5020.9  918.14  5021.2  917.64  5024.7  917.64  5024.9  918.14  5080.0  919.76
  5209.2  921.35  5245.3  923.33  5250.1  924.18  5281.3  927.39  5288.9  928.90
  5314.5  931.73  5332.4  934.05  5353.5  935.56  5358.0  937.00  5361.0  937.00
#Mann=11,-1,0
  4478.4   0.035       0  4489.3    0.07       0  4500.7   0.035       0
  4591.1    0.12       0  4693.0    0.07       0  4794.8   0.035       0
  4896.6    0.07       0  5020.9    0.05       0  5024.9    0.07       0
  5250.1    0.12       0  5314.5    0.07       0
Bank Sta=5020.9,5024.9
Exp/Cntr=0.3,0.1

Type RM Length L Ch R = 1,6264,423,423,423
BEGIN DESCRIPTION:
Upper Dry Comal Tributary 12 9.0
END DESCRIPTION:
XS GIS Cut Line= 3
      2201075.02     13809074.96      2201375.00     13808475.00
      2201424.99     13808225.03
#Sta/Elev= 30
  4324.9  928.97  4361.2  928.60  4405.9  927.35  4434.4  926.89  4481.4  925.96
  4546.8  924.08  4547.9  924.05  4579.2  922.76  4615.5  921.85  4763.6  919.13
  4808.4  919.28  4906.2  917.42  4959.3  917.44  4973.3  917.02  4980.4  917.32
  4987.3  917.54  5003.9  917.01  5004.1  916.51  5007.6  916.51  5007.9  917.01
  5026.3  917.23  5056.9  918.22  5097.7  921.66  5128.3  923.49  5138.5  923.41
  5158.8  925.05  5169.0  925.45  5187.1  927.16  5223.9  930.43  5250.6  931.20
#Mann=10,-1,0
  4324.9   0.035       0  4434.4    0.07       0  4546.8   0.035       0
  4547.9    0.07       0  4763.6   0.035       0  4980.4    0.12       0
  5003.9    0.05       0  5007.9    0.12       0  5187.1    0.07       0
  5223.9    0.12       0
Bank Sta=5003.9,5007.9
Exp/Cntr=0.3,0.1

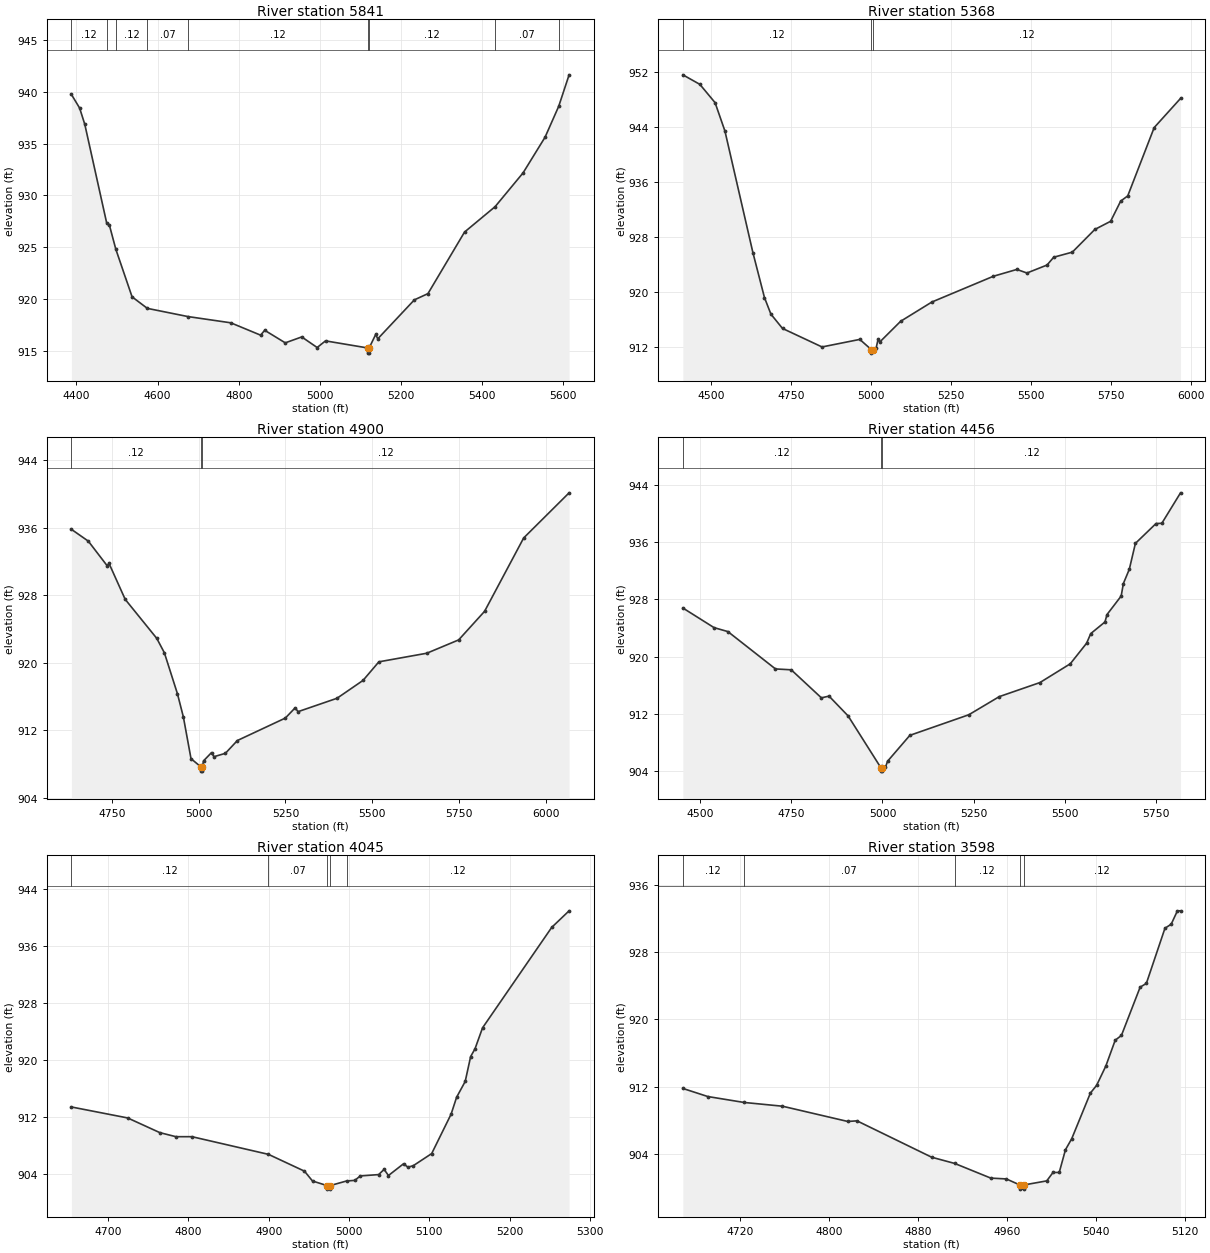
Type RM Length L Ch R = 1,5841,473,473,473
BEGIN DESCRIPTION:
Upper Dry Comal Tributary 12 8.0
END DESCRIPTION:
XS GIS Cut Line= 3
      2201774.99     13809274.97      2201675.00     13808675.00
      2201525.00     13808075.01
#Sta/Elev= 30
  4387.6  939.73  4407.8  938.42  4420.5  936.86  4474.4  927.37  4481.3  927.13
  4497.0  924.83  4537.1  920.24  4574.7  919.13  4674.9  918.34  4780.4  917.74
  4853.9  916.55  4864.0  917.02  4914.7  915.81  4955.3  916.38  4993.3  915.36
  5013.9  916.00  5117.5  915.32  5117.8  914.82  5121.3  914.82  5121.5  915.32
  5137.6  916.62  5142.7  916.20  5232.9  919.95  5266.4  920.55  5356.6  926.48
  5431.8  928.92  5500.9  932.18  5555.0  935.61  5588.7  938.59  5614.3  941.62
#Mann=9,-1,0
  4387.6    0.12       0  4474.4    0.07       0  4497.0    0.12       0
  4574.7    0.07       0  4674.9    0.12       0  5117.5    0.05       0
  5121.5    0.12       0  5431.8    0.07       0  5588.7    0.12       0
Bank Sta=5117.5,5121.5
Exp/Cntr=0.3,0.1

Type RM Length L Ch R = 1,5368,468,468,468
BEGIN DESCRIPTION:
Upper Dry Comal Tributary 12 7.0
END DESCRIPTION:
XS GIS Cut Line= 3
      2202273.61     13809335.16      2202075.00     13808775.00
      2201789.85     13807856.26
#Sta/Elev= 30
  4412.1  951.65  4465.3  950.26  4512.9  947.59  4543.7  943.45  4631.1  925.74
  4667.3  919.18  4687.5  916.76  4723.7  914.68  4847.3  911.98  4965.4  913.08
  5001.8  911.58  5002.0  911.08  5005.8  911.58  5016.9  911.90  5022.7  913.12
  5027.9  912.70  5093.1  915.72  5190.8  918.53  5383.4  922.29  5456.6  923.28
  5488.1  922.76  5550.9  923.92  5571.8  925.06  5630.0  925.80  5700.4  929.11
  5749.8  930.30  5781.2  933.24  5803.3  934.00  5886.0  943.96  5968.4  948.21
#Mann=3,-1,0
  4412.1    0.12       0  5001.8    0.05       0  5005.8    0.12       0
Bank Sta=5001.8,5005.8
Exp/Cntr=0.3,0.1

Type RM Length L Ch R = 1,4900,444,444,444
BEGIN DESCRIPTION:
Upper Dry Comal Tributary 12 6.0
END DESCRIPTION:
XS GIS Cut Line= 3
      2202623.71     13809109.37      2202475.00     13808775.00
      2202029.73     13807806.28
#Sta/Elev= 30
  4634.1  935.83  4682.7  934.43  4736.8  931.52  4742.3  931.79  4788.8  927.53
  4879.7  922.90  4901.5  921.20  4939.2  916.33  4956.3  913.57  4978.2  908.64
  5006.8  907.66  5007.0  907.16  5010.5  907.16  5010.8  907.66  5014.3  908.38
  5037.3  909.36  5044.1  908.87  5077.1  909.27  5111.7  910.79  5249.6  913.45
  5278.0  914.67  5286.2  914.21  5398.4  915.80  5473.3  917.92  5518.8  920.12
  5656.7  921.14  5748.4  922.72  5823.0  926.11  5935.5  934.81  6066.2  940.16
#Mann=3,-1,0
  4634.1    0.12       0  5006.8    0.05       0  5010.8    0.12       0
Bank Sta=5006.8,5010.8
Exp/Cntr=0.3,0.1

Type RM Length L Ch R = 1,4456,411,411,411
BEGIN DESCRIPTION:
Upper Dry Comal Tributary 12 5.0
END DESCRIPTION:
XS GIS Cut Line= 3
      2202886.33     13808948.17      2202725.00     13808425.00
      2202356.50     13807695.01
#Sta/Elev= 30
  4452.5  926.80  4538.1  924.06  4576.0  923.51  4706.6  918.30  4749.8  918.18
  4832.5  914.27  4853.5  914.51  4905.8  911.75  4995.4  904.55  4995.6  904.05
  4999.1  904.05  4999.4  904.55  5008.3  904.58  5013.9  905.42  5075.2  909.04
  5236.9  911.91  5320.5  914.44  5432.0  916.40  5515.3  919.02  5560.1  921.89
  5571.4  923.23  5610.4  924.85  5616.1  925.89  5654.9  928.47  5660.9  930.21
  5677.2  932.20  5693.9  935.81  5750.5  938.58  5766.4  938.61  5817.7  942.86
#Mann=3,-1,0
  4452.5    0.12       0  4995.4    0.05       0  4999.4    0.12       0
Bank Sta=4995.4,4999.4
Exp/Cntr=0.3,0.1

Type RM Length L Ch R = 1,4045,447,447,447
BEGIN DESCRIPTION:
Upper Dry Comal Tributary 12 4.0
END DESCRIPTION:
XS GIS Cut Line= 3
      2202975.00     13808475.03      2202975.00     13808125.00
      2203075.01     13807874.98
#Sta/Elev= 30
  4654.5  913.34  4724.5  911.80  4764.5  909.74  4784.5  909.17  4804.5  909.17
  4899.7  906.69  4944.5  904.33  4954.5  902.95  4972.5  902.31  4972.8  901.81
  4976.3  901.81  4976.5  902.31  4996.8  902.95  5007.2  903.04  5013.9  903.66
  5036.8  903.85  5043.6  904.58  5049.0  903.72  5067.8  905.37  5073.2  904.89
  5079.9  905.10  5102.8  906.80  5127.0  912.34  5133.8  914.70  5144.5  916.92
  5151.3  920.42  5156.7  921.50  5166.1  924.45  5252.2  938.55  5273.8  940.87
#Mann=5,-1,0
  4654.5    0.12       0  4899.7    0.07       0  4972.5    0.05       0
  4976.5    0.07       0  4996.8    0.12       0
Bank Sta=4972.5,4976.5
Exp/Cntr=0.3,0.1

Type RM Length L Ch R = 1,3598,443,443,443
BEGIN DESCRIPTION:
Upper Dry Comal Tributary 12 3.0
END DESCRIPTION:
XS GIS Cut Line= 3
      2203225.00     13808475.01      2203375.00     13808175.00
      2203424.99     13808075.02
#Sta/Elev= 30
  4668.9  911.80  4691.3  910.84  4723.7  910.14  4758.4  909.69  4817.0  907.88
  4825.4  907.95  4892.5  903.63  4913.2  902.89  4945.6  901.15  4959.6  901.05
  4971.6  900.34  4971.8  899.84  4975.3  899.84  4975.6  900.34  4995.9  900.82
  5001.5  901.82  5007.1  901.82  5012.7  904.52  5018.3  905.82  5035.1  911.25
  5040.7  912.17  5049.0  914.47  5057.4  917.53  5063.0  918.10  5079.8  923.83
  5085.4  924.28  5102.1  930.83  5107.7  931.31  5113.3  932.90  5116.1  932.90
#Mann=5,-1,0
  4668.9    0.12       0  4723.7    0.07       0  4913.2    0.12       0
  4971.6    0.05       0  4975.6    0.12       0
Bank Sta=4971.6,4975.6
Exp/Cntr=0.3,0.1

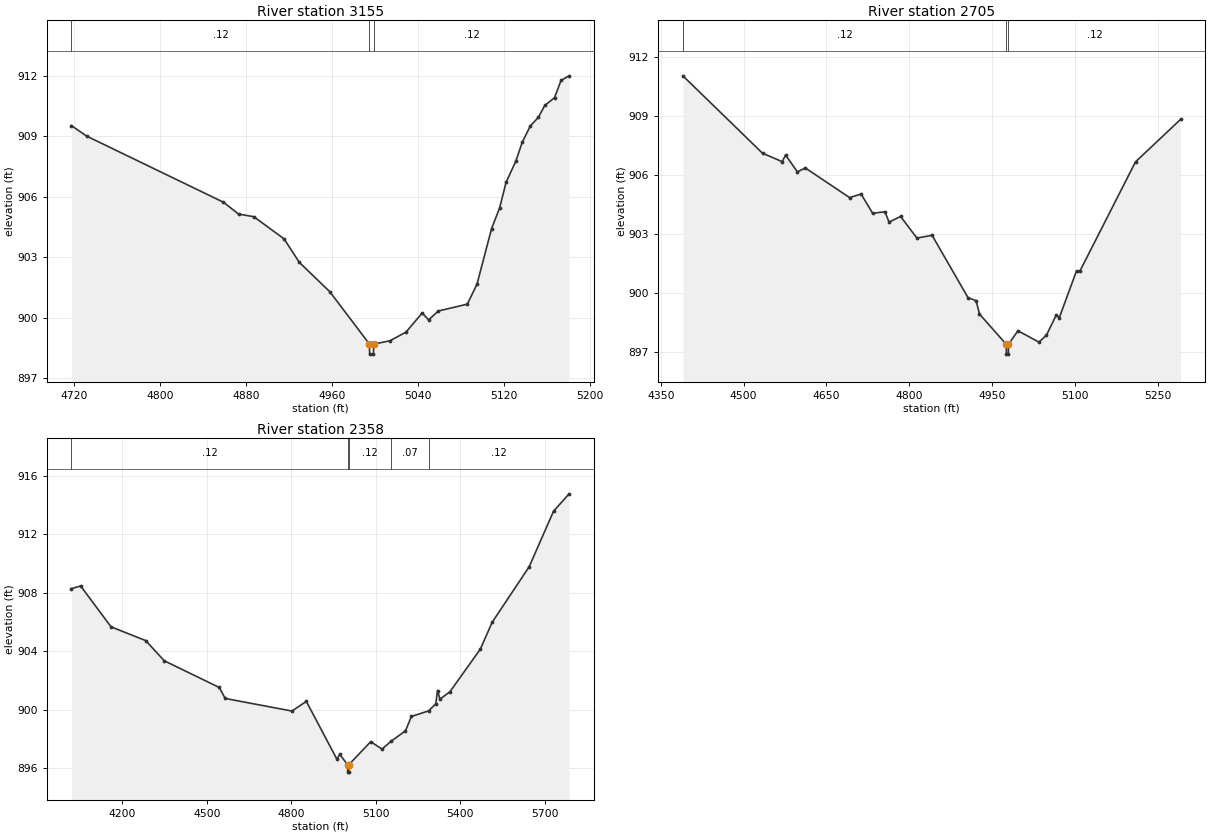
Type RM Length L Ch R = 1,3155,450,450,450
BEGIN DESCRIPTION:
Upper Dry Comal Tributary 12 2.0
END DESCRIPTION:
XS GIS Cut Line= 3
      2203525.03     13808624.97      2203725.00     13808425.00
      2203825.01     13808274.98
#Sta/Elev= 30
  4717.2  909.53  4731.3  909.01  4858.6  905.73  4872.7  905.14  4886.9  905.01
  4915.1  903.91  4929.3  902.74  4957.6  901.29  4994.5  898.69  4994.7  898.19
  4998.2  898.19  4998.5  898.69  5013.5  898.85  5028.5  899.28  5043.6  900.23
  5049.6  899.89  5058.6  900.33  5085.6  900.67  5094.6  901.66  5108.2  904.42
  5115.7  905.45  5121.7  906.72  5130.7  907.76  5136.7  908.70  5144.2  909.51
  5151.7  909.94  5157.7  910.53  5166.8  910.92  5172.8  911.77  5180.3  912.00
#Mann=3,-1,0
  4717.2    0.12       0  4994.5    0.05       0  4998.5    0.12       0
Bank Sta=4994.5,4998.5
Exp/Cntr=0.3,0.1

Type RM Length L Ch R = 1,2705,347,347,347
BEGIN DESCRIPTION:
Upper Dry Comal Tributary 12 1.0
END DESCRIPTION:
XS GIS Cut Line= 3
      2203625.04     13808924.97      2204125.00     13808575.00
      2203975.02     13808325.03
#Sta/Elev= 30
  4389.9  911.04  4534.2  907.10  4569.9  906.67  4576.0  907.01  4597.4  906.15
  4611.8  906.35  4692.0  904.84  4712.9  905.02  4733.8  904.04  4756.1  904.12
  4763.5  903.59  4784.4  903.88  4814.0  902.78  4841.5  902.92  4906.5  899.75
  4921.3  899.59  4927.4  898.91  4975.9  897.37  4976.2  896.87  4979.7  896.87
  4979.9  897.37  4997.1  898.06  5035.2  897.48  5048.8  897.84  5066.3  898.85
  5072.1  898.73  5103.2  901.11  5109.0  901.08  5210.1  906.66  5291.7  908.82
#Mann=3,-1,0
  4389.9    0.12       0  4975.9    0.05       0  4979.9    0.12       0
Bank Sta=4975.9,4979.9
Exp/Cntr=0.3,0.1

Type RM Length L Ch R = 1,2358,0,0,0
BEGIN DESCRIPTION:
XS7885
END DESCRIPTION:
XS GIS Cut Line= 4
      2203719.18     13809145.72      2204416.34     13808676.94
      2204410.33     13808364.41      2204061.91     13807859.81
#Sta/Elev= 30
  4020.0  908.28  4052.7  908.46  4160.6  905.67  4283.6  904.73  4349.6  903.35
  4544.6  901.53  4565.6  900.78  4802.6  899.92  4853.5  900.58  4962.1  896.63
  4972.1  896.97  5000.1  896.25  5000.3  895.75  5003.8  895.75  5004.1  896.25
  5082.1  897.83  5122.1  897.32  5153.7  897.85  5205.4  898.57  5226.4  899.55
  5287.4  899.93  5312.9  900.41  5319.0  901.32  5327.8  900.73  5363.6  901.25
  5471.1  904.15  5513.0  905.98  5644.2  909.77  5730.7  913.56  5785.9  914.75
#Mann=5,-1,0
  4020.0    0.12       0  5000.1    0.05       0  5004.1    0.12       0
  5153.7    0.07       0  5287.4    0.12       0
Bank Sta=5000.1,5004.1
Exp/Cntr=0.3,0.1

Chan Stop Cuts=-1