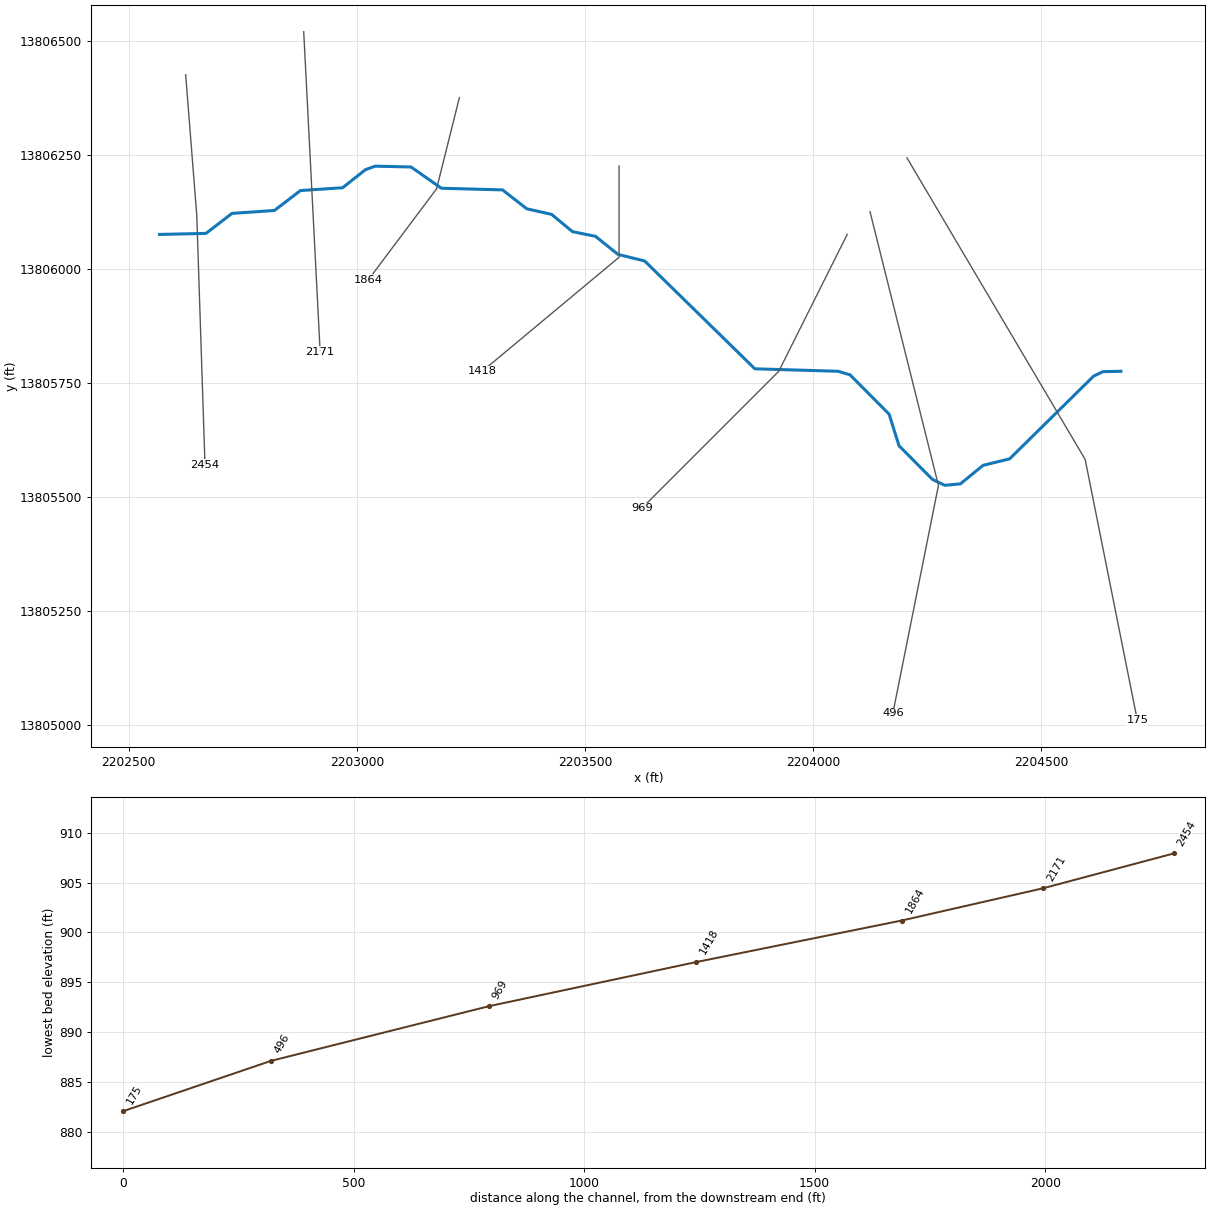
--- Upper Dry Comal Tributary 12b.prj (project) ---

Proj Title=Upper Dry Comal Tributary 12b Base Level Engineering
Current Plan=p01
Default Exp/Contr=0.3,0.1
English Units
Geom File=g01
Flow File=f01
Plan File=p01
BEGIN DESCRIPTION:
Upper Dry Comal Tributary 12b
END DESCRIPTION:

--- Upper Dry Comal Tributary 12b.p01 (plan) ---

Plan Title=Multiple Run
Short Identifier=Multiple
Geom File=g01
Flow File=f01
Subcritical Flow
K Sum by GR= 0
Std Step Tol= 0.01
Critical Tol= 0.01
Num of Std Step Trials= 20
Max Error Tol= 0.3
Flow Tol Ratio= 0.001
Split Flow NTrial= 30
Split Flow Tol= 0.02
Split Flow Ratio= 0.02
Log Output Level= 0
Friction Slope Method= 1
Unsteady Friction Slope Method= 2
Unsteady Bridges Friction Slope Method= 1
Parabolic Critical Depth
Global Vel Dist=  1 , 1 , 1
Global Log Level= 0
CheckData=True
Encroach Param= -1, 0, 0, 0
BEGIN DESCRIPTION:
Multiple Run
END DESCRIPTION:

--- Upper Dry Comal Tributary 12b.f01 (steady flow) ---

Flow Title=Multiple
Number of Profiles=7
Profile Names=10-year,25-year,50-year,1pct_min,100-year,1pct_plu,500-year
River Rch & RM= Upper Dry Comal ,Reach-1,2454
     464     739     985     637    1271    2537    2093
Boundary for River Rch & Prof#=Upper Dry Comal ,Reach-1,1
Up Type=0
Dn Type=3
Dn Slope=0.005
Boundary for River Rch & Prof#=Upper Dry Comal ,Reach-1,2
Up Type=0
Dn Type=3
Dn Slope=0.005
Boundary for River Rch & Prof#=Upper Dry Comal ,Reach-1,3
Up Type=0
Dn Type=3
Dn Slope=0.005
Boundary for River Rch & Prof#=Upper Dry Comal ,Reach-1,4
Up Type=0
Dn Type=3
Dn Slope=0.005
Boundary for River Rch & Prof#=Upper Dry Comal ,Reach-1,5
Up Type=0
Dn Type=3
Dn Slope=0.005
Boundary for River Rch & Prof#=Upper Dry Comal ,Reach-1,6
Up Type=0
Dn Type=3
Dn Slope=0.005
Boundary for River Rch & Prof#=Upper Dry Comal ,Reach-1,7
Up Type=0
Dn Type=3
Dn Slope=0.005

--- Upper Dry Comal Tributary 12b.g01 (geometry) ---

Geom Title=Existing Conditions

River Reach=Upper Dry Comal ,Reach-1
Reach XY= 30
      2202567.75     13806075.00      2202669.53     13806077.24
      2202726.59     13806121.17      2202819.43     13806127.47
      2202876.60     13806171.15      2202969.03     13806177.36
      2203018.96     13806216.91      2203040.27     13806224.62
      2203119.02     13806222.83      2203185.51     13806176.23
      2203319.48     13806172.64      2203372.82     13806131.12
      2203427.20     13806118.92      2203472.80     13806081.08
      2203523.28     13806070.84      2203572.81     13806031.10
      2203631.06     13806016.86      2203872.55     13805780.46
      2204055.02     13805775.04      2204081.21     13805767.20
      2204166.85     13805681.07      2204188.62     13805611.76
      2204261.76     13805538.11      2204289.04     13805525.09
      2204323.26     13805528.31      2204372.81     13805568.82
      2204431.06     13805583.14      2204615.21     13805764.48
      2204635.76     13805774.25      2204675.00     13805775.00

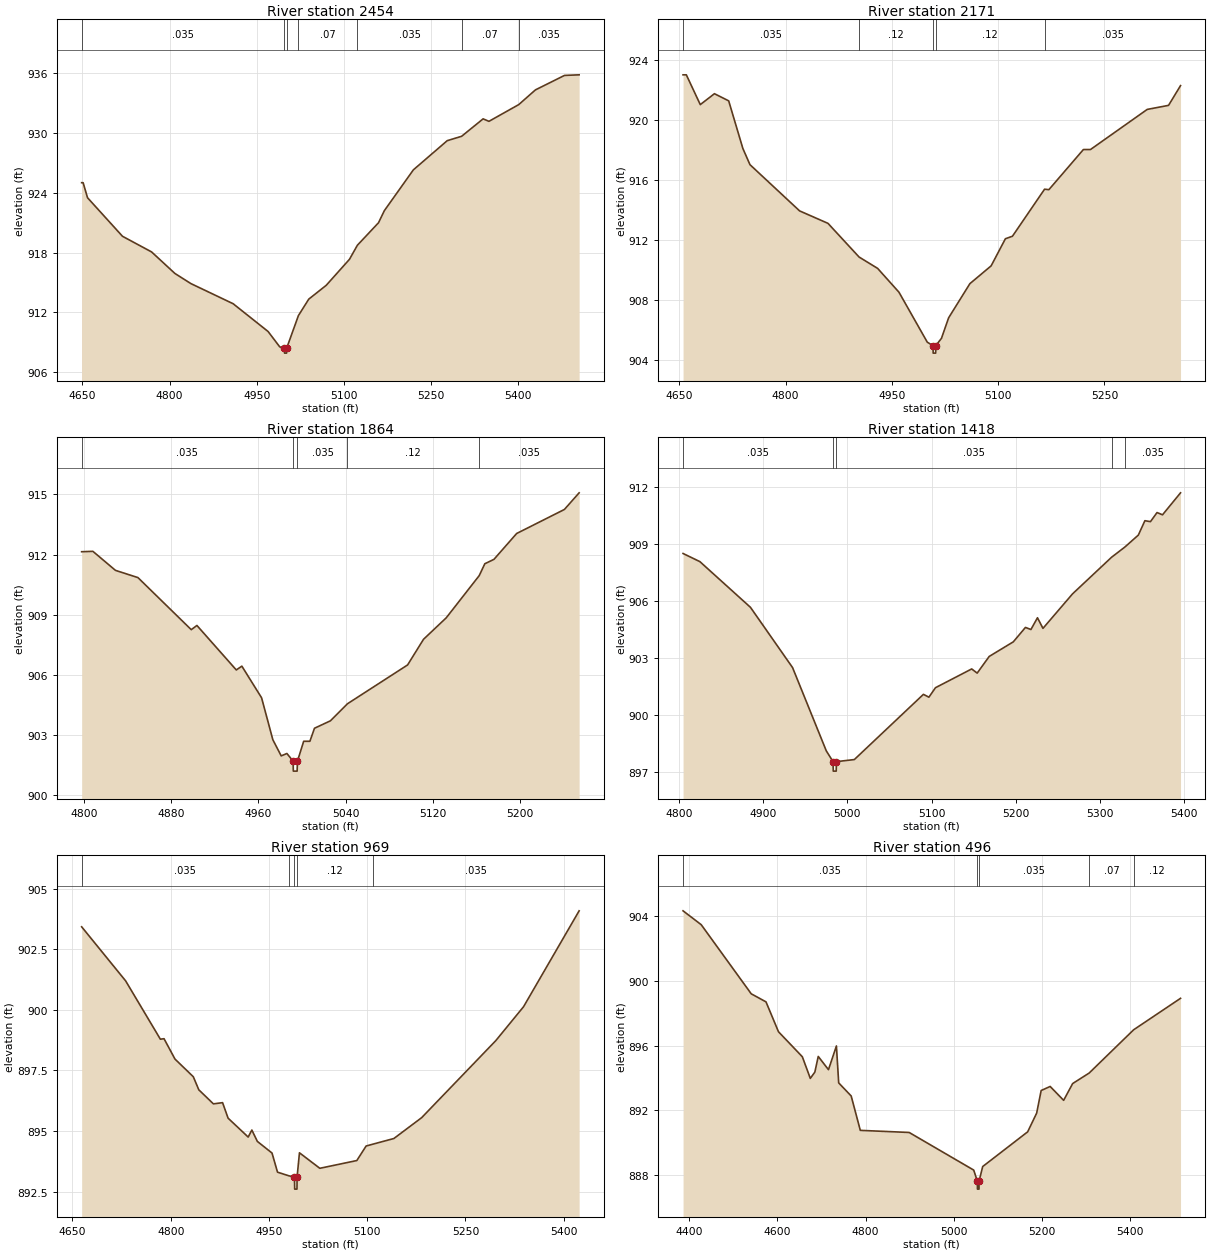
Type RM Length L Ch R = 1,2454,283,283,283
BEGIN DESCRIPTION:
Upper Dry Comal Tributary 12b 5.0
END DESCRIPTION:
XS GIS Cut Line= 3
      2202625.00     13806425.04      2202649.35     13806116.61
      2202667.38     13805569.80
#Sta/Elev= 30
  4648.6  925.03  4651.1  925.03  4658.7  923.52  4718.9  919.65  4769.0  918.08
  4809.1  915.92  4836.7  914.90  4909.4  912.88  4969.6  910.09  4989.6  908.55
  4997.6  908.42  4997.9  907.92  5001.4  907.92  5001.6  908.42  5021.8  911.69
  5039.6  913.34  5069.7  914.73  5109.7  917.34  5123.3  918.75  5159.7  921.01
  5169.7  922.22  5219.7  926.32  5278.0  929.25  5302.8  929.69  5339.8  931.44
  5349.8  931.19  5401.1  932.87  5429.9  934.35  5479.9  935.80  5505.1  935.86
#Mann=7,-1,0
  4648.6   0.035       0  4997.6   0.035       0  5001.6   0.035       0
  5021.8    0.07       0  5123.3   0.035       0  5302.8    0.07       0
  5401.1   0.035       0
Bank Sta=4997.6,5001.6
Exp/Cntr=0.3,0.1

Type RM Length L Ch R = 1,2171,307,307,307
BEGIN DESCRIPTION:
XS7887
END DESCRIPTION:
XS GIS Cut Line= 2
      2202883.75     13806519.27      2202919.71     13805818.09
#Sta/Elev= 30
  4655.3  923.02  4659.9  923.02  4679.6  921.03  4699.6  921.76  4719.7  921.28
  4739.7  918.10  4749.7  917.02  4819.8  913.93  4859.8  913.10  4903.7  910.85
  4929.9  910.09  4960.0  908.50  5000.0  905.16  5008.0  904.93  5008.3  904.43
  5011.8  904.43  5012.0  904.93  5020.0  905.42  5030.1  906.79  5060.1  909.07
  5090.1  910.26  5110.2  912.07  5120.2  912.24  5165.5  915.38  5171.6  915.35
  5220.3  918.03  5230.3  918.03  5310.4  920.71  5340.5  920.98  5357.4  922.30
#Mann=5,-1,0
  4655.3   0.035       0  4903.7    0.12       0  5008.0    0.05       0
  5012.0    0.12       0  5165.5   0.035       0
Bank Sta=5008,5012
Exp/Cntr=0.3,0.1

Type RM Length L Ch R = 1,1864,446,446,446
BEGIN DESCRIPTION:
Upper Dry Comal Tributary 12b 4.0
END DESCRIPTION:
XS GIS Cut Line= 3
      2203225.01     13806375.04      2203175.00     13806175.00
      2203025.00     13805975.00
#Sta/Elev= 30
  4798.0  912.14  4808.3  912.16  4829.0  911.21  4849.6  910.85  4898.5  908.25
  4903.7  908.46  4939.8  906.24  4944.9  906.43  4963.0  904.85  4973.3  902.76
  4981.0  901.95  4986.2  902.07  4991.9  901.69  4992.1  901.19  4995.6  901.19
  4995.9  901.69  5001.6  902.68  5007.3  902.68  5011.5  903.33  5026.1  903.70
  5041.7  904.55  5096.9  906.49  5111.5  907.77  5132.3  908.84  5162.6  910.95
  5167.7  911.54  5176.1  911.76  5196.9  913.05  5240.7  914.25  5254.2  915.08
#Mann=5,-1,0
  4798.0   0.035       0  4991.9   0.035       0  4995.9   0.035       0
  5041.7    0.12       0  5162.6   0.035       0
Bank Sta=4991.9,4995.9
Exp/Cntr=0.3,0.1

Type RM Length L Ch R = 1,1418,449,449,449
BEGIN DESCRIPTION:
Upper Dry Comal Tributary 12b 3.0
END DESCRIPTION:
XS GIS Cut Line= 3
      2203575.00     13806225.04      2203575.00     13806025.00
      2203275.04     13805775.03
#Sta/Elev= 30
  4805.0  908.50  4825.0  908.07  4885.0  905.66  4935.0  902.48  4975.0  898.09
  4983.0  897.52  4983.3  897.02  4986.8  897.02  4987.0  897.52  5008.3  897.63
  5090.3  901.07  5096.8  900.92  5104.6  901.42  5147.6  902.41  5154.1  902.19
  5168.4  903.07  5197.0  903.84  5211.4  904.60  5217.9  904.49  5225.7  905.11
  5232.2  904.55  5267.3  906.37  5313.6  908.30  5329.4  908.84  5345.4  909.47
  5353.2  910.23  5359.8  910.18  5367.6  910.66  5374.1  910.54  5395.5  911.70
#Mann=5,-1,0
  4805.0   0.035       0  4983.0   0.035       0  4987.0   0.035       0
  5313.6    0.07       0  5329.4   0.035       0
Bank Sta=4983,4987
Exp/Cntr=0.3,0.1

Type RM Length L Ch R = 1,969,473,473,473
BEGIN DESCRIPTION:
Upper Dry Comal Tributary 12b 2.0
END DESCRIPTION:
XS GIS Cut Line= 3
      2204074.99     13806074.98      2203925.00     13805775.00
      2203624.97     13805474.97
#Sta/Elev= 30
  4664.0  903.43  4731.1  901.20  4784.2  898.79  4789.8  898.81  4806.5  897.97
  4834.5  897.24  4842.9  896.70  4865.2  896.12  4879.2  896.17  4887.6  895.53
  4918.3  894.75  4923.9  895.04  4932.3  894.57  4954.7  894.09  4963.1  893.30
  4980.4  893.15  4989.0  893.10  4989.3  892.60  4992.8  892.60  4993.0  893.10
  4996.6  894.10  5027.7  893.46  5084.2  893.78  5098.4  894.38  5109.3  894.46
  5140.8  894.69  5183.2  895.55  5296.4  898.73  5338.8  900.13  5423.7  904.09
#Mann=5,-1,0
  4664.0   0.035       0  4980.4    0.12       0  4989.0    0.05       0
  4993.0    0.12       0  5109.3   0.035       0
Bank Sta=4989,4993
Exp/Cntr=0.3,0.1

Type RM Length L Ch R = 1,496,321,321,321
BEGIN DESCRIPTION:
Upper Dry Comal Tributary 12b 1.0
END DESCRIPTION:
XS GIS Cut Line= 3
      2204125.01     13806124.96      2204275.00     13805525.00
      2204175.01     13805025.03
#Sta/Elev= 30
  4386.2  904.35  4427.4  903.49  4540.8  899.21  4574.3  898.71  4602.6  896.86
  4656.7  895.31  4674.8  893.97  4685.1  894.36  4692.8  895.33  4716.0  894.51
  4734.0  895.98  4739.2  893.69  4767.5  892.88  4788.2  890.75  4899.0  890.62
  5045.4  888.29  5053.6  887.61  5053.9  887.11  5057.4  887.11  5057.6  887.61
  5065.8  888.51  5167.8  890.66  5188.2  891.82  5198.4  893.22  5218.8  893.47
  5249.4  892.61  5269.8  893.65  5307.2  894.30  5408.1  896.98  5514.5  898.93
#Mann=5,-1,0
  4386.2   0.035       0  5053.6   0.035       0  5057.6   0.035       0
  5307.2    0.07       0  5408.1    0.12       0
Bank Sta=5053.6,5057.6
Exp/Cntr=0.3,0.1

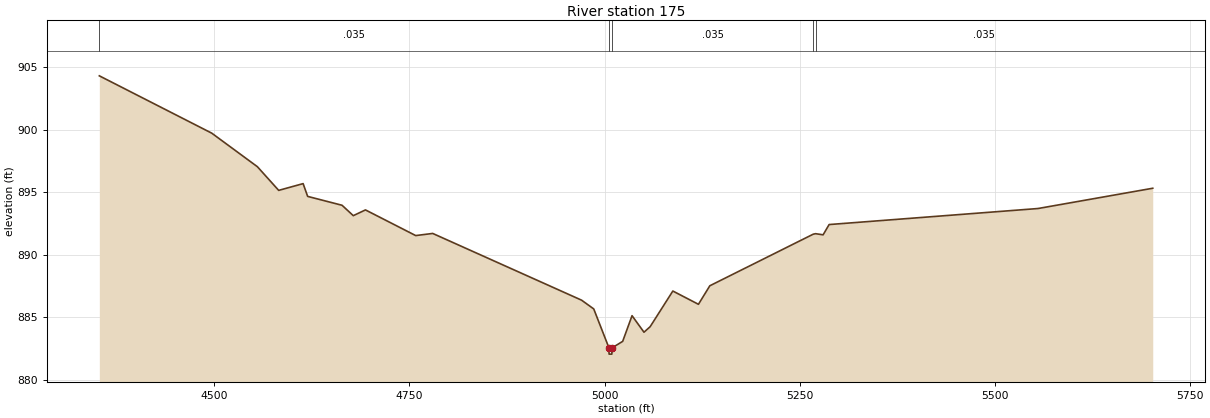
Type RM Length L Ch R = 1,175,0,0,0
BEGIN DESCRIPTION:
XS7886
END DESCRIPTION:
XS GIS Cut Line= 3
      2204205.97     13806242.85      2204596.65     13805581.71
      2204710.84     13805010.75
#Sta/Elev= 30
  4352.5  904.29  4496.6  899.71  4555.1  897.03  4582.4  895.14  4613.7  895.68
  4619.5  894.66  4663.6  893.95  4678.0  893.12  4693.6  893.58  4758.0  891.53
  4779.8  891.70  4970.6  886.37  4986.2  885.67  5005.7  882.56  5005.9  882.06
  5009.4  882.06  5009.7  882.56  5023.3  883.08  5035.3  885.13  5050.6  883.81
  5058.5  884.25  5087.6  887.10  5120.4  886.04  5135.0  887.52  5267.5  891.64
  5270.6  891.68  5280.2  891.59  5287.9  892.41  5555.6  893.69  5702.7  895.31
#Mann=5,-1,0
  4352.5   0.035       0  5005.7   0.035       0  5009.7   0.035       0
  5267.5    0.07       0  5270.6   0.035       0
Bank Sta=5005.7,5009.7
Exp/Cntr=0.3,0.1

Chan Stop Cuts=-1