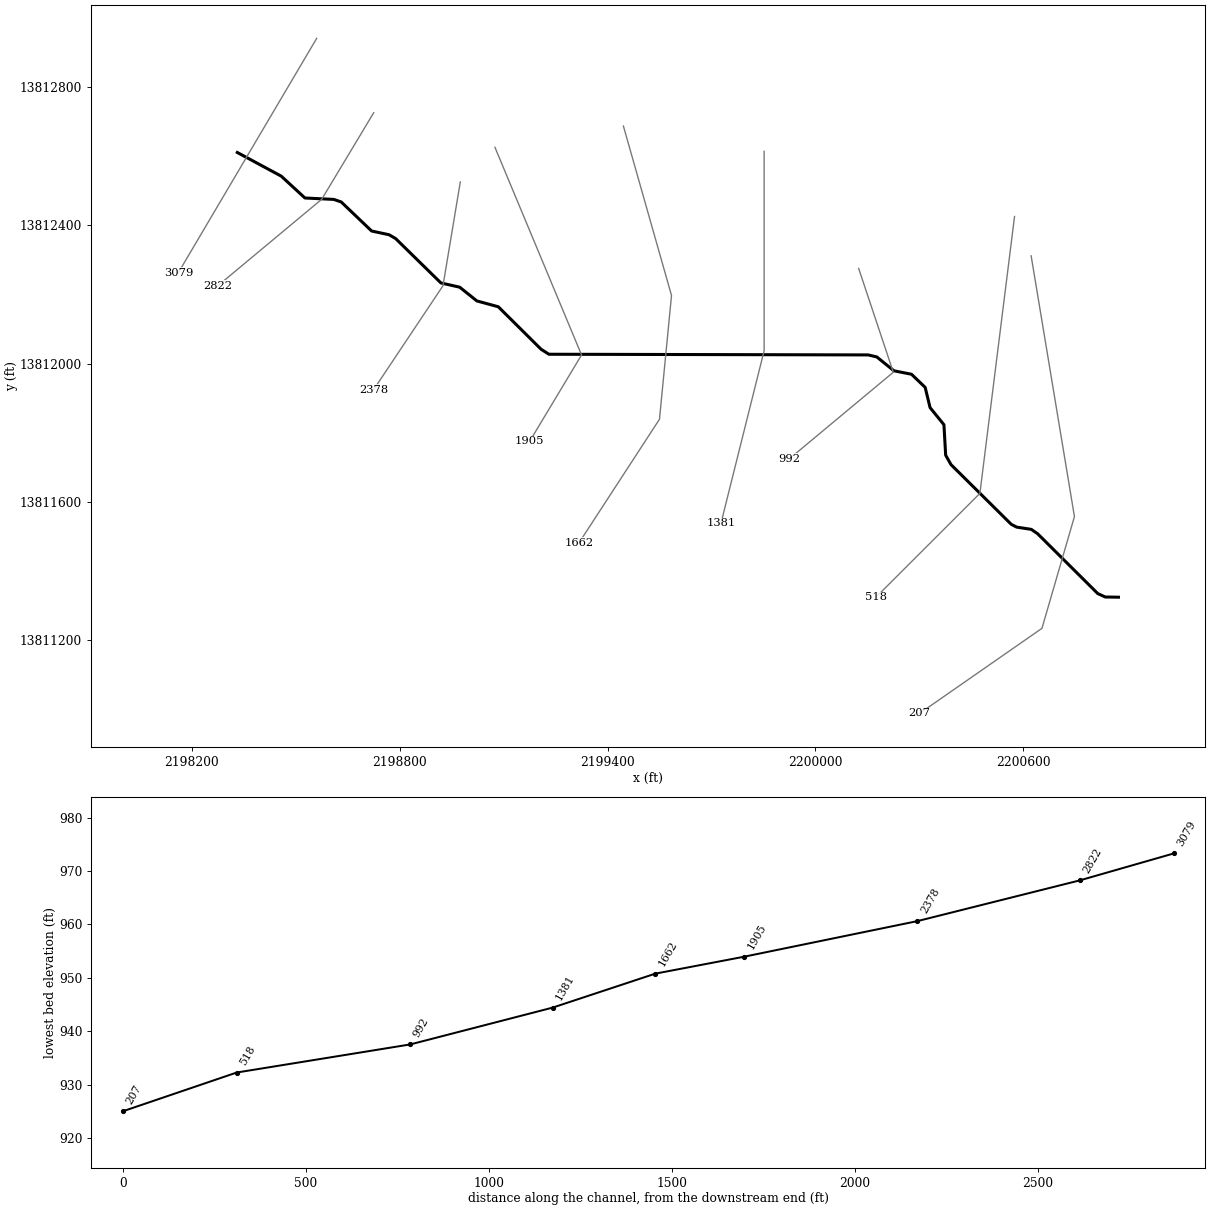
--- Upper Dry Comal Tributary 16.prj (project) ---

Proj Title=Upper Dry Comal Tributary 16 Base Level Engineering
Current Plan=p01
Default Exp/Contr=0.3,0.1
English Units
Geom File=g01
Flow File=f01
Plan File=p01
BEGIN DESCRIPTION:
Upper Dry Comal Tributary 16
END DESCRIPTION:

--- Upper Dry Comal Tributary 16.p01 (plan) ---

Plan Title=Multiple Run
Short Identifier=Multiple
Geom File=g01
Flow File=f01
Subcritical Flow
K Sum by GR= 0
Std Step Tol= 0.01
Critical Tol= 0.01
Num of Std Step Trials= 20
Max Error Tol= 0.3
Flow Tol Ratio= 0.001
Split Flow NTrial= 30
Split Flow Tol= 0.02
Split Flow Ratio= 0.02
Log Output Level= 0
Friction Slope Method= 1
Unsteady Friction Slope Method= 2
Unsteady Bridges Friction Slope Method= 1
Parabolic Critical Depth
Global Vel Dist=  1 , 1 , 1
Global Log Level= 0
CheckData=True
Encroach Param= -1, 0, 0, 0
BEGIN DESCRIPTION:
Multiple Run
END DESCRIPTION:

--- Upper Dry Comal Tributary 16.f01 (steady flow) ---

Flow Title=Multiple
Number of Profiles=7
Profile Names=10-year,25-year,50-year,1pct_min,100-year,1pct_plu,500-year
River Rch & RM= Upper Dry Comal ,Reach-1,3079
     408     649     865     561    1118    2232    1845
Boundary for River Rch & Prof#=Upper Dry Comal ,Reach-1,1
Up Type=0
Dn Type=3
Dn Slope=0.005
Boundary for River Rch & Prof#=Upper Dry Comal ,Reach-1,2
Up Type=0
Dn Type=3
Dn Slope=0.005
Boundary for River Rch & Prof#=Upper Dry Comal ,Reach-1,3
Up Type=0
Dn Type=3
Dn Slope=0.005
Boundary for River Rch & Prof#=Upper Dry Comal ,Reach-1,4
Up Type=0
Dn Type=3
Dn Slope=0.005
Boundary for River Rch & Prof#=Upper Dry Comal ,Reach-1,5
Up Type=0
Dn Type=3
Dn Slope=0.005
Boundary for River Rch & Prof#=Upper Dry Comal ,Reach-1,6
Up Type=0
Dn Type=3
Dn Slope=0.005
Boundary for River Rch & Prof#=Upper Dry Comal ,Reach-1,7
Up Type=0
Dn Type=3
Dn Slope=0.005

--- Upper Dry Comal Tributary 16.g01 (geometry) ---

Geom Title=Existing Conditions

River Reach=Upper Dry Comal ,Reach-1
Reach XY= 30
      2198331.25     13812610.07      2198458.16     13812541.63
      2198526.48     13812478.57      2198609.78     13812474.47
      2198631.16     13812467.12      2198718.96     13812383.18
      2198769.36     13812372.36      2198788.21     13812361.37
      2198918.94     13812233.14      2198973.26     13812220.81
      2199022.81     13812181.10      2199084.68     13812164.23
      2199208.24     13812041.43      2199230.85     13812027.06
      2200152.32     13812025.11      2200177.35     13812019.29
      2200226.78     13811979.23      2200277.55     13811969.27
      2200316.98     13811931.34      2200331.15     13811872.85
      2200371.17     13811823.42      2200376.16     13811735.48
      2200391.46     13811708.25      2200565.32     13811535.78
      2200581.05     13811527.53      2200623.35     13811521.02
      2200641.67     13811508.35      2200815.21     13811335.52
      2200836.84     13811325.59      2200875.00     13811325.00

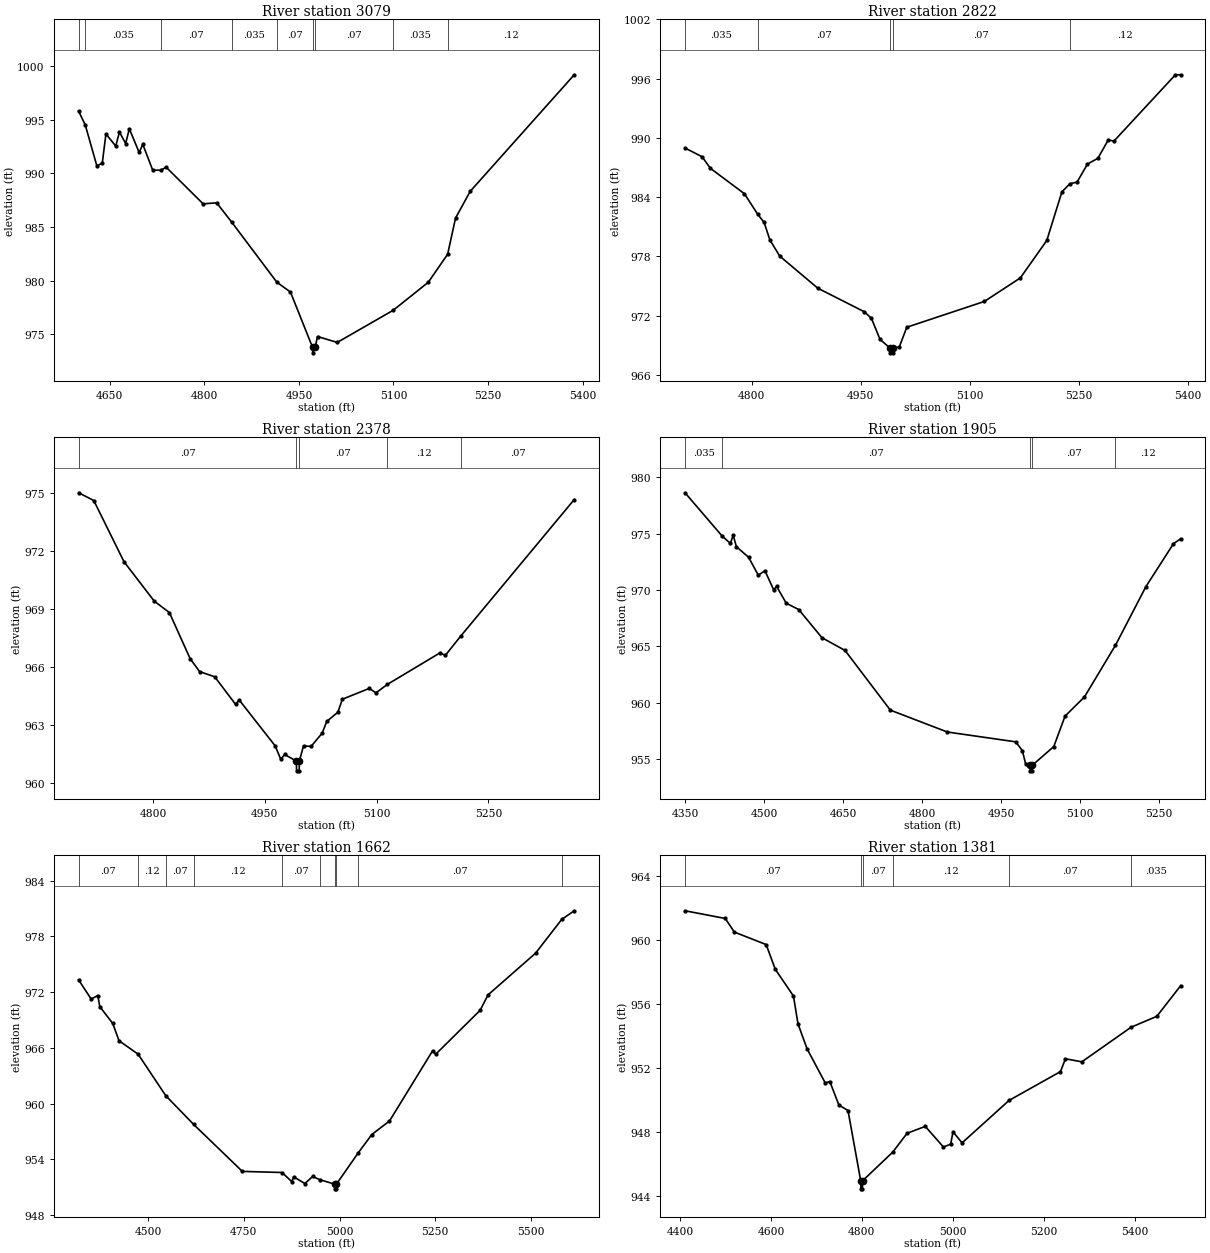
Type RM Length L Ch R = 1,3079,257,257,257
BEGIN DESCRIPTION:
XS7889
END DESCRIPTION:
XS GIS Cut Line= 2
      2198560.42     13812939.93      2198161.09     13812262.81
#Sta/Elev= 30
  4600.6  995.79  4611.1  994.51  4629.5  990.70  4638.1  990.95  4643.9  993.67
  4659.5  992.54  4665.3  993.85  4675.2  992.78  4681.0  994.15  4696.6  991.95
  4702.4  992.70  4718.1  990.30  4730.6  990.29  4739.5  990.57  4798.1  987.16
  4819.5  987.26  4843.8  985.43  4915.1  979.86  4936.6  978.95  4971.7  973.79
  4972.0  973.29  4975.7  973.79  4979.5  974.81  5010.8  974.26  5099.5  977.25
  5155.2  979.86  5185.9  982.47  5198.4  985.83  5221.6  988.32  5386.7  999.18
#Mann=9,-1,0
  4600.6    0.07       0  4611.1   0.035       0  4730.6    0.07       0
  4843.8   0.035       0  4915.1    0.07       0  4971.7    0.05       0
  4975.7    0.07       0  5099.5   0.035       0  5185.9    0.12       0
Bank Sta=4971.7,4975.7
Exp/Cntr=0.3,0.1

Type RM Length L Ch R = 1,2822,444,444,444
BEGIN DESCRIPTION:
Upper Dry Comal Tributary 16 6.0
END DESCRIPTION:
XS GIS Cut Line= 3
      2198725.02     13812725.03      2198575.00     13812475.00
      2198275.00     13812225.00
#Sta/Elev= 30
  4708.4  988.97  4731.8  988.09  4743.4  986.91  4790.1  984.35  4808.5  982.26
  4817.3  981.44  4825.1  979.68  4838.7  978.04  4891.1  974.79  4955.3  972.40
  4965.0  971.73  4976.7  969.62  4990.2  968.75  4990.5  968.25  4994.0  968.25
  4994.2  968.75  5003.2  968.83  5013.6  970.84  5120.4  973.45  5169.9  975.83
  5206.3  979.62  5227.1  984.54  5238.0  985.35  5248.0  985.53  5262.3  987.35
  5276.6  987.93  5290.9  989.79  5298.7  989.67  5383.3  996.38  5390.5  996.38
#Mann=5,-1,0
  4708.4   0.035       0  4808.5    0.07       0  4990.2    0.05       0
  4994.2    0.07       0  5238.0    0.12       0
Bank Sta=4990.2,4994.2
Exp/Cntr=0.3,0.1

Type RM Length L Ch R = 1,2378,473,473,473
BEGIN DESCRIPTION:
Upper Dry Comal Tributary 16 5.0
END DESCRIPTION:
XS GIS Cut Line= 3
      2198975.00     13812525.00      2198925.00     13812225.00
      2198725.00     13811925.00
#Sta/Elev= 30
  4700.3  975.00  4720.6  974.60  4761.1  971.44  4801.7  969.40  4822.0  968.81
  4849.8  966.43  4862.5  965.76  4882.8  965.49  4910.7  964.07  4915.7  964.29
  4963.9  961.92  4971.5  961.22  4976.6  961.48  4992.3  961.13  4992.6  960.63
  4996.1  960.63  4996.3  961.13  5001.9  961.92  5012.0  961.89  5027.0  962.58
  5033.0  963.18  5048.0  963.66  5054.0  964.33  5090.1  964.89  5099.1  964.66
  5114.5  965.10  5184.7  966.72  5192.2  966.60  5212.7  967.59  5365.0  974.65
#Mann=5,-1,0
  4700.3    0.07       0  4992.3    0.05       0  4996.3    0.07       0
  5114.5    0.12       0  5212.7    0.07       0
Bank Sta=4992.3,4996.3
Exp/Cntr=0.3,0.1

Type RM Length L Ch R = 1,1905,243,243,243
BEGIN DESCRIPTION:
Upper Dry Comal Tributary 16 4.0
END DESCRIPTION:
XS GIS Cut Line= 3
      2199075.00     13812624.99      2199325.00     13812025.00
      2199175.02     13811775.03
#Sta/Elev= 30
  4349.9  978.62  4420.1  974.80  4436.0  974.13  4441.4  974.86  4447.4  973.85
  4470.7  972.90  4489.1  971.31  4501.6  971.72  4518.3  970.02  4523.8  970.33
  4542.2  968.83  4566.0  968.27  4609.9  965.78  4653.8  964.65  4739.9  959.36
  4848.2  957.42  4978.2  956.55  4990.7  955.77  4997.2  954.55  5005.7  954.48
  5005.9  953.98  5009.4  953.98  5009.7  954.48  5050.4  956.13  5071.8  958.83
  5108.7  960.53  5167.5  965.10  5225.4  970.30  5277.8  974.11  5291.4  974.54
#Mann=5,-1,0
  4349.9   0.035       0  4420.1    0.07       0  5005.7    0.05       0
  5009.7    0.07       0  5167.5    0.12       0
Bank Sta=5005.7,5009.7
Exp/Cntr=0.3,0.1

Type RM Length L Ch R = 1,1662,281,281,281
BEGIN DESCRIPTION:
XS7890
END DESCRIPTION:
XS GIS Cut Line= 4
      2199445.83     13812686.47      2199584.72     13812196.88
      2199550.00     13811839.24      2199317.35     13811481.58
#Sta/Elev= 30
  4318.4  973.32  4351.1  971.26  4368.5  971.64  4373.7  970.44  4407.6  968.63
  4423.9  966.77  4473.8  965.32  4546.0  960.85  4618.9  957.75  4746.1  952.69
  4849.8  952.57  4875.3  951.59  4880.3  952.10  4909.6  951.38  4929.7  952.14
  4948.9  951.79  4987.9  951.31  4988.2  950.81  4991.7  950.81  4991.9  951.31
  5048.1  954.64  5084.3  956.66  5130.6  958.12  5243.5  965.70  5251.3  965.31
  5367.3  970.04  5388.4  971.72  5512.3  976.20  5580.6  979.84  5613.3  980.77
#Mann=10,-1,0
  4318.4    0.07       0  4473.8    0.12       0  4546.0    0.07       0
  4618.9    0.12       0  4849.8    0.07       0  4948.9   0.035       0
  4987.9   0.035       0  4991.9   0.035       0  5048.1    0.07       0
  5580.6    0.12       0
Bank Sta=4987.9,4991.9
Exp/Cntr=0.3,0.1

Type RM Length L Ch R = 1,1381,389,389,389
BEGIN DESCRIPTION:
Upper Dry Comal Tributary 16 3.0
END DESCRIPTION:
XS GIS Cut Line= 3
      2199852.08     13812613.53      2199852.08     13812037.15
      2199727.44     13811538.58
#Sta/Elev= 30
  4411.1  961.81  4499.6  961.33  4519.6  960.48  4589.6  959.70  4609.6  958.16
  4649.6  956.49  4659.6  954.75  4679.6  953.19  4719.6  951.06  4729.6  951.15
  4749.6  949.68  4769.6  949.34  4797.6  944.95  4797.9  944.45  4801.4  944.45
  4801.6  944.95  4868.3  946.75  4899.6  947.92  4939.6  948.35  4979.6  947.06
  4995.5  947.24  5000.6  948.01  5020.6  947.32  5123.9  949.97  5237.1  951.77
  5248.0  952.57  5284.1  952.38  5392.4  954.54  5449.0  955.22  5501.4  957.13
#Mann=6,-1,0
  4411.1    0.07       0  4797.6    0.05       0  4801.6    0.07       0
  4868.3    0.12       0  5123.9    0.07       0  5392.4   0.035       0
Bank Sta=4797.6,4801.6
Exp/Cntr=0.3,0.1

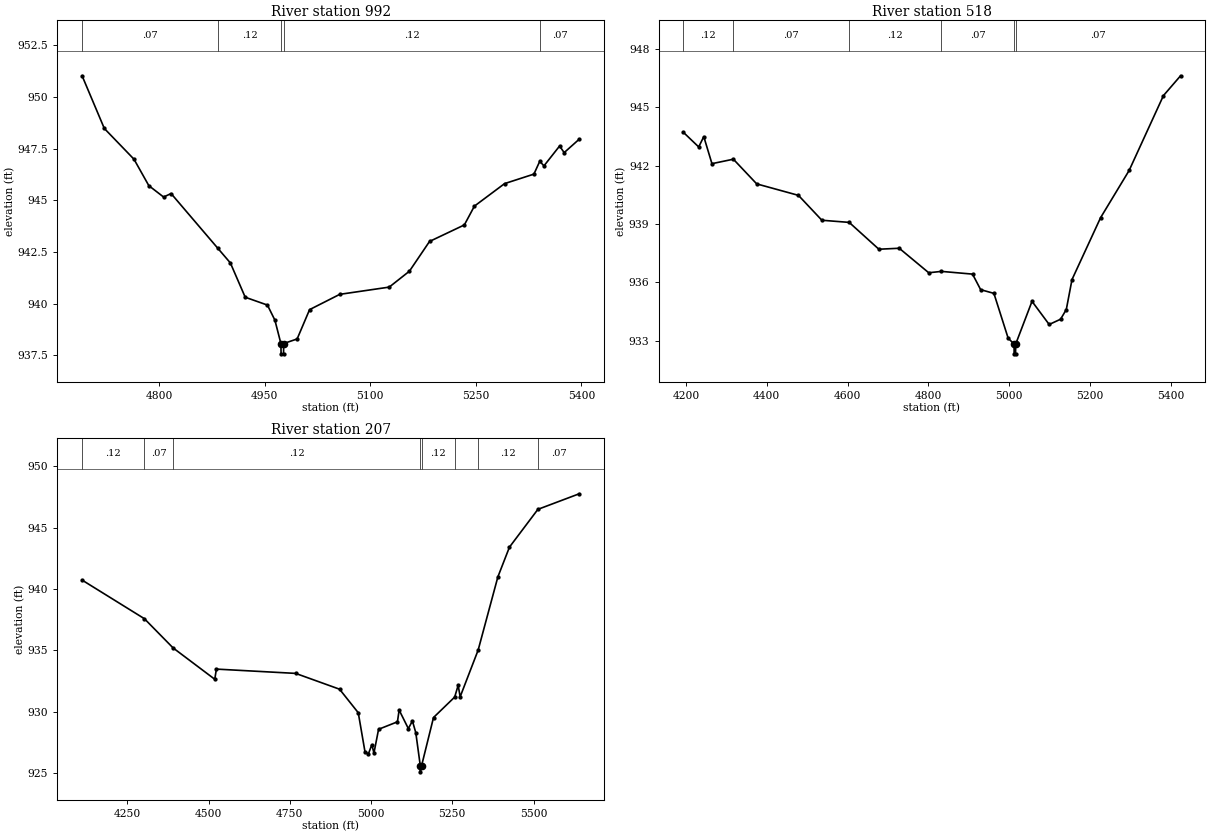
Type RM Length L Ch R = 1,992,474,474,474
BEGIN DESCRIPTION:
Upper Dry Comal Tributary 16 2.0
END DESCRIPTION:
XS GIS Cut Line= 3
      2200125.00     13812275.00      2200225.00     13811975.00
      2199925.03     13811725.02
#Sta/Elev= 30
  4690.2  951.03  4721.8  948.48  4764.0  946.99  4785.1  945.71  4806.1  945.16
  4816.7  945.33  4883.4  942.67  4901.0  941.97  4922.1  940.31  4953.7  939.93
  4964.3  939.20  4972.8  938.07  4973.1  937.57  4976.6  937.57  4976.8  938.07
  4995.9  938.29  5013.6  939.71  5056.5  940.45  5126.8  940.80  5155.5  941.57
  5184.1  943.01  5233.6  943.81  5247.9  944.72  5290.8  945.81  5332.5  946.27
  5340.8  946.89  5346.8  946.67  5369.0  947.63  5375.5  947.31  5396.9  947.96
#Mann=5,-1,0
  4690.2    0.07       0  4883.4    0.12       0  4972.8    0.05       0
  4976.8    0.12       0  5340.8    0.07       0
Bank Sta=4972.8,4976.8
Exp/Cntr=0.3,0.1

Type RM Length L Ch R = 1,518,311,311,311
BEGIN DESCRIPTION:
Upper Dry Comal Tributary 16 1.0
END DESCRIPTION:
XS GIS Cut Line= 3
      2200575.00     13812425.03      2200475.00     13811625.00
      2200175.01     13811325.01
#Sta/Elev= 30
  4193.7  943.71  4231.5  942.96  4244.1  943.49  4264.3  942.10  4317.3  942.33
  4375.1  941.06  4478.4  940.47  4536.4  939.19  4604.0  939.08  4677.5  937.70
  4727.9  937.75  4800.9  936.49  4832.3  936.56  4909.3  936.42  4929.4  935.62
  4962.2  935.43  4997.4  933.13  5012.1  932.82  5012.3  932.32  5015.8  932.32
  5016.1  932.82  5056.5  935.02  5099.0  933.83  5127.2  934.10  5141.4  934.60
  5155.5  936.14  5226.2  939.32  5296.9  941.75  5381.8  945.60  5424.2  946.62
#Mann=6,-1,0
  4193.7    0.12       0  4317.3    0.07       0  4604.0    0.12       0
  4832.3    0.07       0  5012.1    0.05       0  5016.1    0.07       0
Bank Sta=5012.1,5016.1
Exp/Cntr=0.3,0.1

Type RM Length L Ch R = 1,207,0,0,0
BEGIN DESCRIPTION:
XS7888
END DESCRIPTION:
XS GIS Cut Line= 4
      2200622.92     13812311.42      2200747.92     13811557.99
      2200654.17     13811235.07      2200301.07     13810989.29
#Sta/Elev= 30
  4110.5  940.72  4302.3  937.57  4390.5  935.19  4518.9  932.63  4523.9  933.46
  4767.8  933.11  4903.0  931.82  4960.6  929.90  4981.5  926.68  4991.9  926.55
  5002.3  927.29  5008.9  926.62  5023.1  928.55  5081.2  929.16  5086.4  930.12
  5114.7  928.61  5127.3  929.23  5137.7  928.27  5151.5  925.58  5151.7  925.08
  5155.5  925.58  5192.2  929.51  5257.4  931.18  5268.1  932.14  5274.2  931.20
  5329.6  935.01  5390.3  940.98  5426.0  943.41  5513.5  946.49  5640.7  947.76
#Mann=8,-1,0
  4110.5    0.12       0  4302.3    0.07       0  4390.5    0.12       0
  5151.5    0.05       0  5155.5    0.12       0  5257.4    0.07       0
  5329.6    0.12       0  5513.5    0.07       0
Bank Sta=5151.5,5155.5
Exp/Cntr=0.3,0.1

Chan Stop Cuts=-1