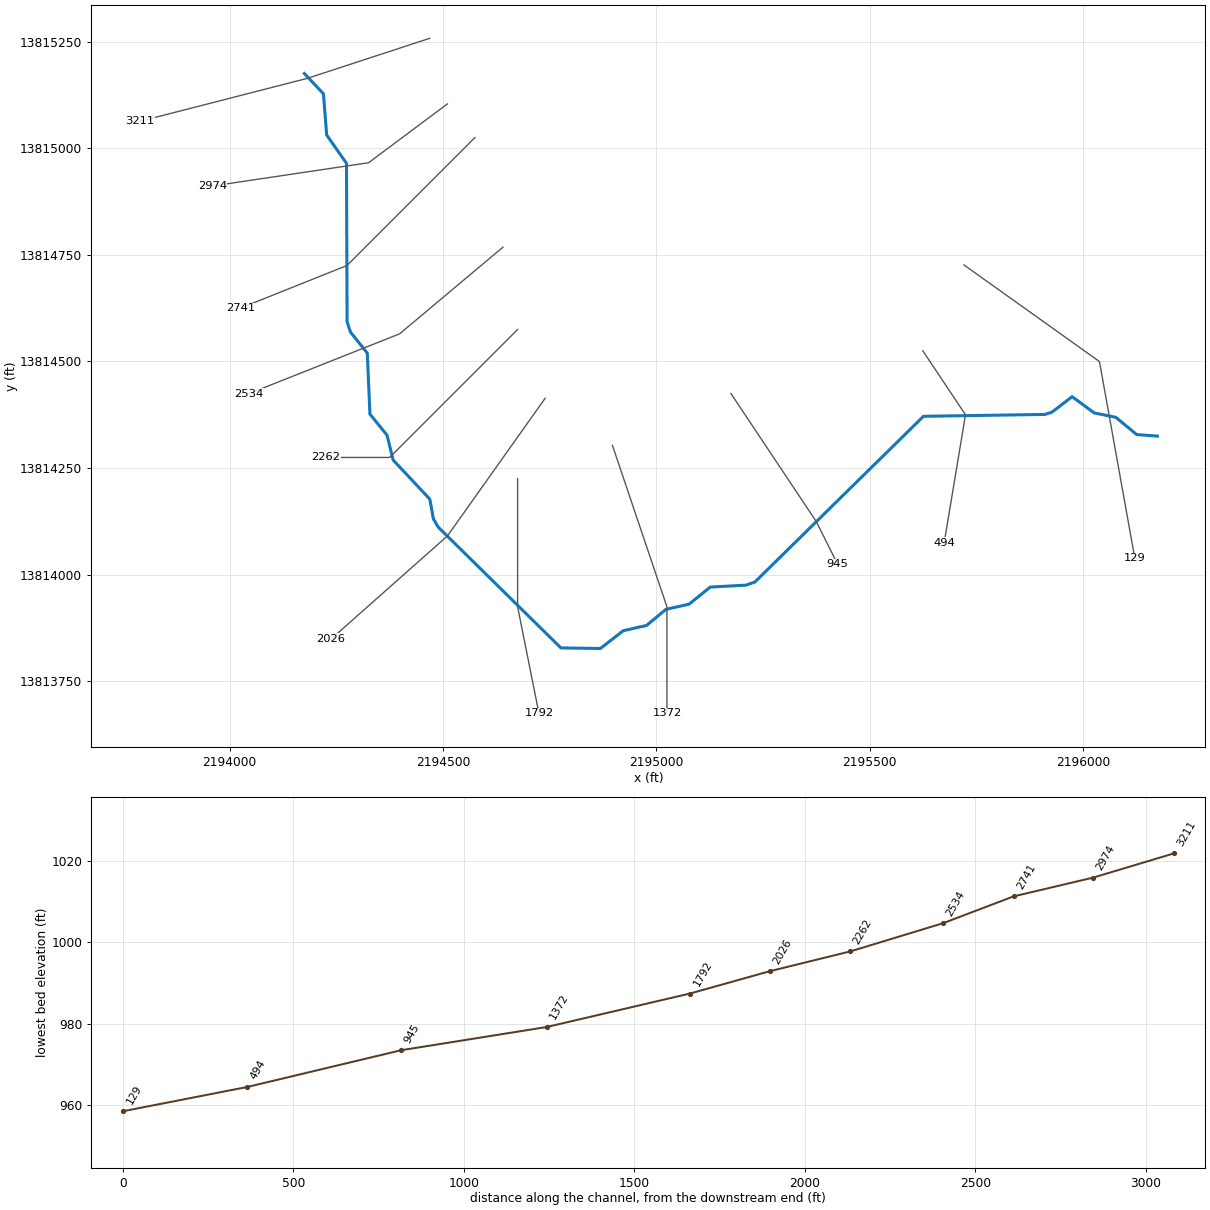
--- Upper Dry Comal Tributary 17.prj (project) ---

Proj Title=Upper Dry Comal Tributary 17 Base Level Engineering
Current Plan=p01
Default Exp/Contr=0.3,0.1
English Units
Geom File=g01
Flow File=f01
Plan File=p01
BEGIN DESCRIPTION:
Upper Dry Comal Tributary 17
END DESCRIPTION:

--- Upper Dry Comal Tributary 17.p01 (plan) ---

Plan Title=Multiple Run
Short Identifier=Multiple
Geom File=g01
Flow File=f01
Subcritical Flow
K Sum by GR= 0
Std Step Tol= 0.01
Critical Tol= 0.01
Num of Std Step Trials= 20
Max Error Tol= 0.3
Flow Tol Ratio= 0.001
Split Flow NTrial= 30
Split Flow Tol= 0.02
Split Flow Ratio= 0.02
Log Output Level= 0
Friction Slope Method= 1
Unsteady Friction Slope Method= 2
Unsteady Bridges Friction Slope Method= 1
Parabolic Critical Depth
Global Vel Dist=  1 , 1 , 1
Global Log Level= 0
CheckData=True
Encroach Param= -1, 0, 0, 0
BEGIN DESCRIPTION:
Multiple Run
END DESCRIPTION:

--- Upper Dry Comal Tributary 17.f01 (steady flow) ---

Flow Title=Multiple
Number of Profiles=7
Profile Names=10-year,25-year,50-year,1pct_min,100-year,1pct_plu,500-year
River Rch & RM= Upper Dry Comal ,Reach-1,3211
     708    1174    1608    1070    2135    4260    3718
Boundary for River Rch & Prof#=Upper Dry Comal ,Reach-1,1
Up Type=0
Dn Type=3
Dn Slope=0.005
Boundary for River Rch & Prof#=Upper Dry Comal ,Reach-1,2
Up Type=0
Dn Type=3
Dn Slope=0.005
Boundary for River Rch & Prof#=Upper Dry Comal ,Reach-1,3
Up Type=0
Dn Type=3
Dn Slope=0.005
Boundary for River Rch & Prof#=Upper Dry Comal ,Reach-1,4
Up Type=0
Dn Type=3
Dn Slope=0.005
Boundary for River Rch & Prof#=Upper Dry Comal ,Reach-1,5
Up Type=0
Dn Type=3
Dn Slope=0.005
Boundary for River Rch & Prof#=Upper Dry Comal ,Reach-1,6
Up Type=0
Dn Type=3
Dn Slope=0.005
Boundary for River Rch & Prof#=Upper Dry Comal ,Reach-1,7
Up Type=0
Dn Type=3
Dn Slope=0.005

--- Upper Dry Comal Tributary 17.g01 (geometry) ---

Geom Title=Existing Conditions

River Reach=Upper Dry Comal ,Reach-1
Reach XY= 30
      2194175.00     13815175.00      2194219.78     13815127.55
      2194227.32     13815030.96      2194273.78     13814964.50
      2194275.21     13814593.27      2194283.14     13814568.94
      2194322.61     13814519.47      2194328.76     13814376.56
      2194368.86     13814327.17      2194383.16     13814268.95
      2194469.13     13814177.28      2194477.53     13814131.05
      2194488.63     13814111.79      2194776.50     13813828.46
      2194869.03     13813827.14      2194922.82     13813868.88
      2194977.20     13813881.08      2195022.80     13813918.92
      2195077.18     13813931.12      2195126.59     13813971.17
      2195209.78     13813975.52      2195231.17     13813982.86
      2195626.46     13814371.46      2195911.14     13814375.83
      2195927.45     13814381.02      2195975.01     13814417.47
      2196026.63     13814379.41      2196077.24     13814369.08
      2196126.49     13814328.60      2196175.00     13814325.00

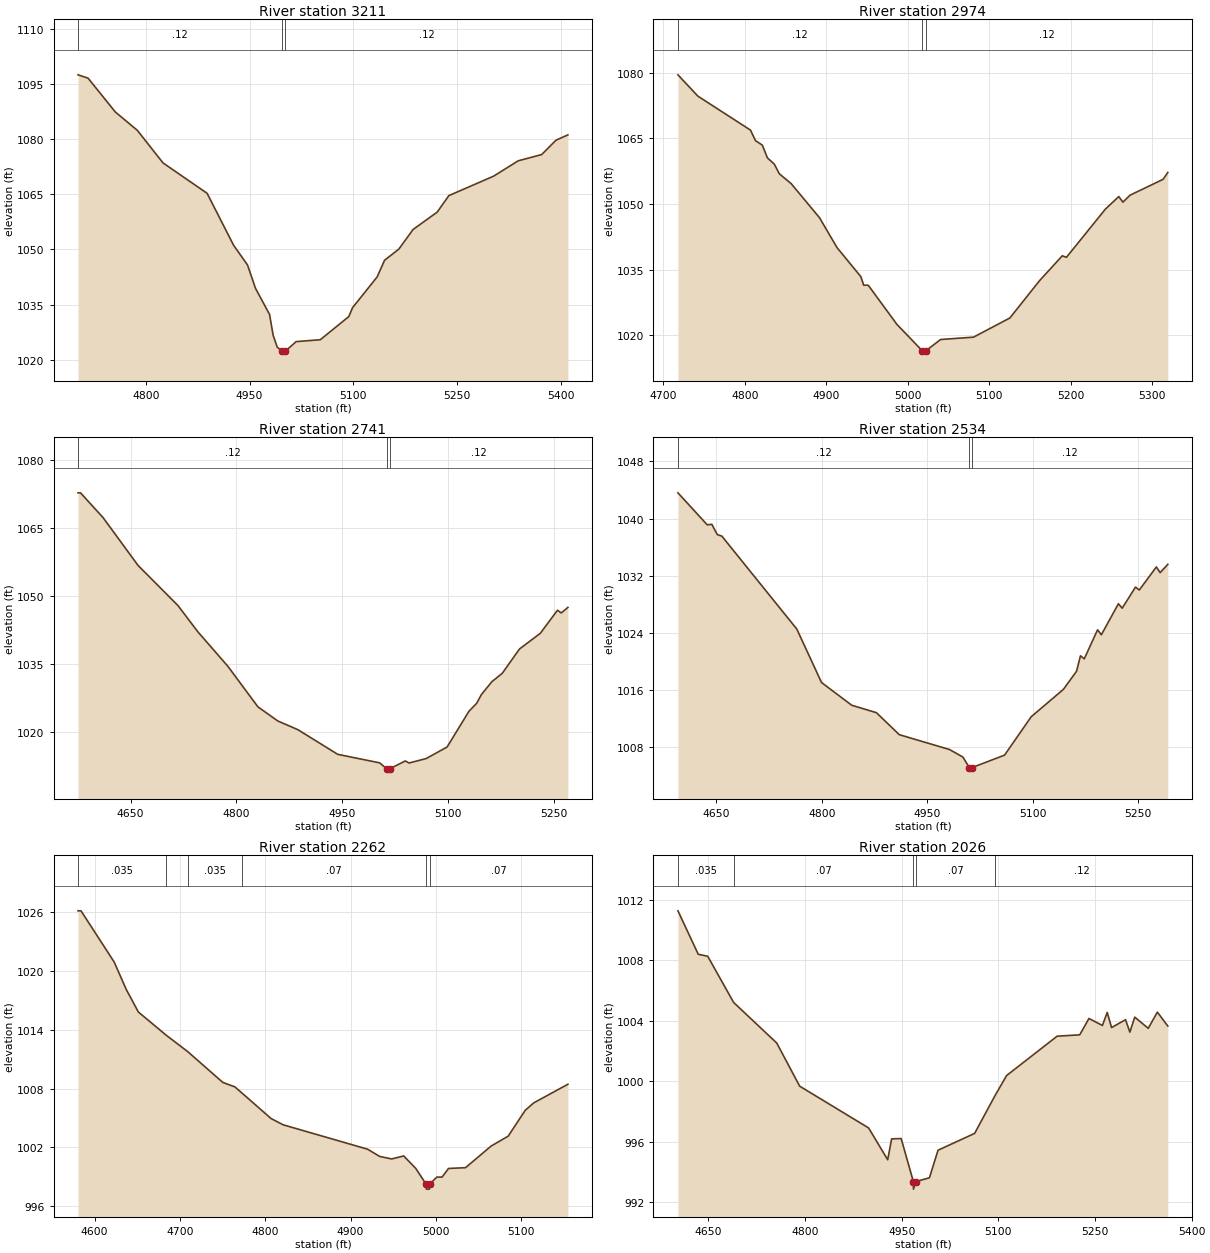
Type RM Length L Ch R = 1,3211,237,237,237
BEGIN DESCRIPTION:
XS7895
END DESCRIPTION:
XS GIS Cut Line= 3
      2194468.75     13815257.55      2194182.29     13815163.80
      2193788.26     13815062.70
#Sta/Elev= 30
  4702.1 1097.44  4716.6 1096.54  4756.0 1087.34  4787.8 1082.36  4824.9 1073.51
  4888.7 1065.24  4927.0 1051.12  4947.1 1045.77  4958.6 1039.44  4979.0 1032.31
  4984.2 1026.63  4990.1 1023.42  4997.5 1022.30  4997.7 1021.80  5001.5 1022.30
  5017.5 1024.93  5052.3 1025.44  5093.6 1031.74  5099.0 1034.16  5134.6 1042.53
  5145.2 1047.03  5165.9 1050.08  5186.5 1055.41  5221.3 1060.12  5238.2 1064.61
  5302.9 1069.90  5338.5 1074.07  5372.4 1075.77  5393.0 1079.66  5410.3 1081.12
#Mann=3,-1,0
  4702.1    0.12       0  4997.5    0.05       0  5001.5    0.12       0
Bank Sta=4997.5,5001.5
Exp/Cntr=0.3,0.1

Type RM Length L Ch R = 1,2974,233,233,233
BEGIN DESCRIPTION:
XS7894
END DESCRIPTION:
XS GIS Cut Line= 3
      2194510.42     13815103.91      2194325.52     13814965.89
      2193959.20     13814911.33
#Sta/Elev= 30
  4717.8 1079.58  4742.2 1074.71  4806.8 1066.92  4813.0 1064.50  4821.4 1063.47
  4827.6 1060.56  4836.0 1059.14  4842.2 1056.92  4856.8 1054.65  4891.5 1046.86
  4913.1 1039.99  4942.3 1033.35  4945.7 1031.40  4951.3 1031.40  4986.5 1022.43
  5017.8 1016.35  5018.1 1015.85  5021.8 1016.35  5040.1 1018.97  5080.5 1019.51
  5125.1 1023.90  5161.4 1032.42  5189.4 1038.14  5194.5 1037.79  5242.3 1048.83
  5258.7 1051.70  5263.8 1050.43  5272.6 1052.02  5313.0 1055.64  5318.9 1057.21
#Mann=3,-1,0
  4717.8    0.12       0  5017.8    0.05       0  5021.8    0.12       0
Bank Sta=5017.8,5021.8
Exp/Cntr=0.3,0.1

Type RM Length L Ch R = 1,2741,207,207,207
BEGIN DESCRIPTION:
Upper Dry Comal Tributary 17 6.0
END DESCRIPTION:
XS GIS Cut Line= 3
      2194575.00     13815025.00      2194275.00     13814725.00
      2194025.02     13814625.01
#Sta/Elev= 30
  4575.7 1072.80  4579.2 1072.80  4611.1 1067.33  4660.6 1056.76  4717.1 1047.88
  4745.4 1042.05  4787.8 1034.44  4830.3 1025.48  4858.5 1022.34  4886.8 1020.43
  4943.4 1014.96  5002.7 1013.08  5012.8 1011.75  5013.0 1011.25  5016.5 1011.25
  5016.8 1011.75  5039.0 1013.50  5044.4 1013.05  5068.6 1014.03  5098.2 1016.59
  5129.2 1024.51  5140.0 1026.24  5146.7 1028.17  5161.5 1031.02  5176.3 1032.89
  5200.6 1038.25  5230.2 1041.74  5254.4 1046.83  5259.8 1046.24  5269.2 1047.46
#Mann=3,-1,0
  4575.7    0.12       0  5012.8    0.05       0  5016.8    0.12       0
Bank Sta=5012.8,5016.8
Exp/Cntr=0.3,0.1

Type RM Length L Ch R = 1,2534,272,272,272
BEGIN DESCRIPTION:
XS7893
END DESCRIPTION:
XS GIS Cut Line= 3
      2194640.59     13814767.94      2194398.44     13814564.84
      2194044.28     13814424.22
#Sta/Elev= 30
  4595.3 1043.60  4637.0 1039.12  4643.5 1039.20  4651.3 1037.76  4657.8 1037.54
  4764.5 1024.53  4799.6 1017.06  4842.6 1013.88  4877.7 1012.84  4910.3 1009.76
  4981.8 1007.68  5000.8 1006.63  5009.9 1005.16  5010.1 1004.66  5013.9 1005.16
  5060.1 1006.90  5098.0 1012.27  5143.8 1016.10  5162.5 1018.63  5168.1 1020.80
  5173.5 1020.37  5192.4 1024.43  5197.8 1023.74  5222.1 1028.08  5227.5 1027.46
  5246.4 1030.41  5251.8 1030.00  5276.1 1033.23  5281.5 1032.43  5292.4 1033.60
#Mann=3,-1,0
  4595.3    0.12       0  5009.9    0.05       0  5013.9    0.12       0
Bank Sta=5009.9,5013.9
Exp/Cntr=0.3,0.1

Type RM Length L Ch R = 1,2262,236,236,236
BEGIN DESCRIPTION:
Upper Dry Comal Tributary 17 5.0
END DESCRIPTION:
XS GIS Cut Line= 3
      2194675.00     13814575.00      2194375.00     13814275.00
      2194224.97     13814275.00
#Sta/Elev= 30
  4580.5 1026.16  4584.0 1026.16  4622.9 1020.93  4637.1 1018.12  4651.2 1015.83
  4683.7 1013.47  4709.0 1011.79  4750.2 1008.64  4764.4 1008.18  4772.6 1007.56
  4806.8 1004.95  4820.9 1004.31  4919.9 1001.82  4934.1 1001.08  4948.2 1000.82
  4962.3 1001.13  4976.5  999.85  4988.6  998.24  4988.9  997.74  4992.4  997.74
  4992.6  998.24  5001.2  998.97  5007.3  998.97  5014.8  999.85  5034.8  999.93
  5064.8 1002.14  5084.8 1003.15  5104.8 1005.79  5114.8 1006.55  5154.8 1008.45
#Mann=6,-1,0
  4580.5   0.035       0  4683.7    0.12       0  4709.0   0.035       0
  4772.6    0.07       0  4988.6    0.05       0  4992.6    0.07       0
Bank Sta=4988.6,4992.6
Exp/Cntr=0.3,0.1

Type RM Length L Ch R = 1,2026,234,234,234
BEGIN DESCRIPTION:
XS7892
END DESCRIPTION:
XS GIS Cut Line= 3
      2194739.56     13814413.77      2194510.42     13814090.89
      2194237.72     13813849.36
#Sta/Elev= 30
  4602.8 1011.26  4634.3 1008.39  4649.0 1008.26  4689.2 1005.21  4756.1 1002.53
  4791.7  999.68  4898.7  996.92  4928.3  994.82  4934.4  996.20  4949.2  996.22
  4968.1  993.38  4968.3  992.88  4972.1  993.38  4993.1  993.63  5006.4  995.45
  5063.2  996.56  5094.9  999.06  5112.8 1000.38  5191.2 1002.98  5226.3 1003.07
  5240.6 1004.15  5261.5 1003.69  5269.0 1004.55  5275.7 1003.55  5297.4 1004.07
  5304.1 1003.25  5311.7 1004.24  5332.6 1003.50  5346.8 1004.57  5363.0 1003.65
#Mann=5,-1,0
  4602.8   0.035       0  4689.2    0.07       0  4968.1    0.05       0
  4972.1    0.07       0  5094.9    0.12       0
Bank Sta=4968.1,4972.1
Exp/Cntr=0.3,0.1

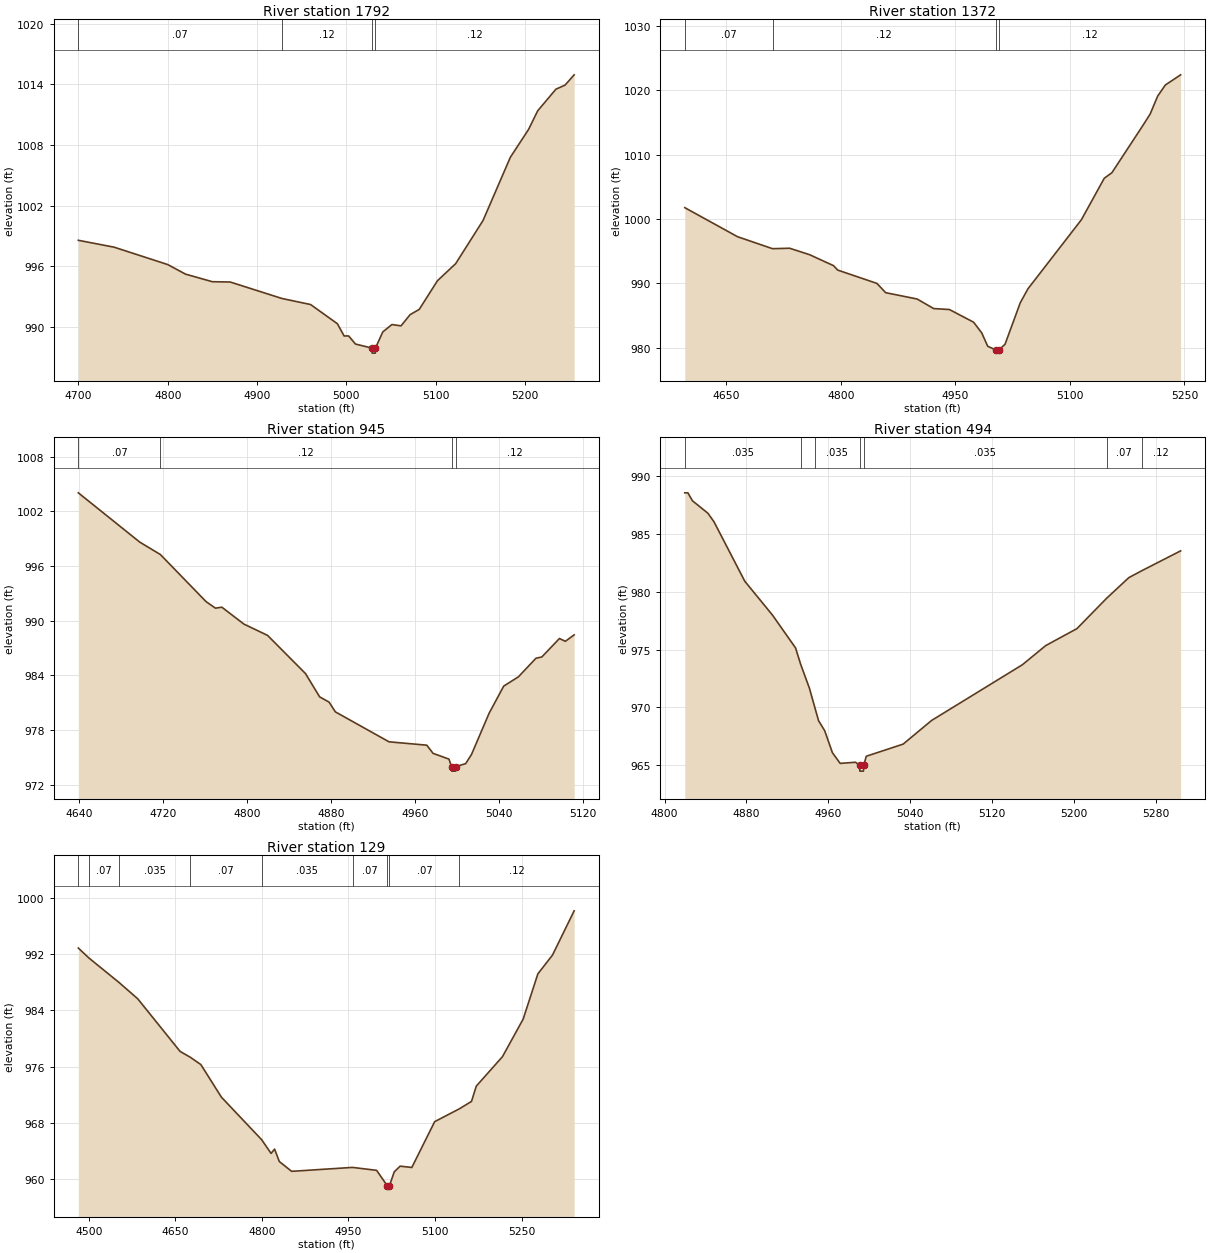
Type RM Length L Ch R = 1,1792,420,420,420
BEGIN DESCRIPTION:
Upper Dry Comal Tributary 17 4.0
END DESCRIPTION:
XS GIS Cut Line= 3
      2194675.00     13814225.05      2194675.00     13813925.00
      2194725.00     13813675.00
#Sta/Elev= 30
  4699.9  998.57  4739.9  997.89  4799.9  996.17  4819.9  995.22  4849.9  994.47
  4869.9  994.44  4927.8  992.81  4959.9  992.21  4989.9  990.31  4997.4  989.10
  5002.5  989.10  5010.1  988.30  5028.5  987.90  5028.8  987.40  5032.3  987.40
  5032.5  987.90  5040.7  989.50  5050.9  990.23  5061.1  990.10  5071.3  991.21
  5081.5  991.73  5101.9  994.57  5122.3  996.26  5152.9 1000.53  5183.5 1006.79
  5203.9 1009.55  5214.1 1011.39  5234.5 1013.53  5244.7 1013.93  5254.9 1014.95
#Mann=4,-1,0
  4699.9    0.07       0  4927.8    0.12       0  5028.5    0.05       0
  5032.5    0.12       0
Bank Sta=5028.5,5032.5
Exp/Cntr=0.3,0.1

Type RM Length L Ch R = 1,1372,427,427,427
BEGIN DESCRIPTION:
Upper Dry Comal Tributary 17 3.0
END DESCRIPTION:
XS GIS Cut Line= 3
      2194897.22     13814303.40      2195025.00     13813925.00
      2195025.00     13813675.00
#Sta/Elev= 30
  4595.6 1001.77  4664.7  997.26  4710.5  995.40  4732.9  995.47  4759.0  994.47
  4790.5  992.76  4795.8  992.08  4847.2  990.01  4858.7  988.57  4900.0  987.58
  4921.6  986.10  4942.2  985.95  4973.9  983.98  4984.5  982.32  4992.4  980.24
  5003.0  979.68  5003.2  979.18  5006.7  979.18  5007.0  979.68  5015.0  980.55
  5035.0  987.01  5045.0  989.16  5115.0  999.89  5145.0 1006.34  5155.0 1007.20
  5195.0 1014.43  5205.0 1016.29  5215.0 1019.11  5225.0 1020.82  5245.0 1022.40
#Mann=4,-1,0
  4595.6    0.07       0  4710.5    0.12       0  5003.0    0.05       0
  5007.0    0.12       0
Bank Sta=5003,5007
Exp/Cntr=0.3,0.1

Type RM Length L Ch R = 1,945,451,451,451
BEGIN DESCRIPTION:
Upper Dry Comal Tributary 17 2.0
END DESCRIPTION:
XS GIS Cut Line= 3
      2195174.99     13814425.02      2195375.00     13814125.00
      2195425.01     13814024.98
#Sta/Elev= 30
  4639.4 1004.05  4698.0  998.63  4717.6  997.27  4761.1  992.10  4770.1  991.38
  4776.1  991.49  4797.2  989.63  4819.7  988.39  4855.8  984.20  4869.3  981.64
  4878.3  981.06  4884.3  979.99  4935.4  976.70  4971.4  976.33  4977.4  975.43
  4992.5  974.80  4995.0  973.98  4995.2  973.48  4998.7  973.48  4999.0  973.98
  5008.4  974.30  5014.0  975.31  5030.7  979.82  5044.7  982.82  5058.7  983.84
  5075.4  985.88  5081.0  986.02  5097.8  988.05  5103.4  987.74  5111.8  988.45
#Mann=4,-1,0
  4639.4    0.07       0  4717.6    0.12       0  4995.0    0.05       0
  4999.0    0.12       0
Bank Sta=4995,4999
Exp/Cntr=0.3,0.1

Type RM Length L Ch R = 1,494,365,365,365
BEGIN DESCRIPTION:
Upper Dry Comal Tributary 17 1.0
END DESCRIPTION:
XS GIS Cut Line= 3
      2195624.99     13814525.02      2195725.00     13814375.00
      2195675.01     13814075.04
#Sta/Elev= 30
  4819.8  988.58  4822.8  988.58  4827.3  987.89  4842.4  986.81  4848.4  986.06
  4878.4  980.92  4905.5  977.98  4928.0  975.14  4933.0  973.72  4941.5  971.66
  4946.9  969.96  4950.5  968.83  4956.5  967.96  4964.0  966.06  4971.6  965.13
  4986.6  965.23  4990.6  964.96  4990.8  964.46  4994.3  964.46  4994.6  964.96
  4997.1  965.75  5033.1  966.80  5060.9  968.85  5149.6  973.68  5172.4  975.34
  5202.9  976.81  5231.9  979.44  5253.6  981.23  5266.3  981.83  5304.2  983.55
#Mann=7,-1,0
  4819.8   0.035       0  4933.0    0.07       0  4946.9   0.035       0
  4990.6   0.035       0  4994.6   0.035       0  5231.9    0.07       0
  5266.3    0.12       0
Bank Sta=4990.6,4994.6
Exp/Cntr=0.3,0.1

Type RM Length L Ch R = 1,129,0,0,0
BEGIN DESCRIPTION:
XS7891
END DESCRIPTION:
XS GIS Cut Line= 3
      2195721.38     13814726.28      2196039.06     13814499.74
      2196122.05     13814038.12
#Sta/Elev= 30
  4481.9  992.91  4500.2  991.49  4552.2  988.01  4584.8  985.67  4658.3  978.15
  4675.8  977.33  4694.2  976.28  4729.8  971.63  4799.5  965.56  4815.9  963.60
  4822.0  964.21  4830.2  962.44  4851.5  961.04  4957.1  961.60  4998.8  961.18
  5017.1  959.00  5017.4  958.50  5021.1  959.00  5029.3  960.96  5039.5  961.78
  5059.8  961.59  5099.4  968.13  5141.9  969.95  5163.2  971.02  5171.5  973.20
  5216.9  977.41  5252.8  982.78  5278.2  989.22  5303.6  991.91  5341.1  998.22
#Mann=9,-1,0
  4481.9    0.12       0  4500.2    0.07       0  4552.2   0.035       0
  4675.8    0.07       0  4799.5   0.035       0  4957.1    0.07       0
  5017.1    0.05       0  5021.1    0.07       0  5141.9    0.12       0
Bank Sta=5017.1,5021.1
Exp/Cntr=0.3,0.1

Chan Stop Cuts=-1