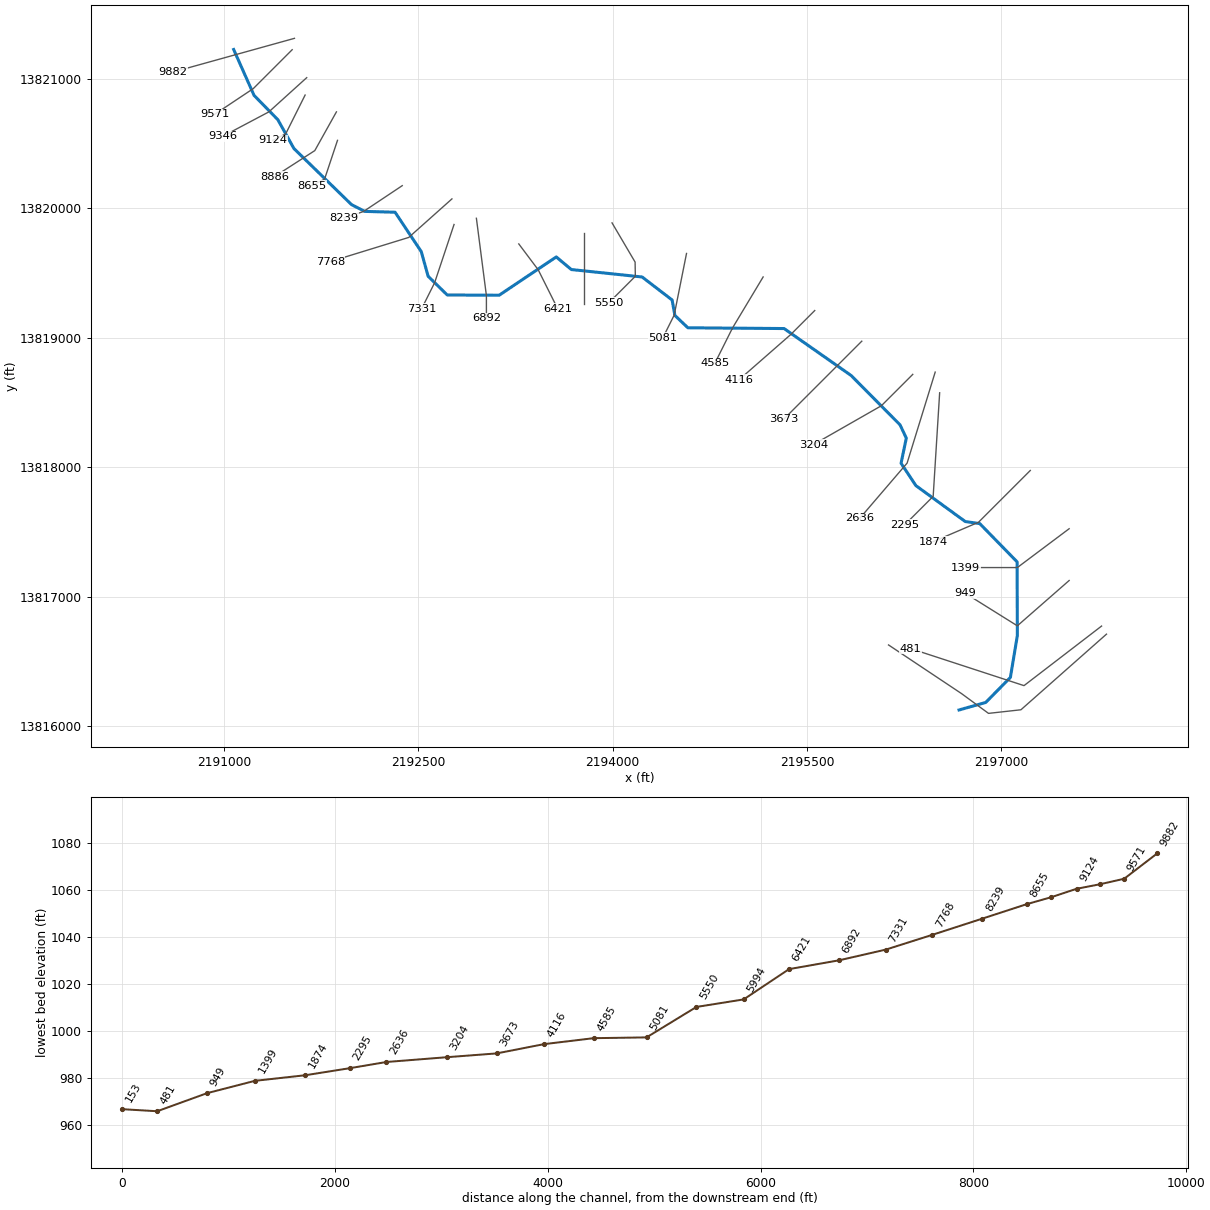
--- Upper Dry Comal Tributary 18.prj (project) ---

Proj Title=Upper Dry Comal Tributary 18 Base Level Engineering
Current Plan=p01
Default Exp/Contr=0.3,0.1
English Units
Geom File=g01
Flow File=f01
Plan File=p01
BEGIN DESCRIPTION:
Upper Dry Comal Tributary 18
END DESCRIPTION:

--- Upper Dry Comal Tributary 18.p01 (plan) ---

Plan Title=Multiple Run
Short Identifier=Multiple
Geom File=g01
Flow File=f01
Subcritical Flow
K Sum by GR= 0
Std Step Tol= 0.01
Critical Tol= 0.01
Num of Std Step Trials= 20
Max Error Tol= 0.3
Flow Tol Ratio= 0.001
Split Flow NTrial= 30
Split Flow Tol= 0.02
Split Flow Ratio= 0.02
Log Output Level= 0
Friction Slope Method= 1
Unsteady Friction Slope Method= 2
Unsteady Bridges Friction Slope Method= 1
Parabolic Critical Depth
Global Vel Dist=  1 , 1 , 1
Global Log Level= 0
CheckData=True
Encroach Param= -1, 0, 0, 0
BEGIN DESCRIPTION:
Multiple Run
END DESCRIPTION:

--- Upper Dry Comal Tributary 18.f01 (steady flow) ---

Flow Title=Multiple
Number of Profiles=7
Profile Names=10-year,25-year,50-year,1pct_min,100-year,1pct_plu,500-year
River Rch & RM= Upper Dry Comal ,Reach-1,9882
     555     903    1222     804    1605    3202    2730
River Rch & RM= Upper Dry Comal ,Reach-1,7331
    1131    1923    2679    1809    3609    7200    6477
River Rch & RM= Upper Dry Comal ,Reach-1,5081
    1653    2851    4008    2724    5436   10846    9904
Boundary for River Rch & Prof#=Upper Dry Comal ,Reach-1,1
Up Type=0
Dn Type=3
Dn Slope=0.005
Boundary for River Rch & Prof#=Upper Dry Comal ,Reach-1,2
Up Type=0
Dn Type=3
Dn Slope=0.005
Boundary for River Rch & Prof#=Upper Dry Comal ,Reach-1,3
Up Type=0
Dn Type=3
Dn Slope=0.005
Boundary for River Rch & Prof#=Upper Dry Comal ,Reach-1,4
Up Type=0
Dn Type=3
Dn Slope=0.005
Boundary for River Rch & Prof#=Upper Dry Comal ,Reach-1,5
Up Type=0
Dn Type=3
Dn Slope=0.005
Boundary for River Rch & Prof#=Upper Dry Comal ,Reach-1,6
Up Type=0
Dn Type=3
Dn Slope=0.005
Boundary for River Rch & Prof#=Upper Dry Comal ,Reach-1,7
Up Type=0
Dn Type=3
Dn Slope=0.005

--- Upper Dry Comal Tributary 18.g01 (geometry) ---

Geom Title=Existing Conditions

River Reach=Upper Dry Comal ,Reach-1
Reach XY= 30
      2191073.05     13821226.95      2191230.52     13820872.57
      2191414.22     13820684.68      2191538.63     13820461.79
      2191983.19     13820028.67      2192085.48     13819976.19
      2192319.56     13819969.82      2192521.51     13819666.53
      2192575.00     13819475.00      2192722.55     13819330.45
      2193123.45     13819328.75      2193564.36     13819624.44
      2193680.86     13819527.08      2194227.45     13819469.54
      2194458.87     13819292.05      2194480.49     13819172.55
      2194580.84     13819077.05      2195323.45     13819071.25
      2195841.67     13818708.35      2196219.19     13818327.29
      2196267.47     13818225.01      2196227.06     13818030.86
      2196341.50     13817857.95      2196722.58     13817580.54
      2196834.79     13817564.48      2197122.94     13817269.15
      2197125.11     13816699.88      2197071.26     13816376.53
      2196881.05     13816183.15      2196675.00     13816125.00

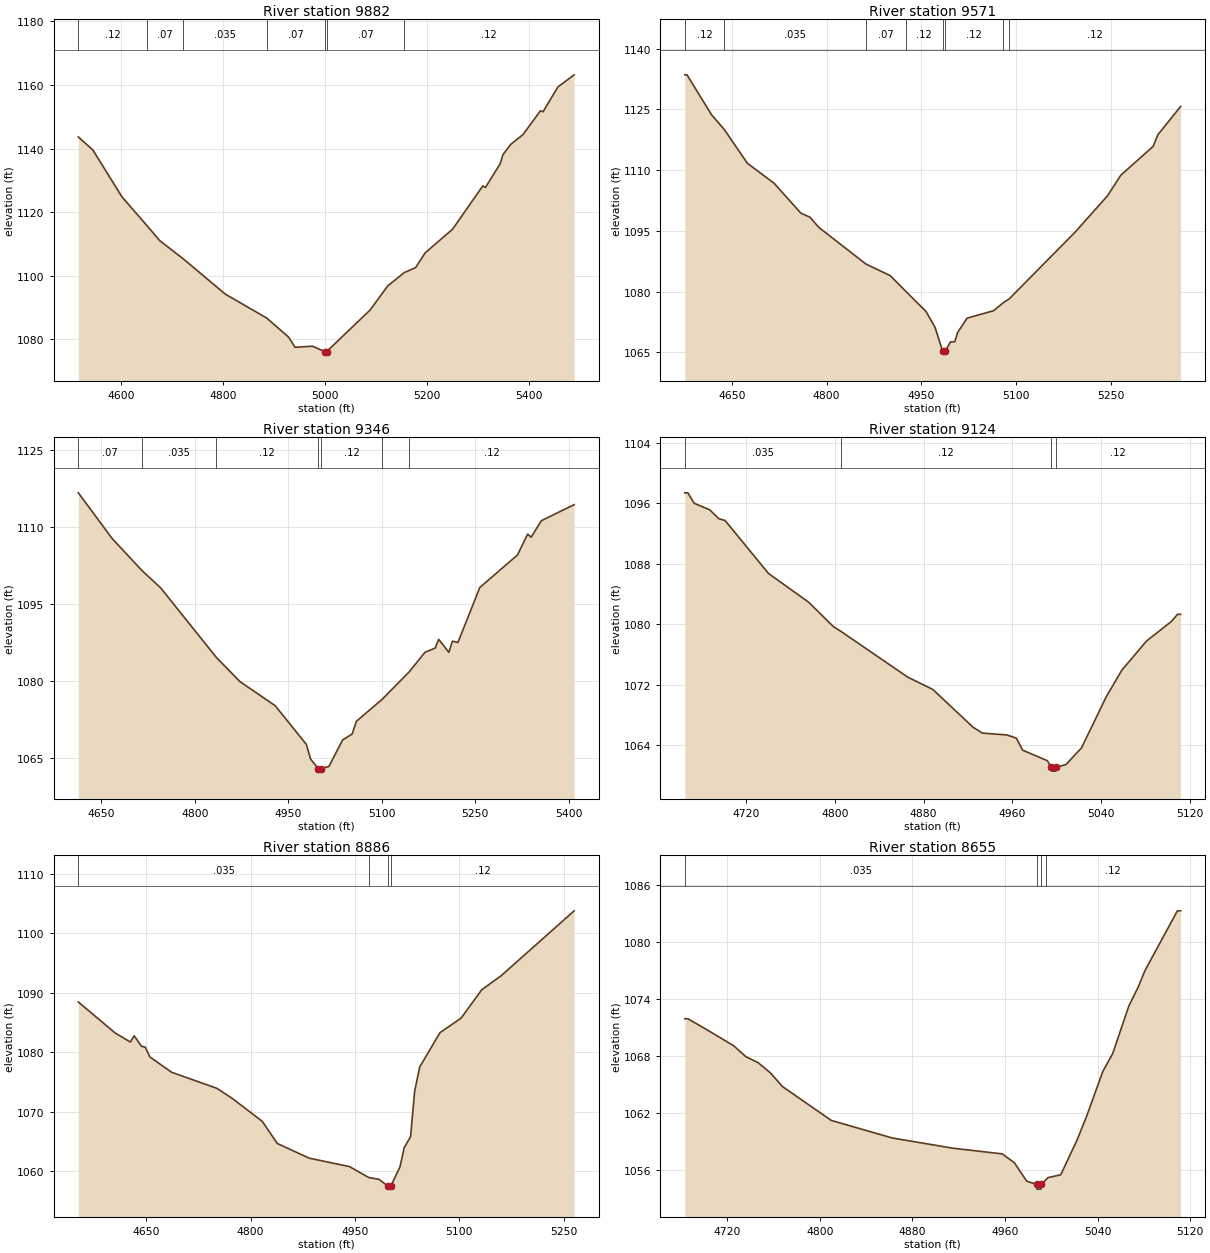
Type RM Length L Ch R = 1,9882,311,311,311
BEGIN DESCRIPTION:
XS7896
END DESCRIPTION:
XS GIS Cut Line= 2
      2191542.68     13821313.01      2190605.18     13821052.60
#Sta/Elev= 30
  4515.8 1143.65  4544.5 1139.51  4601.7 1124.73  4650.4 1115.77  4675.4 1111.05
  4721.9 1105.27  4804.0 1094.22  4886.0 1086.61  4928.5 1080.66  4941.1 1077.47
  4975.3 1077.81  4999.2 1076.13  4999.4 1075.63  5003.2 1076.13  5088.5 1089.21
  5122.7 1096.73  5155.1 1100.95  5177.6 1102.53  5196.4 1107.18  5250.3 1114.63
  5309.5 1128.24  5314.7 1127.75  5343.7 1135.23  5349.0 1138.05  5364.4 1141.32
  5388.4 1144.39  5422.6 1151.88  5427.8 1151.57  5456.9 1159.38  5488.8 1163.19
#Mann=7,-1,0
  4515.8    0.12       0  4650.4    0.07       0  4721.9   0.035       0
  4886.0    0.07       0  4999.2    0.05       0  5003.2    0.07       0
  5155.1    0.12       0
Bank Sta=4999.2,5003.2
Exp/Cntr=0.3,0.1

Type RM Length L Ch R = 1,9571,225,225,225
BEGIN DESCRIPTION:
Upper Dry Comal Tributary 18 21.0
END DESCRIPTION:
XS GIS Cut Line= 3
      2191524.99     13821224.99      2191225.00     13820925.00
      2190925.00     13820725.00
#Sta/Elev= 30
  4575.7 1133.54  4579.2 1133.54  4618.1 1123.67  4638.4 1120.00  4674.7 1111.71
  4717.1 1106.76  4759.5 1099.37  4773.7 1098.40  4787.8 1095.87  4862.3 1086.83
  4901.0 1083.94  4925.4 1080.10  4957.5 1075.11  4971.7 1071.22  4983.8 1065.32
  4984.1 1064.82  4987.8 1065.32  4996.4 1067.61  5003.0 1067.61  5007.5 1069.90
  5022.5 1073.45  5064.5 1075.30  5079.9 1077.28  5089.2 1078.22  5193.7 1094.73
  5244.8 1103.68  5265.9 1108.76  5316.9 1115.86  5324.4 1118.72  5360.5 1125.74
#Mann=8,-1,0
  4575.7    0.12       0  4638.4   0.035       0  4862.3    0.07       0
  4925.4    0.12       0  4983.8    0.05       0  4987.8    0.12       0
  5079.9    0.07       0  5089.2    0.12       0
Bank Sta=4983.8,4987.8
Exp/Cntr=0.3,0.1

Type RM Length L Ch R = 1,9346,222,222,222
BEGIN DESCRIPTION:
H21511
END DESCRIPTION:
XS GIS Cut Line= 3
      2191637.13     13821009.15      2191344.97     13820744.82
      2190990.30     13820557.05
#Sta/Elev= 30
  4613.3 1116.64  4667.5 1107.76  4715.6 1101.49  4745.2 1098.18  4834.6 1084.64
  4872.4 1079.94  4929.1 1075.23  4979.1 1067.70  4985.8 1064.87  4998.0 1063.01
  4998.3 1062.51  5002.0 1063.01  5015.2 1063.41  5037.3 1068.59  5052.5 1069.72
  5059.3 1072.20  5100.7 1076.49  5144.0 1081.82  5169.3 1085.62  5185.6 1086.44
  5191.3 1088.14  5207.6 1085.63  5213.3 1087.78  5222.2 1087.54  5257.3 1098.23
  5317.6 1104.54  5334.0 1108.61  5339.6 1108.01  5356.0 1111.22  5408.6 1114.34
#Mann=7,-1,0
  4613.3    0.07       0  4715.6   0.035       0  4834.6    0.12       0
  4998.0    0.05       0  5002.0    0.12       0  5100.7    0.07       0
  5144.0    0.12       0
Bank Sta=4998,5002
Exp/Cntr=0.3,0.1

Type RM Length L Ch R = 1,9124,238,238,238
BEGIN DESCRIPTION:
Upper Dry Comal Tributary 18 20.0
END DESCRIPTION:
XS GIS Cut Line= 3
      2191625.00     13820874.99      2191475.00     13820575.00
      2191375.00     13820525.00
#Sta/Elev= 30
  4664.6 1097.41  4667.4 1097.41  4673.0 1096.03  4687.0 1095.17  4695.3 1093.98
  4700.9 1093.75  4740.1 1086.73  4776.4 1082.91  4798.8 1079.67  4805.6 1079.04
  4865.8 1072.99  4888.2 1071.38  4924.5 1066.38  4932.9 1065.59  4955.3 1065.34
  4963.7 1064.91  4969.3 1063.33  4991.6 1061.93  4995.2 1061.05  4995.5 1060.55
  4999.0 1060.55  4999.2 1061.05  5008.4 1061.42  5022.4 1063.63  5044.7 1070.39
  5058.7 1073.91  5081.1 1077.79  5103.4 1080.36  5109.0 1081.32  5111.8 1081.32
#Mann=4,-1,0
  4664.6   0.035       0  4805.6    0.12       0  4995.2    0.05       0
  4999.2    0.12       0
Bank Sta=4995.2,4999.2
Exp/Cntr=0.3,0.1

Type RM Length L Ch R = 1,8886,231,231,231
BEGIN DESCRIPTION:
H21510
END DESCRIPTION:
XS GIS Cut Line= 3
      2191866.64     13820744.85      2191699.69     13820445.74
      2191388.38     13820245.12
#Sta/Elev= 30
  4552.2 1088.46  4605.2 1083.24  4626.9 1081.73  4632.6 1082.76  4642.9 1081.02
  4648.6 1080.84  4655.1 1079.21  4686.3 1076.64  4751.5 1073.93  4773.2 1072.26
  4816.6 1068.39  4838.3 1064.66  4884.1 1062.19  4942.1 1060.77  4969.8 1058.93
  4984.4 1058.63  4997.5 1057.48  4997.8 1056.98  5001.3 1056.98  5001.5 1057.48
  5014.7 1060.73  5020.7 1063.94  5029.9 1065.81  5035.8 1073.48  5043.1 1077.54
  5072.2 1083.30  5102.5 1085.74  5132.3 1090.52  5159.9 1092.85  5265.1 1103.79
#Mann=4,-1,0
  4552.2   0.035       0  4969.8    0.12       0  4997.5    0.05       0
  5001.5    0.12       0
Bank Sta=4997.5,5001.5
Exp/Cntr=0.3,0.1

Type RM Length L Ch R = 1,8655,416,416,416
BEGIN DESCRIPTION:
Upper Dry Comal Tributary 18 19.0
END DESCRIPTION:
XS GIS Cut Line= 3
      2191875.01     13820525.02      2191775.00     13820225.00
      2191674.96     13820174.98
#Sta/Elev= 30
  4683.5 1071.93  4686.2 1071.93  4704.6 1070.63  4725.7 1069.09  4736.2 1067.94
  4746.8 1067.31  4757.3 1066.25  4767.8 1064.80  4810.0 1061.23  4862.7 1059.38
  4915.4 1058.30  4957.6 1057.71  4968.1 1056.77  4978.7 1054.84  4987.2 1054.50
  4987.5 1054.00  4991.0 1054.00  4991.2 1054.50  4995.2 1054.98  4997.1 1055.21
  5008.1 1055.51  5022.1 1059.15  5030.5 1061.69  5044.5 1066.41  5052.9 1068.25
  5066.8 1073.24  5075.2 1075.33  5080.8 1077.00  5108.8 1083.29  5111.6 1083.29
#Mann=4,-1,0
  4683.5   0.035       0  4987.2    0.05       0  4991.2   0.035       0
  4995.2    0.12       0
Bank Sta=4987.2,4991.2
Exp/Cntr=0.3,0.1

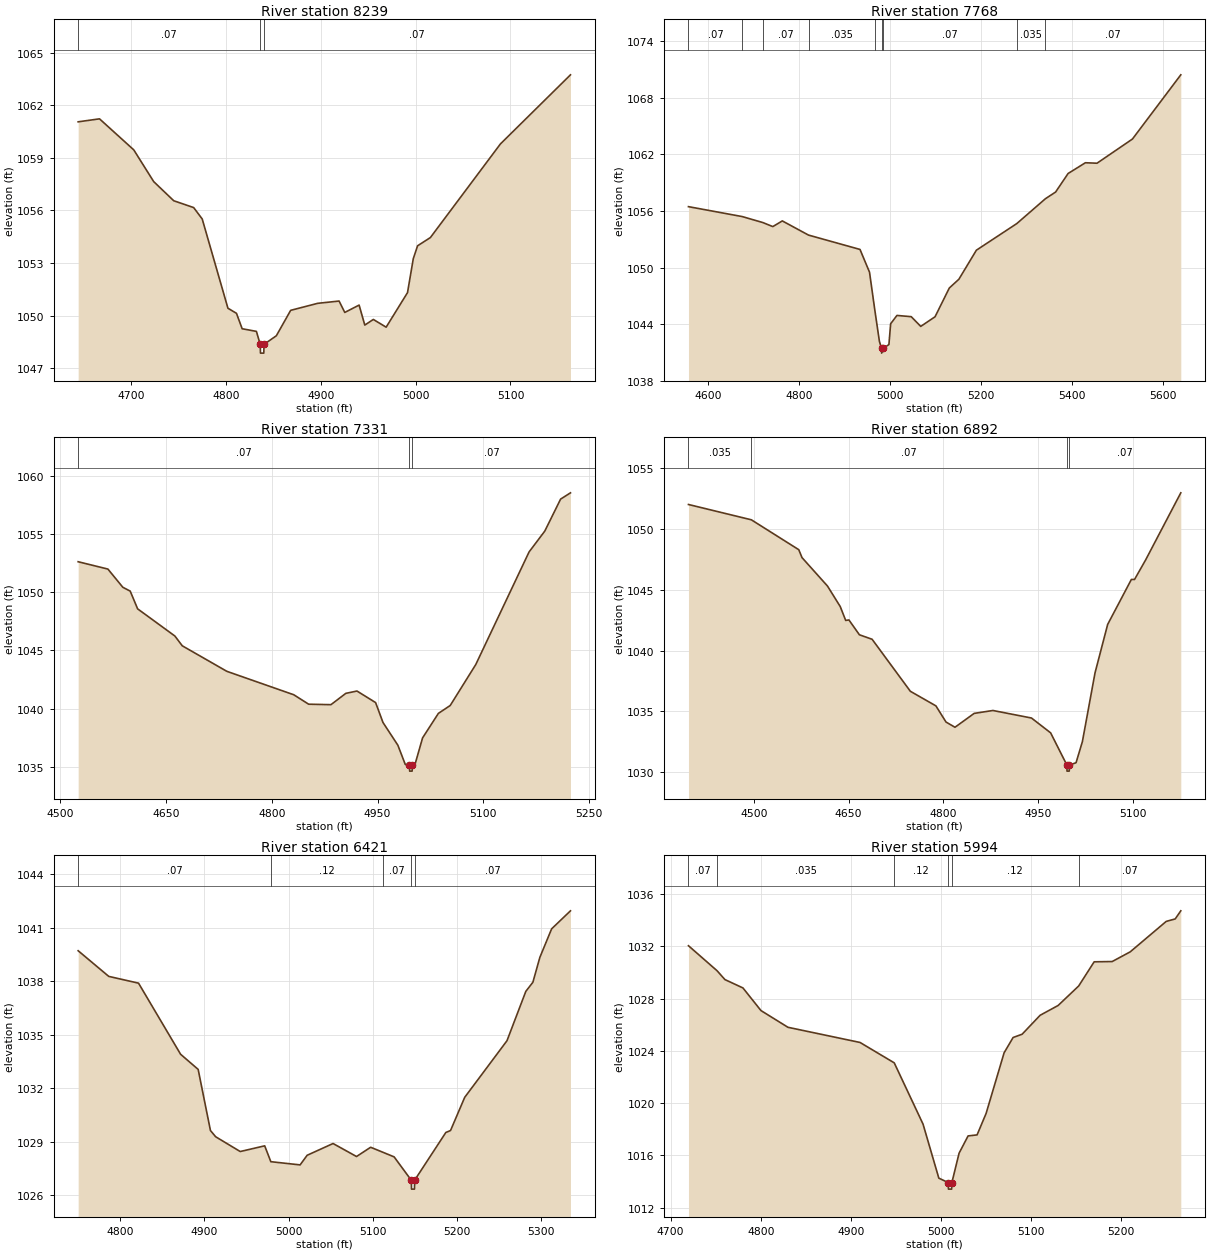
Type RM Length L Ch R = 1,8239,471,471,471
BEGIN DESCRIPTION:
Upper Dry Comal Tributary 18 18.0
END DESCRIPTION:
XS GIS Cut Line= 3
      2192375.01     13820175.01      2192075.00     13819975.00
      2191924.98     13819924.99
#Sta/Elev= 30
  4644.5 1061.05  4667.0 1061.22  4703.1 1059.45  4724.1 1057.64  4745.2 1056.55
  4766.2 1056.16  4775.2 1055.51  4802.3 1050.42  4811.3 1050.13  4817.3 1049.25
  4832.3 1049.10  4836.3 1048.36  4836.6 1047.86  4840.1 1047.86  4840.3 1048.36
  4853.3 1048.85  4868.4 1050.30  4896.9 1050.70  4919.4 1050.83  4925.4 1050.18
  4940.5 1050.60  4946.5 1049.46  4955.5 1049.78  4969.0 1049.34  4991.5 1051.31
  4997.6 1053.25  5002.1 1053.98  5015.6 1054.45  5089.4 1059.79  5163.2 1063.73
#Mann=3,-1,0
  4644.5    0.07       0  4836.3    0.05       0  4840.3    0.07       0
Bank Sta=4836.3,4840.3
Exp/Cntr=0.3,0.1

Type RM Length L Ch R = 1,7768,437,437,437
BEGIN DESCRIPTION:
Upper Dry Comal Tributary 18 17.0
END DESCRIPTION:
XS GIS Cut Line= 3
      2192758.78     13820072.78      2192425.00     13819775.00
      2191819.14     13819588.55
#Sta/Elev= 30
  4557.6 1056.45  4675.6 1055.40  4720.7 1054.77  4742.8 1054.34  4763.7 1054.94
  4821.2 1053.44  4934.3 1051.92  4955.2 1049.51  4966.7 1045.55  4976.9 1042.19
  4981.6 1041.44  4981.8 1040.94  4985.6 1041.44  4997.8 1041.85  5001.6 1044.05
  5015.4 1044.93  5046.8 1044.80  5067.7 1043.77  5099.1 1044.79  5130.5 1047.84
  5151.4 1048.76  5189.9 1051.84  5278.7 1054.66  5341.5 1057.29  5363.9 1058.00
  5391.3 1059.96  5429.3 1061.10  5454.8 1061.05  5532.6 1063.61  5638.8 1070.41
#Mann=9,-1,0
  4557.6    0.07       0  4675.6   0.035       0  4720.7    0.07       0
  4821.2   0.035       0  4966.7    0.07       0  4981.6    0.05       0
  4985.6    0.07       0  5278.7   0.035       0  5341.5    0.07       0
Bank Sta=4981.6,4985.6
Exp/Cntr=0.3,0.1

Type RM Length L Ch R = 1,7331,439,439,439
BEGIN DESCRIPTION:
Upper Dry Comal Tributary 18 16.0
END DESCRIPTION:
XS GIS Cut Line= 3
      2192775.01     13819875.02      2192625.00     13819425.00
      2192524.99     13819224.97
#Sta/Elev= 30
  4525.6 1052.61  4567.8 1051.98  4588.9 1050.42  4599.4 1050.09  4609.9 1048.57
  4662.7 1046.24  4673.2 1045.40  4736.4 1043.21  4831.3 1041.20  4852.4 1040.39
  4884.0 1040.35  4905.1 1041.32  4920.9 1041.52  4947.3 1040.53  4957.8 1038.82
  4978.9 1036.87  4989.4 1035.22  4995.3 1035.15  4995.6 1034.65  4999.1 1034.65
  4999.3 1035.15  5002.8 1035.15  5013.9 1037.50  5036.3 1039.60  5053.1 1040.28
  5089.4 1043.80  5164.9 1053.45  5187.2 1055.24  5209.6 1057.98  5223.6 1058.52
#Mann=3,-1,0
  4525.6    0.07       0  4995.3    0.05       0  4999.3    0.07       0
Bank Sta=4995.3,4999.3
Exp/Cntr=0.3,0.1

Type RM Length L Ch R = 1,6892,471,471,471
BEGIN DESCRIPTION:
Upper Dry Comal Tributary 18 15.0
END DESCRIPTION:
XS GIS Cut Line= 4
      2192947.63     13819923.13      2193025.00     13819325.00
      2193025.00     13819225.00      2193025.00     13819149.31
#Sta/Elev= 30
  4396.8 1052.03  4496.3 1050.77  4571.3 1048.31  4576.4 1047.66  4616.7 1045.32
  4636.9 1043.63  4645.5 1042.49  4650.6 1042.53  4667.2 1041.31  4687.3 1040.94
  4747.8 1036.66  4788.2 1035.46  4804.2 1034.13  4818.4 1033.70  4848.7 1034.84
  4878.4 1035.08  4939.4 1034.46  4969.7 1033.24  4995.4 1030.59  4995.6 1030.09
  4999.1 1030.09  4999.4 1030.59  5009.9 1030.78  5019.9 1032.51  5039.9 1038.17
  5059.9 1042.16  5097.4 1045.86  5102.4 1045.86  5119.9 1047.46  5175.6 1052.99
#Mann=4,-1,0
  4396.8   0.035       0  4496.3    0.07       0  4995.4    0.05       0
  4999.4    0.07       0
Bank Sta=4995.4,4999.4
Exp/Cntr=0.3,0.1

Type RM Length L Ch R = 1,6421,427,427,427
BEGIN DESCRIPTION:
Upper Dry Comal Tributary 18 14.0
END DESCRIPTION:
XS GIS Cut Line= 3
      2193275.02     13819724.97      2193425.00     13819525.00
      2193575.01     13819224.97
#Sta/Elev= 30
  4749.8 1039.71  4786.2 1038.27  4821.6 1037.89  4871.6 1033.90  4892.5 1033.05
  4907.1 1029.62  4913.3 1029.27  4942.5 1028.44  4971.6 1028.76  4978.9 1027.87
  5013.7 1027.69  5022.1 1028.23  5052.9 1028.89  5080.8 1028.16  5097.6 1028.68
  5112.6 1028.39  5125.5 1028.14  5145.9 1026.83  5146.2 1026.33  5149.7 1026.33
  5149.9 1026.83  5187.0 1029.51  5192.6 1029.62  5209.4 1031.48  5259.7 1034.66
  5282.1 1037.43  5290.5 1037.94  5298.8 1039.34  5312.8 1040.94  5335.2 1041.95
#Mann=5,-1,0
  4749.8    0.07       0  4978.9    0.12       0  5112.6    0.07       0
  5145.9    0.05       0  5149.9    0.07       0
Bank Sta=5145.9,5149.9
Exp/Cntr=0.3,0.1

Type RM Length L Ch R = 1,5994,444,444,444
BEGIN DESCRIPTION:
Upper Dry Comal Tributary 18 13.0
END DESCRIPTION:
XS GIS Cut Line= 5
      2193775.00     13819805.47      2193775.00     13819625.00
      2193775.00     13819525.00      2193775.00     13819425.00
      2193775.00     13819258.77
#Sta/Elev= 30
  4719.8 1032.04  4751.5 1030.13  4760.3 1029.45  4780.3 1028.81  4800.3 1027.08
  4830.3 1025.80  4910.3 1024.64  4948.3 1023.08  4980.3 1018.39  4997.8 1014.26
  5008.3 1013.92  5008.5 1013.42  5012.0 1013.42  5012.3 1013.92  5020.3 1016.17
  5030.3 1017.49  5040.3 1017.57  5050.3 1019.21  5070.3 1023.85  5080.3 1025.02
  5090.3 1025.27  5110.3 1026.72  5130.3 1027.47  5153.1 1028.96  5170.3 1030.81
  5190.3 1030.83  5210.3 1031.57  5250.3 1033.90  5260.3 1034.09  5266.5 1034.71
#Mann=6,-1,0
  4719.8    0.07       0  4751.5   0.035       0  4948.3    0.12       0
  5008.3    0.05       0  5012.3    0.12       0  5153.1    0.07       0
Bank Sta=5008.3,5012.3
Exp/Cntr=0.3,0.1

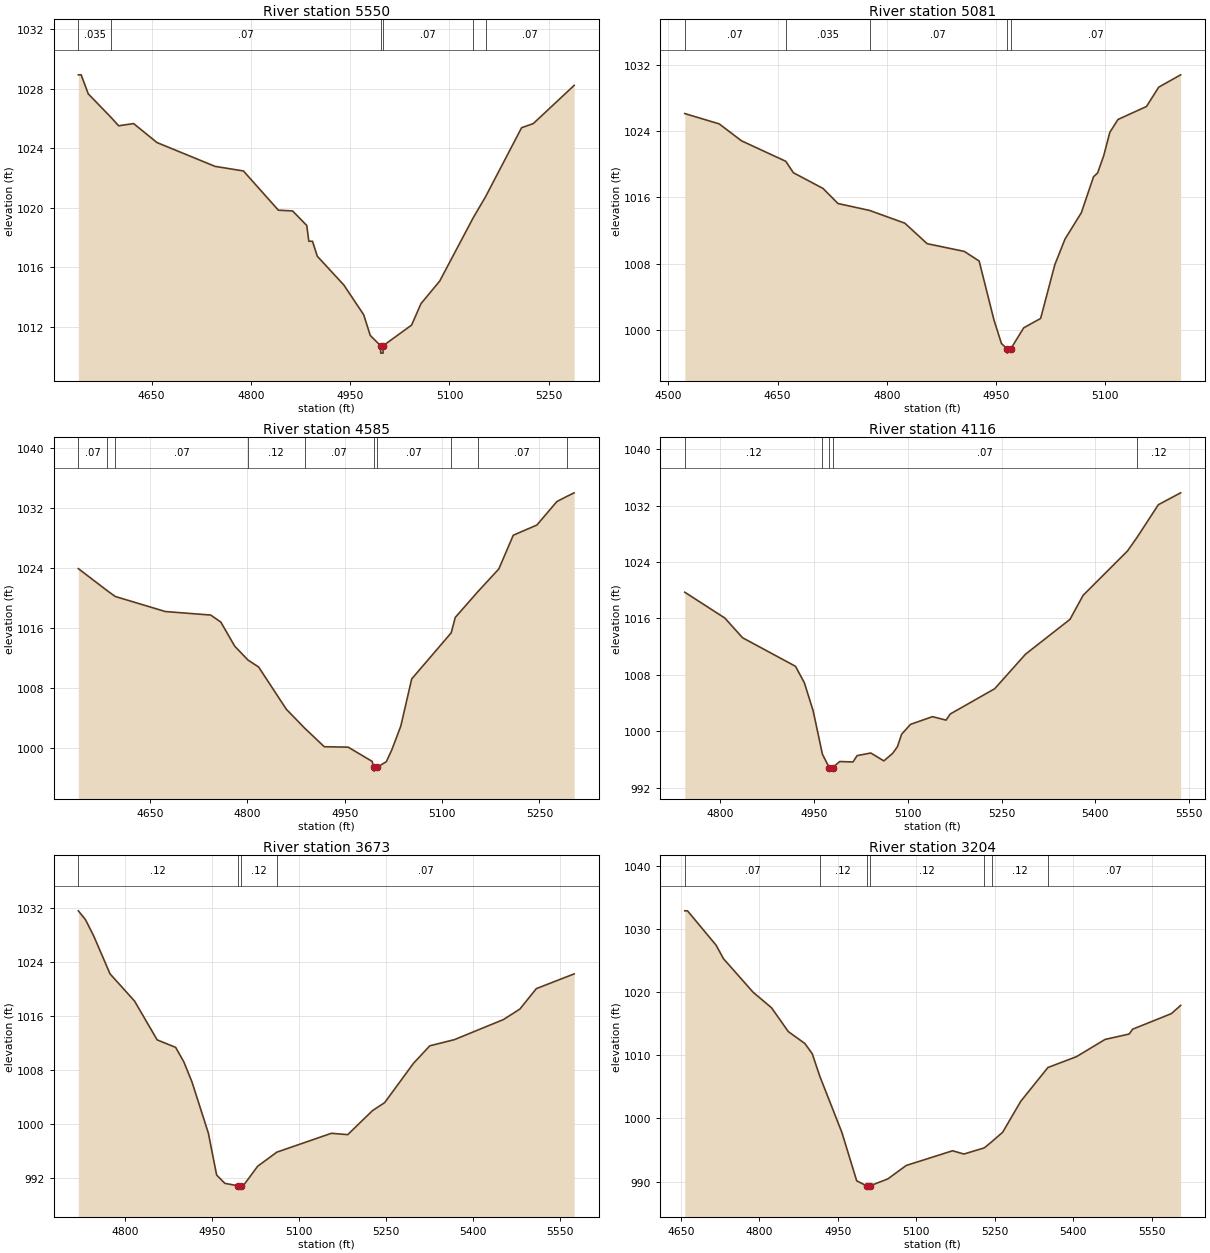
Type RM Length L Ch R = 1,5550,469,469,469
BEGIN DESCRIPTION:
Upper Dry Comal Tributary 18 12.0
END DESCRIPTION:
XS GIS Cut Line= 5
      2193995.07     13819887.51      2194173.18     13819584.72
      2194175.00     13819475.00      2194025.00     13819325.00
      2193971.37     13819271.37
#Sta/Elev= 30
  4539.4 1028.94  4543.7 1028.94  4554.4 1027.66  4588.3 1026.10  4600.3 1025.51
  4622.9 1025.66  4658.3 1024.38  4745.9 1022.78  4788.8 1022.47  4841.6 1019.83
  4863.0 1019.78  4884.5 1018.80  4887.6 1017.74  4893.1 1017.74  4900.4 1016.73
  4940.4 1014.80  4970.4 1012.80  4980.4 1011.40  4995.9 1010.71  4996.2 1010.21
  4999.7 1010.21  4999.9 1010.71  5042.9 1012.10  5057.0 1013.54  5085.3 1015.06
  5135.9 1019.32  5154.5 1020.73  5209.0 1025.38  5226.7 1025.66  5288.4 1028.23
#Mann=6,-1,0
  4539.4   0.035       0  4588.3    0.07       0  4995.9    0.05       0
  4999.9    0.07       0  5135.9   0.035       0  5154.5    0.07       0
Bank Sta=4995.9,4999.9
Exp/Cntr=0.3,0.1

Type RM Length L Ch R = 1,5081,496,496,496
BEGIN DESCRIPTION:
Upper Dry Comal Tributary 18 11.0
END DESCRIPTION:
XS GIS Cut Line= 5
      2194570.25     13819651.24      2194525.00     13819425.00
      2194475.00     13819175.00      2194425.00     13819075.00
      2194387.78     13819000.56
#Sta/Elev= 30
  4522.6 1026.11  4569.8 1024.87  4600.4 1022.83  4661.2 1020.36  4671.7 1018.98
  4712.5 1017.08  4732.9 1015.27  4776.2 1014.44  4824.7 1012.90  4855.3 1010.43
  4906.3 1009.50  4926.7 1008.34  4947.1 1001.22  4957.3  998.41  4965.0  997.74
  4965.3  997.24  4970.0  997.74  4987.9 1000.29  5011.1 1001.42  5030.6 1007.90
  5044.6 1010.99  5067.0 1014.16  5083.7 1018.49  5089.3 1018.95  5097.7 1021.03
  5106.1 1023.85  5117.3 1025.40  5156.4 1026.96  5173.2 1029.29  5203.3 1030.78
#Mann=5,-1,0
  4522.6    0.07       0  4661.2   0.035       0  4776.2    0.07       0
  4965.0    0.05       0  4970.0    0.07       0
Bank Sta=4965,4970
Exp/Cntr=0.3,0.1

Type RM Length L Ch R = 1,4585,469,469,469
BEGIN DESCRIPTION:
Upper Dry Comal Tributary 18 10.0
END DESCRIPTION:
XS GIS Cut Line= 5
      2195161.92     13819469.87      2195075.00     13819325.00
      2194925.00     13819075.00      2194875.00     13818975.00
      2194789.31     13818803.62
#Sta/Elev= 30
  4539.5 1023.95  4584.4 1020.98  4596.4 1020.23  4673.5 1018.22  4743.4 1017.75
  4759.0 1016.82  4780.4 1013.60  4800.8 1011.75  4817.3 1010.81  4860.0 1005.17
  4888.1 1002.66  4918.4 1000.17  4955.3 1000.11  4992.2  998.21  4994.5  997.41
  4994.9  996.91  4999.6  997.41  5014.0  998.17  5022.3  999.72  5036.3 1002.92
  5053.1 1009.22  5114.0 1015.38  5120.2 1017.43  5154.6 1020.83  5187.3 1023.90
  5209.6 1028.41  5246.0 1029.77  5276.7 1032.90  5292.3 1033.60  5303.4 1034.07
#Mann=10,-1,0
  4539.5    0.07       0  4584.4    0.12       0  4596.4    0.07       0
  4800.8    0.12       0  4888.1    0.07       0  4994.5    0.05       0
  4999.6    0.07       0  5114.0    0.12       0  5154.6    0.07       0
  5292.3    0.12       0
Bank Sta=4994.5,4999.6
Exp/Cntr=0.3,0.1

Type RM Length L Ch R = 1,4116,443,443,443
BEGIN DESCRIPTION:
Upper Dry Comal Tributary 18 9.0
END DESCRIPTION:
XS GIS Cut Line= 4
      2195560.32     13819210.32      2195475.00     13819125.00
      2195375.00     13819025.00      2194974.99     13818675.00
#Sta/Elev= 30
  4743.0 1019.72  4807.1 1016.06  4835.4 1013.27  4920.2 1009.22  4934.4 1006.88
  4948.5 1002.89  4963.3  996.75  4974.2  994.86  4974.6  994.36  4979.5  994.86
  4990.9  995.72  5012.2  995.66  5018.8  996.56  5040.7  996.93  5061.6  995.81
  5075.8  996.89  5083.4  997.84  5090.0  999.59  5104.3 1000.99  5139.4 1002.08
  5161.2 1001.59  5167.9 1002.46  5239.0 1006.04  5288.4 1010.94  5359.6 1015.88
  5380.5 1019.28  5451.6 1025.57  5466.9 1027.50  5501.0 1032.13  5536.6 1033.81
#Mann=5,-1,0
  4743.0    0.12       0  4963.3    0.07       0  4974.2    0.05       0
  4979.5    0.07       0  5466.9    0.12       0
Bank Sta=4974.2,4979.5
Exp/Cntr=0.3,0.1

Type RM Length L Ch R = 1,3673,469,469,469
BEGIN DESCRIPTION:
Upper Dry Comal Tributary 18 8.0
END DESCRIPTION:
XS GIS Cut Line= 5
      2195923.69     13818973.69      2195825.00     13818875.00
      2195725.00     13818775.00      2195475.00     13818525.00
      2195318.83     13818368.83
#Sta/Elev= 30
  4718.8 1031.59  4731.1 1030.29  4745.2 1027.90  4773.5 1022.27  4815.9 1018.23
  4854.8 1012.50  4886.7 1011.39  4900.8 1009.25  4914.9 1006.27  4943.2  998.68
  4957.4  992.51  4971.5  991.28  4993.6  990.92  4994.0  990.42  4998.5  990.42
  4998.9  990.92  5003.3  990.92  5028.1  993.80  5061.3  995.89  5155.4  998.68
  5183.6  998.48  5226.1 1002.02  5247.3 1003.22  5296.8 1009.01  5325.1 1011.62
  5367.5 1012.53  5452.3 1015.51  5480.6 1017.06  5508.9 1020.08  5574.2 1022.26
#Mann=4,-1,0
  4718.8    0.12       0  4993.6    0.05       0  4998.9    0.12       0
  5061.3    0.07       0
Bank Sta=4993.6,4998.9
Exp/Cntr=0.3,0.1

Type RM Length L Ch R = 1,3204,568,568,568
BEGIN DESCRIPTION:
Upper Dry Comal Tributary 18 7.0
END DESCRIPTION:
XS GIS Cut Line= 5
      2196317.33     13818717.33      2196175.00     13818575.00
      2196075.00     13818475.00      2195725.00     13818275.00
      2195549.63     13818174.79
#Sta/Elev= 30
  4657.3 1032.90  4662.5 1032.90  4717.2 1027.45  4731.3 1025.31  4787.9 1020.00
  4823.2 1017.53  4855.1 1013.77  4886.9 1011.87  4901.0 1010.24  4915.5 1006.66
  4957.6  997.78  4985.9  990.12  5005.2  989.30  5005.6  988.80  5010.6  989.30
  5045.4  990.42  5080.6  992.55  5169.2  994.88  5190.8  994.36  5229.9  995.34
  5244.2  996.32  5264.9  997.81  5299.5 1002.72  5351.4 1008.07  5406.0 1009.79
  5460.7 1012.52  5506.8 1013.38  5513.3 1014.14  5587.4 1016.61  5605.1 1017.91
#Mann=7,-1,0
  4657.3    0.07       0  4915.5    0.12       0  5005.2    0.05       0
  5010.6    0.12       0  5229.9    0.07       0  5244.2    0.12       0
  5351.4    0.07       0
Bank Sta=5005.2,5010.6
Exp/Cntr=0.3,0.1

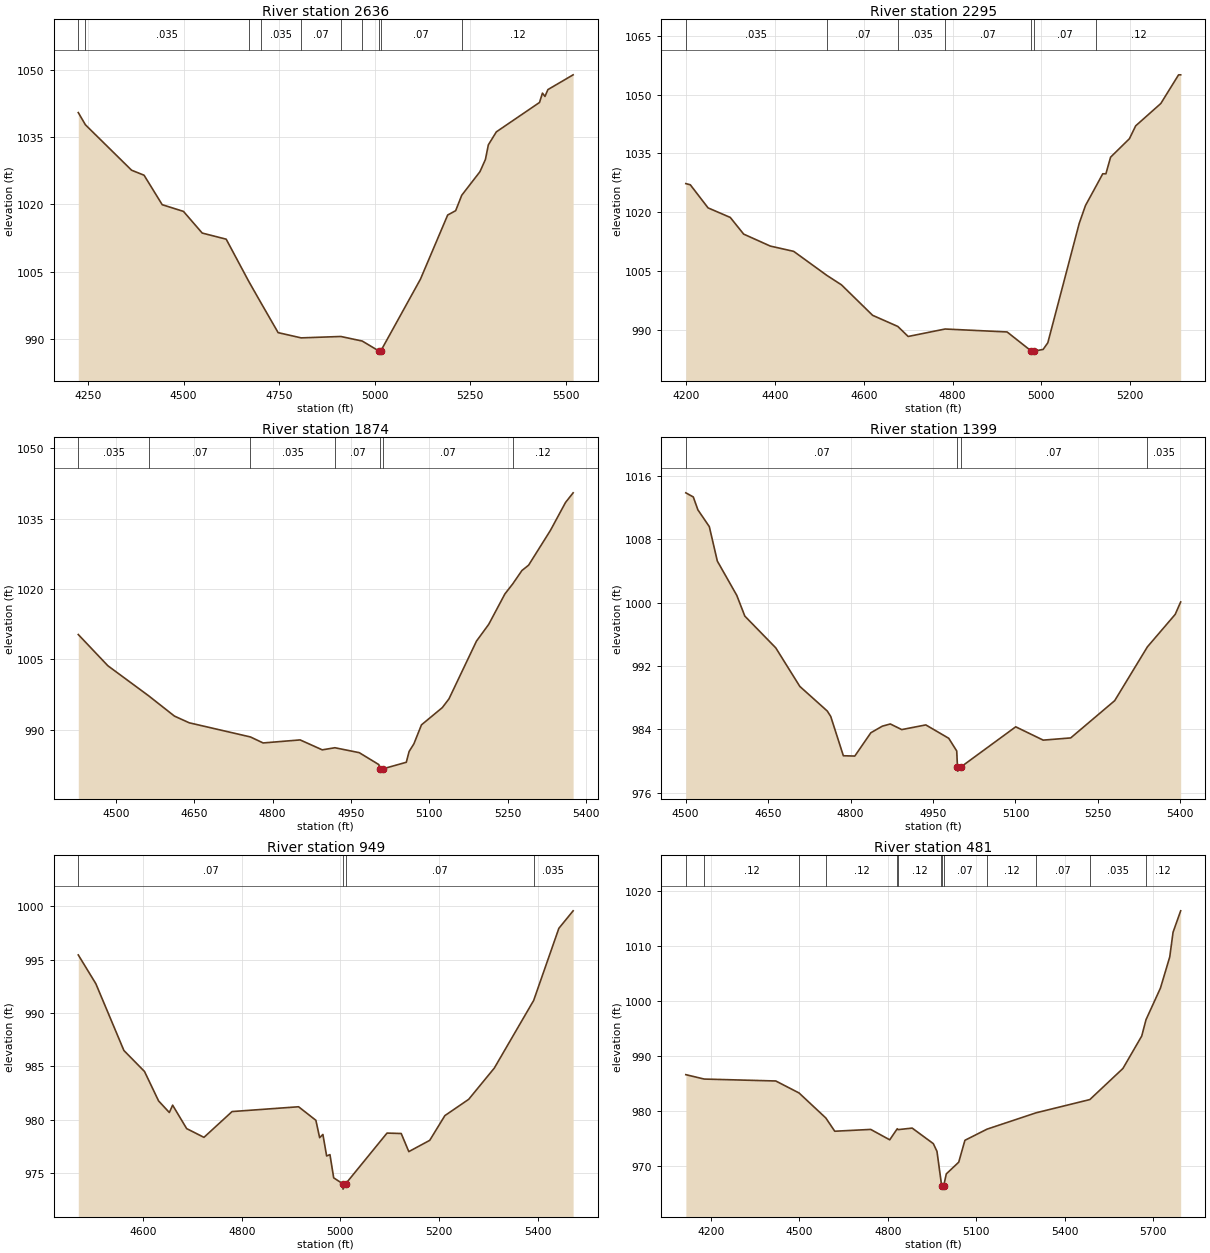
Type RM Length L Ch R = 1,2636,341,341,341
BEGIN DESCRIPTION:
Upper Dry Comal Tributary 18 6.0
END DESCRIPTION:
XS GIS Cut Line= 3
      2196490.64     13818734.94      2196273.61     13818031.77
      2195909.49     13817606.97
#Sta/Elev= 30
  4224.4 1040.53  4243.1 1037.80  4363.9 1027.65  4396.6 1026.53  4444.1 1019.94
  4499.8 1018.44  4548.8 1013.60  4611.6 1012.23  4671.3 1002.70  4703.8  997.83
  4747.6  991.34  4807.8  990.17  4911.7  990.48  4967.7  989.46  5010.9  987.26
  5011.3  986.76  5016.4  987.26  5120.1 1003.29  5191.4 1017.63  5212.3 1018.60
  5228.2 1022.05  5275.9 1027.32  5290.2 1030.05  5297.9 1033.32  5318.8 1036.22
  5431.8 1042.79  5439.5 1044.88  5446.1 1044.14  5453.8 1045.67  5519.8 1048.97
#Mann=10,-1,0
  4224.4    0.07       0  4243.1   0.035       0  4671.3    0.12       0
  4703.8   0.035       0  4807.8    0.07       0  4911.7   0.035       0
  4967.7    0.07       0  5010.9    0.05       0  5016.4    0.07       0
  5228.2    0.12       0
Bank Sta=5010.9,5016.4
Exp/Cntr=0.3,0.1

Type RM Length L Ch R = 1,2295,421,421,421
BEGIN DESCRIPTION:
Upper Dry Comal Tributary 18 5.0
END DESCRIPTION:
XS GIS Cut Line= 4
      2196525.00     13818575.04      2196475.00     13817775.00
      2196375.00     13817675.00      2196253.32     13817553.32
#Sta/Elev= 30
  4198.7 1027.32  4208.8 1027.02  4248.8 1021.14  4298.9 1018.70  4329.0 1014.46
  4389.1 1011.41  4441.7 1010.07  4516.6 1003.94  4549.4 1001.54  4619.6  993.78
  4676.5  990.94  4699.7  988.39  4783.0  990.29  4922.7  989.54  4977.5  984.65
  4977.9  984.15  4983.0  984.65  5003.8  985.09  5014.4  986.78  5085.2 1017.20
  5099.3 1021.74  5124.0 1026.85  5138.2 1029.82  5145.3 1029.82  5155.9 1034.05
  5198.3 1038.75  5212.4 1042.03  5269.0 1047.71  5309.1 1055.02  5313.8 1055.02
#Mann=7,-1,0
  4198.7   0.035       0  4516.6    0.07       0  4676.5   0.035       0
  4783.0    0.07       0  4977.5    0.05       0  4983.0    0.07       0
  5124.0    0.12       0
Bank Sta=4977.5,4983
Exp/Cntr=0.3,0.1

Type RM Length L Ch R = 1,1874,475,475,475
BEGIN DESCRIPTION:
Upper Dry Comal Tributary 18 4.0
END DESCRIPTION:
XS GIS Cut Line= 3
      2197225.03     13817975.03      2196825.00     13817575.00
      2196475.01     13817425.00
#Sta/Elev= 30
  4428.4 1010.26  4485.0 1003.60  4563.0  997.19  4612.3  992.86  4640.6  991.43
  4757.7  988.41  4782.0  987.13  4852.7  987.78  4895.1  985.66  4919.2  986.11
  4965.8  985.06  5003.2  982.52  5005.8  981.62  5006.2  981.12  5011.5  981.62
  5055.8  983.01  5061.2  985.32  5070.3  986.93  5084.8  990.99  5124.7  994.67
  5137.4  996.53  5190.0 1008.85  5213.5 1012.44  5244.4 1018.92  5259.4 1021.07
  5277.0 1023.92  5289.7 1025.05  5331.4 1032.46  5360.4 1038.44  5374.9 1040.49
#Mann=7,-1,0
  4428.4   0.035       0  4563.0    0.07       0  4757.7   0.035       0
  4919.2    0.07       0  5005.8    0.05       0  5011.5    0.07       0
  5259.4    0.12       0
Bank Sta=5005.8,5011.5
Exp/Cntr=0.3,0.1

Type RM Length L Ch R = 1,1399,450,450,450
BEGIN DESCRIPTION:
Upper Dry Comal Tributary 18 3.0
END DESCRIPTION:
XS GIS Cut Line= 3
      2197525.03     13817525.02      2197125.00     13817225.00
      2196725.03     13817225.00
#Sta/Elev= 30
  4500.5 1013.84  4514.1 1013.32  4522.4 1011.70  4543.2 1009.58  4557.8 1005.23
  4593.2 1000.90  4607.8  998.29  4664.1  994.28  4707.8  989.42  4757.8  986.31
  4764.1  985.62  4787.0  980.67  4807.8  980.63  4837.0  983.57  4857.8  984.40
  4872.4  984.68  4893.2  983.97  4937.0  984.56  4978.7  982.87  4993.2  981.27
  4994.6  979.23  4995.0  978.73  5000.3  979.23  5100.5  984.32  5150.5  982.64
  5200.5  982.92  5280.5  987.62  5340.0  994.41  5390.5  998.50  5400.5 1000.07
#Mann=4,-1,0
  4500.5    0.07       0  4994.6    0.05       0  5000.3    0.07       0
  5340.0   0.035       0
Bank Sta=4994.6,5000.3
Exp/Cntr=0.3,0.1

Type RM Length L Ch R = 1,949,468,468,468
BEGIN DESCRIPTION:
Upper Dry Comal Tributary 18 2.0
END DESCRIPTION:
XS GIS Cut Line= 3
      2197525.01     13817125.01      2197125.00     13816775.00
      2196725.01     13817024.99
#Sta/Elev= 30
  4468.6  995.45  4504.2  992.75  4561.1  986.48  4602.9  984.51  4631.4  981.75
  4653.2  980.66  4659.9  981.35  4688.3  979.15  4723.4  978.33  4780.4  980.75
  4915.2  981.20  4950.3  979.93  4957.9  978.30  4964.5  978.60  4972.1  976.58
  4978.8  976.71  4986.4  974.53  5004.9  973.97  5005.4  973.47  5010.7  973.97
  5094.5  978.73  5123.3  978.69  5138.7  976.99  5181.1  978.05  5211.8  980.37
  5260.1  981.90  5312.0  984.83  5391.8  991.18  5442.9  997.95  5471.8  999.59
#Mann=4,-1,0
  4468.6    0.07       0  5004.9    0.05       0  5010.7    0.07       0
  5391.8   0.035       0
Bank Sta=5004.9,5010.7
Exp/Cntr=0.3,0.1

Type RM Length L Ch R = 1,481,328,328,328
BEGIN DESCRIPTION:
Upper Dry Comal Tributary 18 1.0
END DESCRIPTION:
XS GIS Cut Line= 3
      2197775.38     13816773.12      2197176.39     13816313.02
      2196299.80     13816599.43
#Sta/Elev= 30
  4115.3  986.60  4177.7  985.80  4420.3  985.45  4499.1  983.27  4589.9  978.72
  4620.2  976.31  4742.1  976.64  4806.5  974.75  4832.0  976.76  4835.0  976.60
  4882.6  976.88  4954.2  974.06  4966.7  972.65  4981.5  966.81  4983.1  966.28
  4983.6  965.78  4989.0  966.28  4998.3  968.55  5040.4  970.68  5061.4  974.66
  5136.4  976.69  5302.5  979.66  5484.9  982.07  5597.1  987.73  5660.8  993.63
  5675.3  996.60  5724.2 1002.34  5755.8 1008.02  5767.0 1012.51  5792.8 1016.40
#Mann=13,-1,0
  4115.3    0.07       0  4177.7    0.12       0  4499.1    0.07       0
  4589.9    0.12       0  4832.0    0.07       0  4835.0    0.12       0
  4981.5    0.07       0  4983.1    0.05       0  4989.0    0.07       0
  5136.4    0.12       0  5302.5    0.07       0  5484.9   0.035       0
  5675.3    0.12       0
Bank Sta=4983.1,4989
Exp/Cntr=0.3,0.1

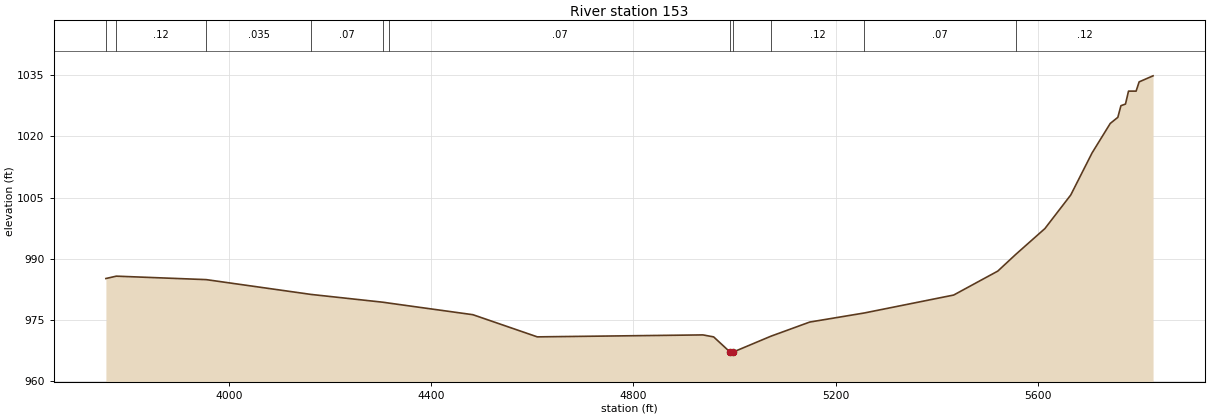
Type RM Length L Ch R = 1,153,0,0,0
BEGIN DESCRIPTION:
H21509
END DESCRIPTION:
XS GIS Cut Line= 5
      2197813.39     13816710.73      2197152.66     13816126.50
      2196902.26     13816098.67      2196693.61     13816251.69
      2196130.20     13816627.30
#Sta/Elev= 30
  3757.2  985.18  3777.8  985.76  3955.5  984.91  4162.8  981.28  4304.9  979.37
  4316.6  979.16  4482.7  976.31  4609.9  970.88  4937.3  971.36  4958.5  970.87
  4991.0  967.15  4991.5  966.65  4996.9  967.15  5071.6  971.04  5148.4  974.51
  5256.5  976.74  5432.9  981.13  5520.1  987.00  5555.5  991.08  5613.2  997.42
  5664.3 1005.65  5706.4 1015.95  5742.4 1023.19  5757.4 1024.69  5763.5 1027.54
  5772.5 1027.94  5778.5 1031.11  5793.5 1031.11  5799.5 1033.38  5827.0 1034.86
#Mann=11,-1,0
  3757.2    0.07       0  3777.8    0.12       0  3955.5   0.035       0
  4162.8    0.07       0  4304.9    0.12       0  4316.6    0.07       0
  4991.0    0.05       0  4996.9    0.07       0  5071.6    0.12       0
  5256.5    0.07       0  5555.5    0.12       0
Bank Sta=4991,4996.9
Exp/Cntr=0.3,0.1

Chan Stop Cuts=-1