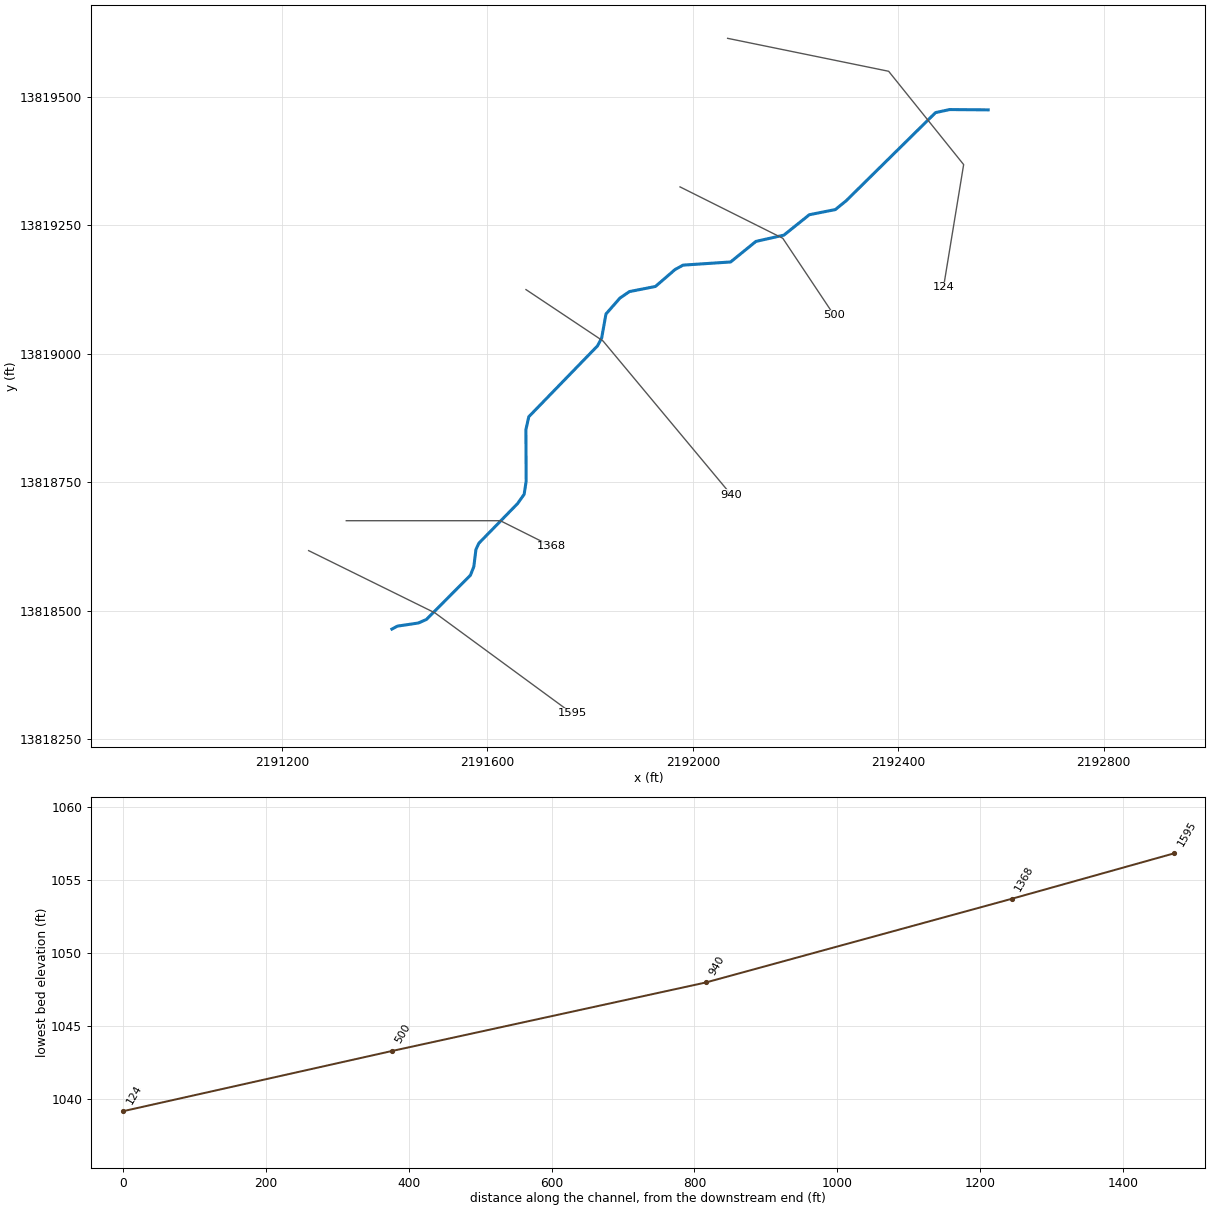
--- Upper Dry Comal Tributary 18b.prj (project) ---

Proj Title=Upper Dry Comal Tributary 18b Base Level Engineering
Current Plan=p01
Default Exp/Contr=0.3,0.1
English Units
Geom File=g01
Flow File=f01
Plan File=p01
BEGIN DESCRIPTION:
Upper Dry Comal Tributary 18b
END DESCRIPTION:

--- Upper Dry Comal Tributary 18b.p01 (plan) ---

Plan Title=Multiple Run
Short Identifier=Multiple
Geom File=g01
Flow File=f01
Subcritical Flow
K Sum by GR= 0
Std Step Tol= 0.01
Critical Tol= 0.01
Num of Std Step Trials= 20
Max Error Tol= 0.3
Flow Tol Ratio= 0.001
Split Flow NTrial= 30
Split Flow Tol= 0.02
Split Flow Ratio= 0.02
Log Output Level= 0
Friction Slope Method= 1
Unsteady Friction Slope Method= 2
Unsteady Bridges Friction Slope Method= 1
Parabolic Critical Depth
Global Vel Dist=  1 , 1 , 1
Global Log Level= 0
CheckData=True
Encroach Param= -1, 0, 0, 0
BEGIN DESCRIPTION:
Multiple Run
END DESCRIPTION:

--- Upper Dry Comal Tributary 18b.f01 (steady flow) ---

Flow Title=Multiple
Number of Profiles=7
Profile Names=10-year,25-year,50-year,1pct_min,100-year,1pct_plu,500-year
River Rch & RM= Upper Dry Comal ,Reach-1,1595
     602     981    1328     873    1743    3477    2964
Boundary for River Rch & Prof#=Upper Dry Comal ,Reach-1,1
Up Type=0
Dn Type=3
Dn Slope=0.005
Boundary for River Rch & Prof#=Upper Dry Comal ,Reach-1,2
Up Type=0
Dn Type=3
Dn Slope=0.005
Boundary for River Rch & Prof#=Upper Dry Comal ,Reach-1,3
Up Type=0
Dn Type=3
Dn Slope=0.005
Boundary for River Rch & Prof#=Upper Dry Comal ,Reach-1,4
Up Type=0
Dn Type=3
Dn Slope=0.005
Boundary for River Rch & Prof#=Upper Dry Comal ,Reach-1,5
Up Type=0
Dn Type=3
Dn Slope=0.005
Boundary for River Rch & Prof#=Upper Dry Comal ,Reach-1,6
Up Type=0
Dn Type=3
Dn Slope=0.005
Boundary for River Rch & Prof#=Upper Dry Comal ,Reach-1,7
Up Type=0
Dn Type=3
Dn Slope=0.005

--- Upper Dry Comal Tributary 18b.g01 (geometry) ---

Geom Title=Existing Conditions

River Reach=Upper Dry Comal ,Reach-1
Reach XY= 30
      2191413.99     13818463.99      2191424.56     13818469.69
      2191465.57     13818475.85      2191481.23     13818482.76
      2191566.85     13818568.93      2191573.46     13818585.63
      2191577.54     13818618.95      2191583.18     13818631.04
      2191658.54     13818708.25      2191671.45     13818726.47
      2191675.34     13818752.13      2191674.83     13818852.34
      2191680.47     13818877.45      2191814.21     13819015.34
      2191822.34     13819030.68      2191830.75     13819077.54
      2191857.95     13819108.51      2191876.42     13819121.14
      2191927.15     13819131.15      2191965.34     13819164.17
      2191980.96     13819172.67      2192073.42     13819178.83
      2192122.82     13819218.88      2192177.20     13819231.08
      2192226.74     13819270.81      2192277.30     13819280.83
      2192298.47     13819298.01      2192472.50     13819469.65
      2192499.75     13819475.59      2192575.00     13819475.00

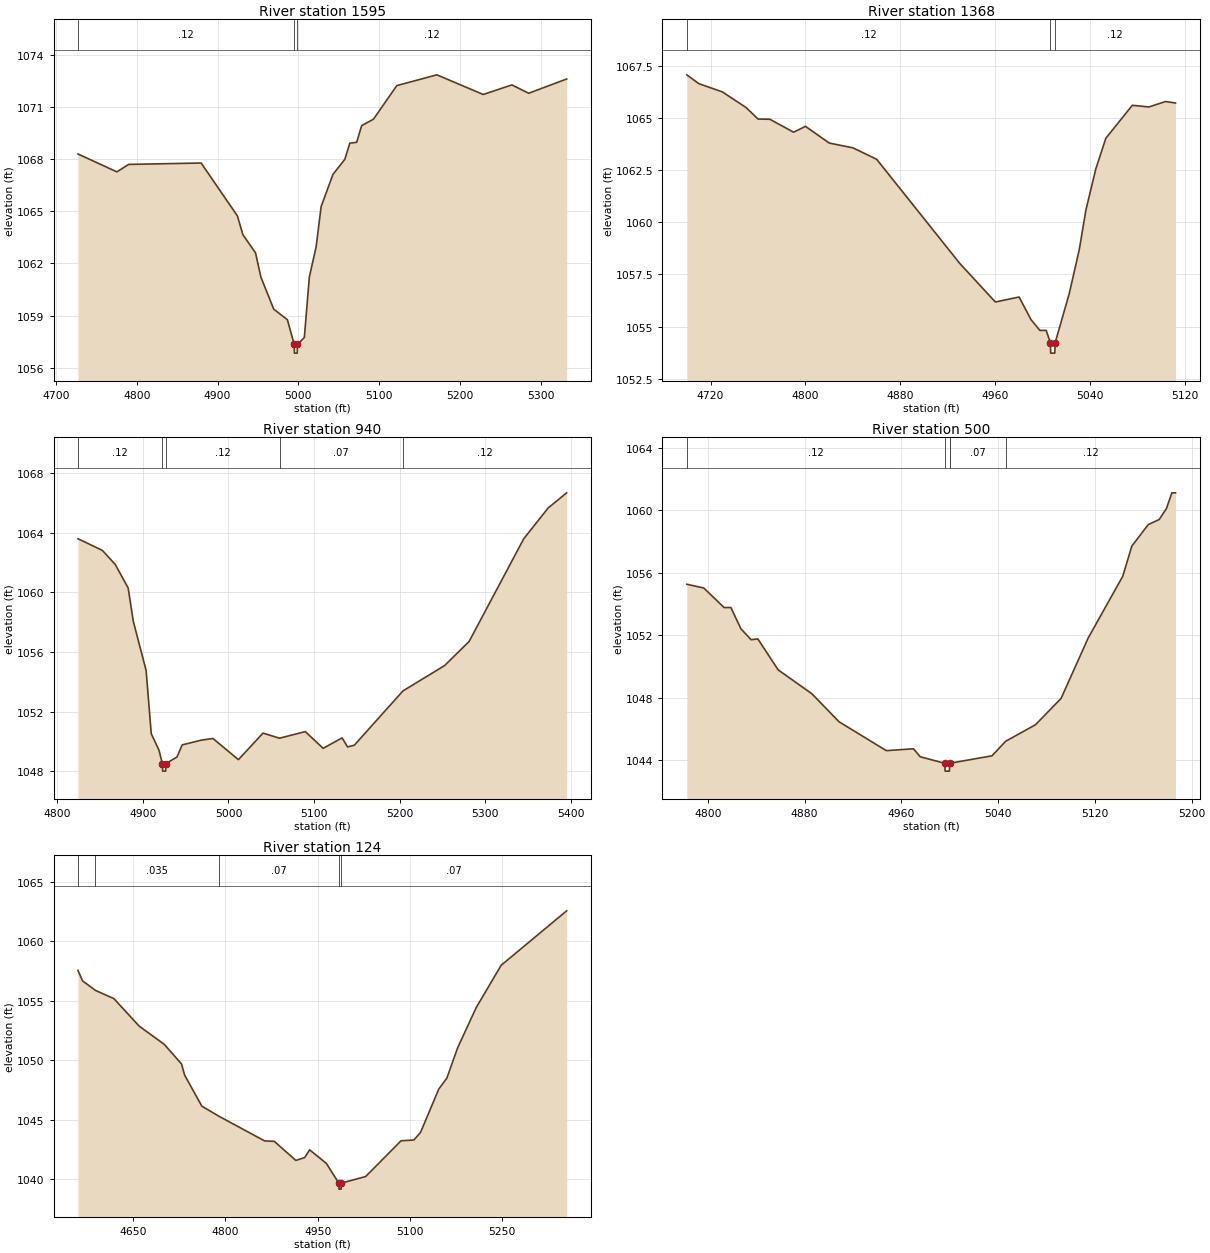
Type RM Length L Ch R = 1,1595,227,227,227
BEGIN DESCRIPTION:
XS7898
END DESCRIPTION:
XS GIS Cut Line= 3
      2191251.80     13818616.74      2191497.62     13818495.61
      2191764.59     13818299.83
#Sta/Elev= 30
  4727.1 1068.29  4775.3 1067.26  4789.8 1067.69  4879.6 1067.77  4924.5 1064.73
  4931.3 1063.65  4947.0 1062.60  4953.6 1061.21  4969.5 1059.37  4986.4 1058.76
  4994.9 1057.34  4995.1 1056.84  4998.6 1056.84  4998.9 1057.34  5007.4 1057.74
  5013.6 1061.22  5022.0 1062.95  5028.2 1065.27  5042.9 1067.12  5057.5 1067.98
  5063.7 1068.91  5072.2 1068.96  5078.4 1069.92  5093.0 1070.29  5121.9 1072.22
  5171.5 1072.84  5228.9 1071.71  5264.4 1072.26  5285.2 1071.78  5332.2 1072.60
#Mann=3,-1,0
  4727.1    0.12       0  4994.9    0.05       0  4998.9    0.12       0
Bank Sta=4994.9,4998.9
Exp/Cntr=0.3,0.1

Type RM Length L Ch R = 1,1368,428,428,428
BEGIN DESCRIPTION:
Upper Dry Comal Tributary 18b 3.0
END DESCRIPTION:
XS GIS Cut Line= 3
      2191325.03     13818675.00      2191625.00     13818675.00
      2191725.02     13818624.99
#Sta/Elev= 30
  4700.0 1067.07  4710.0 1066.65  4730.0 1066.25  4750.0 1065.50  4760.0 1064.95
  4770.0 1064.94  4790.0 1064.32  4800.0 1064.60  4820.0 1063.80  4840.0 1063.57
  4860.0 1063.02  4930.0 1058.03  4960.0 1056.18  4980.0 1056.42  4990.0 1055.34
  4997.5 1054.82  5002.8 1054.82  5006.4 1054.23  5006.6 1053.73  5010.1 1053.73
  5010.4 1054.23  5022.3 1056.59  5030.7 1058.69  5036.3 1060.59  5044.7 1062.57
  5053.1 1064.03  5075.4 1065.61  5089.4 1065.53  5103.4 1065.79  5111.8 1065.72
#Mann=3,-1,0
  4700.0    0.12       0  5006.4    0.05       0  5010.4    0.12       0
Bank Sta=5006.4,5010.4
Exp/Cntr=0.3,0.1

Type RM Length L Ch R = 1,940,440,440,440
BEGIN DESCRIPTION:
Upper Dry Comal Tributary 18b 2.0
END DESCRIPTION:
XS GIS Cut Line= 3
      2191675.00     13819125.00      2191825.00     13819025.00
      2192075.01     13818724.99
#Sta/Elev= 30
  4824.2 1063.59  4852.7 1062.81  4867.8 1061.86  4882.8 1060.29  4888.8 1058.06
  4903.8 1054.75  4909.8 1050.51  4918.8 1049.41  4922.8 1048.50  4923.1 1048.00
  4926.6 1048.00  4926.8 1048.50  4939.9 1048.95  4945.9 1049.76  4968.4 1050.08
  4981.9 1050.19  5011.6 1048.77  5040.3 1050.55  5059.6 1050.21  5089.7 1050.65
  5110.6 1049.53  5132.7 1050.23  5139.2 1049.62  5147.0 1049.74  5203.8 1053.38
  5252.4 1055.08  5281.1 1056.70  5344.9 1063.59  5373.5 1065.66  5395.0 1066.67
#Mann=5,-1,0
  4824.2    0.12       0  4922.8    0.05       0  4926.8    0.12       0
  5059.6    0.07       0  5203.8    0.12       0
Bank Sta=4922.8,4926.8
Exp/Cntr=0.3,0.1

Type RM Length L Ch R = 1,500,376,376,376
BEGIN DESCRIPTION:
Upper Dry Comal Tributary 18b 1.0
END DESCRIPTION:
XS GIS Cut Line= 3
      2191974.98     13819325.01      2192175.00     13819225.00
      2192275.00     13819075.00
#Sta/Elev= 30
  4782.7 1055.26  4796.7 1055.02  4813.5 1053.77  4819.1 1053.77  4827.4 1052.41
  4835.8 1051.71  4841.4 1051.76  4858.2 1049.78  4886.1 1048.25  4908.5 1046.46
  4947.6 1044.61  4970.0 1044.73  4975.6 1044.22  4995.9 1043.80  4996.2 1043.30
  4999.7 1043.30  4999.9 1043.80  5000.5 1043.81  5034.9 1044.28  5046.2 1045.21
  5070.9 1046.27  5092.0 1047.95  5114.5 1051.83  5143.0 1055.77  5150.5 1057.70
  5164.1 1059.08  5173.1 1059.40  5179.1 1060.10  5183.6 1061.11  5186.6 1061.11
#Mann=5,-1,0
  4782.7    0.12       0  4995.9    0.05       0  4999.9    0.12       0
  5000.5    0.07       0  5046.2    0.12       0
Bank Sta=4995.9,4999.9
Exp/Cntr=0.3,0.1

Type RM Length L Ch R = 1,124,0,0,0
BEGIN DESCRIPTION:
XS7897
END DESCRIPTION:
XS GIS Cut Line= 4
      2192067.65     13819614.29      2192381.16     13819550.16
      2192527.23     13819368.46      2192488.06     13819129.89
#Sta/Elev= 30
  4560.1 1057.54  4567.6 1056.66  4588.6 1055.86  4618.6 1055.17  4659.5 1052.87
  4700.3 1051.34  4728.5 1049.69  4733.6 1048.75  4761.5 1046.15  4790.0 1045.28
  4863.6 1043.23  4879.5 1043.19  4914.5 1041.59  4928.9 1041.83  4936.9 1042.48
  4964.1 1041.34  4984.5 1039.68  4984.7 1039.18  4988.2 1039.18  4988.5 1039.68
  5028.1 1040.24  5085.7 1043.24  5106.5 1043.30  5117.5 1043.96  5147.1 1047.59
  5160.1 1048.49  5177.5 1051.02  5207.9 1054.42  5248.5 1057.97  5355.0 1062.54
#Mann=5,-1,0
  4560.1    0.07       0  4588.6   0.035       0  4790.0    0.07       0
  4984.5    0.05       0  4988.5    0.07       0
Bank Sta=4984.5,4988.5
Exp/Cntr=0.3,0.1

Chan Stop Cuts=-1