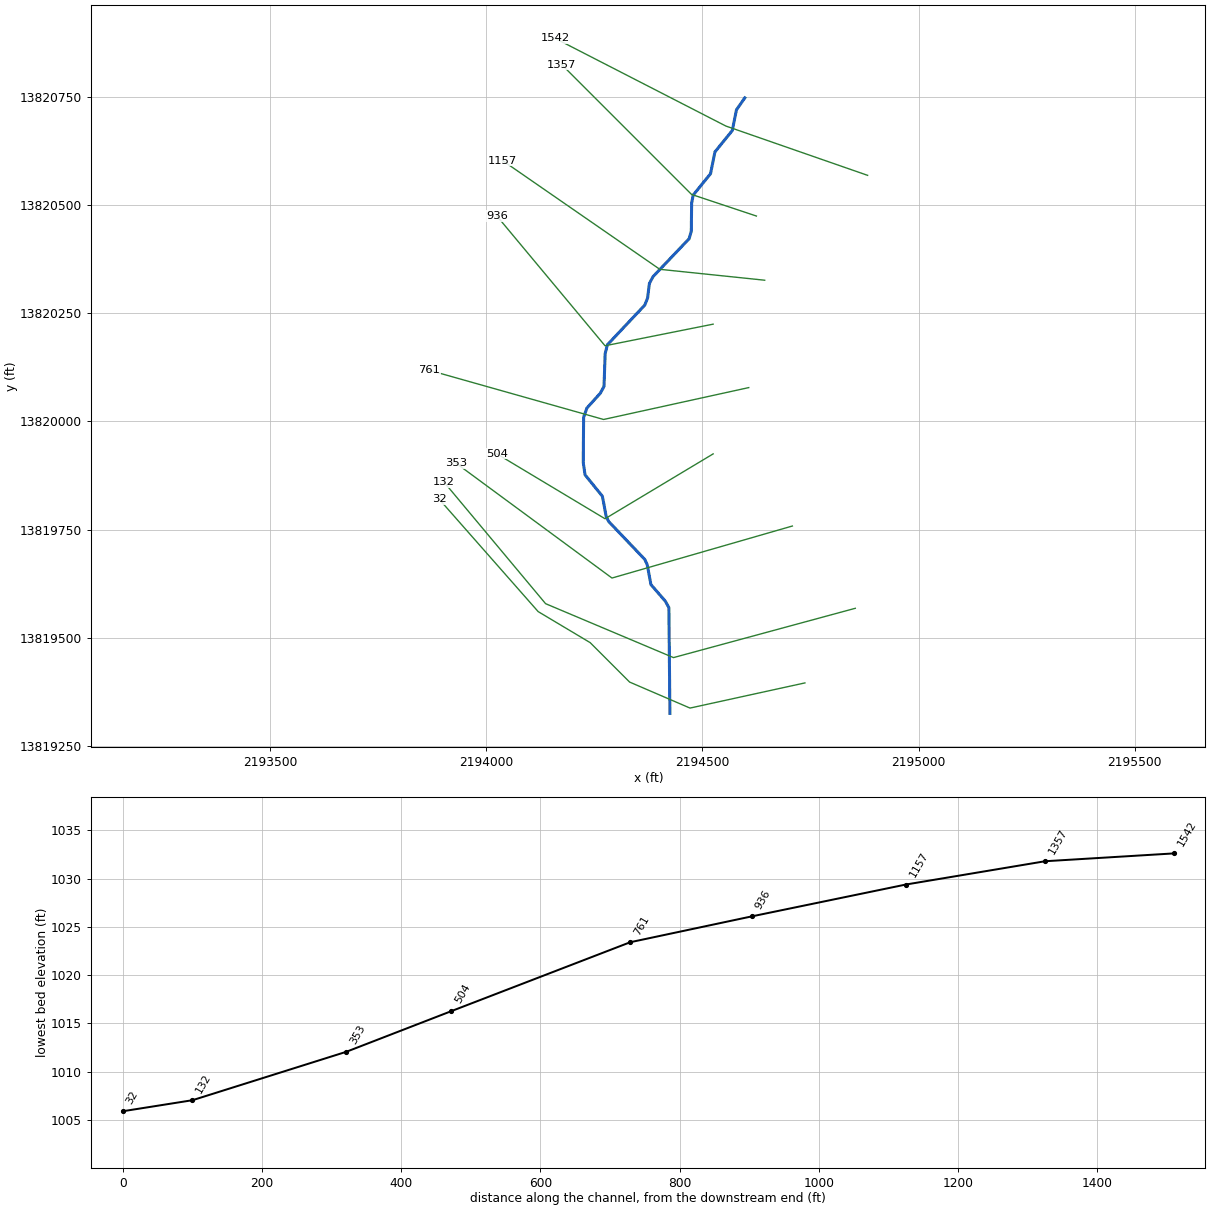
--- Upper Dry Comal Tributary 19.prj (project) ---

Proj Title=Upper Dry Comal Tributary 19 Base Level Engineering
Current Plan=p01
Default Exp/Contr=0.3,0.1
English Units
Geom File=g01
Flow File=f01
Plan File=p01
BEGIN DESCRIPTION:
Upper Dry Comal Tributary 19
END DESCRIPTION:

--- Upper Dry Comal Tributary 19.p01 (plan) ---

Plan Title=Multiple Run
Short Identifier=Multiple
Geom File=g01
Flow File=f01
Subcritical Flow
K Sum by GR= 0
Std Step Tol= 0.01
Critical Tol= 0.01
Num of Std Step Trials= 20
Max Error Tol= 0.3
Flow Tol Ratio= 0.001
Split Flow NTrial= 30
Split Flow Tol= 0.02
Split Flow Ratio= 0.02
Log Output Level= 0
Friction Slope Method= 1
Unsteady Friction Slope Method= 2
Unsteady Bridges Friction Slope Method= 1
Parabolic Critical Depth
Global Vel Dist=  1 , 1 , 1
Global Log Level= 0
CheckData=True
Encroach Param= -1, 0, 0, 0
BEGIN DESCRIPTION:
Multiple Run
END DESCRIPTION:

--- Upper Dry Comal Tributary 19.f01 (steady flow) ---

Flow Title=Multiple
Number of Profiles=7
Profile Names=10-year,25-year,50-year,1pct_min,100-year,1pct_plu,500-year
River Rch & RM= Upper Dry Comal ,Reach-1,1542
     717    1185    1621    1077    2148    4286    3725
Boundary for River Rch & Prof#=Upper Dry Comal ,Reach-1,1
Up Type=0
Dn Type=3
Dn Slope=0.005
Boundary for River Rch & Prof#=Upper Dry Comal ,Reach-1,2
Up Type=0
Dn Type=3
Dn Slope=0.005
Boundary for River Rch & Prof#=Upper Dry Comal ,Reach-1,3
Up Type=0
Dn Type=3
Dn Slope=0.005
Boundary for River Rch & Prof#=Upper Dry Comal ,Reach-1,4
Up Type=0
Dn Type=3
Dn Slope=0.005
Boundary for River Rch & Prof#=Upper Dry Comal ,Reach-1,5
Up Type=0
Dn Type=3
Dn Slope=0.005
Boundary for River Rch & Prof#=Upper Dry Comal ,Reach-1,6
Up Type=0
Dn Type=3
Dn Slope=0.005
Boundary for River Rch & Prof#=Upper Dry Comal ,Reach-1,7
Up Type=0
Dn Type=3
Dn Slope=0.005

--- Upper Dry Comal Tributary 19.g01 (geometry) ---

Geom Title=Existing Conditions

River Reach=Upper Dry Comal ,Reach-1
Reach XY= 30
      2194598.18     13820748.18      2194578.90     13820720.64
      2194569.21     13820672.68      2194529.13     13820623.29
      2194518.89     13820572.82      2194478.83     13820523.41
      2194475.24     13820504.90      2194474.47     13820440.22
      2194469.46     13820422.58      2194385.80     13820334.67
      2194377.54     13820318.95      2194373.45     13820285.64
      2194366.82     13820268.96      2194280.54     13820177.42
      2194275.25     13820156.71      2194272.64     13820080.98
      2194264.10     13820065.37      2194233.13     13820031.06
      2194225.50     13820009.78      2194224.60     13819904.86
      2194228.74     13819876.56      2194268.86     13819827.17
      2194277.50     13819781.04      2194283.16     13819768.95
      2194366.84     13819681.05      2194372.50     13819668.96
      2194381.14     13819622.83      2194414.21     13819584.67
      2194422.65     13819569.48      2194425.00     13819325.00

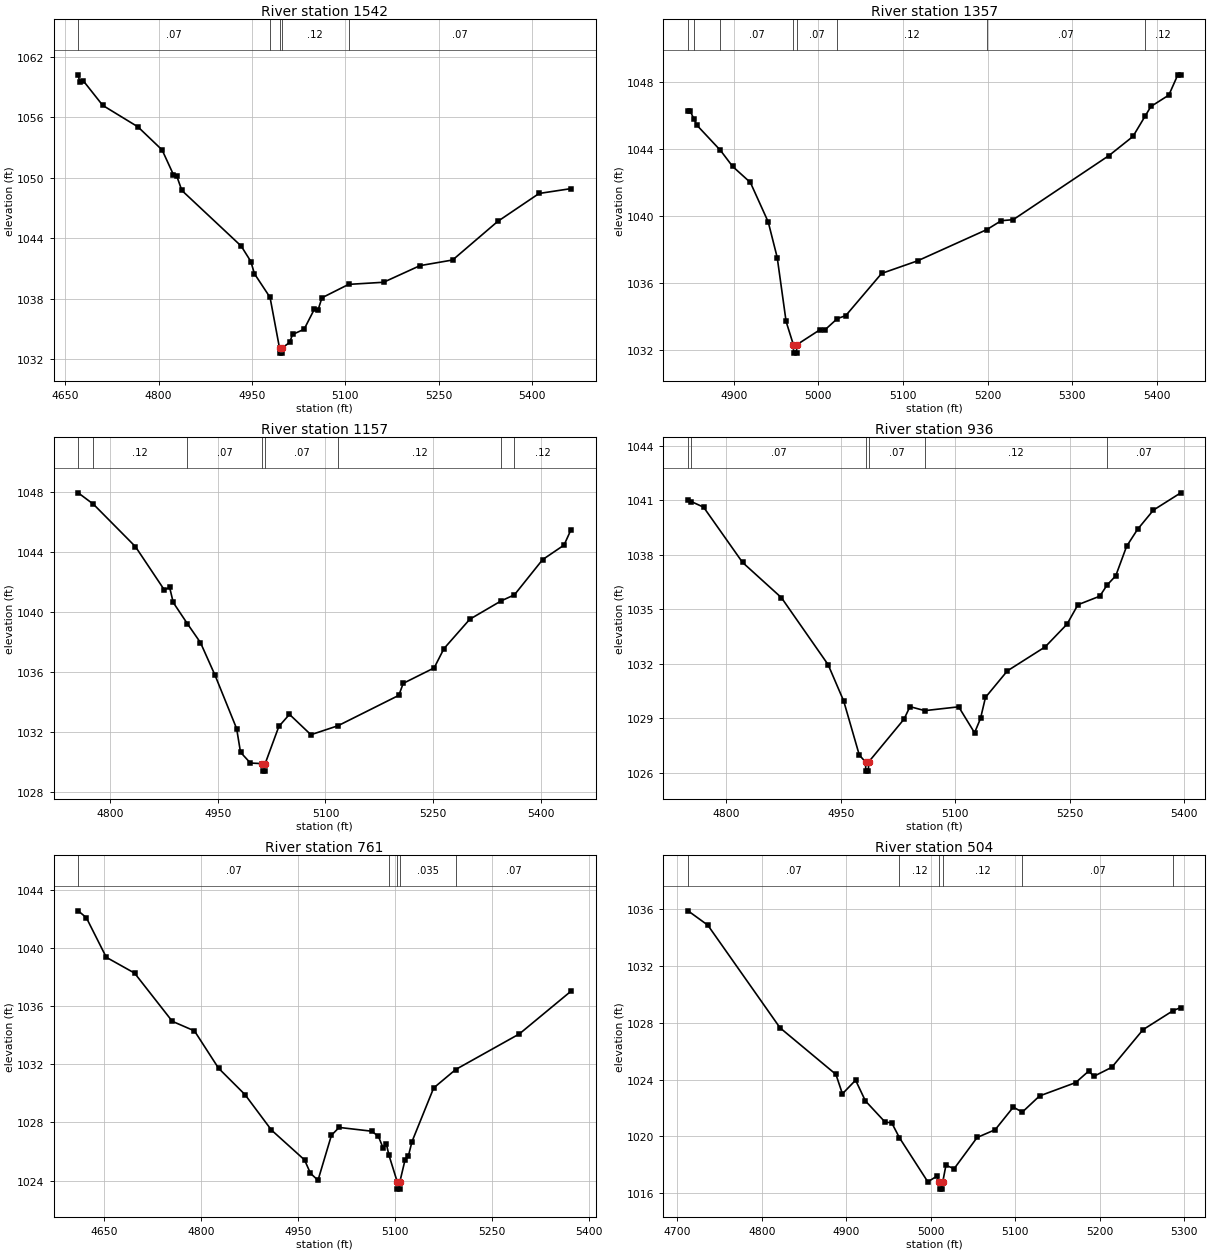
Type RM Length L Ch R = 1,1542,185,185,185
BEGIN DESCRIPTION:
XS7899
END DESCRIPTION:
XS GIS Cut Line= 3
      2194882.18     13820569.08      2194554.39     13820683.09
      2194159.47     13820885.89
#Sta/Elev= 30
  4671.0 1060.21  4673.6 1059.45  4678.9 1059.64  4710.4 1057.18  4766.9 1055.05
  4805.7 1052.76  4823.8 1050.32  4829.1 1050.19  4837.4 1048.74  4932.7 1043.22
  4948.2 1041.69  4953.9 1040.48  4979.0 1038.13  4994.2 1033.10  4994.5 1032.60
  4998.0 1032.60  4998.2 1033.10  5010.4 1033.66  5015.1 1034.45  5033.7 1034.97
  5050.3 1036.98  5055.9 1036.85  5062.3 1038.09  5105.1 1039.42  5161.2 1039.63
  5219.7 1041.28  5272.1 1041.84  5344.3 1045.66  5410.9 1048.44  5462.0 1048.92
#Mann=5,-1,0
  4671.0    0.07       0  4979.0    0.12       0  4994.2    0.05       0
  4998.2    0.12       0  5105.1    0.07       0
Bank Sta=4994.2,4998.2
Exp/Cntr=0.3,0.1

Type RM Length L Ch R = 1,1357,200,200,200
BEGIN DESCRIPTION:
Upper Dry Comal Tributary 19 3.0
END DESCRIPTION:
XS GIS Cut Line= 3
      2194624.96     13820475.01      2194475.00     13820525.00
      2194175.03     13820824.97
#Sta/Elev= 30
  4846.1 1046.24  4848.7 1046.24  4852.8 1045.80  4856.6 1045.40  4884.4 1043.90
  4898.8 1042.94  4919.8 1041.98  4940.9 1039.62  4951.5 1037.50  4962.0 1033.68
  4970.6 1032.29  4970.8 1031.79  4974.3 1031.79  4974.6 1032.29  5001.5 1033.17
  5007.7 1033.17  5022.5 1033.85  5032.5 1034.03  5074.9 1036.55  5117.3 1037.30
  5199.3 1039.17  5216.3 1039.70  5230.4 1039.76  5343.6 1043.59  5371.9 1044.73
  5386.7 1045.98  5393.1 1046.52  5414.3 1047.20  5424.9 1048.41  5428.4 1048.41
#Mann=8,-1,0
  4846.1    0.07       0  4852.8    0.12       0  4884.4    0.07       0
  4970.6    0.05       0  4974.6    0.07       0  5022.5    0.12       0
  5199.3    0.07       0  5386.7    0.12       0
Bank Sta=4970.6,4974.6
Exp/Cntr=0.3,0.1

Type RM Length L Ch R = 1,1157,221,221,221
BEGIN DESCRIPTION:
H21514
END DESCRIPTION:
XS GIS Cut Line= 3
      2194644.17     13820326.60      2194401.64     13820351.82
      2194038.45     13820602.96
#Sta/Elev= 30
  4756.0 1047.96  4777.2 1047.20  4835.6 1044.37  4875.8 1041.48  4883.2 1041.65
  4888.2 1040.64  4907.8 1039.23  4926.1 1037.96  4946.2 1035.80  4976.4 1032.22
  4981.8 1030.64  4995.6 1029.92  5012.1 1029.88  5012.4 1029.38  5015.9 1029.38
  5016.1 1029.88  5035.1 1032.36  5049.9 1033.17  5079.7 1031.81  5117.4 1032.41
  5202.0 1034.44  5208.1 1035.24  5251.1 1036.27  5264.8 1037.56  5300.7 1039.52
  5344.5 1040.75  5362.8 1041.15  5402.0 1043.50  5431.8 1044.47  5441.4 1045.49
#Mann=8,-1,0
  4756.0    0.07       0  4777.2    0.12       0  4907.8    0.07       0
  5012.1    0.05       0  5016.1    0.07       0  5117.4    0.12       0
  5344.5    0.07       0  5362.8    0.12       0
Bank Sta=5012.1,5016.1
Exp/Cntr=0.3,0.1

Type RM Length L Ch R = 1,936,175,175,175
BEGIN DESCRIPTION:
Upper Dry Comal Tributary 19 2.0
END DESCRIPTION:
XS GIS Cut Line= 3
      2194524.97     13820224.99      2194275.00     13820175.00
      2194025.02     13820474.97
#Sta/Elev= 30
  4750.0 1040.99  4754.2 1040.93  4770.4 1040.62  4821.4 1037.58  4872.3 1035.64
  4933.5 1031.95  4953.9 1029.95  4974.3 1026.98  4982.5 1026.59  4982.8 1026.09
  4986.3 1026.09  4986.5 1026.59  5032.9 1028.95  5040.7 1029.64  5060.1 1029.42
  5104.5 1029.63  5125.3 1028.20  5133.1 1028.99  5139.6 1030.15  5168.3 1031.61
  5217.8 1032.93  5246.4 1034.18  5260.7 1035.25  5289.3 1035.72  5299.0 1036.34
  5310.2 1036.84  5324.5 1038.47  5338.8 1039.40  5359.6 1040.46  5395.4 1041.41
#Mann=6,-1,0
  4750.0    0.12       0  4754.2    0.07       0  4982.5    0.05       0
  4986.5    0.07       0  5060.1    0.12       0  5299.0    0.07       0
Bank Sta=4982.5,4986.5
Exp/Cntr=0.3,0.1

Type RM Length L Ch R = 1,761,257,257,257
BEGIN DESCRIPTION:
H21513
END DESCRIPTION:
XS GIS Cut Line= 3
      2194607.28     13820078.30      2194271.66     13820004.58
      2193868.15     13820118.49
#Sta/Elev= 30
  4609.8 1042.58  4622.4 1042.11  4653.3 1039.38  4697.1 1038.29  4755.5 1034.97
  4789.8 1034.31  4827.1 1031.74  4868.1 1029.92  4909.0 1027.48  4960.3 1025.42
  4969.4 1024.50  4981.1 1024.02  5001.9 1027.12  5013.8 1027.66  5064.2 1027.40
  5074.6 1027.05  5081.8 1026.25  5087.0 1026.50  5091.0 1025.74  5103.8 1023.91
  5104.1 1023.41  5107.6 1023.41  5107.8 1023.91  5115.8 1025.41  5121.0 1025.69
  5126.6 1026.68  5160.2 1030.38  5194.3 1031.65  5292.8 1034.10  5372.7 1037.04
#Mann=5,-1,0
  4609.8    0.07       0  5091.0   0.035       0  5103.8    0.05       0
  5107.8   0.035       0  5194.3    0.07       0
Bank Sta=5103.8,5107.8
Exp/Cntr=0.3,0.1

Type RM Length L Ch R = 1,504,151,151,151
BEGIN DESCRIPTION:
Upper Dry Comal Tributary 19 1.0
END DESCRIPTION:
XS GIS Cut Line= 3
      2194525.02     13819925.01      2194275.00     13819775.00
      2194025.02     13819924.99
#Sta/Elev= 30
  4712.8 1035.90  4736.2 1034.89  4821.7 1027.65  4887.8 1024.37  4895.5 1023.00
  4911.1 1023.96  4922.7 1022.50  4946.1 1021.00  4953.8 1020.96  4963.0 1019.90
  4996.6 1016.79  5007.3 1017.20  5010.2 1016.78  5010.4 1016.28  5013.9 1016.28
  5014.2 1016.78  5018.0 1017.96  5027.7 1017.72  5054.9 1019.92  5076.3 1020.47
  5097.7 1022.06  5108.4 1021.71  5128.8 1022.85  5171.5 1023.79  5187.1 1024.61
  5192.9 1024.23  5214.3 1024.87  5251.2 1027.52  5287.0 1028.87  5295.9 1029.08
#Mann=6,-1,0
  4712.8    0.07       0  4963.0    0.12       0  5010.2    0.05       0
  5014.2    0.12       0  5108.4    0.07       0  5287.0   0.035       0
Bank Sta=5010.2,5014.2
Exp/Cntr=0.3,0.1

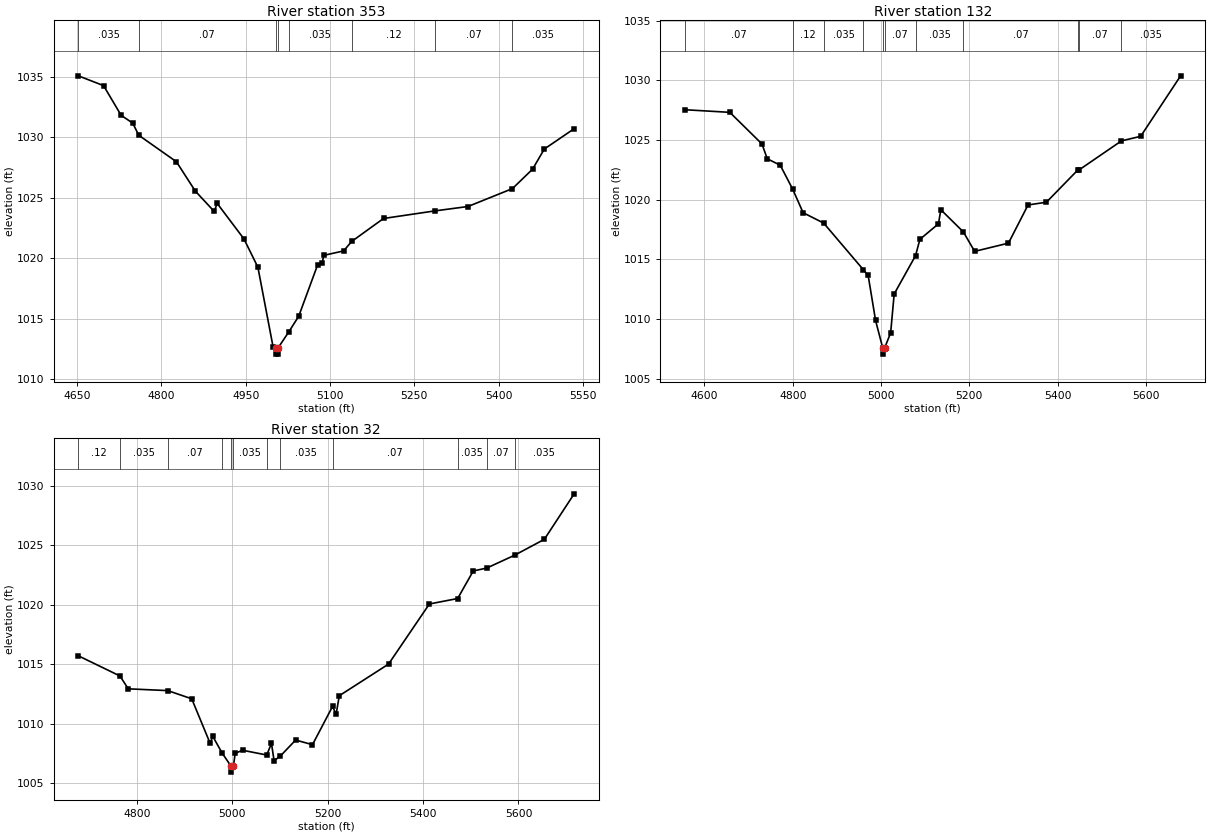
Type RM Length L Ch R = 1,353,221,221,221
BEGIN DESCRIPTION:
H21515
END DESCRIPTION:
XS GIS Cut Line= 3
      2194708.15     13819758.22      2194291.06     13819637.94
      2193930.25     13819903.70
#Sta/Elev= 30
  4652.1 1035.07  4697.0 1034.26  4728.2 1031.81  4748.9 1031.16  4759.6 1030.16
  4826.6 1027.97  4860.3 1025.54  4893.9 1023.86  4899.1 1024.53  4946.8 1021.59
  4971.6 1019.25  4998.8 1012.62  5003.3 1012.57  5003.5 1012.07  5007.0 1012.07
  5007.3 1012.57  5027.0 1013.94  5044.2 1015.20  5077.8 1019.44  5086.2 1019.61
  5088.6 1020.23  5124.1 1020.60  5138.4 1021.38  5195.1 1023.28  5287.0 1023.91
  5345.4 1024.27  5424.5 1025.75  5460.4 1027.36  5481.2 1029.02  5534.3 1030.70
#Mann=8,-1,0
  4652.1   0.035       0  4759.6    0.07       0  5003.3    0.05       0
  5007.3    0.07       0  5027.0   0.035       0  5138.4    0.12       0
  5287.0    0.07       0  5424.5   0.035       0
Bank Sta=5003.3,5007.3
Exp/Cntr=0.3,0.1

Type RM Length L Ch R = 1,132,100,100,100
BEGIN DESCRIPTION:
XS7900
END DESCRIPTION:
XS GIS Cut Line= 4
      2194853.66     13819567.98      2194433.26     13819453.97
      2194137.55     13819578.66      2193902.46     13819860.07
#Sta/Elev= 30
  4555.5 1027.54  4657.5 1027.32  4730.3 1024.67  4742.3 1023.43  4771.7 1022.89
  4800.2 1020.86  4823.5 1018.91  4870.1 1018.04  4959.8 1014.14  4970.9 1013.65
  4987.6 1009.89  5004.0 1007.56  5004.3 1007.06  5008.0 1007.56  5021.8 1008.84
  5029.8 1012.10  5078.2 1015.31  5088.1 1016.68  5130.1 1017.98  5135.5 1019.16
  5186.5 1017.30  5212.1 1015.67  5288.7 1016.36  5333.1 1019.56  5374.7 1019.79
  5446.1 1022.50  5448.8 1022.50  5544.7 1024.93  5588.2 1025.31  5678.7 1030.38
#Mann=11,-1,0
  4555.5    0.07       0  4800.2    0.12       0  4870.1   0.035       0
  4959.8    0.07       0  5004.0    0.05       0  5008.0    0.07       0
  5078.2   0.035       0  5186.5    0.07       0  5446.1   0.035       0
  5448.8    0.07       0  5544.7   0.035       0
Bank Sta=5004,5008
Exp/Cntr=0.3,0.1

Type RM Length L Ch R = 1,32,0,0,0
BEGIN DESCRIPTION:
H21512
END DESCRIPTION:
XS GIS Cut Line= 6
      2194737.19     13819395.44      2194471.47     13819337.26
      2194331.80     13819397.39      2194240.63     13819488.57
      2194120.35     13819560.34      2193891.55     13819820.17
#Sta/Elev= 30
  4677.4 1015.71  4764.7 1014.01  4782.0 1012.93  4864.9 1012.78  4915.1 1012.09
  4953.7 1008.34  4959.1 1008.94  4978.7 1007.53  4997.5 1006.42  4997.9 1005.92
  5002.5 1006.42  5006.2 1007.51  5021.8 1007.76  5072.3 1007.36  5082.2 1008.34
  5087.7 1006.89  5100.3 1007.25  5132.9 1008.62  5168.2 1008.23  5210.3 1011.45
  5217.7 1010.78  5224.4 1012.35  5327.6 1015.01  5413.2 1020.07  5472.5 1020.53
  5505.2 1022.85  5533.3 1023.09  5591.7 1024.17  5654.2 1025.51  5716.7 1029.34
#Mann=12,-1,0
  4677.4    0.12       0  4764.7   0.035       0  4864.9    0.07       0
  4978.7   0.035       0  4997.5   0.035       0  5002.5   0.035       0
  5072.3    0.07       0  5100.3   0.035       0  5210.3    0.07       0
  5472.5   0.035       0  5533.3    0.07       0  5591.7   0.035       0
Bank Sta=4997.5,5002.5
Exp/Cntr=0.3,0.1

Chan Stop Cuts=-1