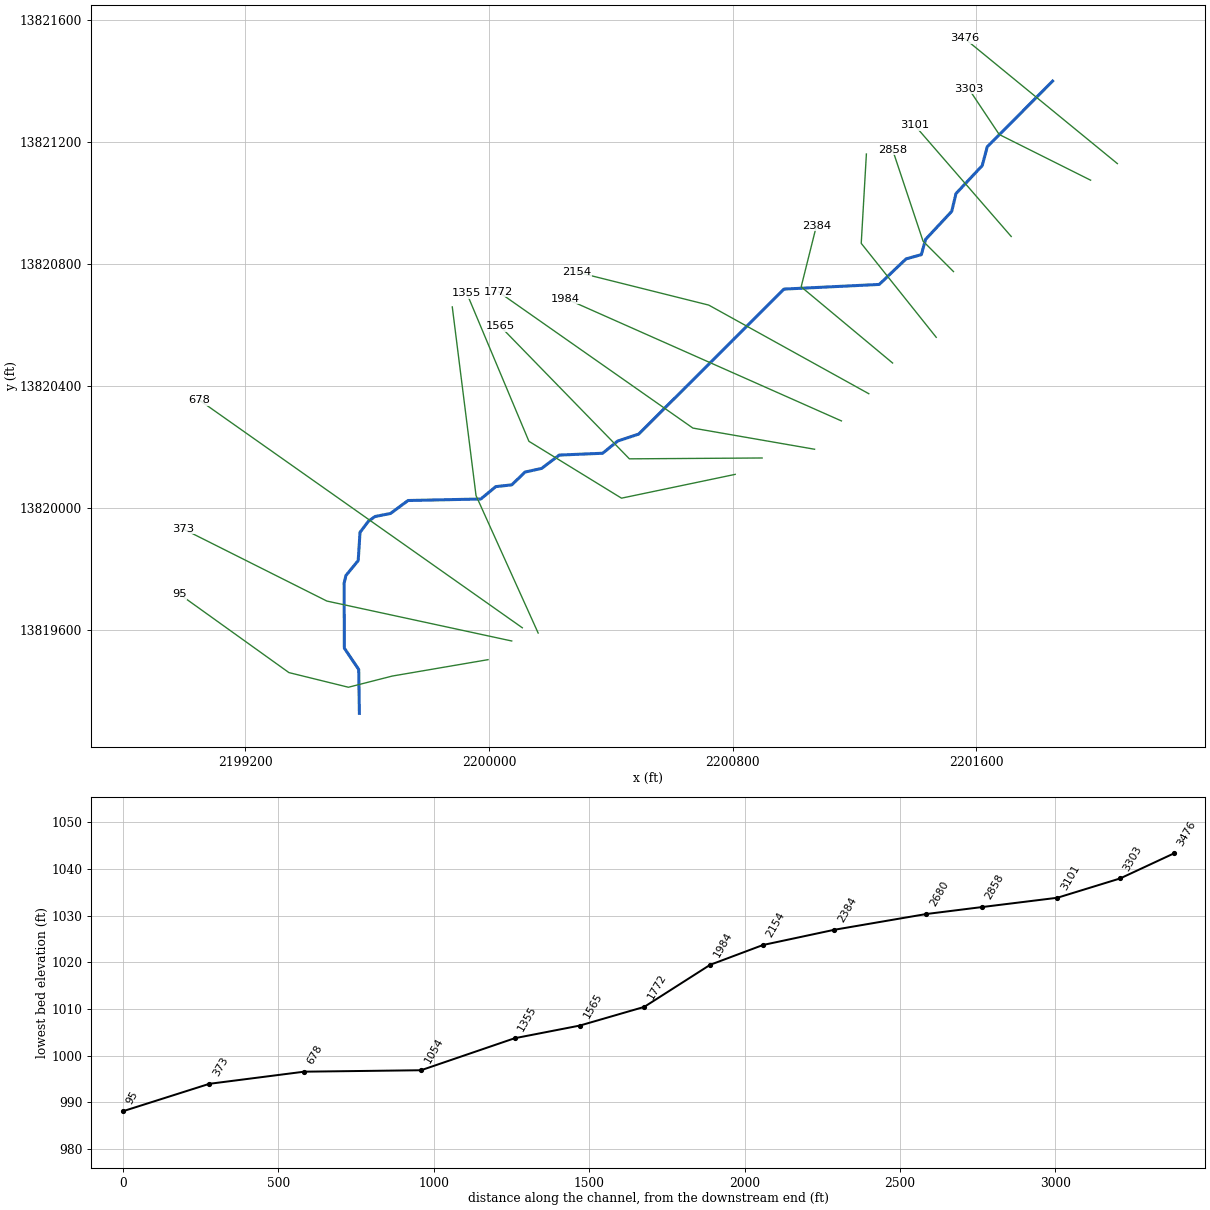
--- Upper Dry Comal Tributary 20.prj (project) ---

Proj Title=Upper Dry Comal Tributary 20 Base Level Engineering
Current Plan=p01
Default Exp/Contr=0.3,0.1
English Units
Geom File=g01
Flow File=f01
Plan File=p01
BEGIN DESCRIPTION:
Upper Dry Comal Tributary 20
END DESCRIPTION:

--- Upper Dry Comal Tributary 20.p01 (plan) ---

Plan Title=Multiple Run
Short Identifier=Multiple
Geom File=g01
Flow File=f01
Subcritical Flow
K Sum by GR= 0
Std Step Tol= 0.01
Critical Tol= 0.01
Num of Std Step Trials= 20
Max Error Tol= 0.3
Flow Tol Ratio= 0.001
Split Flow NTrial= 30
Split Flow Tol= 0.02
Split Flow Ratio= 0.02
Log Output Level= 0
Friction Slope Method= 1
Unsteady Friction Slope Method= 2
Unsteady Bridges Friction Slope Method= 1
Parabolic Critical Depth
Global Vel Dist=  1 , 1 , 1
Global Log Level= 0
CheckData=True
Encroach Param= -1, 0, 0, 0
BEGIN DESCRIPTION:
Multiple Run
END DESCRIPTION:

--- Upper Dry Comal Tributary 20.f01 (steady flow) ---

Flow Title=Multiple
Number of Profiles=7
Profile Names=10-year,25-year,50-year,1pct_min,100-year,1pct_plu,500-year
River Rch & RM= Upper Dry Comal ,Reach-1,3476
     346     545     722     466     929    1854    1517
River Rch & RM= Upper Dry Comal ,Reach-1,2154
     623    1022    1391     920    1835    3662    3155
River Rch & RM= Upper Dry Comal ,Reach-1,1054
     944    1589    2199    1476    2945    5877    5223
Boundary for River Rch & Prof#=Upper Dry Comal ,Reach-1,1
Up Type=0
Dn Type=3
Dn Slope=0.005
Boundary for River Rch & Prof#=Upper Dry Comal ,Reach-1,2
Up Type=0
Dn Type=3
Dn Slope=0.005
Boundary for River Rch & Prof#=Upper Dry Comal ,Reach-1,3
Up Type=0
Dn Type=3
Dn Slope=0.005
Boundary for River Rch & Prof#=Upper Dry Comal ,Reach-1,4
Up Type=0
Dn Type=3
Dn Slope=0.005
Boundary for River Rch & Prof#=Upper Dry Comal ,Reach-1,5
Up Type=0
Dn Type=3
Dn Slope=0.005
Boundary for River Rch & Prof#=Upper Dry Comal ,Reach-1,6
Up Type=0
Dn Type=3
Dn Slope=0.005
Boundary for River Rch & Prof#=Upper Dry Comal ,Reach-1,7
Up Type=0
Dn Type=3
Dn Slope=0.005

--- Upper Dry Comal Tributary 20.g01 (geometry) ---

Geom Title=Existing Conditions

River Reach=Upper Dry Comal ,Reach-1
Reach XY= 30
      2201850.38     13821400.38      2201635.78     13821184.68
      2201619.13     13821122.72      2201533.18     13821031.04
      2201519.13     13820972.72      2201433.30     13820880.74
      2201419.38     13820830.62      2201369.26     13820816.70
      2201281.19     13820732.83      2200968.65     13820717.57
      2200491.68     13820241.64      2200422.83     13820218.86
      2200373.44     13820178.76      2200230.93     13820172.76
      2200173.31     13820129.08      2200118.85     13820117.09
      2200075.00     13820075.00      2200022.66     13820069.26
      2199973.51     13820028.60      2199734.65     13820023.64
      2199677.14     13819981.15      2199626.39     13819971.16
      2199604.43     13819955.42      2199577.07     13819919.29
      2199571.14     13819826.60      2199530.74     13819777.34
      2199524.90     13819752.31      2199525.68     13819538.92
      2199572.78     13819469.08      2199575.00     13819325.00

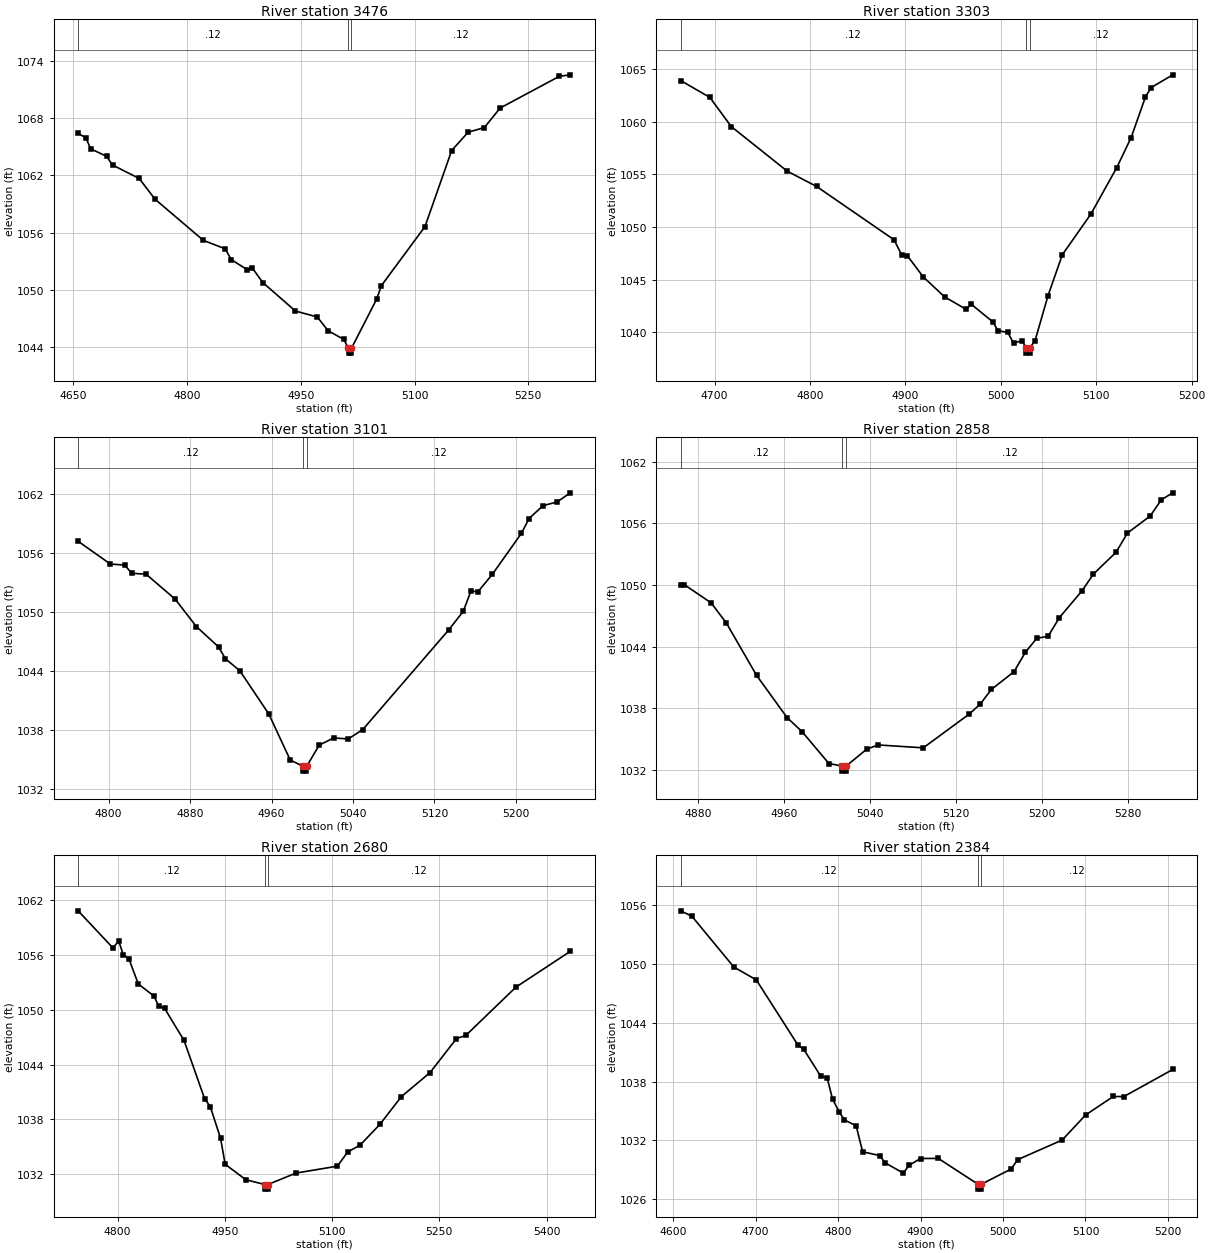
Type RM Length L Ch R = 1,3476,173,173,173
BEGIN DESCRIPTION:
XS7910
END DESCRIPTION:
XS GIS Cut Line= 2
      2202062.82     13821129.45      2201560.80     13821540.59
#Sta/Elev= 30
  4656.5 1066.39  4666.6 1065.94  4673.1 1064.77  4693.9 1064.00  4701.8 1063.08
  4737.0 1061.67  4757.8 1059.50  4821.7 1055.18  4850.4 1054.30  4858.3 1053.17
  4879.1 1052.13  4886.3 1052.27  4899.9 1050.77  4943.0 1047.78  4971.7 1047.16
  4986.1 1045.72  5006.9 1044.80  5012.8 1043.87  5013.0 1043.37  5016.5 1043.37
  5016.8 1043.87  5049.9 1049.00  5056.4 1050.45  5113.8 1056.63  5149.0 1064.60
  5170.7 1066.52  5192.0 1067.00  5212.9 1069.05  5291.1 1072.38  5305.4 1072.53
#Mann=3,-1,0
  4656.5    0.12       0  5012.8    0.05       0  5016.8    0.12       0
Bank Sta=5012.8,5016.8
Exp/Cntr=0.3,0.1

Type RM Length L Ch R = 1,3303,202,202,202
BEGIN DESCRIPTION:
Upper Dry Comal Tributary 20 7.0
END DESCRIPTION:
XS GIS Cut Line= 3
      2201974.97     13821075.01      2201675.00     13821225.00
      2201574.98     13821375.03
#Sta/Elev= 30
  4664.4 1063.94  4695.1 1062.33  4717.5 1059.56  4776.2 1055.31  4806.9 1053.86
  4888.0 1048.79  4896.4 1047.30  4902.0 1047.27  4918.7 1045.25  4941.1 1043.35
  4963.4 1042.18  4969.0 1042.65  4991.4 1040.99  4997.0 1040.14  5007.3 1039.97
  5013.3 1038.94  5022.3 1039.20  5026.3 1038.50  5026.6 1038.00  5030.1 1038.00
  5030.3 1038.50  5035.8 1039.18  5049.4 1043.46  5064.4 1047.36  5094.4 1051.24
  5121.5 1055.66  5136.5 1058.51  5151.5 1062.37  5157.5 1063.27  5180.1 1064.48
#Mann=3,-1,0
  4664.4    0.12       0  5026.3    0.05       0  5030.3    0.12       0
Bank Sta=5026.3,5030.3
Exp/Cntr=0.3,0.1

Type RM Length L Ch R = 1,3101,243,243,243
BEGIN DESCRIPTION:
H21520
END DESCRIPTION:
XS GIS Cut Line= 2
      2201714.35     13820890.29      2201397.49     13821255.24
#Sta/Elev= 30
  4770.1 1057.20  4801.7 1054.89  4816.0 1054.78  4822.6 1053.95  4836.8 1053.86
  4865.3 1051.33  4886.2 1048.54  4908.1 1046.46  4914.7 1045.27  4928.9 1044.05
  4957.4 1039.65  4978.3 1035.00  4990.6 1034.36  4990.8 1033.86  4994.3 1033.86
  4994.6 1034.36  5006.8 1036.50  5021.1 1037.23  5035.3 1037.13  5049.6 1038.08
  5134.0 1048.20  5148.3 1050.09  5155.9 1052.17  5162.5 1052.05  5176.8 1053.84
  5205.3 1057.99  5212.9 1059.51  5226.6 1060.82  5240.4 1061.19  5253.4 1062.12
#Mann=3,-1,0
  4770.1    0.12       0  4990.6    0.05       0  4994.6    0.12       0
Bank Sta=4990.6,4994.6
Exp/Cntr=0.3,0.1

Type RM Length L Ch R = 1,2858,178,178,178
BEGIN DESCRIPTION:
Upper Dry Comal Tributary 20 6.0
END DESCRIPTION:
XS GIS Cut Line= 3
      2201524.99     13820775.01      2201425.00     13820875.00
      2201325.01     13821174.96
#Sta/Elev= 30
  4863.7 1050.02  4867.2 1050.02  4892.0 1048.26  4906.1 1046.32  4934.4 1041.18
  4962.7 1037.08  4976.8 1035.69  5001.6 1032.60  5013.7 1032.36  5013.9 1031.86
  5017.4 1031.86  5017.7 1032.36  5036.7 1033.99  5047.3 1034.41  5089.4 1034.13
  5131.6 1037.38  5142.1 1038.36  5152.7 1039.82  5173.8 1041.55  5184.3 1043.44
  5194.9 1044.80  5205.4 1044.99  5215.9 1046.81  5237.0 1049.43  5247.6 1051.06
  5268.6 1053.18  5279.2 1055.05  5300.3 1056.71  5310.8 1058.30  5321.3 1058.97
#Mann=3,-1,0
  4863.7    0.12       0  5013.7    0.05       0  5017.7    0.12       0
Bank Sta=5013.7,5017.7
Exp/Cntr=0.3,0.1

Type RM Length L Ch R = 1,2680,296,296,296
BEGIN DESCRIPTION:
H21519
END DESCRIPTION:
XS GIS Cut Line= 3
      2201468.26     13820559.28      2201222.13     13820867.65
      2201239.05     13821160.91
#Sta/Elev= 30
  4744.9 1060.81  4793.6 1056.75  4801.6 1057.51  4808.0 1056.02  4816.0 1055.54
  4829.0 1052.81  4851.2 1051.48  4857.6 1050.36  4865.7 1050.15  4893.0 1046.64
  4921.7 1040.28  4929.7 1039.40  4944.1 1035.93  4950.5 1033.10  4979.3 1031.41
  5006.1 1030.88  5006.4 1030.38  5009.9 1030.38  5010.1 1030.88  5049.8 1032.14
  5107.4 1032.89  5121.8 1034.43  5139.4 1035.21  5166.8 1037.45  5196.9 1040.49
  5237.0 1043.12  5274.0 1046.84  5287.0 1047.18  5357.2 1052.47  5433.2 1056.38
#Mann=3,-1,0
  4744.9    0.12       0  5006.1    0.05       0  5010.1    0.12       0
Bank Sta=5006.1,5010.1
Exp/Cntr=0.3,0.1

Type RM Length L Ch R = 1,2384,230,230,230
BEGIN DESCRIPTION:
Upper Dry Comal Tributary 20 5.0
END DESCRIPTION:
XS GIS Cut Line= 3
      2201325.04     13820474.97      2201025.00     13820725.00
      2201075.00     13820924.98
#Sta/Elev= 30
  4609.1 1055.45  4622.8 1054.90  4673.6 1049.71  4700.9 1048.39  4751.7 1041.69
  4758.2 1041.32  4779.0 1038.55  4786.8 1038.37  4793.3 1036.22  4801.2 1034.92
  4807.7 1034.08  4822.0 1033.47  4829.8 1030.82  4850.6 1030.43  4857.1 1029.69
  4879.3 1028.63  4885.8 1029.42  4900.1 1030.13  4921.6 1030.14  4969.7 1027.50
  4969.9 1027.00  4973.4 1027.00  4973.7 1027.50  5010.0 1029.06  5017.7 1030.01
  5071.8 1032.02  5100.2 1034.58  5133.7 1036.47  5146.5 1036.46  5205.8 1039.23
#Mann=3,-1,0
  4609.1    0.12       0  4969.7    0.05       0  4973.7    0.12       0
Bank Sta=4969.7,4973.7
Exp/Cntr=0.3,0.1

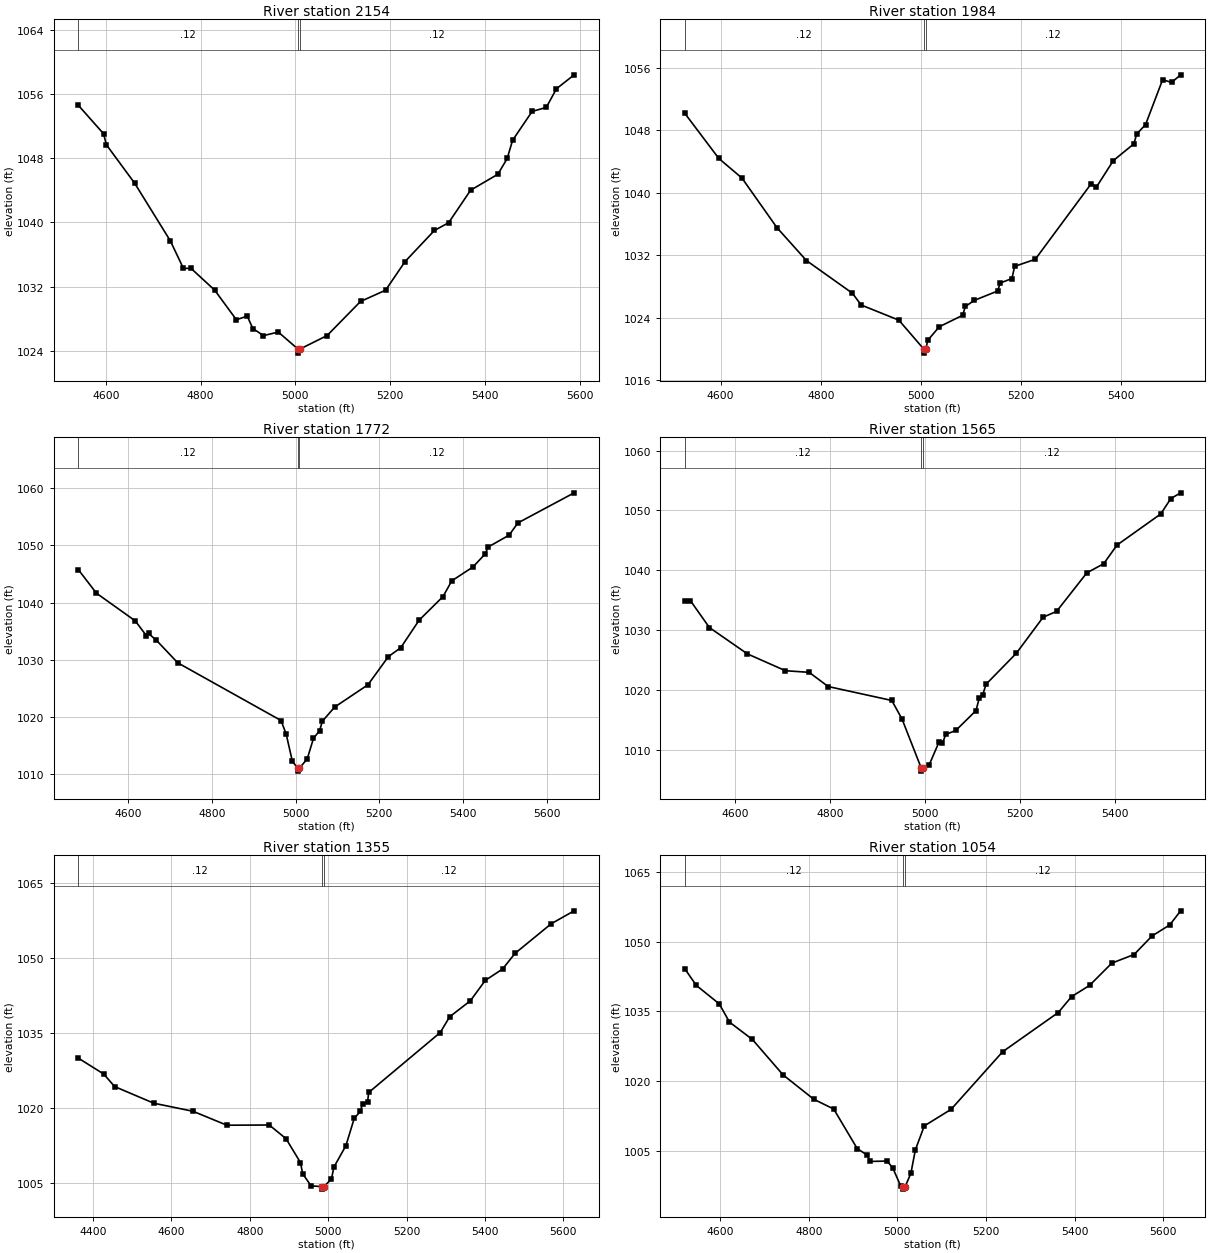
Type RM Length L Ch R = 1,2154,170,170,170
BEGIN DESCRIPTION:
XS7906
END DESCRIPTION:
XS GIS Cut Line= 3
      2201246.89     13820374.21      2200721.70     13820665.02
      2200288.85     13820773.23
#Sta/Elev= 30
  4541.9 1054.57  4595.1 1051.03  4601.2 1049.65  4660.6 1044.89  4736.2 1037.69
  4763.6 1034.28  4779.7 1034.28  4829.8 1031.56  4875.5 1027.88  4898.4 1028.34
  4910.2 1026.79  4932.7 1025.91  4964.0 1026.35  5005.5 1024.23  5005.8 1023.73
  5009.5 1024.23  5067.0 1025.92  5137.5 1030.16  5190.4 1031.56  5231.6 1035.13
  5293.4 1038.99  5323.5 1039.96  5369.8 1044.00  5427.4 1045.99  5447.1 1047.95
  5458.4 1050.21  5499.6 1053.80  5529.6 1054.31  5551.1 1056.63  5588.4 1058.36
#Mann=3,-1,0
  4541.9    0.12       0  5005.5    0.05       0  5009.5    0.12       0
Bank Sta=5005.5,5009.5
Exp/Cntr=0.3,0.1

Type RM Length L Ch R = 1,1984,212,212,212
BEGIN DESCRIPTION:
H21518
END DESCRIPTION:
XS GIS Cut Line= 2
      2201157.11     13820284.88      2200251.83     13820686.59
#Sta/Elev= 30
  4528.5 1050.18  4596.4 1044.41  4642.7 1041.89  4712.5 1035.55  4771.5 1031.33
  4863.1 1027.16  4880.9 1025.64  4956.1 1023.70  5006.1 1019.98  5006.4 1019.48
  5010.1 1019.98  5013.6 1021.11  5036.9 1022.86  5083.4 1024.32  5088.9 1025.45
  5106.7 1026.23  5153.2 1027.43  5158.7 1028.46  5181.9 1029.03  5187.4 1030.59
  5228.5 1031.49  5340.4 1041.18  5350.3 1040.70  5384.5 1044.13  5425.6 1046.28
  5431.0 1047.52  5448.8 1048.73  5483.0 1054.50  5500.8 1054.13  5518.9 1055.11
#Mann=3,-1,0
  4528.5    0.12       0  5006.1    0.05       0  5010.1    0.12       0
Bank Sta=5006.1,5010.1
Exp/Cntr=0.3,0.1

Type RM Length L Ch R = 1,1772,207,207,207
BEGIN DESCRIPTION:
XS7905
END DESCRIPTION:
XS GIS Cut Line= 3
      2201068.92     13820191.93      2200669.62     13820261.37
      2200031.64     13820708.39
#Sta/Elev= 30
  4481.1 1045.76  4524.4 1041.63  4617.0 1036.79  4643.7 1034.19  4648.7 1034.58
  4667.8 1033.37  4718.5 1029.44  4965.2 1019.33  4977.5 1016.97  4992.2 1012.22
  5005.0 1010.96  5005.3 1010.46  5009.0 1010.96  5027.9 1012.62  5042.8 1016.21
  5057.6 1017.57  5063.7 1019.18  5093.3 1021.68  5172.9 1025.59  5221.7 1030.53
  5251.1 1032.07  5295.0 1036.90  5352.2 1041.05  5373.1 1043.80  5423.7 1046.23
  5453.3 1048.55  5459.5 1049.71  5510.0 1051.80  5530.9 1053.94  5665.4 1059.22
#Mann=3,-1,0
  4481.1    0.12       0  5005.0    0.05       0  5009.0    0.12       0
Bank Sta=5005,5009
Exp/Cntr=0.3,0.1

Type RM Length L Ch R = 1,1565,210,210,210
BEGIN DESCRIPTION:
H21517
END DESCRIPTION:
XS GIS Cut Line= 3
      2200896.83     13820163.25      2200461.16     13820160.42
      2200036.85     13820596.05
#Sta/Elev= 30
  4493.8 1034.95  4505.6 1034.93  4545.6 1030.44  4625.6 1026.04  4705.6 1023.23
  4755.6 1022.96  4795.6 1020.59  4929.5 1018.26  4951.1 1015.16  4991.6 1006.96
  4991.8 1006.46  4995.6 1006.96  5007.7 1007.40  5029.0 1011.32  5036.0 1011.08
  5043.2 1012.59  5064.3 1013.25  5106.7 1016.56  5113.9 1018.70  5120.9 1019.19
  5128.1 1020.98  5191.6 1026.13  5248.2 1032.17  5276.5 1033.14  5340.2 1039.58
  5375.5 1041.09  5403.8 1044.22  5495.7 1049.41  5517.0 1051.98  5537.6 1052.94
#Mann=3,-1,0
  4493.8    0.12       0  4991.6    0.05       0  4995.6    0.12       0
Bank Sta=4991.6,4995.6
Exp/Cntr=0.3,0.1

Type RM Length L Ch R = 1,1355,301,301,301
BEGIN DESCRIPTION:
XS7904
END DESCRIPTION:
XS GIS Cut Line= 4
      2200808.46     13820109.45      2200435.24     13820031.34
      2200131.42     13820217.97      2199927.45     13820704.04
#Sta/Elev= 30
  4362.5 1029.95  4427.3 1026.77  4455.2 1024.26  4555.1 1020.93  4655.0 1019.32
  4741.4 1016.53  4849.7 1016.57  4892.4 1013.83  4929.2 1009.06  4935.0 1006.81
  4956.3 1004.39  4985.1 1004.24  4985.4 1003.74  4989.1 1004.24  5008.4 1005.78
  5014.3 1008.11  5045.1 1012.43  5066.4 1017.90  5081.9 1019.29  5087.7 1020.82
  5100.4 1021.19  5103.3 1023.08  5285.9 1035.08  5309.7 1038.21  5362.7 1041.43
  5400.8 1045.51  5444.8 1047.78  5476.7 1050.92  5569.1 1056.85  5627.5 1059.43
#Mann=3,-1,0
  4362.5    0.12       0  4985.1    0.05       0  4989.1    0.12       0
Bank Sta=4985.1,4989.1
Exp/Cntr=0.3,0.1

Type RM Length L Ch R = 1,1054,376,376,376
BEGIN DESCRIPTION:
XS7903
END DESCRIPTION:
XS GIS Cut Line= 3
      2200161.79     13819588.67      2199957.81     13820040.02
      2199879.88     13820659.13
#Sta/Elev= 30
  4520.0 1044.15  4546.0 1040.58  4597.7 1036.63  4620.9 1032.71  4672.6 1028.98
  4741.9 1021.38  4811.3 1016.15  4856.2 1014.06  4909.2 1005.58  4932.3 1004.14
  4937.8 1002.82  4976.9 1002.90  4989.5 1001.41  5007.1  997.62  5013.3  997.38
  5013.5  996.88  5017.3  997.38  5030.4 1000.28  5040.5 1005.30  5060.6 1010.44
  5121.1 1013.99  5237.5 1026.35  5363.0 1034.76  5393.2 1038.18  5433.6 1040.57
  5484.0 1045.36  5534.3 1047.21  5574.7 1051.18  5615.0 1053.58  5639.3 1056.58
#Mann=3,-1,0
  4520.0    0.12       0  5013.3    0.05       0  5017.3    0.12       0
Bank Sta=5013.3,5017.3
Exp/Cntr=0.3,0.1

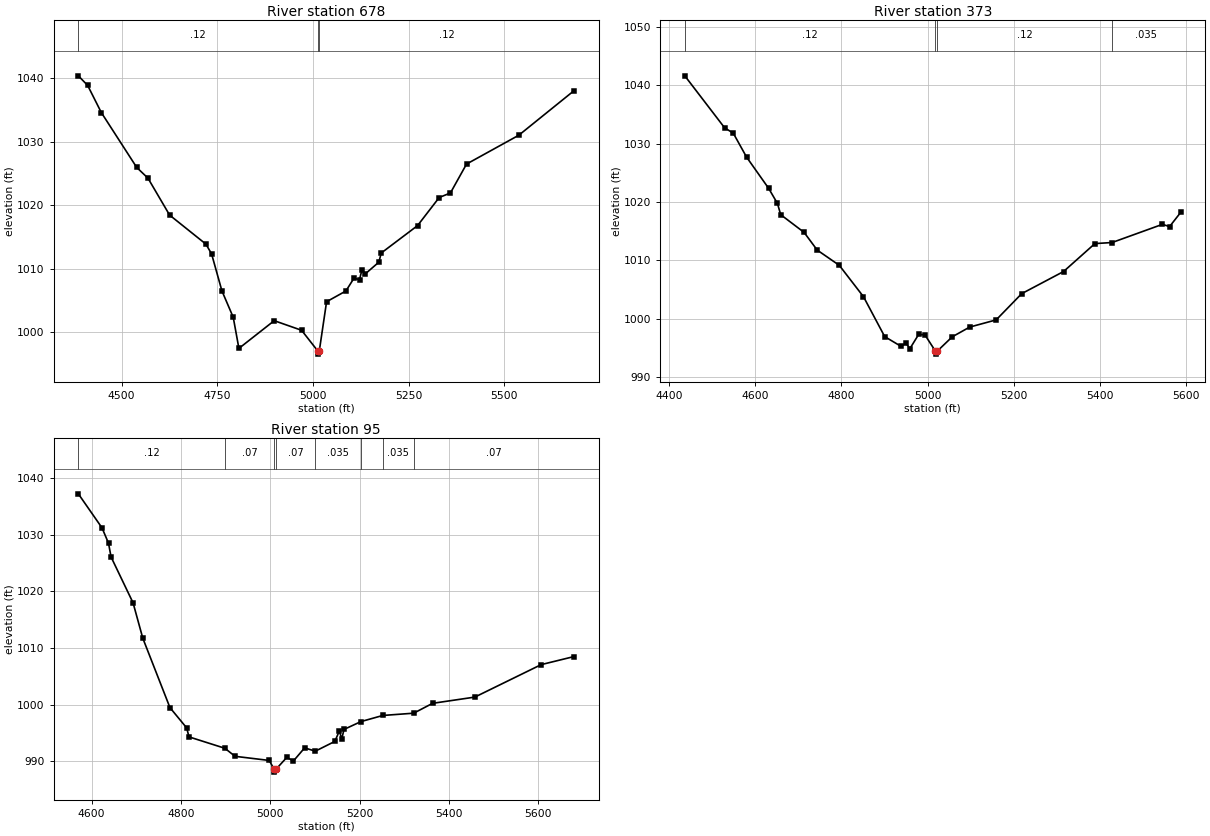
Type RM Length L Ch R = 1,678,305,305,305
BEGIN DESCRIPTION:
XS7902
END DESCRIPTION:
XS GIS Cut Line= 2
      2200109.75     13819605.97      2199050.72     13820352.50
#Sta/Elev= 30
  4386.9 1040.34  4411.2 1038.84  4446.9 1034.57  4539.5 1025.93  4568.8 1024.25
  4625.4 1018.44  4720.3 1013.87  4735.1 1012.34  4762.1 1006.52  4791.7 1002.36
  4806.5  997.47  4898.8 1001.83  4970.3 1000.32  5012.6  997.07  5012.9  996.57
  5016.6  997.07  5035.6 1004.81  5086.1 1006.50  5107.0 1008.49  5121.8 1008.30
  5127.9 1009.81  5136.6 1009.18  5172.3 1011.04  5178.4 1012.47  5273.3 1016.78
  5329.9 1021.20  5359.3 1021.92  5401.3 1026.46  5538.0 1031.00  5682.6 1038.02
#Mann=3,-1,0
  4386.9    0.12       0  5012.6    0.05       0  5016.6    0.12       0
Bank Sta=5012.6,5016.6
Exp/Cntr=0.3,0.1

Type RM Length L Ch R = 1,373,278,278,278
BEGIN DESCRIPTION:
XS7901
END DESCRIPTION:
XS GIS Cut Line= 3
      2200075.00     13819562.59      2199468.22     13819693.66
      2198995.75     13819930.77
#Sta/Elev= 30
  4437.2 1041.60  4529.3 1032.72  4549.7 1031.77  4580.4 1027.69  4631.6 1022.34
  4652.0 1019.75  4659.5 1017.84  4713.8 1014.80  4744.1 1011.78  4795.3 1009.17
  4851.4 1003.80  4900.6  996.97  4938.5  995.30  4949.9  995.86  4959.0  994.91
  4979.4  997.35  4994.0  997.25  5018.3  994.47  5018.6  993.97  5022.3  994.47
  5057.1  996.93  5097.6  998.60  5159.0  999.83  5218.2 1004.32  5315.3 1008.11
  5387.9 1012.89  5427.7 1013.07  5544.3 1016.18  5561.0 1015.80  5586.6 1018.21
#Mann=4,-1,0
  4437.2    0.12       0  5018.3    0.05       0  5022.3    0.12       0
  5427.7   0.035       0
Bank Sta=5018.3,5022.3
Exp/Cntr=0.3,0.1

Type RM Length L Ch R = 1,95,0,0,0
BEGIN DESCRIPTION:
H21516
END DESCRIPTION:
XS GIS Cut Line= 5
      2199997.23     13819501.29      2199683.21     13819447.54
      2199538.94     13819410.77      2199343.74     13819458.86
      2198984.46     13819716.30
#Sta/Elev= 30
  4570.2 1037.20  4623.2 1031.20  4637.8 1028.49  4643.5 1026.06  4692.8 1017.96
  4714.5 1011.74  4775.4  999.47  4812.9  995.89  4818.0  994.31  4898.4  992.30
  4921.2  990.88  4997.8  990.15  5008.8  988.59  5009.0  988.09  5012.8  988.59
  5037.1  990.69  5052.0  990.06  5077.0  992.37  5101.0  991.79  5144.7  993.51
  5154.9  995.38  5160.0  993.92  5165.3  995.63  5203.2  997.01  5252.2  998.09
  5321.3  998.49  5363.6 1000.23  5458.2 1001.33  5606.8 1007.06  5680.7 1008.49
#Mann=8,-1,0
  4570.2    0.12       0  4898.4    0.07       0  5008.8    0.05       0
  5012.8    0.07       0  5101.0   0.035       0  5203.2    0.07       0
  5252.2   0.035       0  5321.3    0.07       0
Bank Sta=5008.8,5012.8
Exp/Cntr=0.3,0.1

Chan Stop Cuts=-1