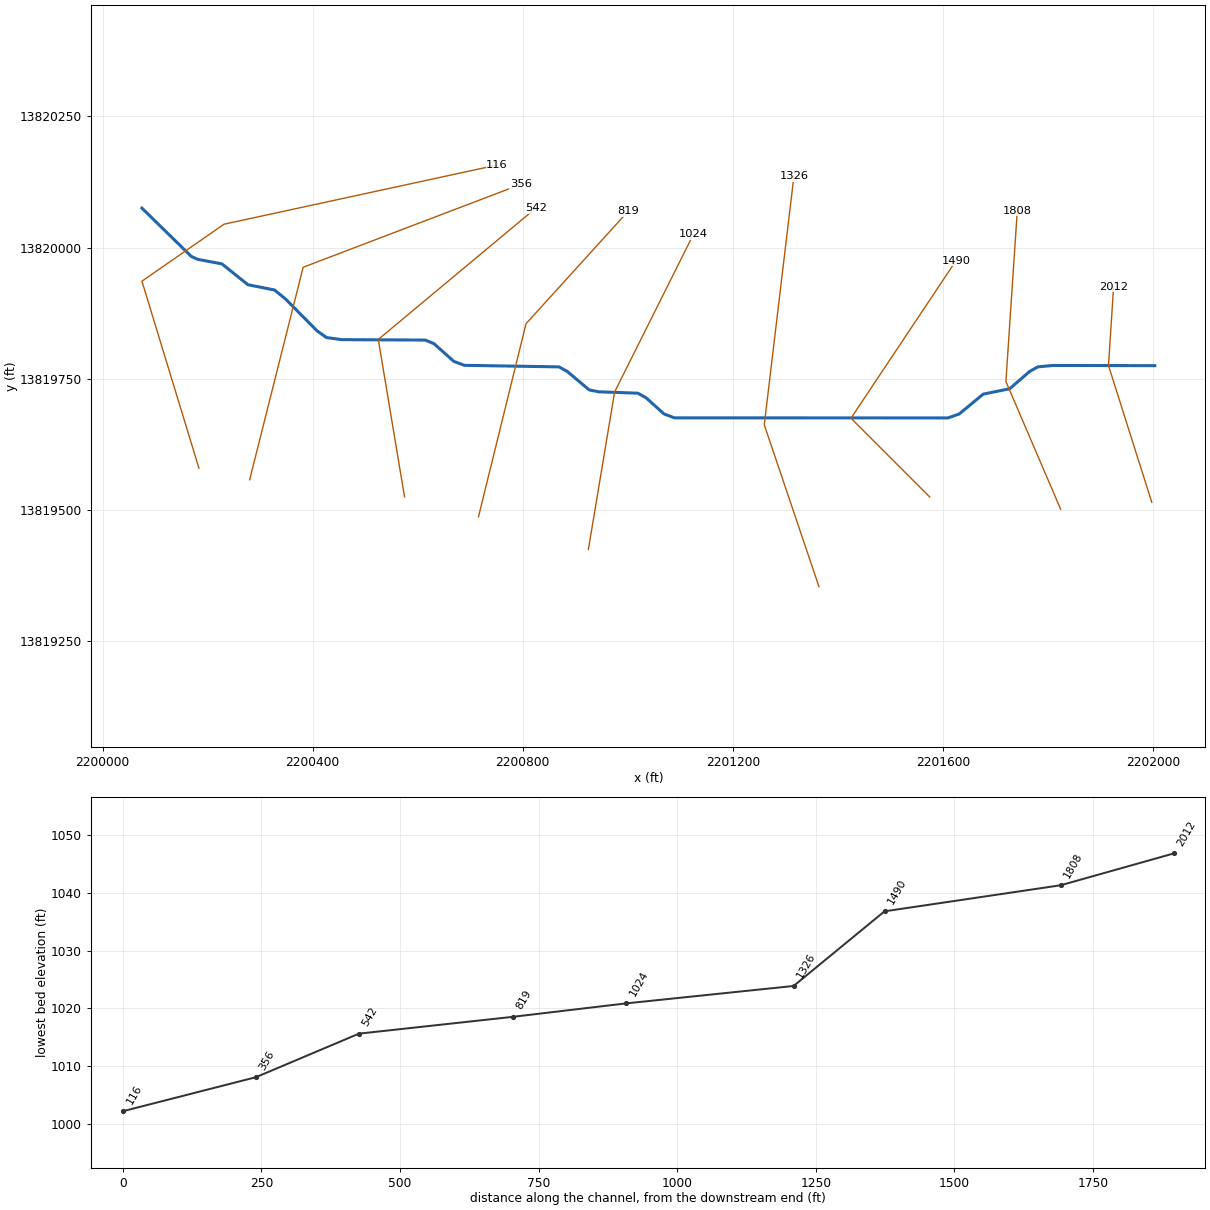
--- Upper Dry Comal Tributary 20b.prj (project) ---

Proj Title=Upper Dry Comal Tributary 20b Base Level Engineering
Current Plan=p01
Default Exp/Contr=0.3,0.1
English Units
Geom File=g01
Flow File=f01
Plan File=p01
BEGIN DESCRIPTION:
Upper Dry Comal Tributary 20b
END DESCRIPTION:

--- Upper Dry Comal Tributary 20b.p01 (plan) ---

Plan Title=Multiple Run
Short Identifier=Multiple
Geom File=g01
Flow File=f01
Subcritical Flow
K Sum by GR= 0
Std Step Tol= 0.01
Critical Tol= 0.01
Num of Std Step Trials= 20
Max Error Tol= 0.3
Flow Tol Ratio= 0.001
Split Flow NTrial= 30
Split Flow Tol= 0.02
Split Flow Ratio= 0.02
Log Output Level= 0
Friction Slope Method= 1
Unsteady Friction Slope Method= 2
Unsteady Bridges Friction Slope Method= 1
Parabolic Critical Depth
Global Vel Dist=  1 , 1 , 1
Global Log Level= 0
CheckData=True
Encroach Param= -1, 0, 0, 0
BEGIN DESCRIPTION:
Multiple Run
END DESCRIPTION:

--- Upper Dry Comal Tributary 20b.f01 (steady flow) ---

Flow Title=Multiple
Number of Profiles=7
Profile Names=10-year,25-year,50-year,1pct_min,100-year,1pct_plu,500-year
River Rch & RM= Upper Dry Comal ,Reach-1,2012
     459     737     990     646    1290    2573    2161
Boundary for River Rch & Prof#=Upper Dry Comal ,Reach-1,1
Up Type=0
Dn Type=3
Dn Slope=0.005
Boundary for River Rch & Prof#=Upper Dry Comal ,Reach-1,2
Up Type=0
Dn Type=3
Dn Slope=0.005
Boundary for River Rch & Prof#=Upper Dry Comal ,Reach-1,3
Up Type=0
Dn Type=3
Dn Slope=0.005
Boundary for River Rch & Prof#=Upper Dry Comal ,Reach-1,4
Up Type=0
Dn Type=3
Dn Slope=0.005
Boundary for River Rch & Prof#=Upper Dry Comal ,Reach-1,5
Up Type=0
Dn Type=3
Dn Slope=0.005
Boundary for River Rch & Prof#=Upper Dry Comal ,Reach-1,6
Up Type=0
Dn Type=3
Dn Slope=0.005
Boundary for River Rch & Prof#=Upper Dry Comal ,Reach-1,7
Up Type=0
Dn Type=3
Dn Slope=0.005

--- Upper Dry Comal Tributary 20b.g01 (geometry) ---

Geom Title=Existing Conditions

River Reach=Upper Dry Comal ,Reach-1
Reach XY= 30
      2202003.41     13819775.00      2201809.82     13819775.44
      2201780.93     13819772.76      2201765.33     13819764.20
      2201727.18     13819731.12      2201676.74     13819720.81
      2201631.08     13819683.09      2201609.79     13819675.51
      2201088.92     13819675.68      2201068.94     13819683.14
      2201034.63     13819714.11      2201019.02     13819722.64
      2200945.10     13819725.24      2200926.60     13819728.86
      2200884.65     13819764.15      2200869.06     13819772.74
      2200688.92     13819775.69      2200668.94     13819783.14
      2200631.06     13819816.86      2200614.49     13819823.78
      2200454.82     13819824.57      2200426.47     13819828.55
      2200408.25     13819841.46      2200348.44     13819901.94
      2200327.29     13819919.15      2200276.73     13819929.19
      2200227.19     13819968.91      2200181.03     13819977.48
      2200168.92     13819983.09      2200075.00     13820075.00

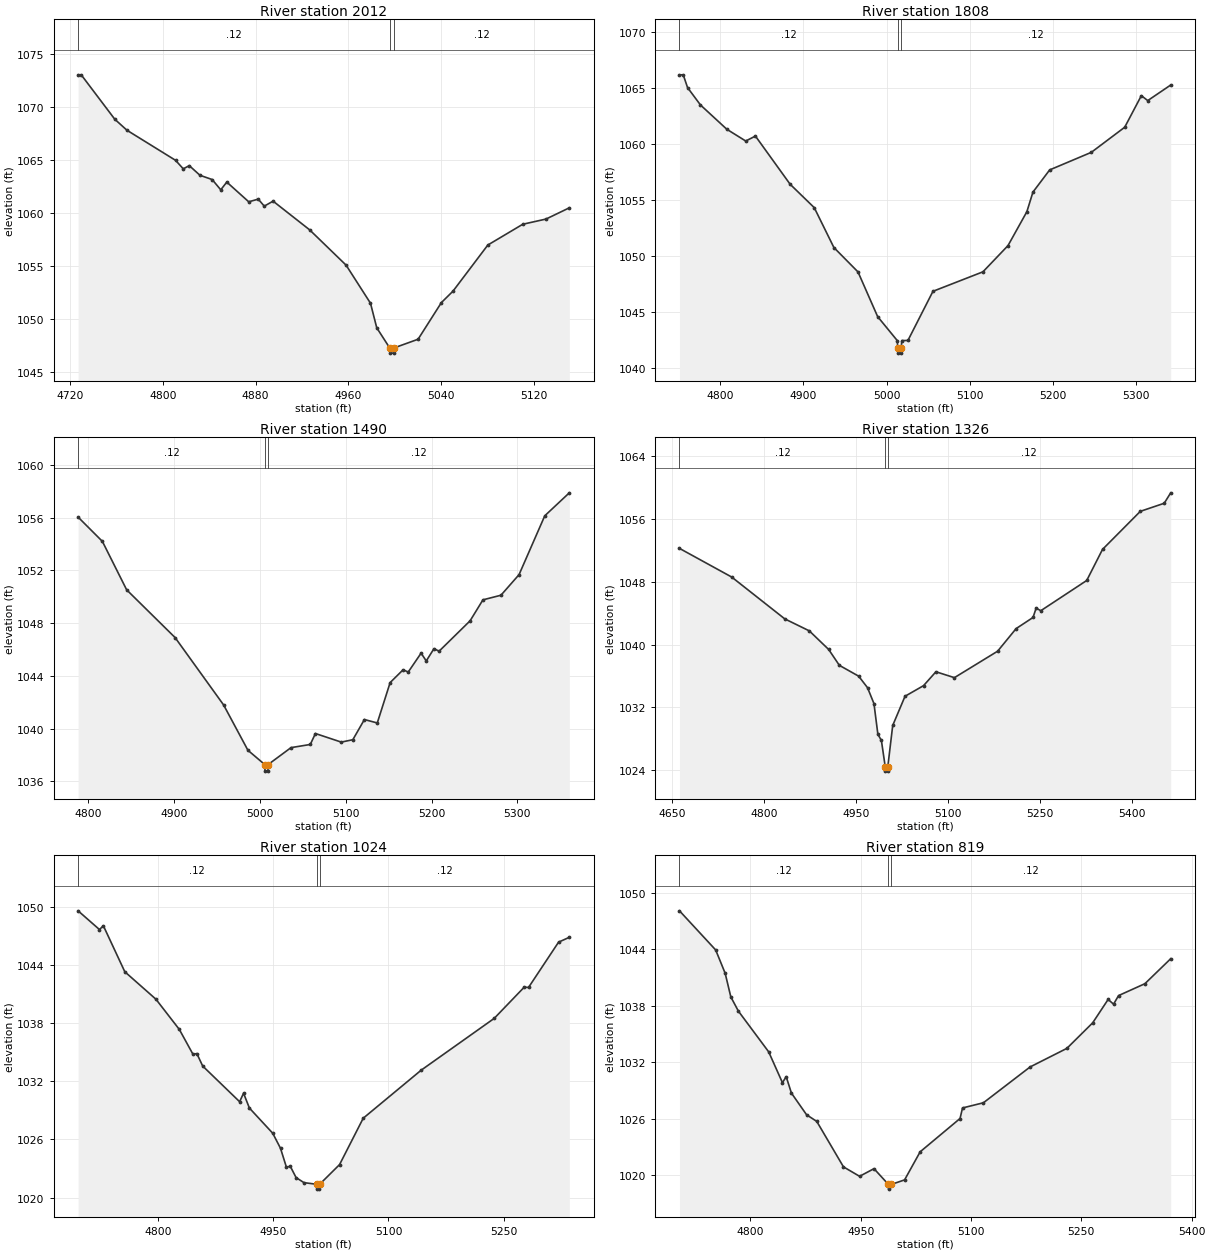
Type RM Length L Ch R = 1,2012,204,204,204
BEGIN DESCRIPTION:
Upper Dry Comal Tributary 20b 4.0
END DESCRIPTION:
XS GIS Cut Line= 3
      2201997.73     13819514.87      2201915.28     13819775.26
      2201925.00     13819925.02
#Sta/Elev= 30
  4727.1 1073.05  4729.8 1073.05  4758.7 1068.86  4769.2 1067.82  4811.1 1064.98
  4817.7 1064.18  4822.9 1064.48  4832.1 1063.57  4842.6 1063.17  4850.0 1062.20
  4855.2 1062.93  4874.1 1061.07  4882.3 1061.32  4887.5 1060.66  4895.1 1061.13
  4926.5 1058.43  4958.0 1055.09  4979.0 1051.50  4984.4 1049.18  4995.5 1047.29
  4995.7 1046.79  4999.2 1046.79  4999.5 1047.29  5020.0 1048.10  5040.1 1051.56
  5050.1 1052.64  5080.1 1056.99  5110.2 1058.95  5130.2 1059.44  5150.3 1060.50
#Mann=3,-1,0
  4727.1    0.12       0  4995.5    0.05       0  4999.5    0.12       0
Bank Sta=4995.5,4999.5
Exp/Cntr=0.3,0.1

Type RM Length L Ch R = 1,1808,318,318,318
BEGIN DESCRIPTION:
XS7909
END DESCRIPTION:
XS GIS Cut Line= 3
      2201824.14     13819501.81      2201719.97     13819744.88
      2201741.65     13820070.20
#Sta/Elev= 30
  4751.1 1066.14  4755.6 1066.14  4760.8 1065.00  4776.3 1063.45  4808.0 1061.28
  4830.7 1060.23  4842.4 1060.67  4884.1 1056.37  4913.1 1054.28  4936.7 1050.72
  4965.7 1048.54  4989.3 1044.55  5012.9 1042.41  5013.5 1041.79  5013.8 1041.29
  5017.3 1041.29  5017.5 1041.79  5018.4 1042.41  5025.7 1042.42  5055.8 1046.81
  5115.9 1048.55  5146.0 1050.89  5168.7 1053.92  5176.0 1055.67  5196.1 1057.65
  5246.2 1059.22  5286.3 1061.46  5306.3 1064.28  5314.0 1063.84  5341.6 1065.23
#Mann=3,-1,0
  4751.1    0.12       0  5013.5    0.05       0  5017.5    0.12       0
Bank Sta=5013.5,5017.5
Exp/Cntr=0.3,0.1

Type RM Length L Ch R = 1,1490,164,164,164
BEGIN DESCRIPTION:
Upper Dry Comal Tributary 20b 3.0
END DESCRIPTION:
XS GIS Cut Line= 3
      2201574.99     13819525.01      2201425.00     13819675.00
      2201625.02     13819975.02
#Sta/Elev= 30
  4787.9 1056.03  4816.2 1054.19  4844.5 1050.52  4901.0 1046.90  4957.6 1041.79
  4985.9 1038.36  5005.5 1037.28  5005.8 1036.78  5009.3 1036.78  5009.5 1037.28
  5036.1 1038.56  5058.6 1038.80  5064.6 1039.63  5094.7 1038.98  5108.2 1039.16
  5121.7 1040.69  5136.7 1040.43  5151.7 1043.49  5166.8 1044.46  5172.8 1044.29
  5187.8 1045.72  5193.8 1045.13  5202.8 1046.06  5208.8 1045.87  5244.9 1048.17
  5259.9 1049.76  5280.9 1050.11  5302.0 1051.67  5332.0 1056.13  5360.6 1057.87
#Mann=3,-1,0
  4787.9    0.12       0  5005.5    0.05       0  5009.5    0.12       0
Bank Sta=5005.5,5009.5
Exp/Cntr=0.3,0.1

Type RM Length L Ch R = 1,1326,302,302,302
BEGIN DESCRIPTION:
XS7908
END DESCRIPTION:
XS GIS Cut Line= 3
      2201364.05     13819354.29      2201259.90     13819662.41
      2201316.32     13820135.51
#Sta/Elev= 30
  4662.1 1052.26  4747.3 1048.61  4833.9 1043.28  4874.0 1041.75  4905.6 1039.38
  4923.0 1037.36  4954.5 1035.98  4969.0 1034.51  4979.5 1032.48  4985.9 1028.56
  4991.6 1027.80  4998.0 1024.38  4998.3 1023.88  5001.8 1023.88  5002.0 1024.38
  5010.1 1029.70  5030.2 1033.42  5060.4 1034.77  5080.6 1036.54  5110.8 1035.79
  5181.3 1039.16  5211.5 1042.04  5239.1 1043.46  5244.2 1044.65  5251.8 1044.32
  5326.7 1048.17  5352.5 1052.13  5414.2 1056.98  5453.2 1058.01  5463.8 1059.34
#Mann=3,-1,0
  4662.1    0.12       0  4998.0    0.05       0  5002.0    0.12       0
Bank Sta=4998,5002
Exp/Cntr=0.3,0.1

Type RM Length L Ch R = 1,1024,205,205,205
BEGIN DESCRIPTION:
Upper Dry Comal Tributary 20b 2.0
END DESCRIPTION:
XS GIS Cut Line= 3
      2200925.01     13819425.04      2200975.00     13819725.00
      2201125.00     13820024.99
#Sta/Elev= 30
  4695.9 1049.56  4723.7 1047.63  4728.8 1048.02  4756.7 1043.28  4797.2 1040.45
  4827.7 1037.33  4845.4 1034.78  4850.5 1034.84  4858.1 1033.56  4906.2 1029.88
  4911.3 1030.76  4918.9 1029.23  4949.3 1026.63  4959.4 1025.08  4967.1 1023.13
  4972.1 1023.23  4979.7 1022.06  4989.9 1021.54  5006.4 1021.37  5006.6 1020.87
  5010.1 1020.87  5010.4 1021.37  5036.3 1023.40  5067.1 1028.18  5142.5 1033.13
  5237.6 1038.47  5276.7 1041.69  5282.3 1041.66  5321.4 1046.33  5335.4 1046.83
#Mann=3,-1,0
  4695.9    0.12       0  5006.4    0.05       0  5010.4    0.12       0
Bank Sta=5006.4,5010.4
Exp/Cntr=0.3,0.1

Type RM Length L Ch R = 1,819,277,277,277
BEGIN DESCRIPTION:
H21522
END DESCRIPTION:
XS GIS Cut Line= 3
      2200715.77     13819487.19      2200806.28     13819854.90
      2201000.76     13820069.11
#Sta/Elev= 30
  4703.5 1048.06  4752.7 1043.91  4765.6 1041.44  4773.3 1038.93  4783.6 1037.42
  4824.8 1033.10  4843.5 1029.83  4848.6 1030.47  4855.7 1028.73  4876.3 1026.43
  4890.2 1025.72  4926.5 1020.90  4948.4 1019.90  4968.0 1020.71  4987.6 1019.04
  4987.8 1018.54  4991.6 1019.04  5009.6 1019.52  5030.8 1022.50  5085.0 1026.03
  5088.4 1027.15  5116.8 1027.70  5180.3 1031.50  5230.3 1033.47  5265.4 1036.18
  5286.4 1038.66  5293.8 1038.16  5300.6 1039.07  5336.4 1040.33  5371.5 1042.98
#Mann=3,-1,0
  4703.5    0.12       0  4987.6    0.05       0  4991.6    0.12       0
Bank Sta=4987.6,4991.6
Exp/Cntr=0.3,0.1

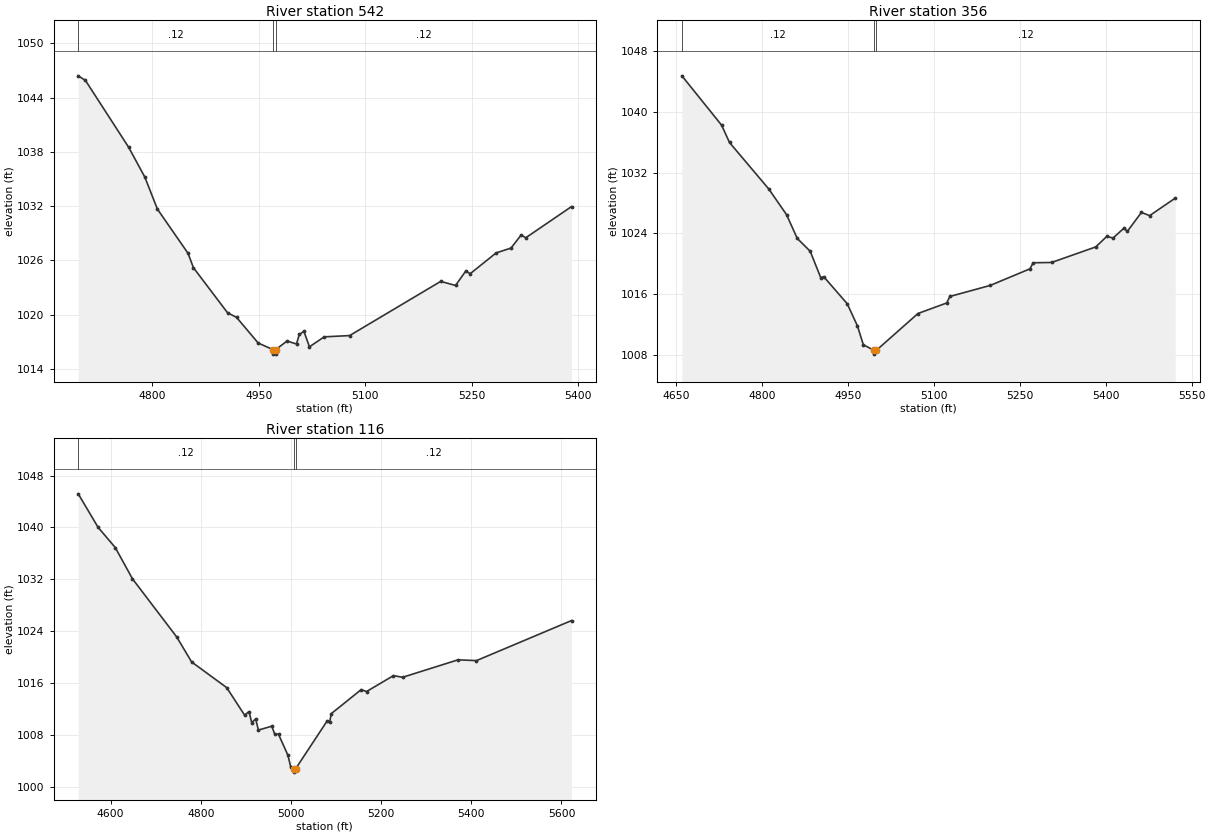
Type RM Length L Ch R = 1,542,186,186,186
BEGIN DESCRIPTION:
Upper Dry Comal Tributary 20b 1.0
END DESCRIPTION:
XS GIS Cut Line= 3
      2200575.00     13819525.02      2200525.00     13819825.00
      2200824.98     13820074.98
#Sta/Elev= 30
  4695.9 1046.40  4706.0 1045.90  4766.8 1038.52  4789.7 1035.21  4807.4 1031.67
  4850.5 1026.79  4858.1 1025.20  4906.2 1020.21  4918.9 1019.70  4949.3 1016.87
  4970.1 1016.14  4970.4 1015.64  4973.9 1015.64  4974.1 1016.14  4989.9 1017.09
  5003.3 1016.76  5007.2 1017.81  5013.7 1018.16  5021.5 1016.45  5042.3 1017.55
  5078.1 1017.69  5206.3 1023.68  5227.2 1023.23  5241.5 1024.81  5248.0 1024.54
  5284.4 1026.83  5305.3 1027.36  5319.6 1028.81  5326.1 1028.50  5390.5 1031.95
#Mann=3,-1,0
  4695.9    0.12       0  4970.1    0.05       0  4974.1    0.12       0
Bank Sta=4970.1,4974.1
Exp/Cntr=0.3,0.1

Type RM Length L Ch R = 1,356,240,240,240
BEGIN DESCRIPTION:
H21521
END DESCRIPTION:
XS GIS Cut Line= 3
      2200280.10     13819557.84      2200381.95     13819962.40
      2200796.69     13820120.40
#Sta/Elev= 30
  4660.3 1044.76  4729.6 1038.26  4743.4 1035.98  4812.1 1029.84  4843.0 1026.47
  4861.6 1023.35  4884.2 1021.66  4902.7 1018.17  4907.8 1018.31  4948.9 1014.74
  4966.7 1011.82  4977.0 1009.34  4995.7 1008.61  4995.9 1008.11  4999.7 1008.61
  5072.3 1013.46  5122.6 1014.85  5127.9 1015.70  5198.5 1017.16  5267.7 1019.34
  5273.4 1020.14  5305.5 1020.18  5382.7 1022.23  5401.8 1023.61  5412.8 1023.40
  5432.2 1024.72  5437.6 1024.26  5462.3 1026.77  5476.7 1026.35  5521.3 1028.65
#Mann=3,-1,0
  4660.3    0.12       0  4995.7    0.05       0  4999.7    0.12       0
Bank Sta=4995.7,4999.7
Exp/Cntr=0.3,0.1

Type RM Length L Ch R = 1,116,0,0,0
BEGIN DESCRIPTION:
XS7907
END DESCRIPTION:
XS GIS Cut Line= 4
      2200183.52     13819579.92      2200075.00     13819935.85
      2200231.25     13820044.36      2200751.05     13820156.98
#Sta/Elev= 30
  4528.1 1045.18  4572.2 1040.01  4610.3 1036.89  4648.4 1032.07  4746.8 1023.07
  4779.6 1019.24  4857.5 1015.27  4897.1 1011.03  4906.9 1011.57  4913.0 1009.87
  4921.7 1010.44  4927.8 1008.72  4957.5 1009.32  4963.6 1008.16  4972.4 1008.07
  4993.3 1004.83  4999.4 1003.04  5006.2 1002.73  5006.4 1002.23  5010.2 1002.73
  5079.8 1010.08  5085.9 1010.02  5089.7 1011.27  5155.7 1014.96  5167.7 1014.67
  5227.3 1017.12  5247.8 1016.87  5370.5 1019.56  5411.5 1019.44  5622.3 1025.62
#Mann=3,-1,0
  4528.1    0.12       0  5006.2    0.05       0  5010.2    0.12       0
Bank Sta=5006.2,5010.2
Exp/Cntr=0.3,0.1

Chan Stop Cuts=-1