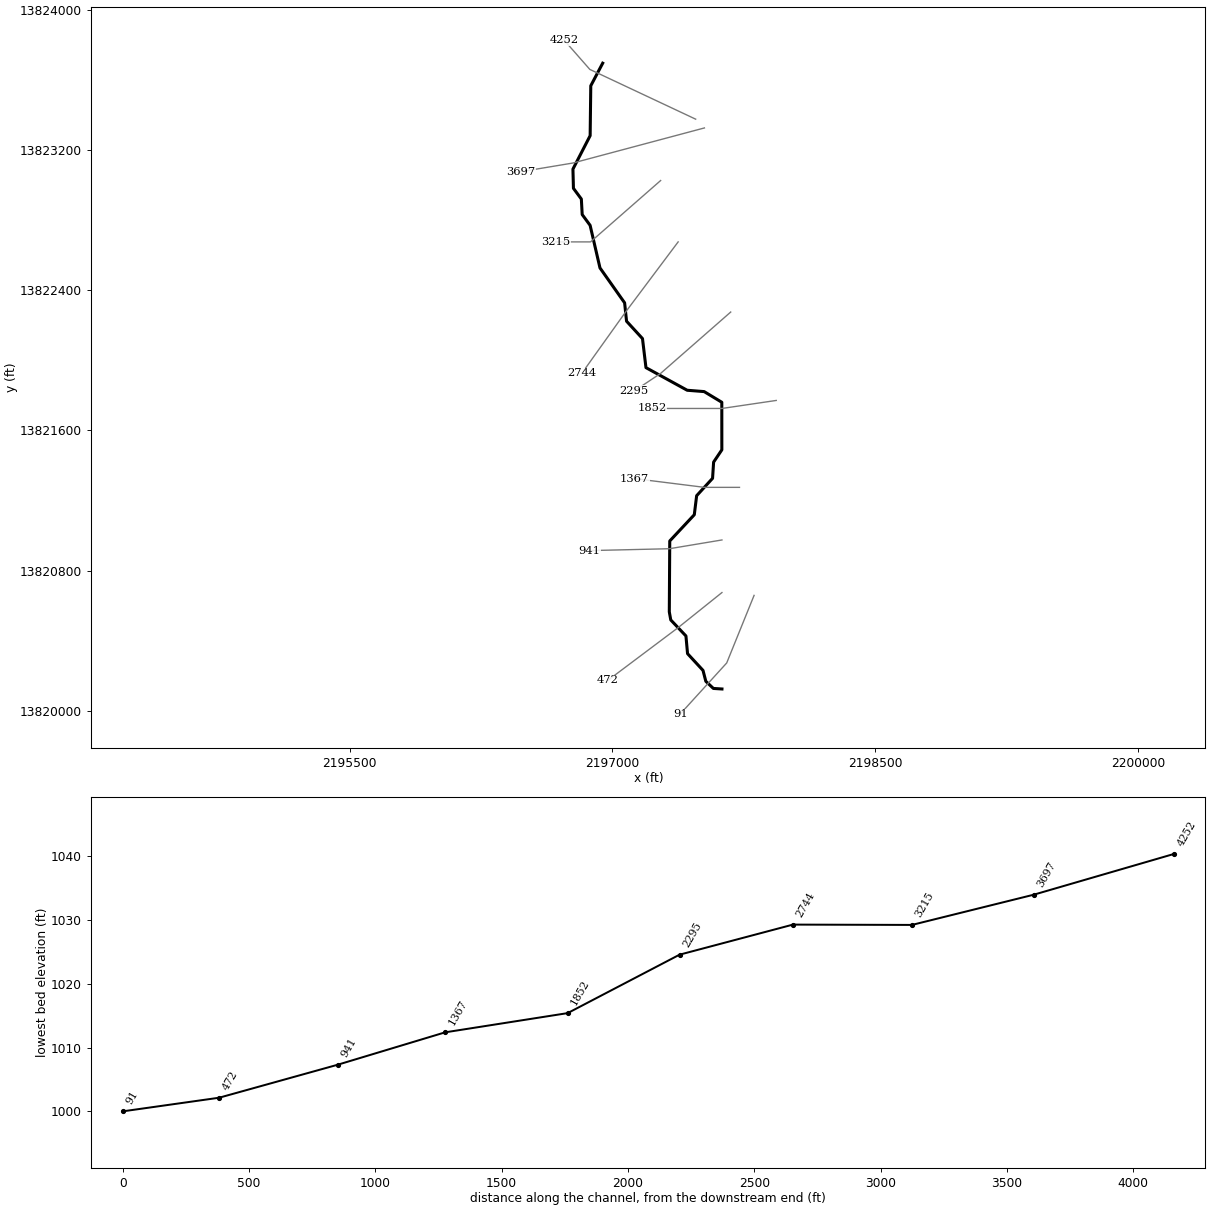
--- Upper Dry Comal Tributary 21.prj (project) ---

Proj Title=Upper Dry Comal Tributary 21 Base Level Engineering
Current Plan=p01
Default Exp/Contr=0.3,0.1
English Units
Geom File=g01
Flow File=f01
Plan File=p01
BEGIN DESCRIPTION:
Upper Dry Comal Tributary 21
END DESCRIPTION:

--- Upper Dry Comal Tributary 21.p01 (plan) ---

Plan Title=Multiple Run
Short Identifier=Multiple
Geom File=g01
Flow File=f01
Subcritical Flow
K Sum by GR= 0
Std Step Tol= 0.01
Critical Tol= 0.01
Num of Std Step Trials= 20
Max Error Tol= 0.3
Flow Tol Ratio= 0.001
Split Flow NTrial= 30
Split Flow Tol= 0.02
Split Flow Ratio= 0.02
Log Output Level= 0
Friction Slope Method= 1
Unsteady Friction Slope Method= 2
Unsteady Bridges Friction Slope Method= 1
Parabolic Critical Depth
Global Vel Dist=  1 , 1 , 1
Global Log Level= 0
CheckData=True
Encroach Param= -1, 0, 0, 0
BEGIN DESCRIPTION:
Multiple Run
END DESCRIPTION:

--- Upper Dry Comal Tributary 21.f01 (steady flow) ---

Flow Title=Multiple
Number of Profiles=7
Profile Names=10-year,25-year,50-year,1pct_min,100-year,1pct_plu,500-year
River Rch & RM= Upper Dry Comal ,Reach-1,4252
    1023    1720    2379    1593    3179    6343    5618
River Rch & RM= Upper Dry Comal ,Reach-1,3697
    1296    2201    3062    2061    4113    8206    7343
Boundary for River Rch & Prof#=Upper Dry Comal ,Reach-1,1
Up Type=0
Dn Type=3
Dn Slope=0.005
Boundary for River Rch & Prof#=Upper Dry Comal ,Reach-1,2
Up Type=0
Dn Type=3
Dn Slope=0.005
Boundary for River Rch & Prof#=Upper Dry Comal ,Reach-1,3
Up Type=0
Dn Type=3
Dn Slope=0.005
Boundary for River Rch & Prof#=Upper Dry Comal ,Reach-1,4
Up Type=0
Dn Type=3
Dn Slope=0.005
Boundary for River Rch & Prof#=Upper Dry Comal ,Reach-1,5
Up Type=0
Dn Type=3
Dn Slope=0.005
Boundary for River Rch & Prof#=Upper Dry Comal ,Reach-1,6
Up Type=0
Dn Type=3
Dn Slope=0.005
Boundary for River Rch & Prof#=Upper Dry Comal ,Reach-1,7
Up Type=0
Dn Type=3
Dn Slope=0.005

--- Upper Dry Comal Tributary 21.g01 (geometry) ---

Geom Title=Existing Conditions

River Reach=Upper Dry Comal ,Reach-1
Reach XY= 30
      2196944.31     13823694.31      2196876.33     13823565.36
      2196872.76     13823280.93      2196774.52     13823090.16
      2196777.37     13822980.53      2196822.53     13822919.43
      2196827.35     13822830.97      2196872.53     13822769.43
      2196928.83     13822526.58      2197069.46     13822327.42
      2197080.54     13822222.58      2197171.44     13822123.53
      2197191.28     13821957.86      2197426.59     13821828.83
      2197523.45     13821821.19      2197624.12     13821760.32
      2197624.32     13821488.92      2197577.36     13821419.02
      2197571.38     13821326.50      2197480.54     13821227.42
      2197467.14     13821118.83      2197327.06     13820969.15
      2197324.50     13820564.79      2197332.83     13820518.81
      2197419.46     13820427.42      2197428.63     13820326.50
      2197516.83     13820231.03      2197532.98     13820168.69
      2197576.03     13820128.14      2197625.00     13820125.00

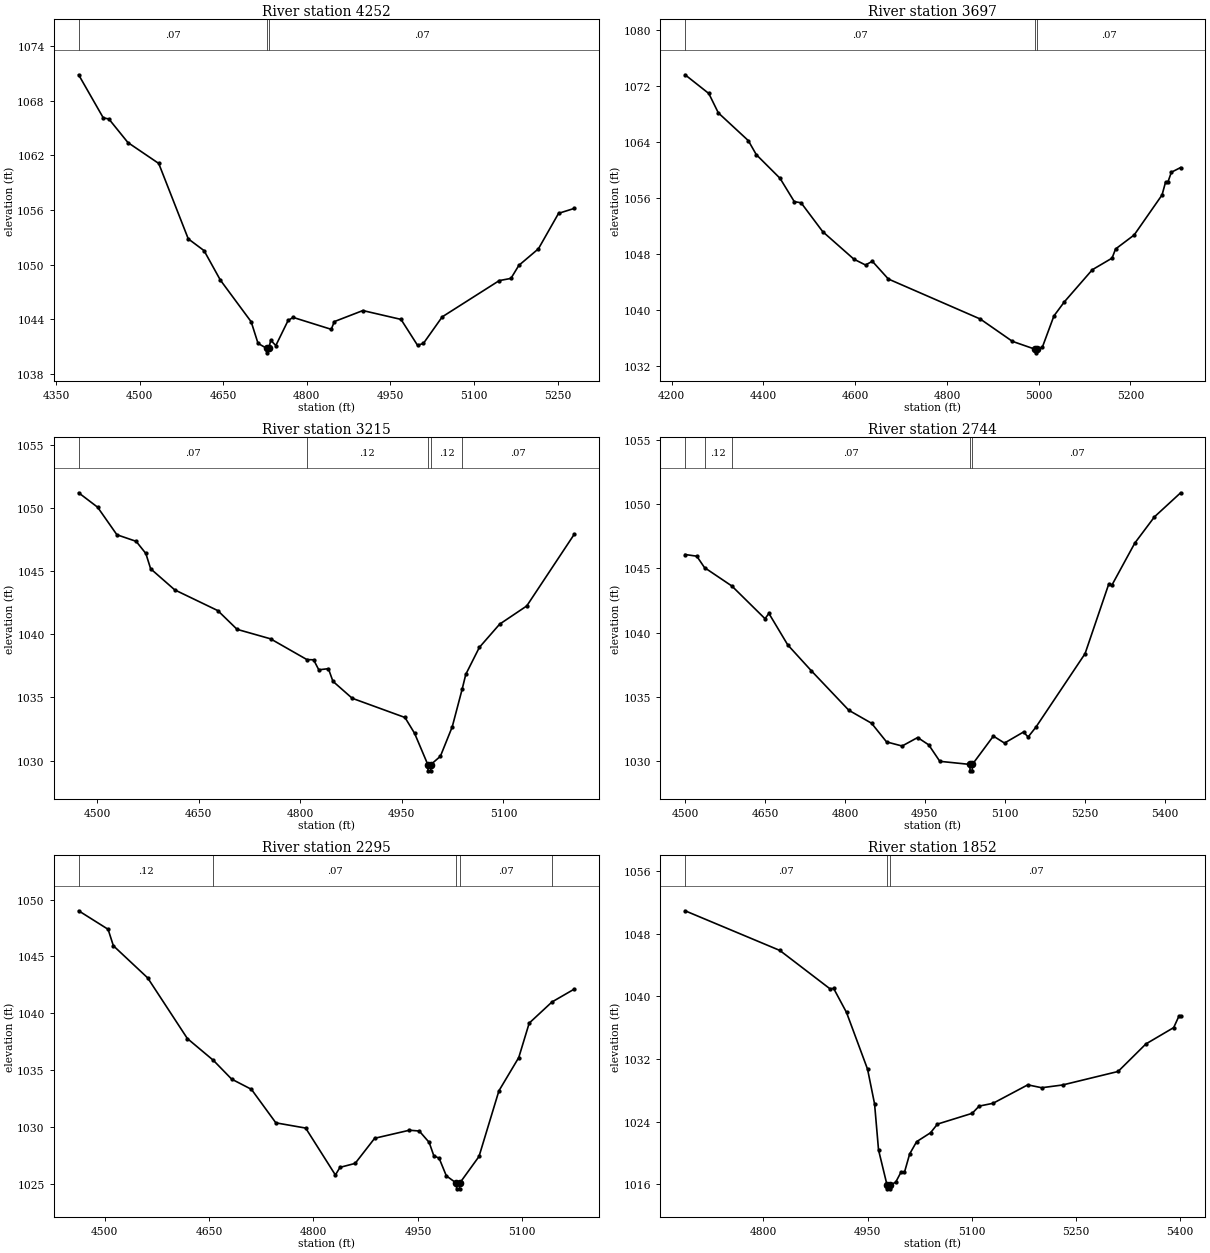
Type RM Length L Ch R = 1,4252,555,555,555
BEGIN DESCRIPTION:
Upper Dry Comal Tributary 21 9.0
END DESCRIPTION:
XS GIS Cut Line= 3
      2197474.99     13823375.00      2196870.83     13823658.85
      2196724.99     13823825.01
#Sta/Elev= 30
  4390.8 1070.83  4435.0 1066.10  4445.0 1065.98  4479.2 1063.39  4534.4 1061.10
  4587.4 1052.82  4615.7 1051.53  4644.9 1048.30  4700.2 1043.72  4712.5 1041.35
  4727.8 1040.81  4728.0 1040.31  4731.8 1040.81  4735.3 1041.69  4744.4 1041.11
  4766.4 1043.86  4775.4 1044.20  4843.8 1042.89  4849.3 1043.74  4900.5 1044.95
  4968.9 1043.98  4998.5 1041.14  5009.0 1041.34  5042.8 1044.26  5145.1 1048.24
  5166.0 1048.48  5180.2 1049.91  5215.3 1051.73  5251.4 1055.62  5279.4 1056.16
#Mann=3,-1,0
  4390.8    0.07       0  4727.8    0.05       0  4731.8    0.07       0
Bank Sta=4727.8,4731.8
Exp/Cntr=0.3,0.1

Type RM Length L Ch R = 1,3697,482,482,482
BEGIN DESCRIPTION:
Upper Dry Comal Tributary 21 8.0
END DESCRIPTION:
XS GIS Cut Line= 3
      2197525.00     13823325.00      2196775.00     13823125.00
      2196475.04     13823075.01
#Sta/Elev= 30
  4229.2 1073.59  4280.9 1070.92  4301.6 1068.16  4367.0 1064.20  4384.4 1062.20
  4436.2 1058.82  4467.2 1055.50  4482.1 1055.33  4529.3 1051.21  4597.2 1047.29
  4622.5 1046.46  4637.4 1046.99  4672.3 1044.46  4872.8 1038.75  4942.7 1035.57
  4992.8 1034.43  4993.1 1033.93  4997.3 1034.43  5007.9 1034.71  5033.3 1039.20
  5056.1 1041.21  5116.9 1045.78  5160.0 1047.44  5167.6 1048.74  5208.2 1050.74
  5269.0 1056.45  5276.6 1058.28  5281.7 1058.28  5289.3 1059.69  5309.5 1060.36
#Mann=3,-1,0
  4229.2    0.07       0  4992.8    0.05       0  4997.3    0.07       0
Bank Sta=4992.8,4997.3
Exp/Cntr=0.3,0.1

Type RM Length L Ch R = 1,3215,471,471,471
BEGIN DESCRIPTION:
Upper Dry Comal Tributary 21 7.0
END DESCRIPTION:
XS GIS Cut Line= 3
      2197274.99     13823024.99      2196875.00     13822675.00
      2196675.00     13822675.00
#Sta/Elev= 30
  4473.0 1051.19  4501.0 1050.05  4529.5 1047.87  4557.9 1047.35  4572.2 1046.39
  4579.3 1045.18  4614.9 1043.51  4678.5 1041.87  4706.9 1040.39  4756.3 1039.64
  4809.9 1038.00  4819.9 1037.98  4827.5 1037.19  4841.7 1037.28  4848.4 1036.28
  4876.8 1034.94  4954.7 1033.42  4968.9 1032.17  4988.4 1029.70  4988.8 1029.20
  4992.7 1029.20  4993.0 1029.70  5007.0 1030.35  5024.5 1032.68  5039.1 1035.65
  5044.5 1036.83  5064.5 1038.96  5094.5 1040.80  5134.5 1042.24  5204.5 1047.90
#Mann=5,-1,0
  4473.0    0.07       0  4809.9    0.12       0  4988.4    0.05       0
  4993.0    0.12       0  5039.1    0.07       0
Bank Sta=4988.4,4993
Exp/Cntr=0.3,0.1

Type RM Length L Ch R = 1,2744,449,449,449
BEGIN DESCRIPTION:
Upper Dry Comal Tributary 21 6.0
END DESCRIPTION:
XS GIS Cut Line= 3
      2197375.00     13822675.00      2197075.00     13822275.00
      2196825.01     13821925.01
#Sta/Elev= 30
  4500.0 1046.07  4521.9 1045.94  4536.5 1045.05  4587.8 1043.62  4650.0 1041.08
  4657.3 1041.49  4692.7 1039.04  4736.5 1037.05  4807.3 1033.96  4850.0 1032.95
  4878.1 1031.50  4907.3 1031.18  4936.5 1031.84  4957.3 1031.27  4978.1 1029.99
  5034.5 1029.75  5034.9 1029.25  5038.9 1029.25  5039.2 1029.75  5078.6 1031.95
  5099.5 1031.41  5135.2 1032.27  5143.8 1031.88  5158.5 1032.65  5250.7 1038.36
  5294.9 1043.74  5301.1 1043.69  5344.1 1046.96  5381.0 1049.00  5430.1 1050.87
#Mann=5,-1,0
  4500.0    0.07       0  4536.5    0.12       0  4587.8    0.07       0
  5034.5    0.05       0  5039.2    0.07       0
Bank Sta=5034.5,5039.2
Exp/Cntr=0.3,0.1

Type RM Length L Ch R = 1,2295,443,443,443
BEGIN DESCRIPTION:
Upper Dry Comal Tributary 21 5.0
END DESCRIPTION:
XS GIS Cut Line= 3
      2197675.03     13822275.02      2197275.00     13821925.00
      2197125.02     13821825.01
#Sta/Elev= 30
  4462.7 1049.02  4505.0 1047.39  4512.6 1045.94  4561.9 1043.11  4618.9 1037.77
  4656.3 1035.85  4682.5 1034.20  4710.9 1033.30  4746.0 1030.35  4788.8 1029.89
  4831.5 1025.76  4838.1 1026.43  4859.9 1026.78  4887.9 1028.99  4937.8 1029.70
  4952.0 1029.63  4966.2 1028.63  4972.9 1027.45  4980.5 1027.24  4990.9 1025.68
  5005.4 1025.04  5005.7 1024.54  5009.8 1024.54  5010.1 1025.04  5037.8 1027.39
  5066.4 1033.17  5094.9 1036.10  5109.9 1039.13  5142.6 1040.99  5174.5 1042.12
#Mann=5,-1,0
  4462.7    0.12       0  4656.3    0.07       0  5005.4    0.05       0
  5010.1    0.07       0  5142.6   0.035       0
Bank Sta=5005.4,5010.1
Exp/Cntr=0.3,0.1

Type RM Length L Ch R = 1,1852,485,485,485
BEGIN DESCRIPTION:
Upper Dry Comal Tributary 21 4.0
END DESCRIPTION:
XS GIS Cut Line= 3
      2197934.82     13821770.71      2197625.00     13821725.00
      2197224.97     13821725.00
#Sta/Elev= 30
  4687.4 1050.95  4823.7 1045.88  4896.1 1040.96  4901.2 1041.02  4919.7 1037.95
  4950.0 1030.69  4960.1 1026.25  4965.8 1020.37  4978.0 1015.89  4978.3 1015.39
  4982.4 1015.39  4982.8 1015.89  4990.5 1016.24  4998.0 1017.50  5003.1 1017.50
  5010.6 1019.85  5020.6 1021.42  5040.6 1022.56  5050.6 1023.67  5100.6 1025.05
  5110.6 1025.97  5130.6 1026.33  5180.6 1028.69  5200.6 1028.32  5230.6 1028.67
  5310.6 1030.40  5350.6 1033.92  5390.6 1036.01  5398.1 1037.47  5400.6 1037.47
#Mann=3,-1,0
  4687.4    0.07       0  4978.0    0.05       0  4982.8    0.07       0
Bank Sta=4978,4982.8
Exp/Cntr=0.3,0.1

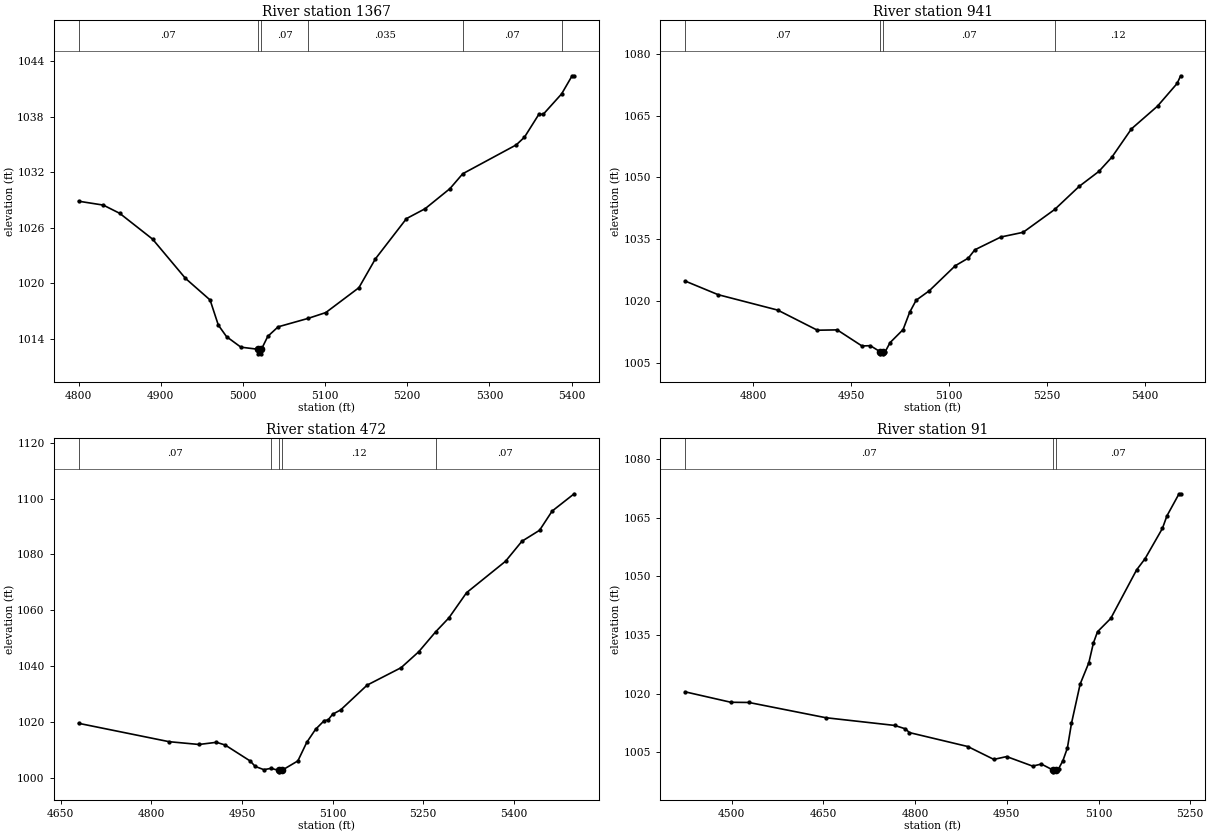
Type RM Length L Ch R = 1,1367,426,426,426
BEGIN DESCRIPTION:
Upper Dry Comal Tributary 21 3.0
END DESCRIPTION:
XS GIS Cut Line= 3
      2197724.98     13821275.00      2197525.00     13821275.00
      2197125.00     13821325.00
#Sta/Elev= 30
  4800.0 1028.88  4830.0 1028.46  4850.0 1027.57  4890.0 1024.78  4930.0 1020.54
  4960.0 1018.20  4970.0 1015.49  4980.0 1014.24  4997.5 1013.10  5017.7 1012.88
  5018.1 1012.38  5022.2 1012.38  5022.5 1012.88  5030.2 1014.27  5042.8 1015.30
  5079.2 1016.21  5100.8 1016.84  5141.1 1019.53  5161.2 1022.65  5199.0 1027.00
  5221.7 1028.07  5251.9 1030.24  5267.5 1031.85  5332.6 1034.97  5342.6 1035.80
  5360.3 1038.30  5365.3 1038.26  5387.8 1040.48  5400.6 1042.44  5403.1 1042.44
#Mann=6,-1,0
  4800.0    0.07       0  5017.7    0.05       0  5022.5    0.07       0
  5079.2   0.035       0  5267.5    0.07       0  5387.8   0.035       0
Bank Sta=5017.7,5022.5
Exp/Cntr=0.3,0.1

Type RM Length L Ch R = 1,941,469,469,469
BEGIN DESCRIPTION:
Upper Dry Comal Tributary 21 2.0
END DESCRIPTION:
XS GIS Cut Line= 3
      2197625.03     13820975.00      2197325.00     13820925.00
      2196869.59     13820914.31
#Sta/Elev= 30
  4695.4 1024.93  4746.1 1021.62  4837.4 1017.89  4898.2 1013.02  4928.6 1013.10
  4966.6 1009.20  4979.3 1009.28  4994.6 1007.80  4994.9 1007.30  4999.1 1007.30
  4999.5 1007.80  5002.1 1007.80  5009.6 1010.01  5029.6 1013.17  5039.6 1017.33
  5049.6 1020.28  5069.6 1022.55  5109.6 1028.63  5129.6 1030.48  5139.6 1032.49
  5179.6 1035.59  5213.6 1036.72  5262.0 1042.25  5299.6 1047.85  5329.7 1051.46
  5349.7 1054.92  5379.7 1061.77  5419.7 1067.28  5449.7 1072.76  5455.1 1074.62
#Mann=4,-1,0
  4695.4    0.07       0  4994.6    0.05       0  4999.5    0.07       0
  5262.0    0.12       0
Bank Sta=4994.6,4999.5
Exp/Cntr=0.3,0.1

Type RM Length L Ch R = 1,472,381,381,381
BEGIN DESCRIPTION:
Upper Dry Comal Tributary 21 1.0
END DESCRIPTION:
XS GIS Cut Line= 3
      2197625.02     13820675.02      2197375.00     13820475.00
      2196974.99     13820174.99
#Sta/Elev= 30
  4679.8 1019.52  4829.5 1012.94  4879.1 1011.94  4907.9 1012.72  4922.3 1011.75
  4964.0 1005.99  4972.0 1004.08  4986.4 1002.92  4998.5 1003.40  5011.0 1002.64
  5011.4 1002.14  5016.0 1002.64  5042.7 1006.06  5057.3 1012.67  5071.9 1017.36
  5086.4 1020.50  5092.7 1020.72  5100.0 1022.74  5113.5 1024.32  5157.3 1033.20
  5213.5 1039.44  5242.7 1045.15  5270.6 1052.26  5292.7 1057.30  5321.9 1066.31
  5386.4 1077.57  5413.5 1084.73  5442.7 1088.66  5463.5 1095.54  5500.0 1101.74
#Mann=5,-1,0
  4679.8    0.07       0  4998.5    0.12       0  5011.0    0.05       0
  5016.0    0.12       0  5270.6    0.07       0
Bank Sta=5011,5016
Exp/Cntr=0.3,0.1

Type RM Length L Ch R = 1,91,0,0,0
BEGIN DESCRIPTION:
XS7911
END DESCRIPTION:
XS GIS Cut Line= 3
      2197808.34     13820658.87      2197652.08     13820273.44
      2197386.46     13819981.77
#Sta/Elev= 30
  4423.8 1020.46  4498.7 1017.79  4528.2 1017.74  4654.1 1013.84  4766.6 1011.87
  4784.1 1011.00  4790.7 1010.04  4886.1 1006.48  4928.7 1003.19  4949.7 1003.91
  4992.2 1001.47  5006.4 1002.00  5024.9 1000.51  5025.3 1000.01  5029.9 1000.51
  5034.8 1000.86  5041.6 1002.84  5049.0 1006.10  5055.7 1012.42  5069.9 1022.46
  5084.1 1027.91  5091.5 1032.92  5098.3 1035.83  5119.9 1039.22  5162.2 1051.63
  5176.0 1054.48  5204.4 1062.23  5211.8 1065.44  5231.6 1071.08  5234.2 1071.08
#Mann=3,-1,0
  4423.8    0.07       0  5024.9    0.05       0  5029.9    0.07       0
Bank Sta=5024.9,5029.9
Exp/Cntr=0.3,0.1

Chan Stop Cuts=-1