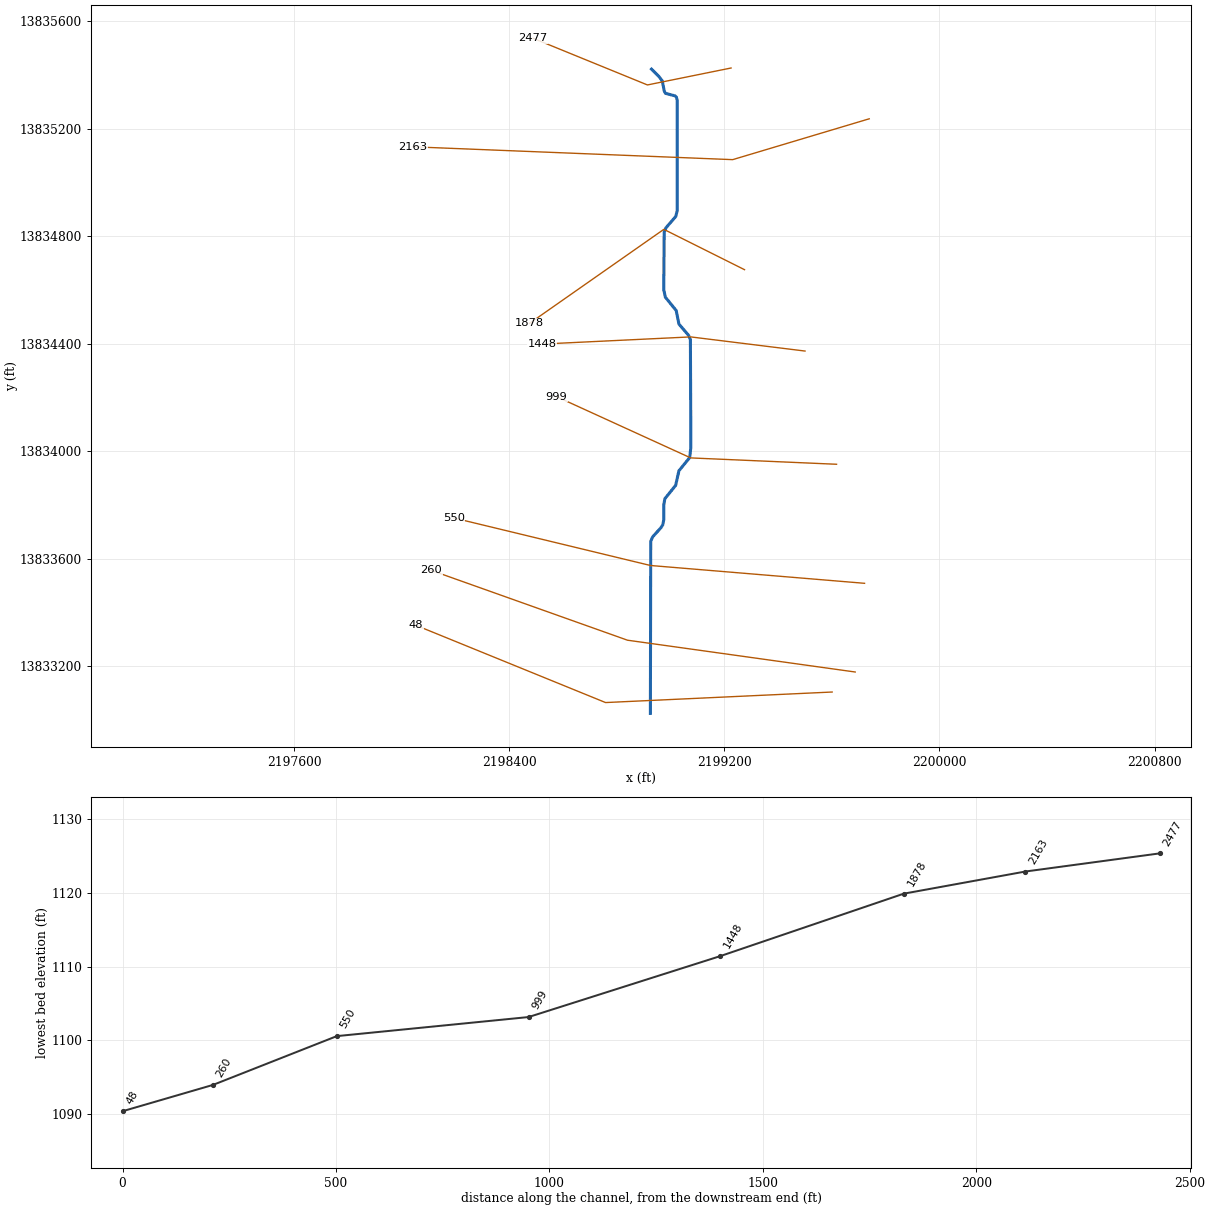
--- Upper Dry Comal Tributary 24.prj (project) ---

Proj Title=Upper Dry Comal Tributary 24 Base Level Engineering
Current Plan=p01
Default Exp/Contr=0.3,0.1
English Units
Geom File=g01
Flow File=f01
Plan File=p01
BEGIN DESCRIPTION:
Upper Dry Comal Tributary 24
END DESCRIPTION:

--- Upper Dry Comal Tributary 24.p01 (plan) ---

Plan Title=Multiple Run
Short Identifier=Multiple
Geom File=g01
Flow File=f01
Subcritical Flow
K Sum by GR= 0
Std Step Tol= 0.01
Critical Tol= 0.01
Num of Std Step Trials= 20
Max Error Tol= 0.3
Flow Tol Ratio= 0.001
Split Flow NTrial= 30
Split Flow Tol= 0.02
Split Flow Ratio= 0.02
Log Output Level= 0
Friction Slope Method= 1
Unsteady Friction Slope Method= 2
Unsteady Bridges Friction Slope Method= 1
Parabolic Critical Depth
Global Vel Dist=  1 , 1 , 1
Global Log Level= 0
CheckData=True
Encroach Param= -1, 0, 0, 0
BEGIN DESCRIPTION:
Multiple Run
END DESCRIPTION:

--- Upper Dry Comal Tributary 24.f01 (steady flow) ---

Flow Title=Multiple
Number of Profiles=7
Profile Names=10-year,25-year,50-year,1pct_min,100-year,1pct_plu,500-year
River Rch & RM= Upper Dry Comal ,Reach-1,2477
     909    1518    2088    1392    2777    5542    4861
River Rch & RM= Upper Dry Comal ,Reach-1,999
    1418    2430    3402    2305    4599    9176    8319
Boundary for River Rch & Prof#=Upper Dry Comal ,Reach-1,1
Up Type=0
Dn Type=3
Dn Slope=0.005
Boundary for River Rch & Prof#=Upper Dry Comal ,Reach-1,2
Up Type=0
Dn Type=3
Dn Slope=0.005
Boundary for River Rch & Prof#=Upper Dry Comal ,Reach-1,3
Up Type=0
Dn Type=3
Dn Slope=0.005
Boundary for River Rch & Prof#=Upper Dry Comal ,Reach-1,4
Up Type=0
Dn Type=3
Dn Slope=0.005
Boundary for River Rch & Prof#=Upper Dry Comal ,Reach-1,5
Up Type=0
Dn Type=3
Dn Slope=0.005
Boundary for River Rch & Prof#=Upper Dry Comal ,Reach-1,6
Up Type=0
Dn Type=3
Dn Slope=0.005
Boundary for River Rch & Prof#=Upper Dry Comal ,Reach-1,7
Up Type=0
Dn Type=3
Dn Slope=0.005

--- Upper Dry Comal Tributary 24.g01 (geometry) ---

Geom Title=Existing Conditions

River Reach=Upper Dry Comal ,Reach-1
Reach XY= 30
      2198929.19     13835420.81      2198956.56     13835393.69
      2198969.06     13835377.12      2198976.41     13835339.81
      2198980.90     13835330.69      2199016.85     13835321.35
      2199021.63     13835316.60      2199024.75     13835304.73
      2199024.93     13834895.03      2199019.25     13834872.67
      2198983.14     13834831.06      2198976.22     13834814.50
      2198974.79     13834599.91      2198980.71     13834572.65
      2199020.81     13834523.26      2199031.12     13834472.82
      2199066.91     13834431.08      2199073.80     13834414.50
      2199075.46     13834014.81      2199071.25     13833976.55
      2199031.12     13833927.18      2199018.89     13833872.82
      2198978.83     13833823.42      2198975.08     13833802.24
      2198974.76     13833745.10      2198971.14     13833726.60
      2198964.11     13833715.37      2198933.14     13833681.06
      2198926.22     13833664.50      2198925.00     13833025.00

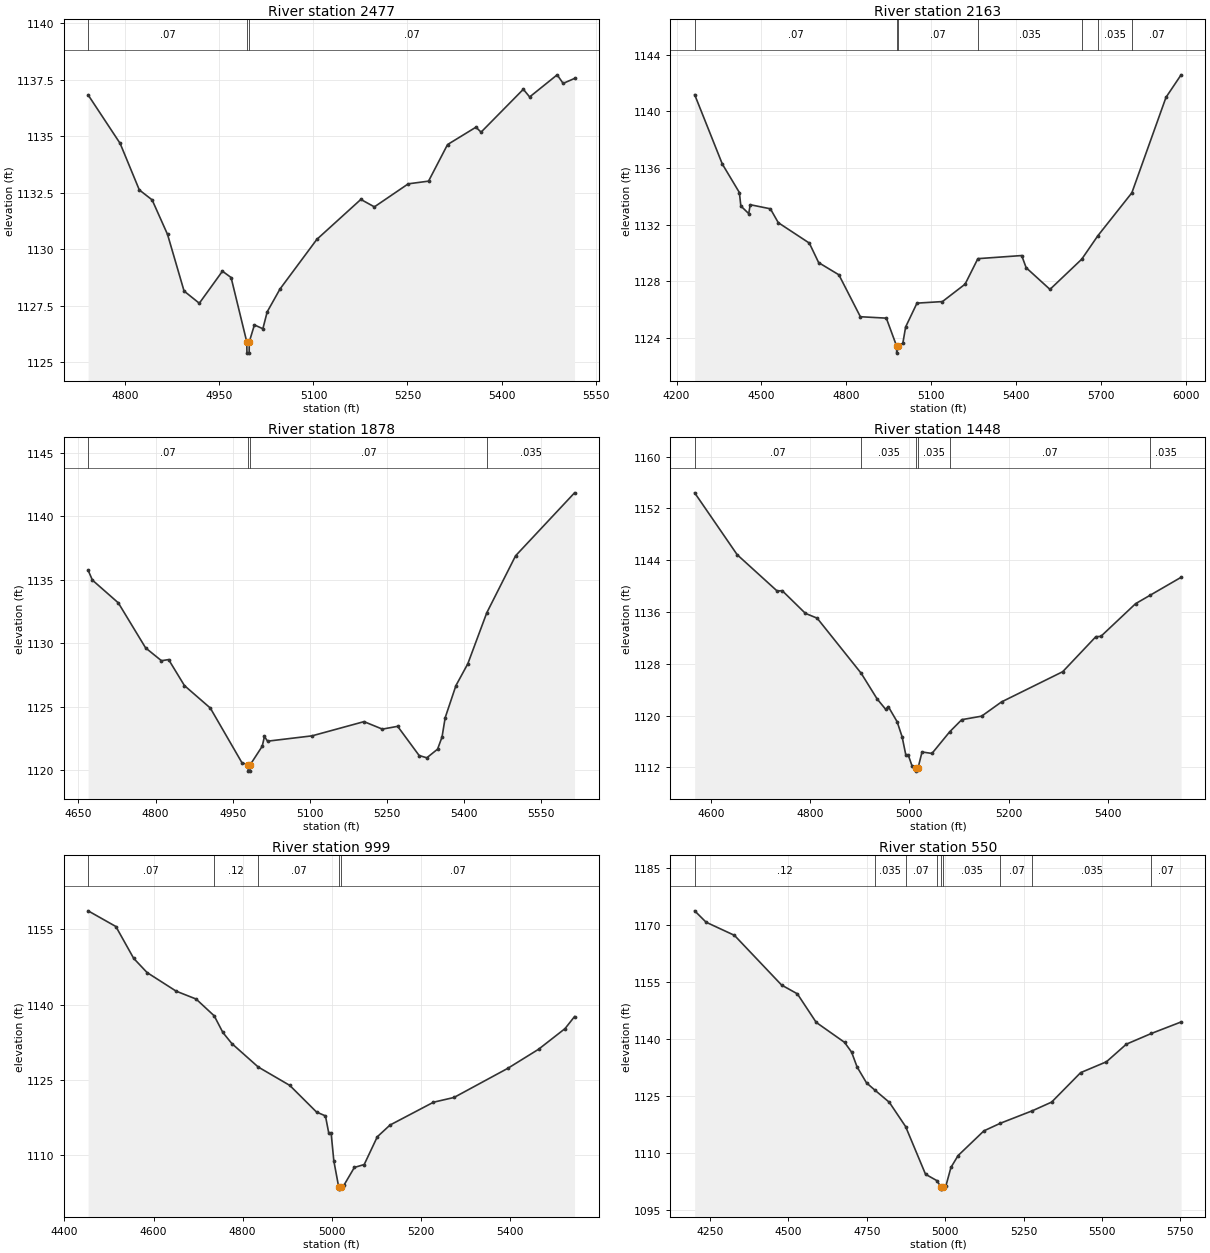
Type RM Length L Ch R = 1,2477,314,314,314
BEGIN DESCRIPTION:
Upper Dry Comal Tributary 24 5.0
END DESCRIPTION:
XS GIS Cut Line= 3
      2199225.04     13835425.01      2198914.06     13835361.98
      2198489.37     13835535.32
#Sta/Elev= 30
  4740.5 1136.83  4791.6 1134.68  4822.2 1132.62  4842.6 1132.18  4867.2 1130.65
  4893.6 1128.14  4917.9 1127.60  4954.8 1129.02  4968.6 1128.74  4993.6 1125.89
  4993.9 1125.39  4997.4 1125.39  4997.6 1125.89  5005.8 1126.64  5019.3 1126.47
  5026.2 1127.22  5046.6 1128.23  5105.4 1130.43  5175.6 1132.20  5197.2 1131.87
  5251.2 1132.89  5283.6 1133.01  5313.9 1134.63  5359.2 1135.40  5367.4 1135.18
  5434.8 1137.08  5444.9 1136.74  5488.8 1137.72  5498.3 1137.34  5516.5 1137.56
#Mann=3,-1,0
  4740.5    0.07       0  4993.6    0.05       0  4997.6    0.07       0
Bank Sta=4993.6,4997.6
Exp/Cntr=0.3,0.1

Type RM Length L Ch R = 1,2163,285,285,285
BEGIN DESCRIPTION:
XS7913
END DESCRIPTION:
XS GIS Cut Line= 3
      2199738.72     13835236.11      2199230.90     13835084.20
      2198041.71     13835131.94
#Sta/Elev= 30
  4263.9 1141.18  4361.7 1136.28  4422.0 1134.27  4427.2 1133.32  4455.1 1132.78
  4460.3 1133.41  4531.7 1133.12  4559.6 1132.14  4669.3 1130.70  4702.4 1129.32
  4773.9 1128.46  4849.9 1125.50  4941.7 1125.40  4978.0 1123.43  4978.3 1122.93
  4982.0 1123.43  5000.0 1123.62  5010.0 1124.78  5050.1 1126.46  5140.1 1126.57
  5220.2 1127.80  5265.4 1129.60  5420.4 1129.82  5436.2 1128.96  5520.4 1127.43
  5632.6 1129.56  5689.8 1131.22  5810.0 1134.25  5930.7 1140.99  5984.1 1142.58
#Mann=7,-1,0
  4263.9    0.07       0  4978.0    0.05       0  4982.0    0.07       0
  5265.4   0.035       0  5632.6    0.07       0  5689.8   0.035       0
  5810.0    0.07       0
Bank Sta=4978,4982
Exp/Cntr=0.3,0.1

Type RM Length L Ch R = 1,1878,430,430,430
BEGIN DESCRIPTION:
Upper Dry Comal Tributary 24 4.0
END DESCRIPTION:
XS GIS Cut Line= 3
      2199275.01     13834675.00      2198975.00     13834825.00
      2198475.04     13834475.03
#Sta/Elev= 30
  4668.7 1135.75  4677.1 1134.97  4727.4 1133.18  4780.5 1129.63  4811.3 1128.62
  4825.2 1128.71  4856.0 1126.66  4906.3 1124.89  4967.8 1120.58  4979.8 1120.42
  4980.0 1119.92  4983.5 1119.92  4983.8 1120.42  5007.2 1121.88  5011.5 1122.65
  5017.6 1122.28  5104.0 1122.70  5205.1 1123.82  5240.8 1123.23  5270.5 1123.45
  5312.3 1121.15  5327.2 1120.97  5348.1 1121.65  5356.8 1122.61  5362.9 1124.13
  5383.8 1126.66  5406.9 1128.38  5443.8 1132.40  5499.8 1136.89  5614.4 1141.85
#Mann=4,-1,0
  4668.7    0.07       0  4979.8    0.05       0  4983.8    0.07       0
  5443.8   0.035       0
Bank Sta=4979.8,4983.8
Exp/Cntr=0.3,0.1

Type RM Length L Ch R = 1,1448,449,449,449
BEGIN DESCRIPTION:
Upper Dry Comal Tributary 24 3.0
END DESCRIPTION:
XS GIS Cut Line= 3
      2199500.03     13834372.39      2199075.00     13834425.00
      2198523.41     13834398.44
#Sta/Elev= 30
  4567.3 1154.42  4653.0 1144.86  4733.6 1139.25  4743.7 1139.31  4790.5 1135.80
  4814.2 1135.06  4903.0 1126.54  4935.1 1122.58  4952.5 1120.96  4957.6 1121.40
  4975.4 1119.06  4985.5 1116.72  4993.1 1113.86  4998.1 1113.86  5005.6 1112.20
  5013.6 1111.93  5013.8 1111.43  5017.6 1111.93  5025.6 1114.39  5045.6 1114.16
  5081.3 1117.50  5105.7 1119.38  5145.7 1119.92  5185.8 1122.12  5309.2 1126.79
  5376.0 1132.20  5386.0 1132.24  5456.1 1137.30  5485.4 1138.60  5547.8 1141.37
#Mann=6,-1,0
  4567.3    0.07       0  4903.0   0.035       0  5013.6   0.035       0
  5017.6   0.035       0  5081.3    0.07       0  5485.4   0.035       0
Bank Sta=5013.6,5017.6
Exp/Cntr=0.3,0.1

Type RM Length L Ch R = 1,999,449,449,449
BEGIN DESCRIPTION:
Upper Dry Comal Tributary 24 2.0
END DESCRIPTION:
XS GIS Cut Line= 3
      2199617.22     13833951.39      2199075.00     13833975.00
      2198575.56     13834203.11
#Sta/Elev= 30
  4453.2 1158.71  4515.5 1155.58  4555.5 1149.22  4585.5 1146.39  4650.9 1142.67
  4695.6 1141.10  4736.3 1137.74  4755.7 1134.42  4775.7 1132.22  4835.0 1127.53
  4905.8 1123.86  4965.9 1118.54  4985.9 1117.77  4993.4 1114.31  4998.7 1114.31
  5004.7 1108.80  5015.5 1103.65  5015.8 1103.15  5020.4 1103.65  5027.7 1103.97
  5050.8 1107.48  5072.9 1108.06  5102.3 1113.60  5130.8 1115.94  5228.4 1120.50
  5274.5 1121.45  5395.1 1127.26  5464.2 1131.07  5523.6 1135.19  5545.0 1137.60
#Mann=5,-1,0
  4453.2    0.07       0  4736.3    0.12       0  4835.0    0.07       0
  5015.5    0.05       0  5020.4    0.07       0
Bank Sta=5015.5,5020.4
Exp/Cntr=0.3,0.1

Type RM Length L Ch R = 1,550,290,290,290
BEGIN DESCRIPTION:
Upper Dry Comal Tributary 24 1.0
END DESCRIPTION:
XS GIS Cut Line= 3
      2199721.35     13833508.68      2198925.00     13833575.00
      2198193.55     13833751.74
#Sta/Elev= 30
  4200.8 1173.83  4237.3 1170.83  4327.6 1167.38  4478.1 1154.29  4528.3 1151.98
  4588.5 1144.46  4678.8 1139.21  4701.3 1136.64  4718.9 1132.72  4749.0 1128.53
  4774.5 1126.71  4821.7 1123.42  4873.6 1117.04  4937.2 1104.48  4972.7 1102.83
  4987.4 1101.06  4987.8 1100.56  4992.4 1101.06  5002.5 1101.51  5018.3 1106.28
  5041.1 1109.40  5123.4 1115.90  5176.1 1117.91  5278.2 1121.20  5339.4 1123.47
  5432.0 1131.23  5514.3 1134.09  5577.9 1138.73  5657.8 1141.55  5752.4 1144.57
#Mann=9,-1,0
  4200.8    0.12       0  4774.5   0.035       0  4873.6    0.07       0
  4972.7   0.035       0  4987.4   0.035       0  4992.4   0.035       0
  5176.1    0.07       0  5278.2   0.035       0  5657.8    0.07       0
Bank Sta=4987.4,4992.4
Exp/Cntr=0.3,0.1

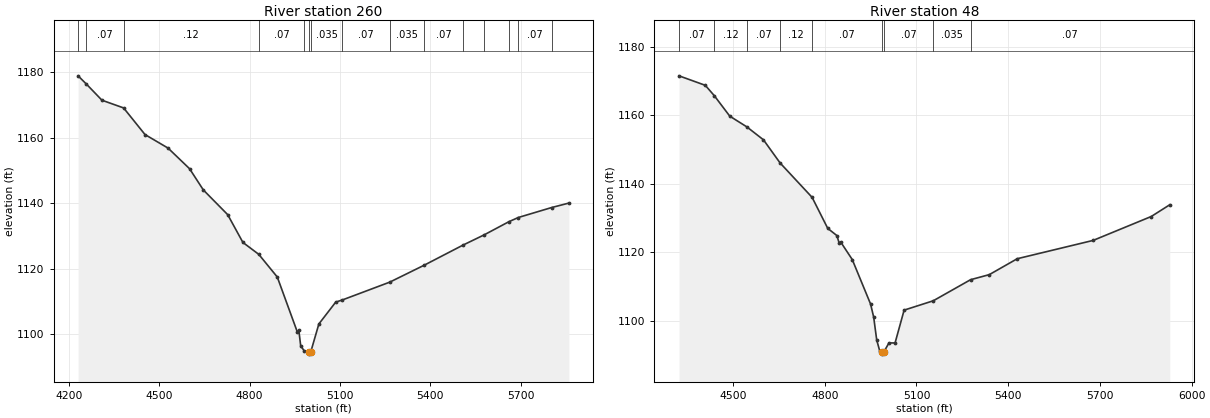
Type RM Length L Ch R = 1,260,212,212,212
BEGIN DESCRIPTION:
XS7912
END DESCRIPTION:
XS GIS Cut Line= 3
      2199686.60     13833178.82      2198839.98     13833297.09
      2198111.08     13833556.43
#Sta/Elev= 30
  4231.0 1178.87  4258.5 1176.36  4310.1 1171.43  4382.1 1169.07  4453.0 1160.95
  4529.6 1156.81  4601.0 1150.51  4646.6 1144.04  4727.4 1136.50  4777.9 1128.02
  4830.5 1124.39  4892.0 1117.46  4958.4 1100.71  4963.5 1101.17  4969.7 1096.44
  4981.4 1094.93  4997.5 1094.43  4997.9 1093.93  5002.5 1094.43  5029.9 1103.13
  5085.8 1109.80  5107.7 1110.46  5265.1 1115.90  5379.4 1121.07  5508.3 1127.21
  5578.4 1130.33  5660.1 1134.33  5691.7 1135.63  5802.2 1138.67  5859.5 1140.03
#Mann=15,-1,0
  4231.0    0.12       0  4258.5    0.07       0  4382.1    0.12       0
  4830.5    0.07       0  4981.4   0.035       0  4997.5   0.035       0
  5002.5   0.035       0  5107.7    0.07       0  5265.1   0.035       0
  5379.4    0.07       0  5508.3   0.035       0  5578.4    0.07       0
  5660.1   0.035       0  5691.7    0.07       0  5802.2   0.035       0
Bank Sta=4997.5,5002.5
Exp/Cntr=0.3,0.1

Type RM Length L Ch R = 1,48,0,0,0
BEGIN DESCRIPTION:
H21523
END DESCRIPTION:
XS GIS Cut Line= 3
      2199600.87     13833104.41      2198758.34     13833065.23
      2198052.97     13833352.60
#Sta/Elev= 30
  4323.4 1171.50  4409.4 1168.73  4438.8 1165.71  4489.4 1159.74  4545.0 1156.63
  4599.6 1152.84  4654.1 1146.08  4758.7 1136.06  4809.8 1127.02  4839.8 1124.91
  4846.9 1122.80  4851.9 1123.08  4889.9 1117.94  4949.9 1104.96  4960.0 1101.16
  4970.0 1094.46  4980.0 1091.23  4987.5 1090.85  4987.8 1090.35  4992.5 1090.85
  5010.0 1093.62  5030.0 1093.61  5059.6 1103.18  5154.8 1105.90  5276.9 1112.05
  5338.2 1113.53  5429.6 1118.17  5677.8 1123.51  5867.8 1130.48  5928.5 1133.91
#Mann=9,-1,0
  4323.4    0.07       0  4438.8    0.12       0  4545.0    0.07       0
  4654.1    0.12       0  4758.7    0.07       0  4987.5    0.05       0
  4992.5    0.07       0  5154.8   0.035       0  5276.9    0.07       0
Bank Sta=4987.5,4992.5
Exp/Cntr=0.3,0.1

Chan Stop Cuts=-1