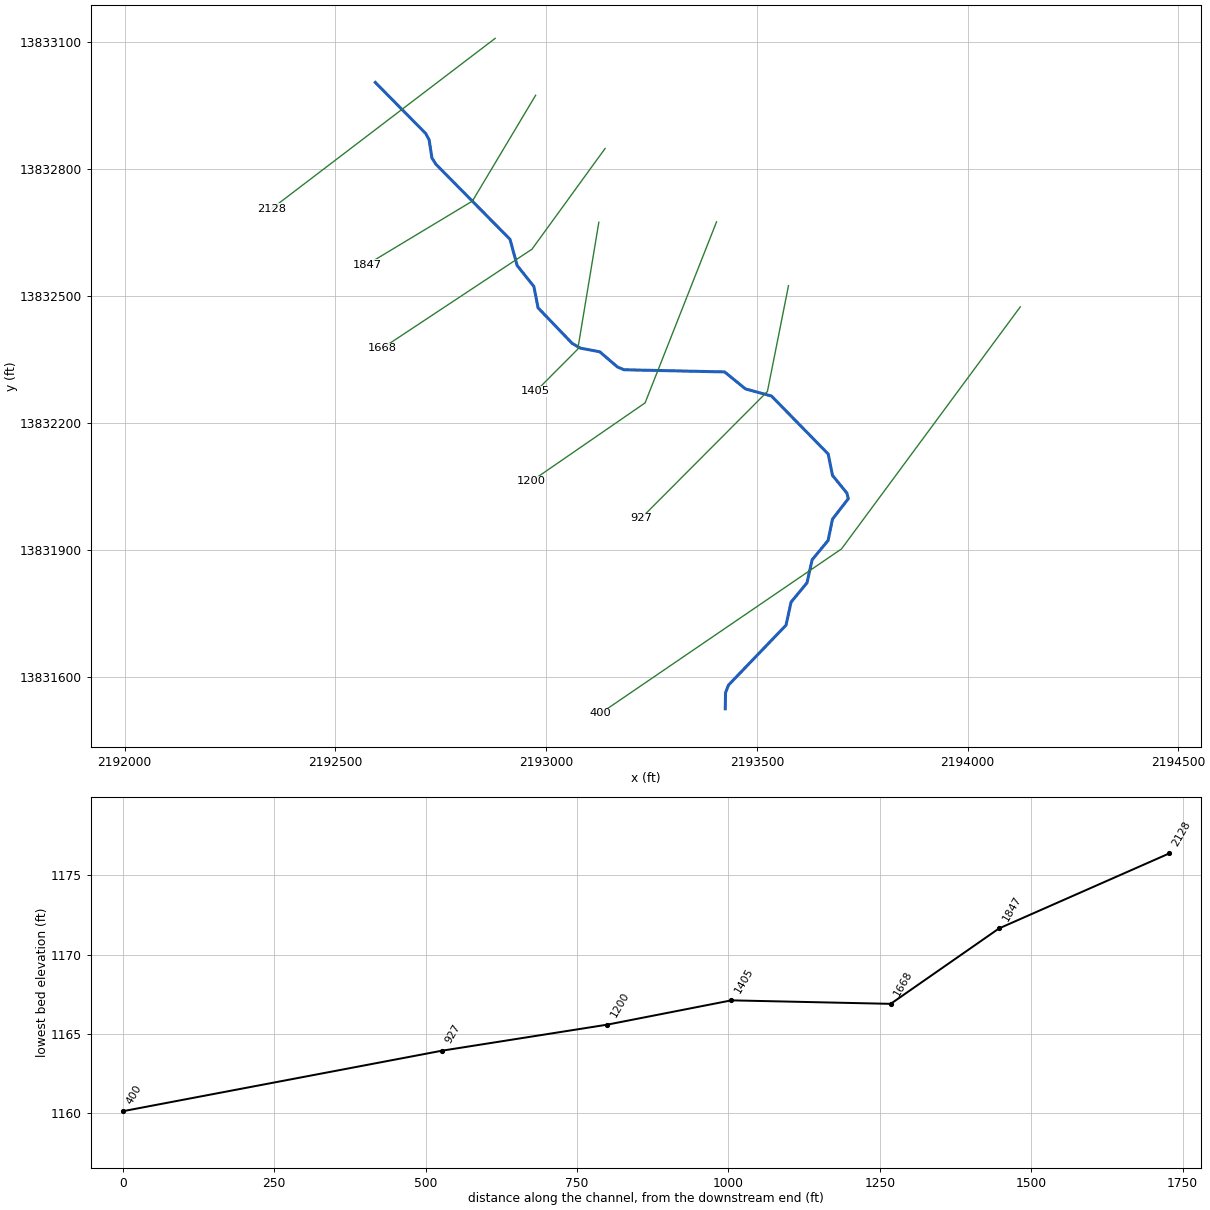
--- Upper Dry Comal Tributary 26.prj (project) ---

Proj Title=Upper Dry Comal Tributary 26 Base Level Engineering
Current Plan=p01
Default Exp/Contr=0.3,0.1
English Units
Geom File=g01
Flow File=f01
Plan File=p01
BEGIN DESCRIPTION:
Upper Dry Comal Tributary 26
END DESCRIPTION:

--- Upper Dry Comal Tributary 26.p01 (plan) ---

Plan Title=Multiple Run
Short Identifier=Multiple
Geom File=g01
Flow File=f01
Subcritical Flow
K Sum by GR= 0
Std Step Tol= 0.01
Critical Tol= 0.01
Num of Std Step Trials= 20
Max Error Tol= 0.3
Flow Tol Ratio= 0.001
Split Flow NTrial= 30
Split Flow Tol= 0.02
Split Flow Ratio= 0.02
Log Output Level= 0
Friction Slope Method= 1
Unsteady Friction Slope Method= 2
Unsteady Bridges Friction Slope Method= 1
Parabolic Critical Depth
Global Vel Dist=  1 , 1 , 1
Global Log Level= 0
CheckData=True
Encroach Param= -1, 0, 0, 0
BEGIN DESCRIPTION:
Multiple Run
END DESCRIPTION:

--- Upper Dry Comal Tributary 26.f01 (steady flow) ---

Flow Title=Multiple
Number of Profiles=7
Profile Names=10-year,25-year,50-year,1pct_min,100-year,1pct_plu,500-year
River Rch & RM= Upper Dry Comal ,Reach-1,2128
     694    1142    1556    1029    2053    4096    3532
Boundary for River Rch & Prof#=Upper Dry Comal ,Reach-1,1
Up Type=0
Dn Type=3
Dn Slope=0.005
Boundary for River Rch & Prof#=Upper Dry Comal ,Reach-1,2
Up Type=0
Dn Type=3
Dn Slope=0.005
Boundary for River Rch & Prof#=Upper Dry Comal ,Reach-1,3
Up Type=0
Dn Type=3
Dn Slope=0.005
Boundary for River Rch & Prof#=Upper Dry Comal ,Reach-1,4
Up Type=0
Dn Type=3
Dn Slope=0.005
Boundary for River Rch & Prof#=Upper Dry Comal ,Reach-1,5
Up Type=0
Dn Type=3
Dn Slope=0.005
Boundary for River Rch & Prof#=Upper Dry Comal ,Reach-1,6
Up Type=0
Dn Type=3
Dn Slope=0.005
Boundary for River Rch & Prof#=Upper Dry Comal ,Reach-1,7
Up Type=0
Dn Type=3
Dn Slope=0.005

--- Upper Dry Comal Tributary 26.g01 (geometry) ---

Geom Title=Existing Conditions

River Reach=Upper Dry Comal ,Reach-1
Reach XY= 30
      2192594.60     13833005.40      2192714.24     13832884.68
      2192722.36     13832869.36      2192728.97     13832826.65
      2192738.63     13832811.79      2192914.24     13832634.68
      2192931.10     13832572.81      2192970.81     13832523.26
      2192980.83     13832472.69      2193061.76     13832388.61
      2193081.02     13832377.49      2193127.17     13832368.86
      2193168.92     13832333.09      2193184.65     13832326.36
      2193423.45     13832321.25      2193472.83     13832281.14
      2193534.68     13832264.24      2193669.19     13832127.29
      2193679.46     13832076.65      2193713.60     13832034.92
      2193716.98     13832021.69      2193679.43     13831973.36
      2193668.95     13831922.81      2193631.08     13831877.20
      2193618.92     13831822.80      2193581.10     13831777.19
      2193569.17     13831722.70      2193432.76     13831581.21
      2193425.59     13831563.16      2193425.00     13831525.00

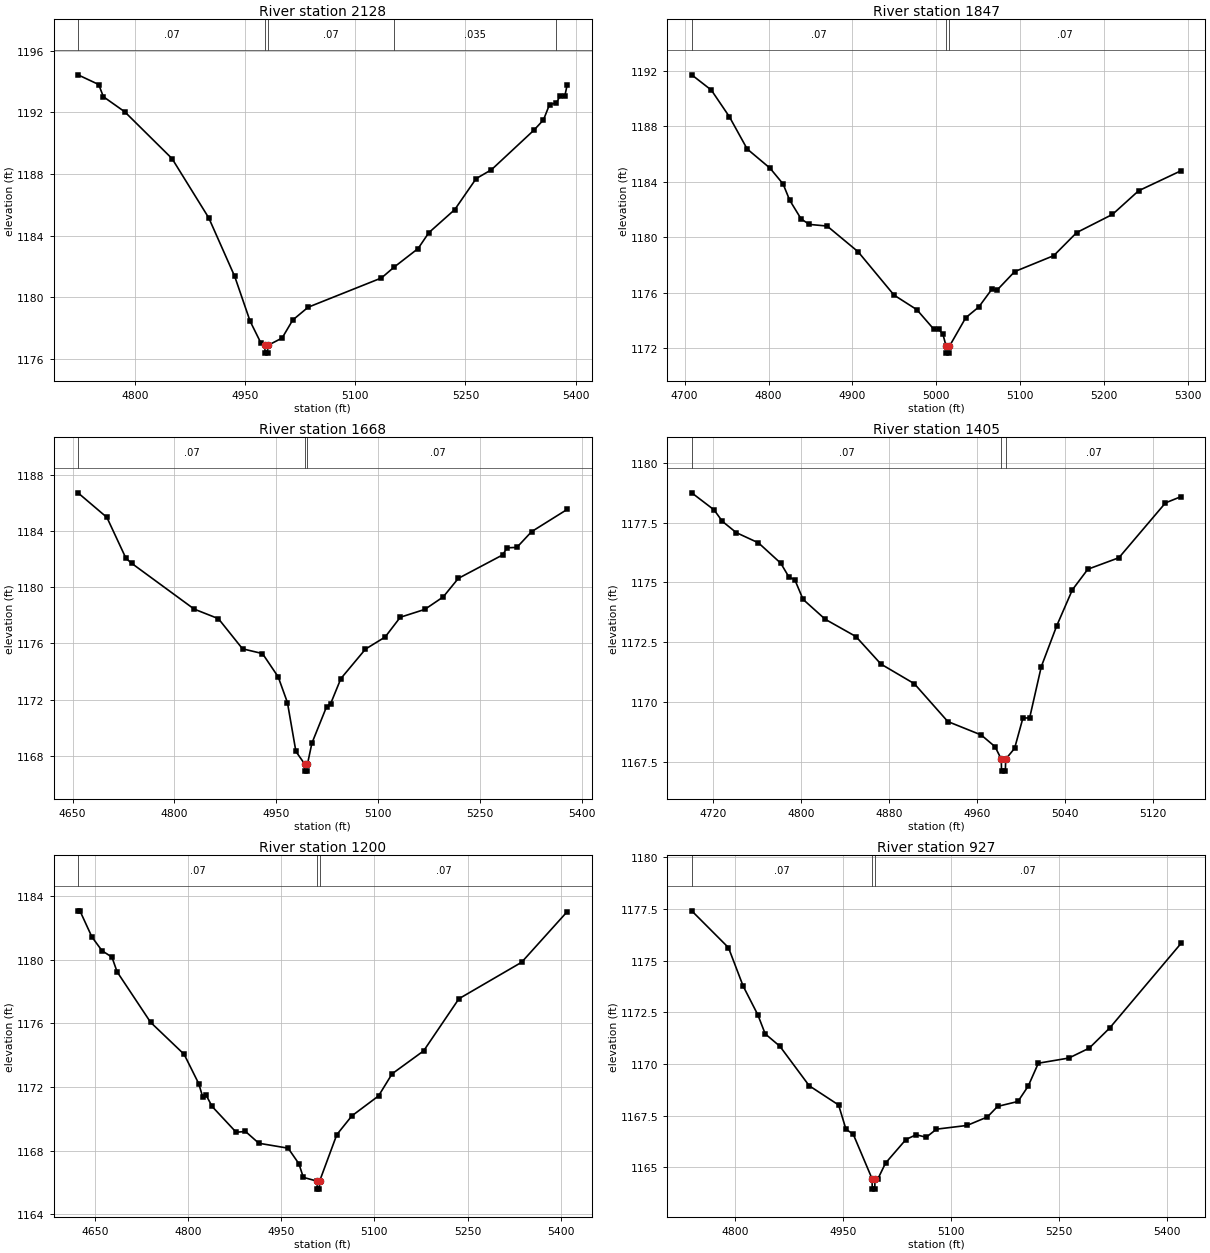
Type RM Length L Ch R = 1,2128,281,281,281
BEGIN DESCRIPTION:
XS7914
END DESCRIPTION:
XS GIS Cut Line= 2
      2192879.11     13833109.61      2192348.73     13832706.96
#Sta/Elev= 30
  4722.7 1194.44  4750.9 1193.81  4757.2 1193.02  4786.3 1192.04  4850.7 1189.00
  4900.7 1185.15  4936.0 1181.35  4956.9 1178.45  4971.4 1177.05  4977.0 1176.87
  4977.2 1176.37  4980.7 1176.37  4981.0 1176.87  5000.5 1177.35  5015.0 1178.52
  5035.9 1179.35  5135.7 1181.25  5152.6 1181.94  5185.6 1183.16  5200.2 1184.19
  5235.5 1185.69  5264.6 1187.70  5285.5 1188.28  5343.1 1190.84  5356.2 1191.51
  5364.5 1192.51  5373.8 1192.61  5379.0 1193.09  5385.3 1193.06  5388.6 1193.81
#Mann=5,-1,0
  4722.7    0.07       0  4977.0    0.05       0  4981.0    0.07       0
  5152.6   0.035       0  5373.8    0.07       0
Bank Sta=4977,4981
Exp/Cntr=0.3,0.1

Type RM Length L Ch R = 1,1847,179,179,179
BEGIN DESCRIPTION:
Upper Dry Comal Tributary 26 4.0
END DESCRIPTION:
XS GIS Cut Line= 3
      2192975.03     13832975.04      2192825.00     13832725.00
      2192575.04     13832575.02
#Sta/Elev= 30
  4708.4 1191.69  4731.8 1190.59  4753.2 1188.68  4774.5 1186.35  4801.7 1184.97
  4817.3 1183.83  4825.1 1182.67  4838.7 1181.32  4848.4 1180.92  4869.8 1180.80
  4906.7 1178.95  4949.5 1175.83  4976.7 1174.78  4997.1 1173.36  5002.9 1173.36
  5007.8 1173.01  5011.6 1172.15  5011.9 1171.65  5015.4 1171.65  5015.6 1172.15
  5035.0 1174.20  5050.5 1174.97  5066.1 1176.25  5071.9 1176.16  5093.3 1177.52
  5139.9 1178.67  5167.2 1180.33  5209.9 1181.64  5241.0 1183.34  5291.5 1184.78
#Mann=3,-1,0
  4708.4    0.07       0  5011.6    0.05       0  5015.6    0.07       0
Bank Sta=5011.6,5015.6
Exp/Cntr=0.3,0.1

Type RM Length L Ch R = 1,1668,263,263,263
BEGIN DESCRIPTION:
H21525
END DESCRIPTION:
XS GIS Cut Line= 3
      2193139.90     13832849.37      2192966.37     13832611.27
      2192611.20     13832377.18
#Sta/Elev= 30
  4658.0 1186.74  4700.5 1184.99  4728.6 1182.07  4737.1 1181.71  4829.0 1178.45
  4864.6 1177.77  4900.1 1175.62  4929.5 1175.28  4952.6 1173.62  4966.2 1171.79
  4978.7 1168.30  4991.7 1167.40  4992.0 1166.90  4995.5 1166.90  4995.7 1167.40
  5002.2 1168.89  5023.9 1171.50  5029.9 1171.72  5044.9 1173.50  5081.1 1175.60
  5110.0 1176.46  5132.3 1177.87  5168.4 1178.43  5195.5 1179.32  5217.7 1180.64
  5282.8 1182.31  5289.6 1182.82  5303.9 1182.85  5325.5 1183.97  5378.0 1185.56
#Mann=3,-1,0
  4658.0    0.07       0  4991.7    0.05       0  4995.7    0.07       0
Bank Sta=4991.7,4995.7
Exp/Cntr=0.3,0.1

Type RM Length L Ch R = 1,1405,205,205,205
BEGIN DESCRIPTION:
Upper Dry Comal Tributary 26 3.0
END DESCRIPTION:
XS GIS Cut Line= 3
      2193125.00     13832674.99      2193075.00     13832375.00
      2192975.03     13832275.03
#Sta/Elev= 30
  4700.3 1178.74  4720.6 1178.03  4728.2 1177.55  4740.8 1177.08  4761.1 1176.65
  4781.4 1175.80  4789.0 1175.21  4794.1 1175.12  4801.7 1174.29  4821.9 1173.46
  4849.8 1172.74  4872.6 1171.59  4903.0 1170.77  4933.5 1169.19  4963.9 1168.63
  4976.5 1168.14  4982.2 1167.62  4982.4 1167.12  4985.9 1167.12  4986.2 1167.62
  4994.3 1168.07  5001.9 1169.34  5008.0 1169.34  5018.6 1171.48  5032.7 1173.19
  5046.9 1174.69  5061.0 1175.55  5089.3 1176.03  5131.7 1178.32  5145.8 1178.58
#Mann=3,-1,0
  4700.3    0.07       0  4982.2    0.05       0  4986.2    0.07       0
Bank Sta=4982.2,4986.2
Exp/Cntr=0.3,0.1

Type RM Length L Ch R = 1,1200,273,273,273
BEGIN DESCRIPTION:
H21524
END DESCRIPTION:
XS GIS Cut Line= 3
      2193404.25     13832675.85      2193234.75     13832248.05
      2192964.39     13832062.43
#Sta/Elev= 30
  4622.5 1183.06  4625.6 1183.06  4644.9 1181.42  4661.1 1180.56  4677.2 1180.15
  4685.5 1179.23  4739.5 1176.06  4793.5 1174.05  4817.0 1172.21  4823.2 1171.40
  4828.6 1171.51  4838.5 1170.78  4877.3 1169.16  4892.3 1169.21  4913.8 1168.47
  4961.0 1168.16  4978.4 1167.18  4985.4 1166.33  5007.7 1166.09  5007.9 1165.59
  5011.4 1165.59  5011.7 1166.09  5039.4 1169.01  5063.7 1170.19  5106.6 1171.44
  5128.5 1172.83  5179.3 1174.27  5236.1 1177.54  5337.1 1179.83  5410.6 1183.01
#Mann=3,-1,0
  4622.5    0.07       0  5007.7    0.05       0  5011.7    0.07       0
Bank Sta=5007.7,5011.7
Exp/Cntr=0.3,0.1

Type RM Length L Ch R = 1,927,527,527,527
BEGIN DESCRIPTION:
Upper Dry Comal Tributary 26 2.0
END DESCRIPTION:
XS GIS Cut Line= 3
      2193575.00     13832524.98      2193525.00     13832275.00
      2193225.00     13831975.00
#Sta/Elev= 30
  4740.3 1177.41  4791.3 1175.63  4811.7 1173.77  4832.1 1172.38  4842.3 1171.46
  4862.7 1170.86  4903.4 1168.95  4944.2 1168.02  4954.4 1166.85  4964.6 1166.60
  4990.7 1164.45  4990.9 1163.95  4994.4 1163.95  4994.7 1164.45  4998.8 1164.45
  5009.4 1165.21  5037.7 1166.35  5051.8 1166.58  5065.9 1166.46  5080.1 1166.85
  5122.5 1167.03  5150.8 1167.44  5164.9 1167.95  5193.2 1168.19  5207.4 1168.93
  5221.5 1170.04  5263.9 1170.29  5292.2 1170.77  5320.5 1171.74  5419.5 1175.83
#Mann=3,-1,0
  4740.3    0.07       0  4990.7    0.05       0  4994.7    0.07       0
Bank Sta=4990.7,4994.7
Exp/Cntr=0.3,0.1

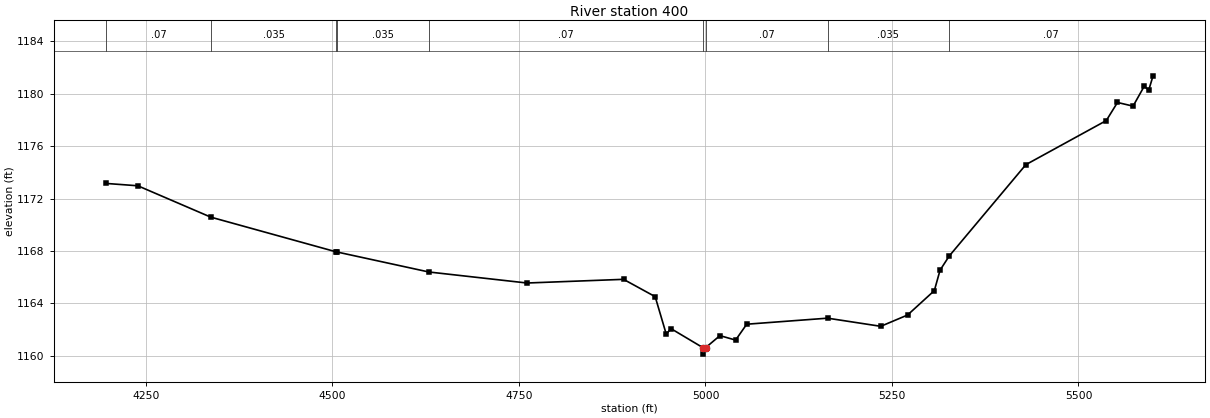
Type RM Length L Ch R = 1,400,0,0,0
BEGIN DESCRIPTION:
Upper Dry Comal Tributary 26 1.0
END DESCRIPTION:
XS GIS Cut Line= 3
      2194125.02     13832475.02      2193700.88     13831902.99
      2193128.88     13831514.27
#Sta/Elev= 30
  4196.3 1173.15  4239.1 1172.97  4336.9 1170.58  4505.3 1167.93  4505.6 1167.93
  4629.2 1166.40  4760.8 1165.56  4890.2 1165.84  4932.6 1164.52  4947.5 1161.65
  4953.6 1162.09  4996.4 1160.64  4996.7 1160.14  5000.4 1160.64  5019.4 1161.55
  5040.4 1161.21  5055.3 1162.42  5163.7 1162.88  5235.0 1162.26  5270.9 1163.12
  5306.8 1164.98  5314.5 1166.54  5326.8 1167.62  5429.5 1174.58  5537.3 1177.94
  5552.3 1179.32  5573.2 1179.04  5588.2 1180.56  5594.2 1180.26  5600.0 1181.35
#Mann=9,-1,0
  4196.3    0.07       0  4336.9   0.035       0  4505.3    0.07       0
  4505.6   0.035       0  4629.2    0.07       0  4996.4    0.05       0
  5000.4    0.07       0  5163.7   0.035       0  5326.8    0.07       0
Bank Sta=4996.4,5000.4
Exp/Cntr=0.3,0.1

Chan Stop Cuts=-1