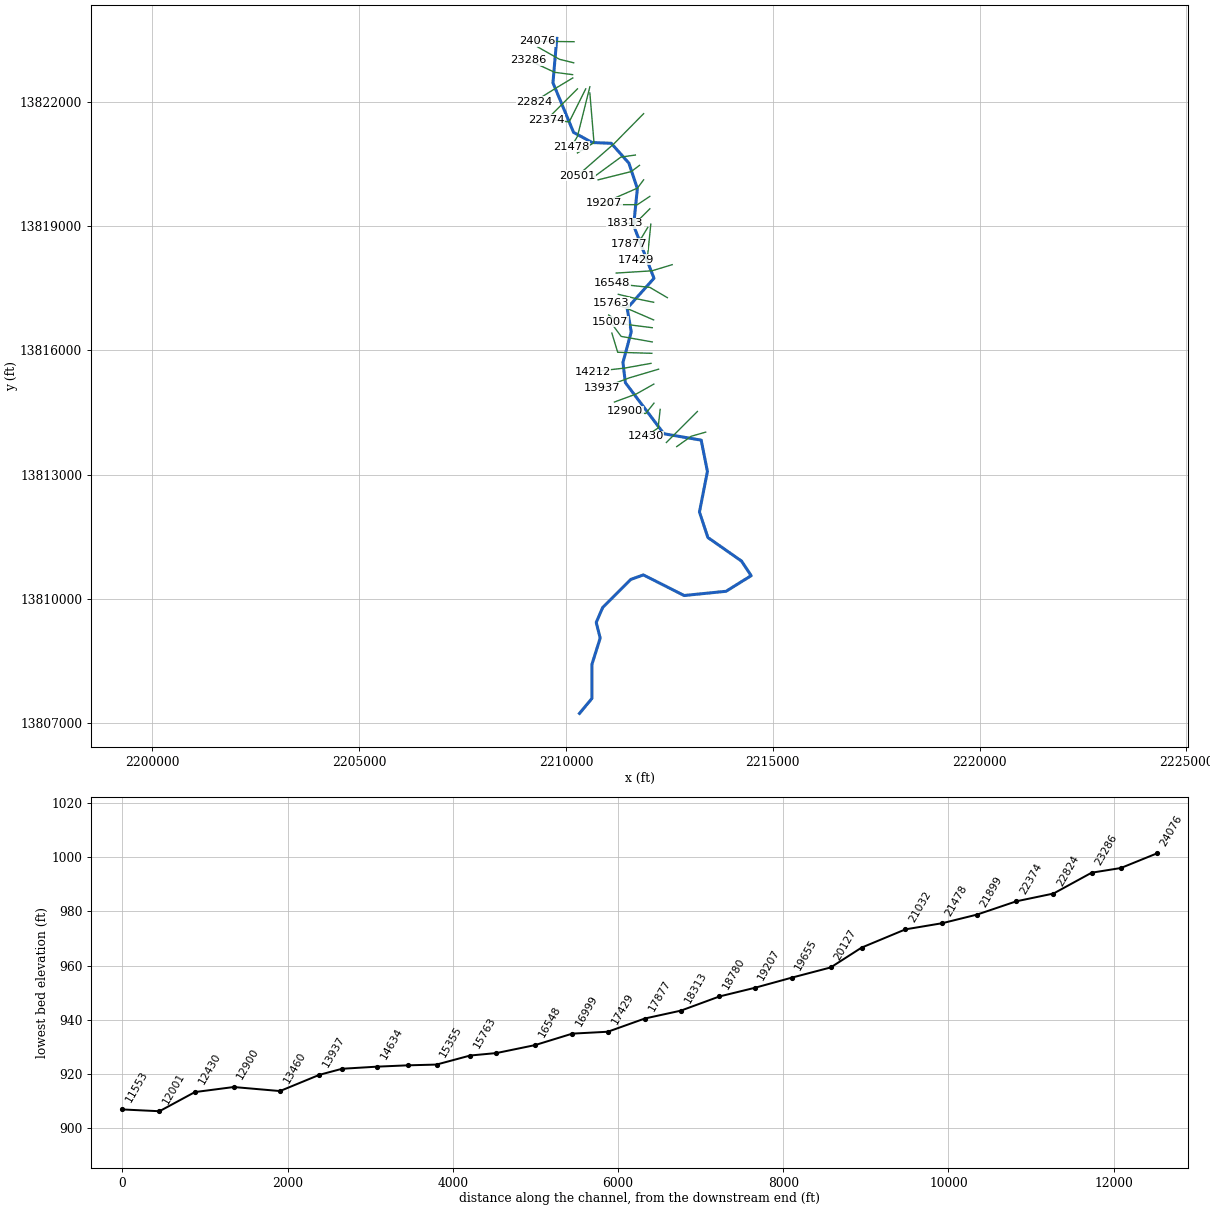
--- Upper Dry Comal Tributary 3.prj (project) ---

Proj Title=Upper Dry Comal Tributary 3 Base Level Engineering
Current Plan=p01
Default Exp/Contr=0.3,0.1
English Units
Geom File=g01
Flow File=f01
Plan File=p01
Y Axis Title=Elevation
X Axis Title(PF)=Main Channel Distance
X Axis Title(XS)=Station
BEGIN DESCRIPTION:
Upper Dry Comal Tributary 3
END DESCRIPTION:
DSS Export Rating Curves= 0
DSS Export Rating Curve Sorted= 0
DSS Export Volume Flow Curves= 0
DXF OffsetX= 0
DXF OffsetY= 0
DXF ScaleX= 1
DXF ScaleY= 10

--- Upper Dry Comal Tributary 3.p01 (plan) ---

Plan Title=Multiple Run
Program Version=4.10
Short Identifier=Multiple
Geom File=g01
Flow File=f01
Subcritical Flow
K Sum by GR= 0
Std Step Tol= 0.01
Critical Tol= 0.01
Num of Std Step Trials= 20
Max Error Tol= 0.3
Flow Tol Ratio= 0.001
Split Flow NTrial= 30
Split Flow Tol= 0.02
Split Flow Ratio= 0.02
Log Output Level= 0
Friction Slope Method= 1
Unsteady Friction Slope Method= 2
Unsteady Bridges Friction Slope Method= 1
Parabolic Critical Depth
Global Vel Dist= 1 , 1 , 1
Global Log Level= 0
CheckData=True
Encroach Param=-1 ,0,0, 0
BEGIN DESCRIPTION:
Multiple Run
END DESCRIPTION:
Computation Interval=1HOUR
Output Interval=1HOUR
Run HTab= 0
Run UNet= 0
Run PostProcess= 0
Run WQNet= 0
UNET Theta= 1
UNET Theta Warmup= 1
UNET ZTol= 0.02
UNET ZSATol= 0.05
UNET MxIter= 20
UNET MaxInSteps= 0
UNET DtIC= 0
UNET DtMin= 0
UNET MaxCRTS= 20
UNET WFStab= 2
UNET SFStab= 1
UNET WFX= 1
UNET SFX= 1
UNET DSS MLevel= 4
UNET DZMax Abort= 100
UNET Convert EG Bridges= 0
UNET Use Existing IB Tables=-1
UNET Froude Reduction=False
UNET Froude Limit= 1
UNET Froude Power= 10
UNET Time Slicing=0,0, 5
UNET Junction Losses=0
Instantaneous Interval=1HOUR
Write IC File= 0
Write IC File at Sim End=0
Echo Input=False
Echo Parameters=False
Echo Output=False
Write Detailed= 0
WQ AD Non Conservative
WQ ULTIMATE=-1
WQ Max Comp Step=1HOUR
WQ Output Interval=15MIN
WQ Output Selected Increments= 0
WQ Output face flow=0
WQ Output face velocity=0
WQ Output face area=0
WQ Output face dispersion=0
WQ Output cell volume=0
WQ Output cell surface area=0
WQ Output cell continuity=0
WQ Output cumulative cell continuity=0
WQ Output face conc=0
WQ Output face dconc_dx=0
WQ Output face courant=0
WQ Output face peclet=0
WQ Output face adv mass=0
WQ Output face disp mass=0
WQ Output cell mass=0
WQ Output cell source sink temp=0
WQ Output cell source sink nsm=0
WQ Output MaxMinRange=-1
WQ Daily Max Min Mean=-1
WQ Daily Range=0
WQ Daily Time=0
WQ Create Restart=0
WQ Fixed Restart=0
WQ System Summary=0
WQ Use Fixed Temperature=0
Sorting and Armoring Iterations= 10
XS Update Threshold= 0.02
Hydraulics Update Threshold= 0.02
Energy Slope Method= 1
Volume Change Method= 0
XS Weighting Method= 0
Number of US Weighted Cross Sections= 1
Number of DS Weighted Cross Sections= 1
Upstream XS Weight=0.25
Main XS Weight=0.5
Downstream XS Weight=0.25
Number of DS XS's Weighted with US Boundary= 1
Upstream Boundary Weight= 1
Weight of XSs Associated with US Boundary= 0
Number of US XS's Weighted with DS Boundary= 1
Downstream Boundary Weight= 0.5
Weight of XSs Associated with DS Boundary= 0.5
Sediment Output Level= 4
Mass or Volume Output= 0
Output Increment Type= 1
Profile and TS Output Increment= 10
XS Output Flag= 0
XS Output Increment= 10
Disregard all LS=0
Disregard all Conn=0
Disregard all Breaches=0
Disregard all Pumps=0

--- Upper Dry Comal Tributary 3.f01 (steady flow) ---

Flow Title=Multiple
Number of Profiles=7
Profile Names=10-year,25-year,50-year,1pct_min,100-year,1pct_plu,500-year
River Rch & RM= Upper Dry Comal ,Reach-1,24076
    1069    1799    2489    1668    3327    6639    5884
River Rch & RM= Upper Dry Comal ,Reach-1,20501
    1225    2072    2874    1930    3851    7683    6839
River Rch & RM= Upper Dry Comal ,Reach-1,16999
    2414    4197    5929    4041    8062   16086   14768
River Rch & RM= Upper Dry Comal ,Reach-1,14212
    2738    4779    6768    4622    9222   18400   16962
River Rch & RM= Upper Dry Comal ,Reach-1,11553
    2744    4787    6776    4625    9229   18413   16959
River Rch & RM= Upper Dry Comal ,Reach-1,10126
    2913    5087    7206    4920    9817   19587   18052
River Rch & RM= Upper Dry Comal ,Reach-1,6996
    3091    5401    7653    5226   10426   20803   19174
River Rch & RM= Upper Dry Comal ,Reach-1,2824
    3182    5552    7858    5358   10691   21332   19607
Boundary for River Rch & Prof#=Upper Dry Comal ,Reach-1,1
Up Type=0
Dn Type=3
Dn Slope=0.005
Boundary for River Rch & Prof#=Upper Dry Comal ,Reach-1,2
Up Type=0
Dn Type=3
Dn Slope=0.005
Boundary for River Rch & Prof#=Upper Dry Comal ,Reach-1,3
Up Type=0
Dn Type=3
Dn Slope=0.005
Boundary for River Rch & Prof#=Upper Dry Comal ,Reach-1,4
Up Type=0
Dn Type=3
Dn Slope=0.005
Boundary for River Rch & Prof#=Upper Dry Comal ,Reach-1,5
Up Type=0
Dn Type=3
Dn Slope=0.005
Boundary for River Rch & Prof#=Upper Dry Comal ,Reach-1,6
Up Type=0
Dn Type=3
Dn Slope=0.005
Boundary for River Rch & Prof#=Upper Dry Comal ,Reach-1,7
Up Type=0
Dn Type=3
Dn Slope=0.005

--- Upper Dry Comal Tributary 3.g01 (geometry) ---

Geom Title=Existing Conditions
Program Version=4.10

River Reach=Upper Dry Comal ,Reach-1
Reach XY= 30
        2209775.     13823546.44      2209682.89     13822471.79
      2210180.82     13821272.69      2210630.97     13821027.17
      2211091.67     13821008.61      2211519.64      13820527.7
      2211723.78      13819914.5      2211633.08      13819021.7
      2212125.28     13817745.18      2211477.24     13817019.07
       2211575.4       13816450.      2211375.08     13815709.61
      2211432.98     13815221.67       2212365.2     13813985.48
      2213266.87     13813831.08      2213417.67      13813074.9
      2213224.96     13812094.99      2213428.55     13811476.47
      2214241.67     13810908.35      2214475.37     13810554.79
      2213869.14     13810177.07      2212854.82     13810074.71
      2211869.07     13810572.77      2211565.32     13810464.22
      2210885.52     13809784.79      2210728.67     13809423.41
      2210824.94     13809045.03      2210625.09     13808409.61
      2210624.01     13807585.28        2210325.       13807225.

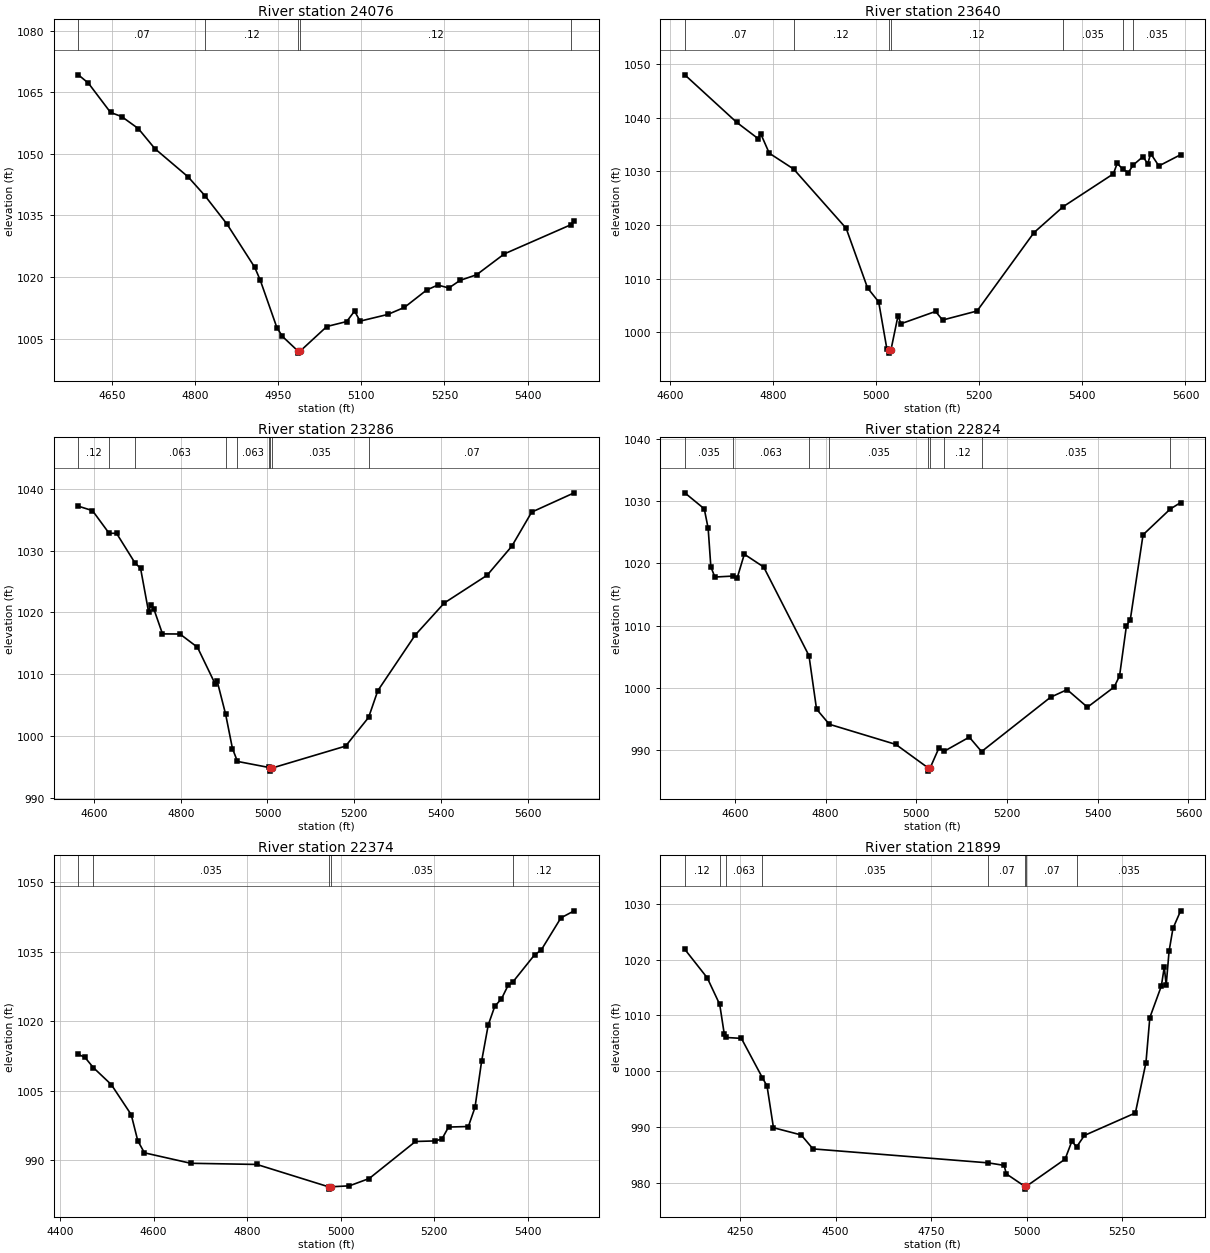
Type RM Length L Ch R = 1 ,24076   ,436,436,436
BEGIN DESCRIPTION:
XS7921
END DESCRIPTION:
XS GIS Cut Line= 2
      2210193.12     13823465.15      2209299.06     13823474.09
#Sta/Elev= 30
  4589.8 1069.21  4607.9 1067.19  4647.9 1060.05  4667.9 1059.05  4697.9 1056.13
  4727.9 1051.23  4787.9 1044.35  4817.8 1039.83  4857.9 1032.87  4907.9 1022.35
  4917.9  1019.2  4947.9 1007.65  4957.9 1005.52  4985.9 1001.96  4986.2 1001.46
  4989.9 1001.96  5037.9 1007.94  5073.7 1009.15  5087.9 1011.69  5097.9 1009.25
  5147.9 1010.88  5177.9  1012.6  5217.9 1016.82    5238 1018.03    5258 1017.32
    5278 1019.16    5308 1020.54    5358 1025.62  5477.7  1032.7  5483.9 1033.65
#Mann= 5 ,-1 , 0
  4589.8     .07       0  4817.8     .12       0  4985.9     .05       0
  4989.9     .12       0  5477.7    .094       0
Bank Sta=4985.9,4989.9
XS Rating Curve= 0 ,0
Exp/Cntr=0.3,0.1

Type RM Length L Ch R = 1 ,23640   ,354,354,354
BEGIN DESCRIPTION:
Upper Dry Comal Tributary 3 49.0
END DESCRIPTION:
XS GIS Cut Line= 3
      2210184.12     13822955.02      2209839.57     13823040.04
      2209311.53     13823339.85
#Sta/Elev= 30
  4628.5 1048.05  4729.1 1039.18  4770.6 1036.14  4775.7 1037.07  4792.4 1033.41
  4839.8 1030.44  4941.6 1019.38  4983.1 1008.24  5004.7 1005.63  5020.6  996.85
  5024.3  996.56  5024.6  996.06  5028.3  996.56  5042.2 1003.02    5048 1001.55
  5115.1 1003.85  5128.7 1002.24  5195.6 1003.93  5306.1 1018.58  5362.7 1023.42
  5460.1 1029.55  5467.6 1031.53    5478 1030.44  5489.2 1029.79  5498.5  1031.2
  5517.6 1032.76  5526.8 1031.42  5532.5 1033.34  5548.4 1031.03  5590.6 1033.13
#Mann= 7 ,-1 , 0
  4628.5     .07       0  4839.8     .12       0  5024.3     .05       0
  5028.3     .12       0  5362.7    .035       0    5478    .063       0
  5498.5    .035       0
Bank Sta=5024.3,5028.3
XS Rating Curve= 0 ,0
Exp/Cntr=0.3,0.1

Type RM Length L Ch R = 1 ,23286   ,462,462,462
BEGIN DESCRIPTION:
Upper Dry Comal Tributary 3 48.0
END DESCRIPTION:
XS GIS Cut Line= 3
      2210157.33     13822668.62        2209725.       13822725.
      2209083.35     13823022.12
#Sta/Elev= 30
  4563.9 1037.19  4596.5 1036.47  4634.8 1032.81    4652  1032.8  4694.5 1028.01
  4707.4 1027.13  4725.9 1020.08    4731 1021.24  4737.7 1020.62  4757.9 1016.53
  4798.2 1016.51  4838.5 1014.37  4878.9  1008.5  4883.9 1008.91  4903.4 1003.56
  4919.2  997.99  4930.7   995.9  5003.4  994.92  5006.6  994.83  5006.8  994.33
  5010.6  994.83  5180.1  998.38  5233.1 1003.02  5254.3 1007.34  5340.5 1016.34
  5407.6 1021.53  5506.4 1026.02  5563.3 1030.72  5609.1 1036.23    5707 1039.35
#Mann= 9 ,-1 , 0
  4563.9     .12       0  4634.8    .035       0  4694.5    .063       0
  4903.4    .035       0  4930.7    .063       0  5003.4    .035       0
  5006.6     .05       0  5010.6    .035       0  5233.1     .07       0
Bank Sta=5006.6,5010.6
XS Rating Curve= 0 ,0
Exp/Cntr=0.3,0.1

Type RM Length L Ch R = 1 ,22824   ,450,450,450
BEGIN DESCRIPTION:
Upper Dry Comal Tributary 3 47.0
END DESCRIPTION:
XS GIS Cut Line= 3
      2210161.72     13822588.05        2209725.       13822325.
      2209230.98     13822015.28
#Sta/Elev= 30
  4489.8 1031.33  4532.7 1028.76  4541.3 1025.62  4547.2 1019.46    4556  1017.8
  4596.6 1017.96  4605.4 1017.68    4621 1021.47  4663.7 1019.41  4763.5 1005.17
  4780.2  996.58  4808.3  994.15    4955  990.91  5026.5  987.12  5026.7  986.62
  5030.5  987.12  5049.7   990.3    5062  989.83  5116.9  992.08  5143.9  989.76
    5296  998.49  5332.5  999.71  5377.3  996.89  5436.2 1000.13  5448.1 1001.92
  5463.3    1010  5471.7 1010.93  5499.9 1024.59  5559.9 1028.73  5582.7 1029.76
#Mann= 9 ,-1 , 0
  4489.8    .035       0  4596.6    .063       0  4763.5     .12       0
  4808.3    .035       0  5026.5    .035       0  5030.5    .035       0
    5062     .12       0  5143.9    .035       0  5559.9     .12       0
Bank Sta=5026.5,5030.5
XS Rating Curve= 0 ,0
Exp/Cntr=0.3,0.1

Type RM Length L Ch R = 1 ,22374   ,475,475,475
BEGIN DESCRIPTION:
Upper Dry Comal Tributary 3 46.0
END DESCRIPTION:
XS GIS Cut Line= 3
      2210274.96     13822324.96        2209875.       13821925.
      2209525.01     13821575.01
#Sta/Elev= 30
  4438.9 1012.84    4453  1012.2  4470.9    1010  4509.6  1006.3    4552  999.83
  4566.1  994.18  4580.3  991.59  4679.3  989.33  4820.7  989.08  4974.3  984.25
  4974.5  983.75  4978.3  984.25  5018.7  984.46  5061.1  986.04  5160.1  994.04
  5202.5  994.16  5216.7  994.58  5230.8  997.15  5273.2  997.27  5287.4 1001.41
  5301.5 1011.35  5315.7 1019.19  5329.8 1023.26  5343.9 1024.81  5358.1 1027.73
  5369.2 1028.58  5414.7 1034.32  5428.8 1035.34  5471.2 1042.32  5499.5 1043.84
#Mann= 5 ,-1 , 0
  4438.9    .063       0  4470.9    .035       0  4974.3    .035       0
  4978.3    .035       0  5369.2     .12       0
Bank Sta=4974.3,4978.3
XS Rating Curve= 0 ,0
Exp/Cntr=0.3,0.1

Type RM Length L Ch R = 1 ,21899   ,421,421,421
BEGIN DESCRIPTION:
Upper Dry Comal Tributary 3 45.0
END DESCRIPTION:
XS GIS Cut Line= 3
      2210474.99     13822324.99        2210075.       13821525.
      2209675.03       13821575.
#Sta/Elev= 30
  4105.6 1021.87  4164.3 1016.76    4197 1011.98    4209 1006.62  4214.3 1006.05
  4253.7 1005.89  4308.7  998.82  4320.8  997.34  4337.6  989.86  4410.2  988.56
    4441  986.06  4900.1  983.55  4941.3   983.1  4946.9  981.58  4995.2  979.34
  4995.5  978.84  4999.2  979.34  5100.8  984.22  5118.4  987.42    5131  986.42
  5151.2  988.47  5284.7  992.51  5312.4 1001.56  5322.5 1009.62  5352.7  1015.3
  5360.3 1018.69  5365.3 1015.46  5372.9 1021.55    5383 1025.61  5403.1 1028.78
#Mann= 8 ,-1 , 0
  4105.6     .12       0    4197    .035       0  4214.3    .063       0
  4308.7    .035       0  4900.1     .07       0  4995.2     .05       0
  4999.2     .07       0    5131    .035       0
Bank Sta=4995.2,4999.2
XS Rating Curve= 0 ,0
Exp/Cntr=0.3,0.1

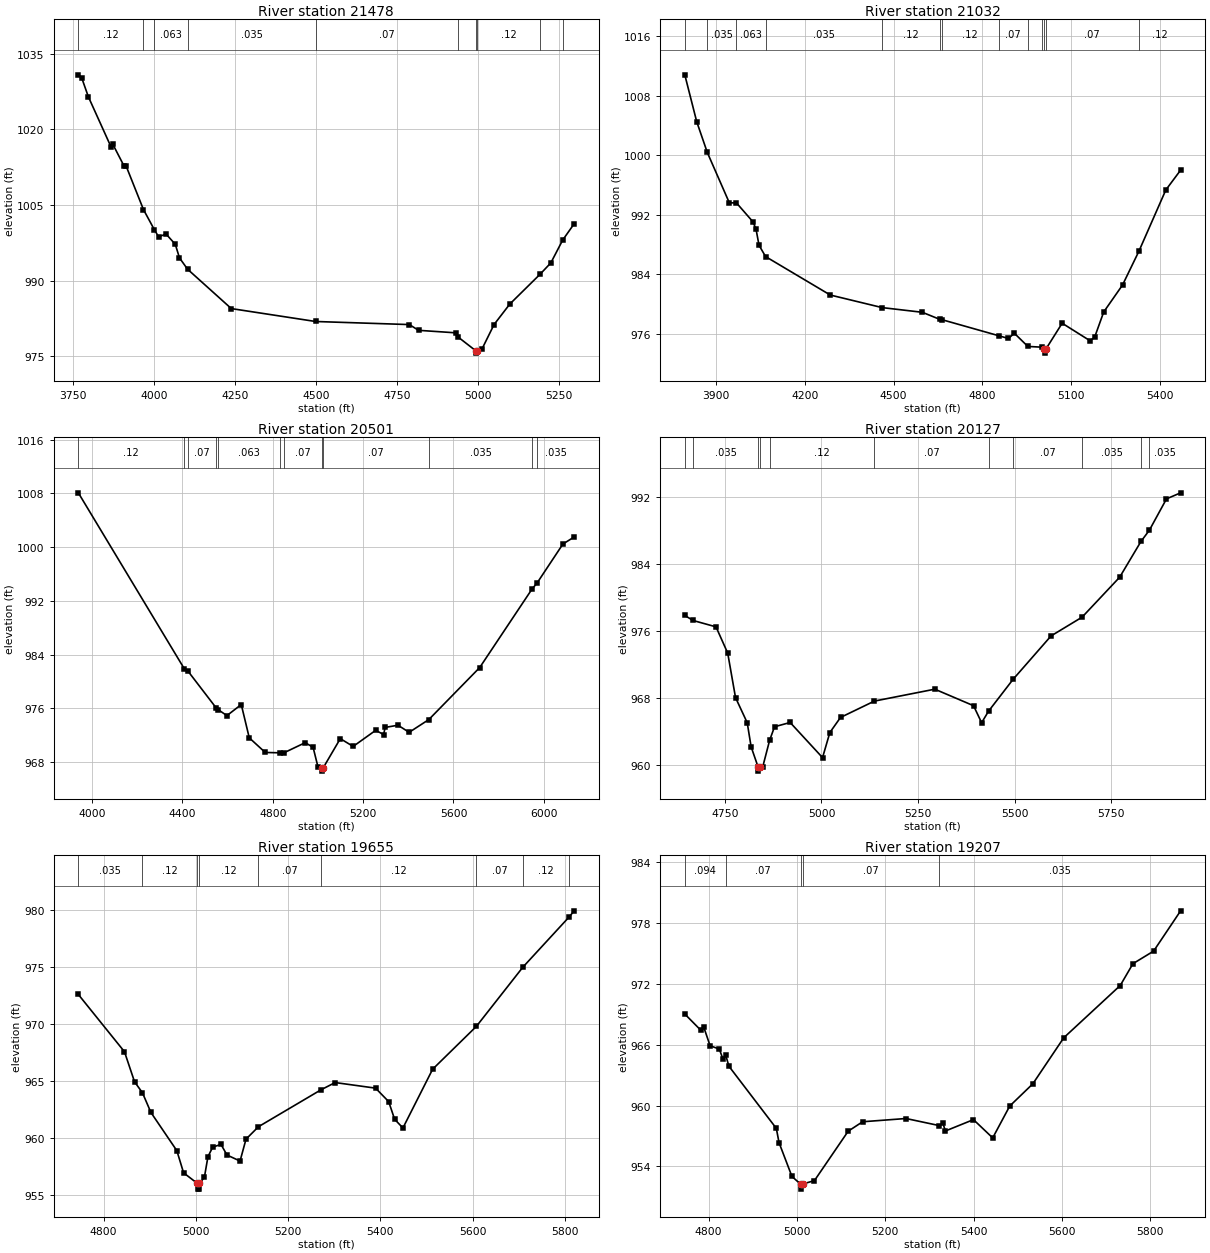
Type RM Length L Ch R = 1 ,21478   ,446,446,446
BEGIN DESCRIPTION:
Upper Dry Comal Tributary 3 44.0
END DESCRIPTION:
XS GIS Cut Line= 3
        2210575.     13822375.01        2210275.       13821175.
        2210125.     13820924.99
#Sta/Elev= 30
  3767.4 1030.83  3777.7 1030.25  3798.3 1026.48  3867.9 1016.58  3873.1 1017.14
  3909.1 1012.66  3914.3 1012.82  3968.1 1004.13    4002  1000.1  4014.8  998.73
    4038  999.26  4066.3  997.23  4079.2  994.54  4104.2  992.29    4239  984.49
  4498.9  981.93  4787.9  981.32  4816.2  980.18  4932.2  979.68  4938.5  978.83
    4992  976.16  4992.2  975.66  4996.1  976.16  5012.1  976.52    5049  981.33
  5097.6  985.39  5190.4  991.27    5224  993.55  5260.6  998.08  5295.9  1001.3
#Mann= 10 ,-1 , 0
  3767.4     .12       0  3968.1    .035       0    4002    .063       0
  4104.2    .035       0  4498.9     .07       0  4938.5     .12       0
    4992     .05       0  4996.1     .12       0  5190.4    .035       0
  5260.6     .12       0
Bank Sta=4992,4996.1
XS Rating Curve= 0 ,0
Exp/Cntr=0.3,0.1

Type RM Length L Ch R = 1 ,21032   ,531,531,531
BEGIN DESCRIPTION:
Upper Dry Comal Tributary 3 43.0
END DESCRIPTION:
XS GIS Cut Line= 3
        2210575.     13822225.04        2210675.       13821025.
        2210275.       13820775.
#Sta/Elev= 30
  3794.3 1010.79  3834.5  1004.5  3870.3 1000.36  3944.9  993.58  3968.8  993.58
  4025.1  991.01  4035.2  990.01  4045.2  987.88  4067.3  986.36    4286  981.19
  4461.3   979.5  4597.1  978.87  4656.8  977.91  4663.1  977.88  4855.3  975.72
  4888.1  975.35  4908.2  976.05  4953.8  974.28  5001.4  974.18    5010  973.88
  5010.3  973.38  5014.1  973.88  5069.8   977.4  5164.2  975.04  5179.5  975.51
  5210.2  978.91  5273.9  982.54  5329.2  987.08  5420.1  995.31  5470.2  997.98
#Mann= 13 ,-1 , 0
  3794.3     .12       0  3870.3    .035       0  3968.8    .063       0
  4067.3    .035       0  4461.3     .12       0  4656.8     .07       0
  4663.1     .12       0  4855.3     .07       0  4953.8    .035       0
  5001.4     .07       0    5010    .035       0  5014.1     .07       0
  5329.2     .12       0
Bank Sta=5010,5014.1
XS Rating Curve= 0 ,0
Exp/Cntr=0.3,0.1

Type RM Length L Ch R = 1 ,20501   ,374,374,374
BEGIN DESCRIPTION:
Upper Dry Comal Tributary 3 42.0
END DESCRIPTION:
XS GIS Cut Line= 3
      2211874.97     13821724.97      2211150.71     13820990.53
      2210275.02     13820225.01
#Sta/Elev= 30
  3939.6 1008.09  4408.6  981.88    4423  981.61    4551  975.99  4559.2  975.77
  4597.2   974.9  4660.8  976.55  4696.2  971.59  4766.9  969.41  4831.5  969.36
  4851.5  969.39  4943.7  970.87  4978.7  970.18  5000.4  967.24  5019.1  967.13
  5019.4  966.63  5023.6  967.13  5099.1  971.47  5156.1  970.31  5255.8  972.71
  5290.9  972.08  5297.5  973.14  5354.5  973.47  5403.8  972.41  5490.9  974.31
  5716.1  982.06  5948.8  993.81    5969   994.6  6084.4 1000.46  6134.2 1001.51
#Mann= 12 ,-1 , 0
  3939.6     .12       0  4408.6    .035       0    4423     .07       0
    4551    .035       0  4559.2    .063       0  4831.5    .035       0
  4851.5     .07       0  5019.1     .05       0  5023.6     .07       0
  5490.9    .035       0  5948.8     .07       0    5969    .035       0
Bank Sta=5019.1,5023.6
XS Rating Curve= 0 ,0
Exp/Cntr=0.3,0.1

Type RM Length L Ch R = 1 ,20127   ,472,472,472
BEGIN DESCRIPTION:
Upper Dry Comal Tributary 3 41.0
END DESCRIPTION:
XS GIS Cut Line= 3
      2211674.99       13820725.        2211325.       13820675.
        2210575.       13820125.
#Sta/Elev= 30
  4646.2  977.86  4667.6  977.26    4727   976.5  4757.3  973.37  4777.5  968.07
  4807.8  965.07  4817.9   962.2  4835.9   959.8  4836.2   959.3  4840.4   959.8
  4848.2  959.85  4865.7  962.96  4878.5  964.59  4918.9   965.1  5002.8  960.91
  5021.7   963.9  5049.3   965.7    5137  967.65  5293.4  969.07  5393.7   967.1
  5414.6  965.07  5432.6  966.45    5496  970.24  5594.4  975.42  5674.8  977.66
    5772  982.42  5827.1  986.68    5849  988.03  5893.2  991.76  5929.8  992.48
#Mann= 11 ,-1 , 0
  4646.2    .063       0  4667.6    .035       0  4835.9     .05       0
  4840.4    .035       0  4865.7     .12       0    5137     .07       0
  5432.6     .12       0    5496     .07       0  5674.8    .035       0
  5827.1     .07       0    5849    .035       0
Bank Sta=4835.9,4840.4
XS Rating Curve= 0 ,0
Exp/Cntr=0.3,0.1

Type RM Length L Ch R = 1 ,19655   ,448,448,448
BEGIN DESCRIPTION:
Upper Dry Comal Tributary 3 40.0
END DESCRIPTION:
XS GIS Cut Line= 3
      2211774.97     13820474.98        2211575.       13820325.
      2210774.99       13820125.
#Sta/Elev= 30
  4745.4  972.58  4845.4  967.56  4867.2  964.93  4884.4  963.96  4902.7  962.24
  4958.9  958.89  4973.5  956.95  5003.4  956.02  5003.7  955.52  5007.6  955.52
    5008  956.02  5018.6  956.56  5026.3  958.36  5036.6   959.2  5054.6  959.44
  5067.5  958.51  5095.9  957.98  5108.8   959.9  5135.8  960.99  5271.1  964.22
    5302  964.86  5389.6  964.37    5418  963.19  5430.9  961.64  5448.9  960.88
  5513.3  966.03    5608  969.78  5708.8  974.97  5809.5  979.39    5820  979.91
#Mann= 9 ,-1 , 0
  4745.4    .035       0  4884.4     .12       0  5003.4     .05       0
    5008     .12       0  5135.8     .07       0  5271.1     .12       0
    5608     .07       0  5708.8     .12       0  5809.5    .035       0
Bank Sta=5003.4,5008
XS Rating Curve= 0 ,0
Exp/Cntr=0.3,0.1

Type RM Length L Ch R = 1 ,19207   ,427,427,427
BEGIN DESCRIPTION:
Upper Dry Comal Tributary 3 39.0
END DESCRIPTION:
XS GIS Cut Line= 3
        2211875.       13820125.        2211725.       13819925.
      2210925.01     13819575.01
#Sta/Elev= 30
  4745.9  969.02  4782.4  967.41  4788.6  967.76  4803.2  965.89    4824  965.57
  4832.4  964.58  4838.5  964.97  4845.9  963.87  4953.2  957.75  4959.4  956.34
  4988.6  953.01    5008  952.26  5008.3  951.76  5012.6  952.26  5039.6   952.6
    5116  957.47  5148.7   958.4    5247  958.72  5321.5  958.03  5330.8  958.23
  5336.2  957.49  5399.8  958.61  5443.4  956.81    5482  959.95  5534.3  962.14
  5604.4  966.68  5732.3  971.83  5761.1  973.98  5807.9  975.22  5869.1  979.19
#Mann= 5 ,-1 , 0
  4745.9    .094       0  4838.5     .07       0    5008     .05       0
  5012.6     .07       0  5321.5    .035       0
Bank Sta=5008,5012.6
XS Rating Curve= 0 ,0
Exp/Cntr=0.3,0.1

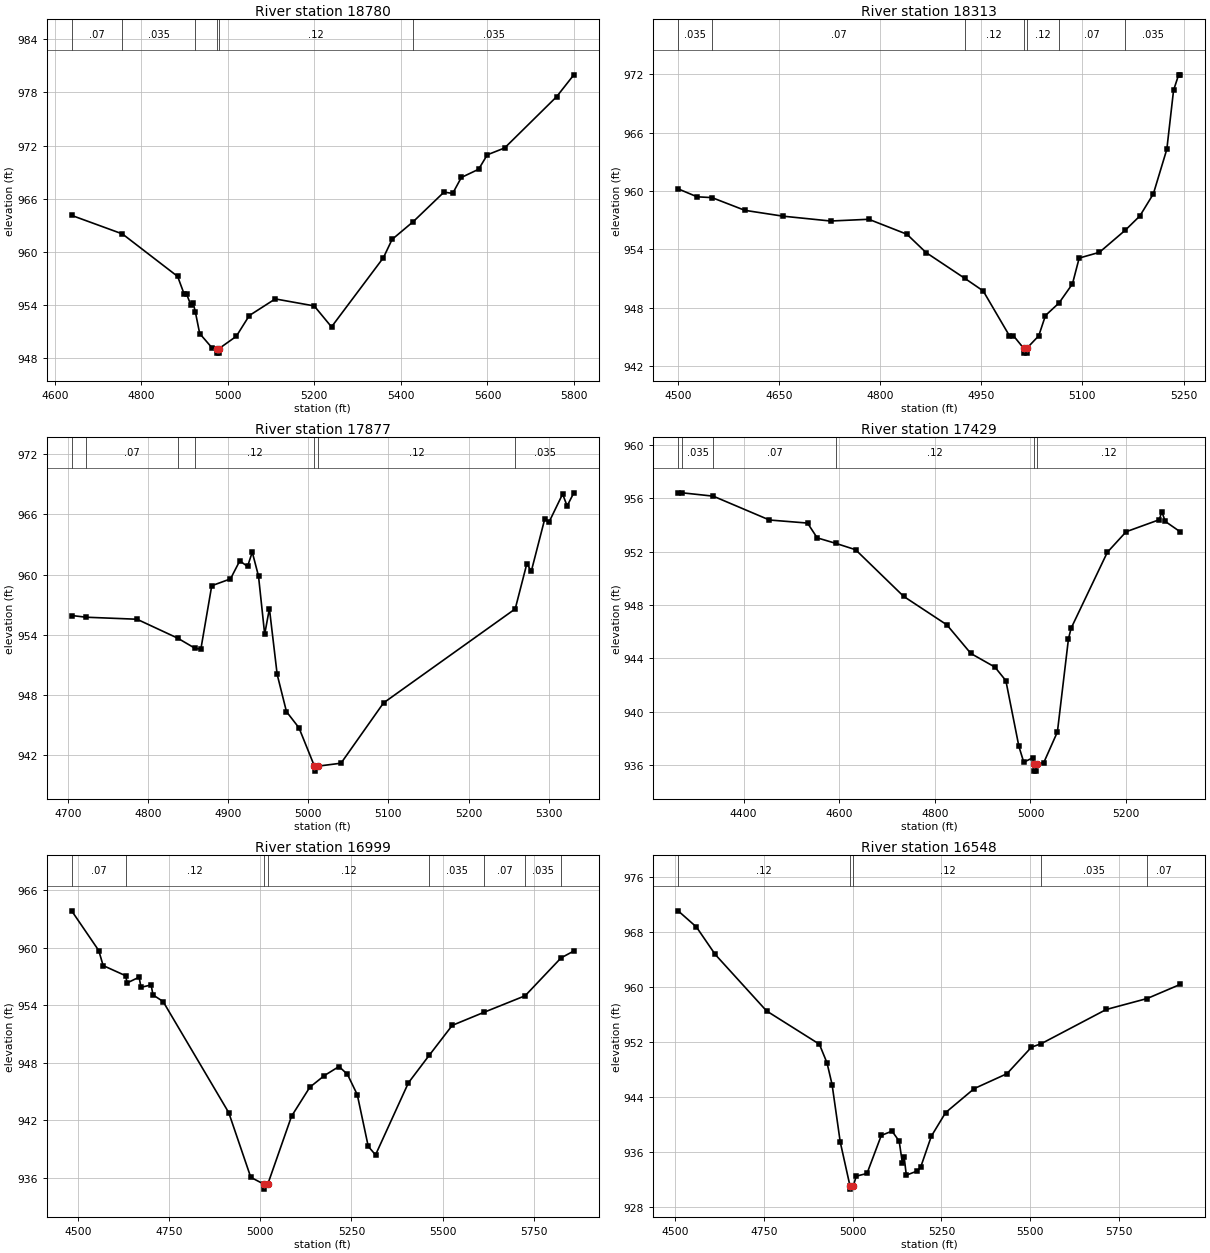
Type RM Length L Ch R = 1 ,18780   ,467,467,467
BEGIN DESCRIPTION:
Upper Dry Comal Tributary 3 38.0
END DESCRIPTION:
XS GIS Cut Line= 3
      2212024.98     13819724.99        2211725.       13819525.
      2210925.03       13819525.
#Sta/Elev= 30
  4639.1  964.12  4756.3  962.03    4884  957.23    4899  955.25    4905  955.21
    4914  954.06    4920  954.21    4925  953.21    4935  950.78  4963.6  949.16
  4974.8  949.07  4975.1  948.57  4979.1  948.57  4979.4  949.07  5019.6  950.47
  5049.6  952.81  5109.6  954.69  5199.6   953.9  5239.6  951.53  5359.6  959.35
  5379.6  961.41  5428.8  963.43  5499.6  966.75  5519.6   966.6  5539.6   968.4
  5579.6  969.33  5599.6  970.96  5639.6  971.73  5759.6  977.51  5799.6  979.99
#Mann= 6 ,-1 , 0
  4639.1     .07       0  4756.3    .035       0    4925     .12       0
  4974.8     .05       0  4979.4     .12       0  5428.8    .035       0
Bank Sta=4974.8,4979.4
XS Rating Curve= 0 ,0
Exp/Cntr=0.3,0.1

Type RM Length L Ch R = 1 ,18313   ,436,436,436
BEGIN DESCRIPTION:
Upper Dry Comal Tributary 3 37.0
END DESCRIPTION:
XS GIS Cut Line= 3
      2212024.97     13819424.97        2211675.       13819075.
      2211425.03       13819075.
#Sta/Elev= 30
  4500.3  960.23  4528.5  959.41  4550.5  959.33  4599.3  958.02  4655.8  957.42
  4726.5  956.92  4783.1   957.1  4839.7  955.56    4868  953.68  4925.4  951.03
  4952.8  949.73  4991.7  945.12  4997.7  945.12  5012.8  943.83  5013.2  943.33
  5017.3  943.33  5017.6  943.83  5035.2  945.11  5045.2   947.2  5065.3  948.49
  5085.2  950.45  5095.2  953.11  5125.2   953.7  5163.8  955.99  5185.2  957.44
  5205.2  959.71  5225.2   964.3  5235.2  970.37  5242.7  971.96  5245.2  971.96
#Mann= 7 ,-1 , 0
  4500.3    .035       0  4550.5     .07       0  4925.4     .12       0
  5012.8     .05       0  5017.6     .12       0  5065.3     .07       0
  5163.8    .035       0
Bank Sta=5012.8,5017.6
XS Rating Curve= 0 ,0
Exp/Cntr=0.3,0.1

Type RM Length L Ch R = 1 ,17877   ,448,448,448
BEGIN DESCRIPTION:
Upper Dry Comal Tributary 3 36.0
END DESCRIPTION:
XS GIS Cut Line= 3
      2211975.01     13818975.01        2211825.       13818725.
      2211524.98     13818574.99
#Sta/Elev= 30
  4704.5  955.93  4722.8  955.76  4786.1  955.56    4837  953.67  4858.4  952.67
  4865.8  952.57  4879.4   958.9  4902.8  959.58  4914.4  961.38  4924.1  960.82
    4930  962.25  4937.8  959.86  4945.5  954.06  4951.4  956.62  4961.1  950.06
  4972.7  946.35  4988.3  944.74  5007.6  940.92    5008  940.42  5012.4  940.92
  5040.8  941.21  5093.9  947.22  5258.3  956.59  5272.8  961.09  5278.4  960.35
  5295.1  965.53  5300.7  965.27  5317.5  968.04  5323.1  966.85  5331.5  968.16
#Mann= 7 ,-1 , 0
  4704.5    .035       0  4722.8     .07       0    4837    .035       0
  4858.4     .12       0  5007.6     .05       0  5012.4     .12       0
  5258.3    .035       0
Bank Sta=5007.6,5012.4
XS Rating Curve= 0 ,0
Exp/Cntr=0.3,0.1

Type RM Length L Ch R = 1 ,17429   ,430,430,430
BEGIN DESCRIPTION:
Upper Dry Comal Tributary 3 35.0
END DESCRIPTION:
XS GIS Cut Line= 3
       2212048.8     13819054.32        2211975.       13818325.
      2211686.11      13818193.4
#Sta/Elev= 30
    4263  956.37  4271.8  956.42  4336.5  956.17    4454  954.38  4533.7  954.15
  4553.9  953.04  4593.5  952.62  4634.2  952.15  4734.7  948.65  4825.2  946.51
  4875.4  944.36  4925.7  943.34  4948.6  942.32  4975.9  937.38    4986   936.2
  5004.8  936.53  5007.9  936.03  5008.3  935.53  5012.4  935.53  5012.7  936.03
  5027.9  936.17  5056.4  938.47  5079.5  945.45    5085  946.25  5160.9  951.96
  5200.2   953.5  5269.4   954.4  5274.9  955.01  5281.8  954.28  5313.5  953.49
#Mann= 6 ,-1 , 0
    4263     .07       0  4271.8    .035       0  4336.5     .07       0
  4593.5     .12       0  5007.9     .05       0  5012.7     .12       0
Bank Sta=5007.9,5012.7
XS Rating Curve= 0 ,0
Exp/Cntr=0.3,0.1

Type RM Length L Ch R = 1 ,16999   ,451,451,451
BEGIN DESCRIPTION:
Upper Dry Comal Tributary 3 34.0
END DESCRIPTION:
XS GIS Cut Line= 3
      2212566.09     13818074.08        2212075.       13817925.
      2211211.98     13817871.32
#Sta/Elev= 30
  4482.3  963.86  4556.6  959.72  4568.7  958.15  4630.4  957.09  4634.5  956.34
  4667.4  956.94  4672.6  955.88  4700.3  956.13  4705.5  955.09  4733.2   954.4
  4913.3  942.81  4973.8  936.06  5010.8  935.33  5011.3  934.83  5020.3  935.33
  5085.7  942.44  5135.8  945.46  5175.9  946.68  5215.9  947.62  5239.1   946.8
    5266  944.68  5296.1  939.29  5316.1   938.4  5406.3  945.92  5463.6   948.8
  5526.5  951.91  5612.7  953.26  5726.6     955  5825.1  958.95  5860.2  959.67
#Mann= 8 ,-1 , 0
  4482.3     .07       0  4630.4     .12       0  5010.8     .05       0
  5020.3     .12       0  5463.6    .035       0  5612.7     .07       0
  5726.6    .035       0  5825.1     .12       0
Bank Sta=5010.8,5020.3
XS Rating Curve= 0 ,0
Exp/Cntr=0.3,0.1

Type RM Length L Ch R = 1 ,16548   ,467,467,467
BEGIN DESCRIPTION:
Upper Dry Comal Tributary 3 33.0
END DESCRIPTION:
XS GIS Cut Line= 3
      2212448.46     13817276.35        2212025.       13817525.
      2211108.51     13817621.33
#Sta/Elev= 30
  4509.2  971.12  4560.6  968.77  4613.5  964.77    4758  956.54  4906.5   951.7
    4928  948.98  4942.3  945.82  4965.2  937.46  4992.5  931.09    4993  930.59
  5002.2  931.09  5010.3  932.48  5040.5  932.87  5080.7  938.41  5110.9  939.04
    5131  937.58  5139.9  934.42  5144.9  935.31  5151.1  932.62  5181.3  933.22
  5191.3  933.76  5221.5   938.3  5261.7  941.74  5342.1  945.23  5434.2   947.4
    5503  951.26    5531  951.78  5713.4  956.75  5828.6  958.35  5921.8  960.41
#Mann= 5 ,-1 , 0
  4509.2     .12       0  4992.5     .05       0  5002.2     .12       0
    5531    .035       0  5828.6     .07       0
Bank Sta=4992.5,5002.2
XS Rating Curve= 0 ,0
Exp/Cntr=0.3,0.1

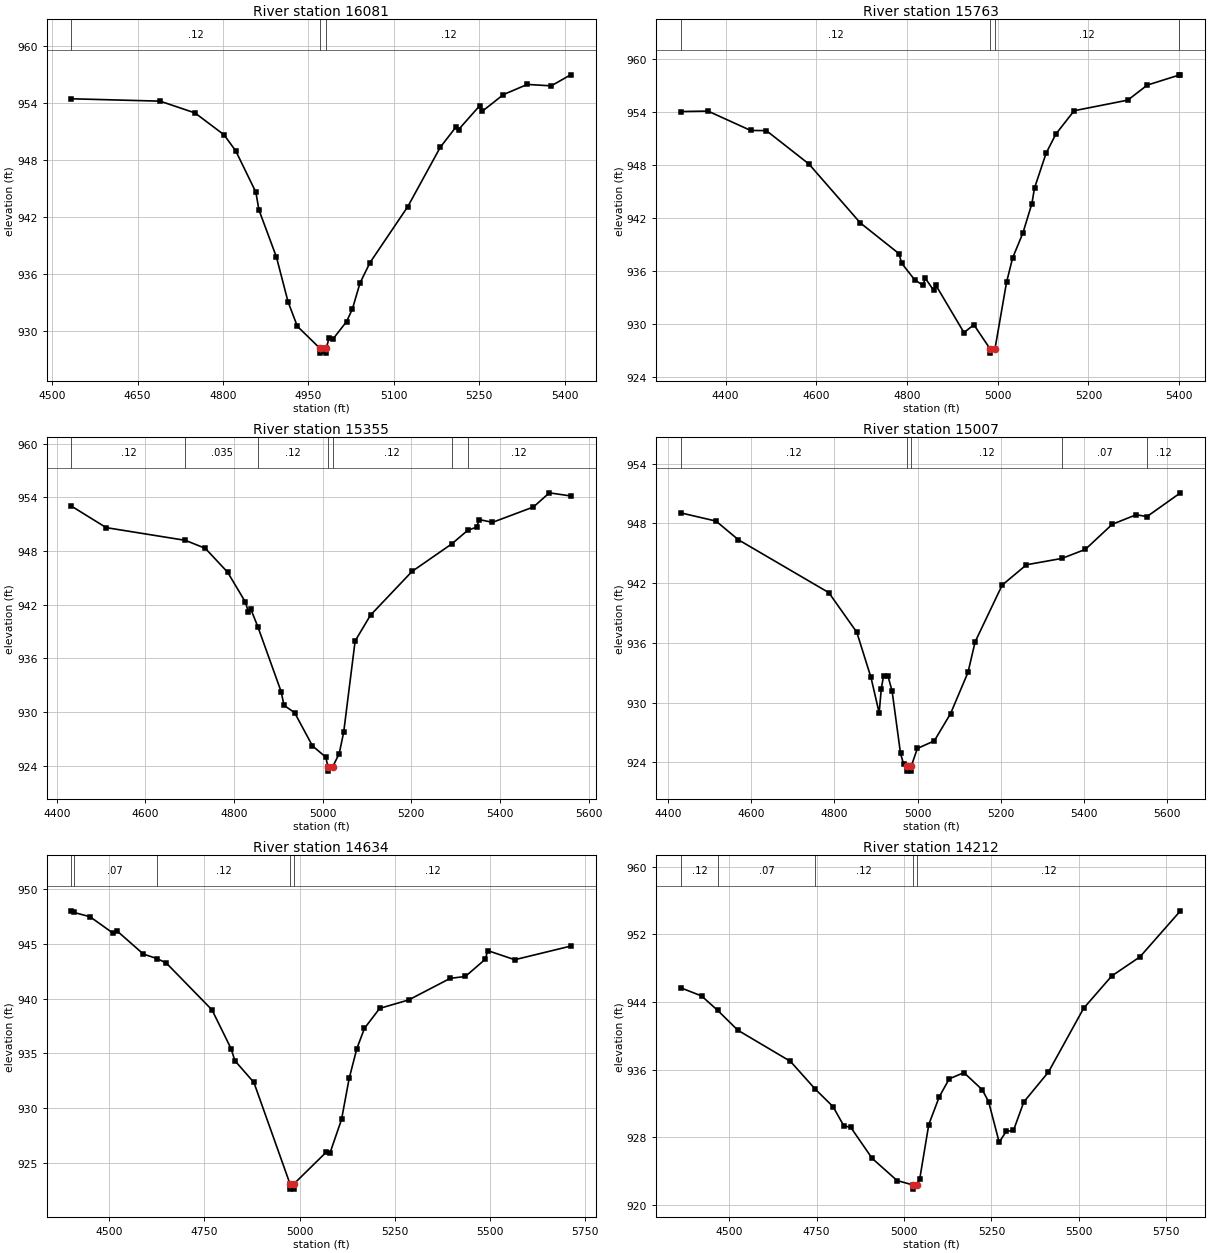
Type RM Length L Ch R = 1 ,16081   ,318,318,318
BEGIN DESCRIPTION:
Upper Dry Comal Tributary 3 32.0
END DESCRIPTION:
XS GIS Cut Line= 3
      2212117.27      13817164.5      2211727.97     13817245.04
      2211262.57     13817356.92
#Sta/Elev= 30
    4534  954.41  4689.5  954.16  4750.8  952.92  4801.8  950.62  4822.3  948.93
  4857.6  944.59  4863.1  942.71  4893.7  937.77  4914.2  933.04  4930.5  930.47
  4970.2  928.15  4970.7  927.65  4980.8  927.65  4981.3  928.15    4986  929.23
  4993.4  929.16  5016.9  930.97  5027.2  932.31  5040.5  935.03    5058  937.17
  5124.4  943.07  5181.4  949.31  5208.3  951.39  5213.5  951.17  5250.3  953.66
  5255.4  953.11  5292.2  954.85  5334.2  955.92  5376.2  955.77  5410.2  956.93
#Mann= 3 ,-1 , 0
    4534     .12       0  4970.2     .05       0  4981.3     .12       0
Bank Sta=4970.2,4981.3
XS Rating Curve= 0 ,0
Exp/Cntr=0.3,0.1

Type RM Length L Ch R = 1 ,15763   ,408,408,408
BEGIN DESCRIPTION:
H21526
END DESCRIPTION:
XS GIS Cut Line= 3
      2212117.11     13816738.05      2211505.22     13817002.36
      2211096.13     13817147.17
#Sta/Elev= 30
  4302.4  954.06  4361.2  954.11  4455.2  951.92  4489.9   951.9  4583.6  948.13
  4696.9  941.47  4782.5  937.98    4788  936.92  4816.9  935.03    4835  934.42
  4840.4   935.2  4858.5  933.85  4863.9  934.39  4925.6  929.06  4947.4  929.95
  4982.9  927.24  4983.4  926.74    4994  927.24  5019.4  934.74  5032.8   937.5
  5055.6  940.34  5075.3  943.65  5081.1  945.41  5106.7  949.35  5128.3  951.52
  5168.5  954.15  5286.8  955.35  5329.8  957.05  5399.8  958.18  5402.9  958.21
#Mann= 4 ,-1 , 0
  4302.4     .12       0  4982.9     .05       0    4994     .12       0
  5399.8     .07       0
Bank Sta=4982.9,4994
XS Rating Curve= 0 ,0
Exp/Cntr=0.3,0.1

Type RM Length L Ch R = 1 ,15355   ,348,348,348
BEGIN DESCRIPTION:
H21527
END DESCRIPTION:
XS GIS Cut Line= 3
      2212084.49     13816549.78      2211338.67     13816643.91
      2211030.88     13816857.55
#Sta/Elev= 30
  4433.1     953  4511.5   950.6  4690.1  949.18    4735  948.29  4785.4  945.62
  4825.7  942.27  4832.5  941.12  4837.5  941.53  4853.9  939.49  4906.3  932.26
  4912.7  930.74  4936.5  929.93  4976.9  926.21  5007.1  924.95  5011.6  923.89
  5012.1  923.39  5022.7  923.89  5037.3  925.35  5047.4  927.75  5073.2  937.94
  5107.9  940.82  5201.5   945.7  5291.5  948.79    5327  950.29  5347.4  950.66
  5353.5   951.5  5383.2  951.19  5475.7  952.91  5511.5  954.49  5559.5  954.14
#Mann= 7 ,-1 , 0
  4433.1     .12       0  4690.1    .035       0  4853.9     .12       0
  5011.6     .05       0  5022.7     .12       0  5291.5     .07       0
    5327     .12       0
Bank Sta=5011.6,5022.7
XS Rating Curve= 0 ,0
Exp/Cntr=0.3,0.1

Type RM Length L Ch R = 1 ,15007   ,373,373,373
BEGIN DESCRIPTION:
H21528
END DESCRIPTION:
XS GIS Cut Line= 3
      2212084.55      13816205.8      2211331.43     13816339.77
      2211071.11     13816690.47
#Sta/Elev= 30
  4431.4  949.05  4514.9  948.24  4568.8  946.36  4786.4  941.05  4853.8  937.07
    4888  932.52  4907.7  928.96  4912.8   931.4  4918.5  932.72  4928.6   932.7
  4938.8  931.17  4959.1  924.89  4966.7  923.79  4973.8  923.61  4974.3  923.11
  4984.5  923.11    4985  923.61  4999.7  925.39  5040.4  926.15  5079.7   928.9
  5121.6  933.04  5138.7   936.1  5203.9  941.81  5262.4  943.85    5348  944.49
  5404.2   945.4  5468.9  947.92  5526.7  948.88  5552.4  948.69  5633.1  951.08
#Mann= 5 ,-1 , 0
  4431.4     .12       0  4973.8     .05       0    4985     .12       0
    5348     .07       0  5552.4     .12       0
Bank Sta=4973.8,4985
XS Rating Curve= 0 ,0
Exp/Cntr=0.3,0.1

Type RM Length L Ch R = 1 ,14634   ,422,422,422
BEGIN DESCRIPTION:
H21529
END DESCRIPTION:
XS GIS Cut Line= 3
       2212073.7     13815930.63      2211248.16     13815955.98
      2211106.95     13816419.41
#Sta/Elev= 30
    4401  948.01  4406.6  947.87  4449.7  947.47  4509.7  945.98  4519.8   946.2
  4589.8  944.06  4625.1  943.66  4649.8  943.25  4769.9  938.97  4819.9  935.44
  4829.9  934.34  4879.9  932.35  4974.4  923.12  4974.9  922.62  4985.1  922.62
  4985.6  923.12    5070     926    5080  925.95    5110  928.98    5130  932.72
    5150  935.42  5170.1  937.29  5210.1  939.11  5286.3  939.88  5395.3  941.85
    5435  942.02  5487.3  943.59  5493.8  944.38  5564.7  943.55  5711.4  944.79
#Mann= 5 ,-1 , 0
    4401     .12       0  4406.6     .07       0  4625.1     .12       0
  4974.4     .05       0  4985.6     .12       0
Bank Sta=4974.4,4985.6
XS Rating Curve= 0 ,0
Exp/Cntr=0.3,0.1

Type RM Length L Ch R = 1 ,14212   ,275,275,275
BEGIN DESCRIPTION:
Upper Dry Comal Tributary 3 28.0
END DESCRIPTION:
XS GIS Cut Line= 3
        2212052.     13815688.05        2211425.       13815575.
      2210639.92     13815485.29
#Sta/Elev= 30
  4363.3  945.65  4421.2  944.71  4467.5  942.99  4524.7  940.66  4675.2  936.97
  4746.2  933.68  4797.2   931.6  4827.7  929.35    4848  929.14    4909  925.48
  4980.1  922.86    5025  922.34  5025.5  921.84  5036.2  922.34  5045.1  923.06
  5070.9  929.49  5101.1  932.79  5129.4   934.9  5171.5  935.63  5223.7  933.61
    5242  932.19  5272.2  927.39  5292.3  928.68  5313.1  928.79  5342.6  932.16
  5413.1   935.7  5513.7  943.25  5594.2  947.08  5674.8  949.34  5790.6  954.79
#Mann= 5 ,-1 , 0
  4363.3     .12       0  4467.5     .07       0  4746.2     .12       0
    5025     .05       0  5036.2     .12       0
Bank Sta=5025,5036.2
XS Rating Curve= 0 ,0
Exp/Cntr=0.3,0.1

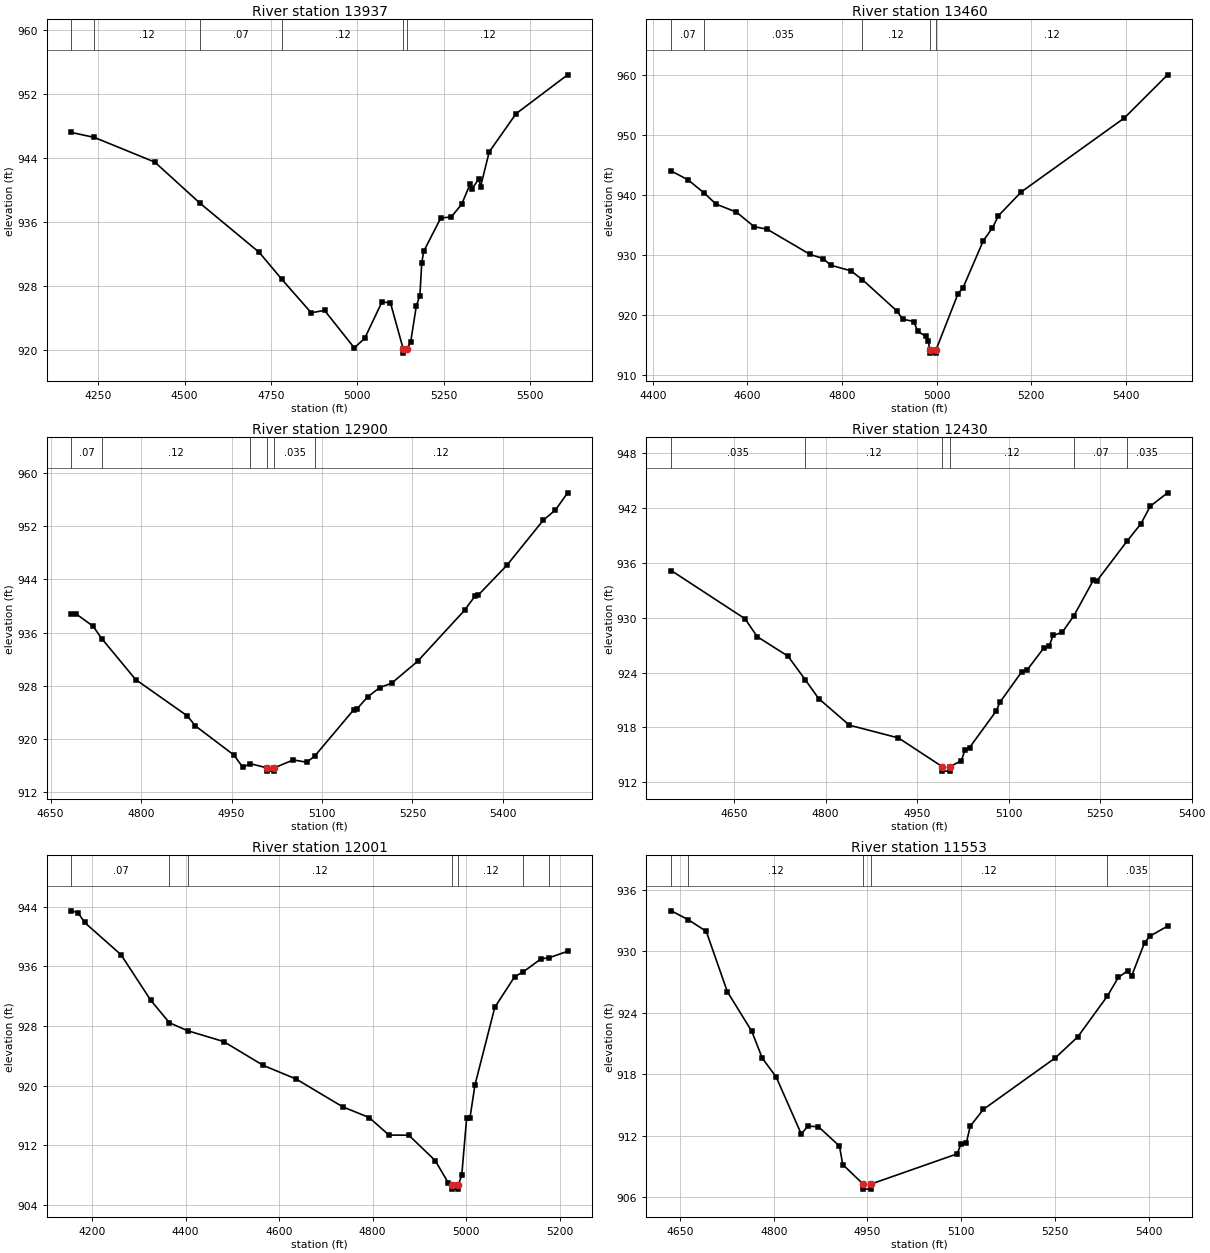
Type RM Length L Ch R = 1 ,13937   ,477,477,477
BEGIN DESCRIPTION:
Upper Dry Comal Tributary 3 27.0
END DESCRIPTION:
XS GIS Cut Line= 3
      2212236.56     13815546.83      2211526.95     13815336.84
      2210875.23     13815090.64
#Sta/Elev= 30
    4172  947.17  4238.6  946.55  4413.5  943.47  4544.4  938.33  4715.9  932.19
  4781.6  928.81  4866.4  924.64  4904.9  924.94  4991.1  920.26  5021.3  921.45
    5071  925.98  5095.8  925.89  5132.9   920.1  5133.4   919.6  5144.2   920.1
  5154.6  921.05  5170.7  925.49    5181  926.79  5186.4  930.85    5192  932.31
  5241.4  936.48  5271.6  936.61  5301.8  938.18  5326.6  940.74  5331.9  940.11
  5351.4  941.38  5356.8  940.41  5381.6  944.73  5459.3  949.51  5608.7  954.37
#Mann= 6 ,-1 , 0
    4172     .07       0  4238.6     .12       0  4544.4     .07       0
  4781.6     .12       0  5132.9     .05       0  5144.2     .12       0
Bank Sta=5132.9,5144.2
XS Rating Curve= 0 ,0
Exp/Cntr=0.3,0.1

Type RM Length L Ch R = 1 ,13460   ,560,560,560
BEGIN DESCRIPTION:
Upper Dry Comal Tributary 3 26.0
END DESCRIPTION:
XS GIS Cut Line= 3
      2212121.76     13815186.59      2211701.12     13814949.42
      2211169.31     13814752.78
#Sta/Elev= 30
  4438.9  944.02    4474  942.57  4508.5  940.35  4533.3  938.51  4576.6  937.16
  4614.2  934.73  4641.8   934.3  4732.6  930.09    4760  929.41    4776  928.29
  4818.8  927.36  4843.2  925.88  4916.1  920.65  4928.3  919.28    4952  918.88
  4960.3  917.23    4977  916.44  4982.4  915.66  4985.9   914.1  4986.4   913.6
  4998.2   913.6  4998.7   914.1  5045.6  923.54  5056.3  924.56  5098.9  932.37
  5118.4  934.53  5130.9  936.55  5179.2  940.53  5397.4  952.89  5488.8   960.1
#Mann= 5 ,-1 , 0
  4438.9     .07       0  4508.5    .035       0  4843.2     .12       0
  4985.9     .05       0  4998.7     .12       0
Bank Sta=4985.9,4998.7
XS Rating Curve= 0 ,0
Exp/Cntr=0.3,0.1

Type RM Length L Ch R = 1 ,12900   ,470,470,470
BEGIN DESCRIPTION:
Upper Dry Comal Tributary 3 25.0
END DESCRIPTION:
XS GIS Cut Line= 3
        2212125.     13814725.01        2211925.       13814475.
      2211424.96       13814525.
#Sta/Elev= 30
  4684.5  938.84  4691.7  938.85  4720.5  936.95    4735  935.07    4791  928.91
  4876.6  923.43  4890.2  921.91  4954.2   917.5  4968.6  915.68    4981  916.22
  5008.3  915.59  5008.8  915.09  5020.6  915.09  5021.1  915.59  5052.4  916.78
    5075  916.43  5088.5  917.42  5152.9  924.38  5157.9  924.46  5175.5  926.28
  5195.6  927.68  5215.7  928.37  5258.4  931.65  5336.3  939.35  5353.9  941.53
  5358.9  941.63  5406.7  946.16    5467  952.96  5487.1  954.49  5507.2  957.07
#Mann= 6 ,-1 , 0
  4684.5     .07       0    4735     .12       0    4981    .035       0
  5008.3    .035       0  5021.1    .035       0  5088.5     .12       0
Bank Sta=5008.3,5021.1
XS Rating Curve= 0 ,0
Exp/Cntr=0.3,0.1

Type RM Length L Ch R = 1 ,12430   ,429,429,429
BEGIN DESCRIPTION:
Upper Dry Comal Tributary 3 24.0
END DESCRIPTION:
XS GIS Cut Line= 3
        2212275.     13814575.02        2212225.       13814125.
      2211925.04     13813925.02
#Sta/Elev= 30
  4547.2  935.16    4668  929.89  4688.1  927.93  4738.4   925.8  4766.6  923.23
  4788.7  921.16    4839  918.25  4919.5  916.85    4991  913.72  4991.5  913.22
  5003.4  913.22  5003.9  913.72  5022.5  914.35  5028.5  915.54    5036   915.8
  5079.6  919.79  5085.6  920.74  5121.7  924.11  5130.7  924.32  5157.7  926.69
  5166.7  926.94  5172.8  928.06  5187.8  928.41  5206.9  930.21  5238.9  934.11
  5244.9  934.05  5293.7  938.35    5317   940.3    5332  942.19  5360.5  943.67
#Mann= 6 ,-1 , 0
  4547.2    .035       0  4766.6     .12       0    4991     .05       0
  5003.9     .12       0  5206.9     .07       0  5293.7    .035       0
Bank Sta=4991,5003.9
XS Rating Curve= 0 ,0
Exp/Cntr=0.3,0.1

Type RM Length L Ch R = 1 ,12001   ,448,448,448
BEGIN DESCRIPTION:
Upper Dry Comal Tributary 3 23.0
END DESCRIPTION:
XS GIS Cut Line= 3
      2213175.01     13814525.01        2212575.       13813925.
      2212424.98     13813774.98
#Sta/Elev= 30
    4156  943.45  4170.2  943.21  4184.3  941.89  4262.1  937.57  4325.7  931.46
  4365.5  928.45  4404.3  927.38  4481.3  925.93  4566.1  922.73  4636.8  920.89
  4735.8  917.18  4792.4  915.74  4834.8  913.39  4877.3  913.37  4933.8  909.96
  4962.1  906.93  4969.8  906.64  4970.3  906.14  4982.2  906.14  4982.7  906.64
  4990.4     908    5001  915.73  5008.1  915.73  5018.7  920.12  5061.1  930.52
  5103.5  934.62  5121.7  935.26  5160.1  937.02    5177  937.15  5216.7  938.03
#Mann= 7 ,-1 , 0
    4156     .07       0  4365.5    .035       0  4404.3     .12       0
  4969.8     .05       0  4982.7     .12       0  5121.7     .07       0
    5177    .035       0
Bank Sta=4969.8,4982.7
XS Rating Curve= 0 ,0
Exp/Cntr=0.3,0.1

Type RM Length L Ch R = 1 ,11553   ,452,452,452
BEGIN DESCRIPTION:
Upper Dry Comal Tributary 3 22.0
END DESCRIPTION:
XS GIS Cut Line= 3
      2213375.02     13814025.01        2213025.       13813925.
      2212675.03     13813675.02
#Sta/Elev= 30
  4636.1  933.94  4663.3  933.07    4692  931.94  4725.8  926.05  4764.8   922.2
  4781.7  919.57  4803.8  917.75  4844.1  912.17  4854.5  912.94  4871.4  912.89
  4905.2     911  4910.4   909.2  4942.9   907.3  4943.4   906.8  4955.5   906.8
    4956   907.3  5093.5  910.24  5099.7   911.2  5108.3  911.33  5114.4  912.93
  5135.3  914.57  5250.8  919.61  5286.5  921.65  5333.7  925.61  5351.6  927.46
  5366.3  928.08  5372.5  927.55  5393.4  930.83    5402  931.47  5430.2  932.45
#Mann= 5 ,-1 , 0
  4636.1     .07       0  4663.3     .12       0  4942.9     .05       0
    4956     .12       0  5333.7    .035       0
Bank Sta=4942.9,4956
XS Rating Curve= 0 ,0
Exp/Cntr=0.3,0.1