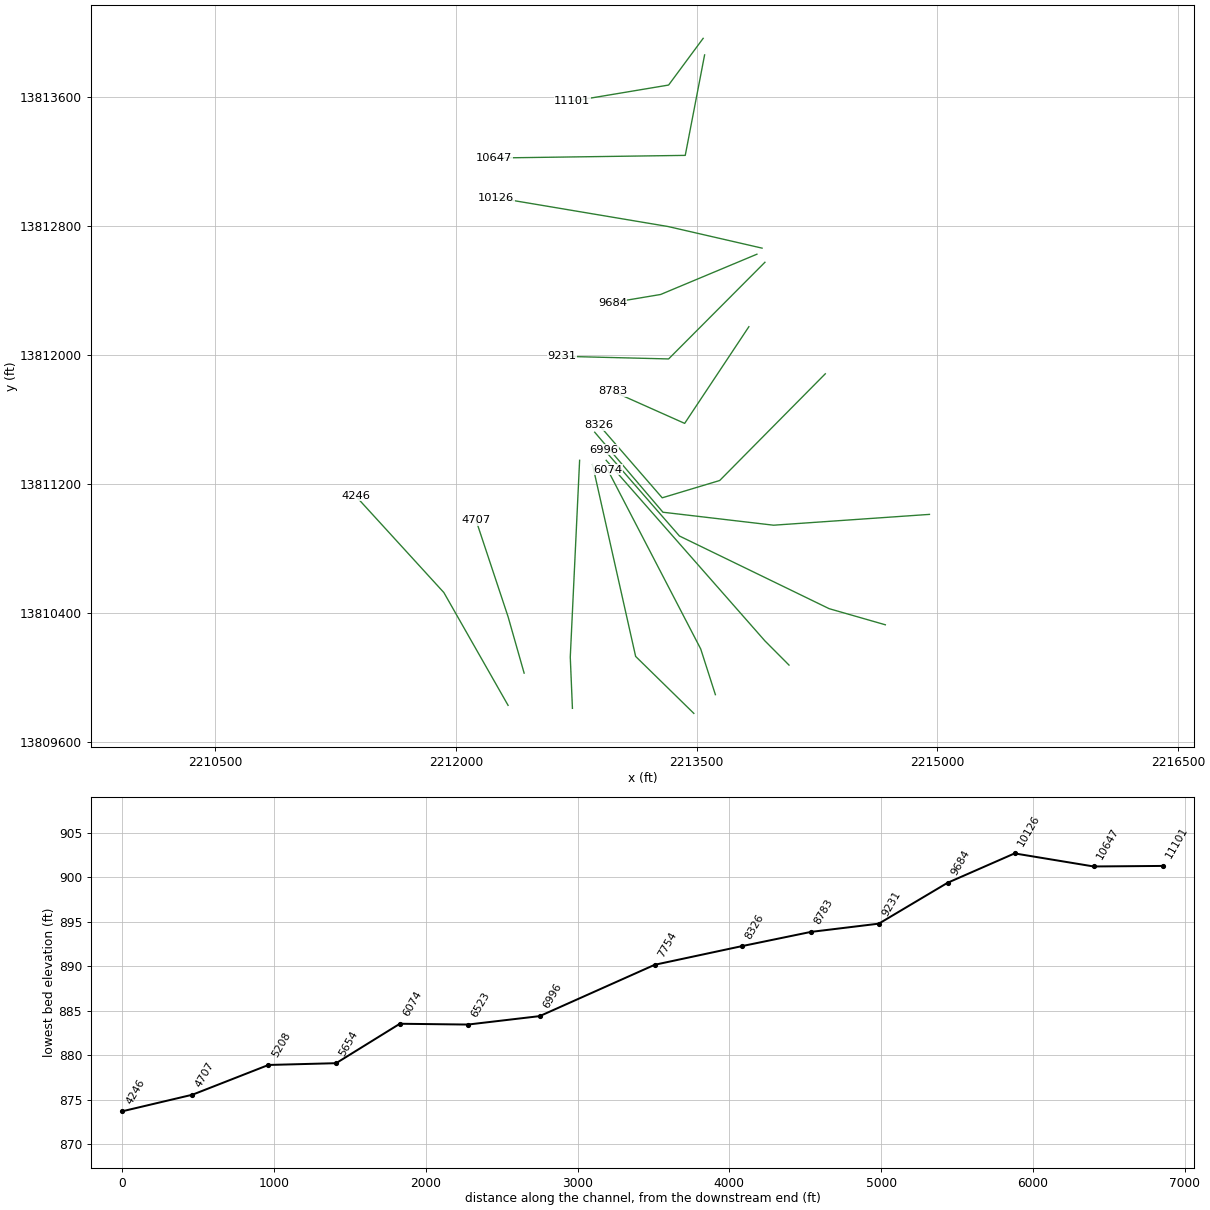
HEC-RAS study Upper Dry Comal Tributary 3.prj: Upper Dry Comal Tributary 3 Base Level Engineering

--- Upper Dry Comal Tributary 3.g01 (geometry) --- (continued)

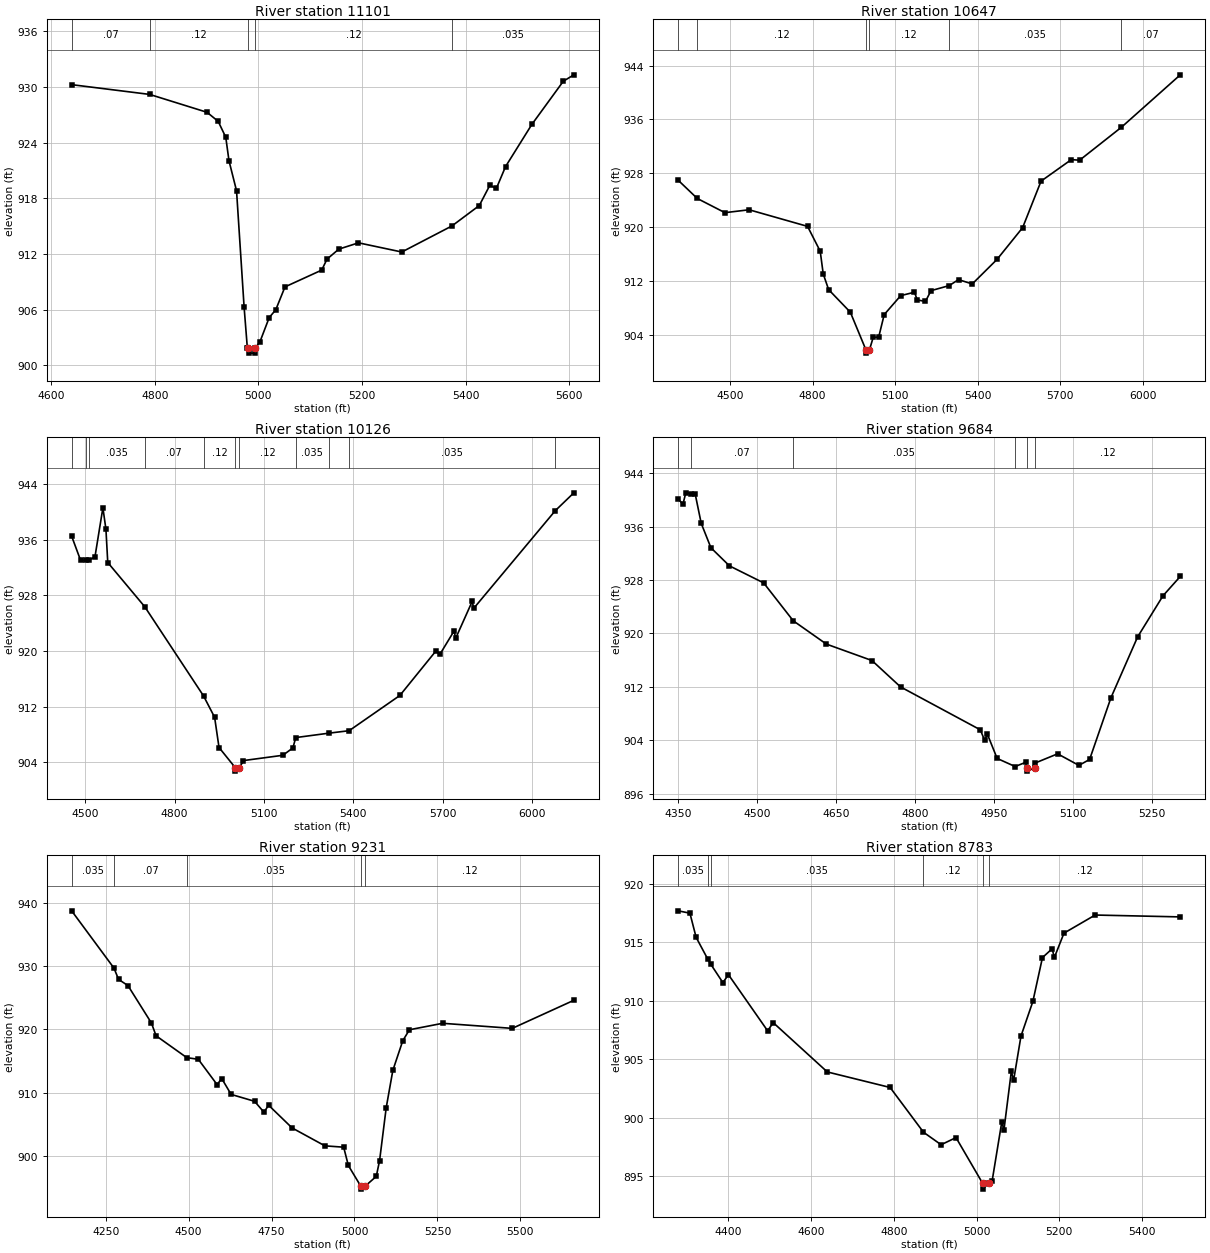
Type RM Length L Ch R = 1 ,11101   ,454,454,454
BEGIN DESCRIPTION:
Upper Dry Comal Tributary 3 21.0
END DESCRIPTION:
XS GIS Cut Line= 3
      2213540.28      13813964.9        2213325.       13813675.
      2212724.97     13813574.99
#Sta/Elev= 30
  4639.6  930.24  4790.1  929.19    4901  927.26  4922.5  926.28  4937.1  924.57
  4943.3  922.04  4957.9   918.8  4972.5  906.26  4978.8  901.82  4980.6   901.8
  4981.1   901.3  4993.2   901.3  4993.7   901.8  5003.2  902.54    5021  905.14
  5033.6  905.97  5051.4  908.44  5122.3  910.25  5132.5  911.43  5155.3  912.51
  5193.3  913.19  5276.9   912.2  5373.7  915.01  5426.5  917.21  5446.8  919.39
  5459.4  919.05  5477.2  921.41  5527.9  925.95  5588.7  930.61    5609   931.3
#Mann= 5 ,-1 , 0
  4639.6     .07       0  4790.1     .12       0  4980.6     .05       0
  4993.7     .12       0  5373.7    .035       0
Bank Sta=4980.6,4993.7
XS Rating Curve= 0 ,0
Exp/Cntr=0.3,0.1

Type RM Length L Ch R = 1 ,10647   ,521,521,521
BEGIN DESCRIPTION:
Upper Dry Comal Tributary 3 20.0
END DESCRIPTION:
XS GIS Cut Line= 3
      2213549.26     13813862.04       2213428.7     13813238.42
      2212239.07     13813222.12
#Sta/Elev= 30
  4311.1  926.96  4380.8  924.24  4481.2  922.13  4569.2  922.56  4781.5  920.09
  4827.5  916.39  4838.4  913.02  4858.1  910.68  4936.9  907.33  4993.4  901.74
  4993.9  901.24  5006.5  901.74    5020  903.58    5040  903.63    5060  906.97
    5120  909.79    5170   910.3    5180  909.15    5210  908.93    5230  910.53
    5296  911.28    5330  912.17    5380  911.53    5470  915.18    5563   919.9
    5630  926.82    5740  930.02    5770  929.93  5922.2  934.84    6136  942.63
#Mann= 6 ,-1 , 0
  4311.1     .07       0  4380.8     .12       0  4993.4     .05       0
  5006.5     .12       0    5296    .035       0  5922.2     .07       0
Bank Sta=4993.4,5006.5
XS Rating Curve= 0 ,0
Exp/Cntr=0.3,0.1

Type RM Length L Ch R = 1 ,10126   ,442,442,442
BEGIN DESCRIPTION:
Upper Dry Comal Tributary 3 19.0
END DESCRIPTION:
XS GIS Cut Line= 3
      2213907.23     13812662.75      2213321.04     13812796.99
      2212251.58     13812975.98
#Sta/Elev= 30
  4454.5  936.53  4484.7  933.03  4502.9  933.05  4511.3  933.03  4532.8  933.57
  4559.4  940.62  4569.6  937.51  4575.7  932.74  4700.1  926.36  4897.3  913.53
  4934.4  910.46  4949.2  906.11  5003.7  903.21  5004.2  902.71  5017.8  903.21
  5031.3  904.23  5163.4  904.99  5197.1  906.05  5206.8  907.54  5317.2  908.17
    5386  908.53  5556.2   913.6  5677.7  920.03  5690.6  919.52  5738.4   922.9
  5743.4  921.81  5799.1  927.15  5804.1  926.14  6078.1  940.21  6140.2  942.77
#Mann= 11 ,-1 , 0
  4454.5    .035       0  4502.9     .07       0  4511.3    .035       0
  4700.1     .07       0  4897.3     .12       0  5003.7     .05       0
  5017.8     .12       0  5206.8    .035       0  5317.2     .12       0
    5386    .035       0  6078.1     .07       0
Bank Sta=5003.7,5017.8
XS Rating Curve= 0 ,0
Exp/Cntr=0.3,0.1

Type RM Length L Ch R = 1 ,9684    ,453,453,453
BEGIN DESCRIPTION:
Upper Dry Comal Tributary 3 18.0
END DESCRIPTION:
XS GIS Cut Line= 3
        2213875.       13812625.        2213275.       13812375.
      2212975.03     13812325.01
#Sta/Elev= 30
  4350.4  940.12  4359.6  939.36    4365  941.05    4375  940.94  4382.9  940.85
  4394.3  936.48  4412.7  932.83  4447.9  930.12  4512.9  927.57  4569.1   921.9
  4632.1  918.41  4718.7  915.95  4772.9  912.01  4924.6  905.58  4932.7  904.01
  4938.1   904.9  4956.5   901.3  4990.7  900.09  5010.5  900.71  5013.6   899.9
  5014.1   899.4  5027.7   899.9  5028.3   900.6  5071.4  901.99  5111.9  900.26
  5132.2  901.15  5172.7  910.38  5223.4  919.49  5271.6  925.64  5304.5  928.54
#Mann= 6 ,-1 , 0
  4350.4    .035       0    4375     .07       0  4569.1    .035       0
  4990.7     .12       0  5013.6     .05       0  5027.7     .12       0
Bank Sta=5013.6,5027.7
XS Rating Curve= 0 ,0
Exp/Cntr=0.3,0.1

Type RM Length L Ch R = 1 ,9231    ,448,448,448
BEGIN DESCRIPTION:
Upper Dry Comal Tributary 3 17.0
END DESCRIPTION:
XS GIS Cut Line= 3
      2213925.03     13812575.03        2213325.       13811975.
      2212659.38     13811991.49
#Sta/Elev= 30
  4147.1  938.72  4274.7  929.68  4288.6   927.9  4316.9  926.92  4387.6  921.02
  4401.7     919  4494.3  915.55    4529  915.29  4585.6   911.3  4599.7  912.25
    4628  909.75  4698.7  908.66    4727  906.94  4741.1  908.04  4811.8  904.46
  4910.8  901.63  4967.4  901.42  4981.5  898.53  5018.6   895.3  5019.1   894.8
  5032.8   895.3  5065.7  896.81  5075.7   899.3  5095.7  907.66  5115.7  913.54
  5145.7  918.23  5165.7  919.95  5265.8  920.97  5475.8  920.17  5661.5   924.6
#Mann= 5 ,-1 , 0
  4147.1    .035       0  4274.7     .07       0  4494.3    .035       0
  5018.6    .035       0  5032.8     .12       0
Bank Sta=5018.6,5032.8
XS Rating Curve= 0 ,0
Exp/Cntr=0.3,0.1

Type RM Length L Ch R = 1 ,8783    ,457,457,457
BEGIN DESCRIPTION:
Upper Dry Comal Tributary 3 16.0
END DESCRIPTION:
XS GIS Cut Line= 3
      2213824.99     13812174.98        2213425.       13811575.
      2212975.03     13811774.99
#Sta/Elev= 30
  4278.9  917.69  4307.4  917.49  4322.4  915.42  4350.2  913.58  4357.6  913.13
    4387  911.55  4400.6  912.22  4495.2  907.42  4508.7  908.12  4639.4   903.9
  4791.2  902.57  4871.8  898.74  4914.4  897.67  4950.4  898.28  5014.7  894.37
  5015.2  893.87    5029  894.37  5037.6  894.55  5060.9  899.59  5066.3  898.95
  5084.1  903.95  5089.6  903.18  5107.4  906.97  5136.1  909.93  5159.3  913.69
  5182.6  914.44  5188.1   913.7  5211.3  915.78  5286.6  917.33  5492.4  917.17
#Mann= 6 ,-1 , 0
  4278.9    .035       0  4350.2     .07       0  4357.6    .035       0
  4871.8     .12       0  5014.7     .05       0    5029     .12       0
Bank Sta=5014.7,5029
XS Rating Curve= 0 ,0
Exp/Cntr=0.3,0.1

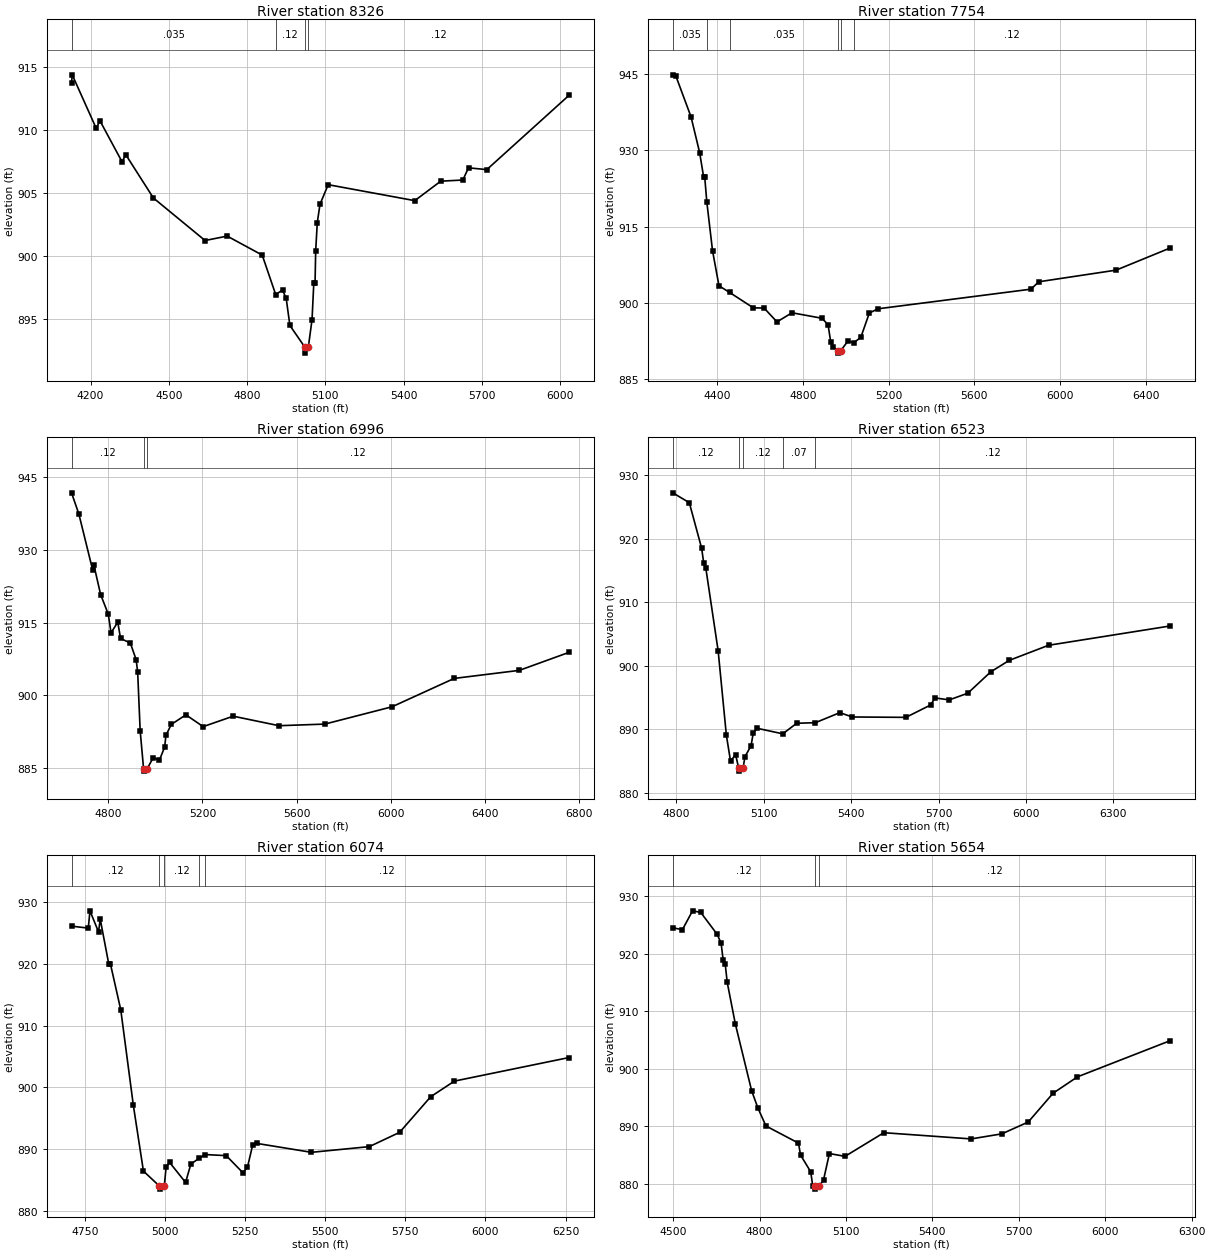
Type RM Length L Ch R = 1 ,8326    ,572,572,572
BEGIN DESCRIPTION:
XS7917
END DESCRIPTION:
XS GIS Cut Line= 4
      2214301.07      13811882.8      2213643.23     13811220.48
      2213285.24     13811113.08      2212891.45     13811565.04
#Sta/Elev= 30
  4126.9  913.78  4129.6   914.4  4221.6  910.14  4235.7  910.75  4320.6  907.48
  4334.7  908.05  4440.8   904.6  4638.8  901.22  4723.6  901.57  4857.9  900.06
  4909.6  896.92  4935.7  897.28  4949.9  896.61    4964  894.46  5020.5  892.76
    5021  892.26  5034.8  892.76  5048.9  894.92  5055.6  897.81  5060.4  897.81
  5062.9  900.39    5069  902.64  5079.4   904.1  5110.8  905.66  5442.7  904.39
  5542.4  905.94  5626.9  906.03  5648.8     907    5719  906.86  6033.6  912.76
#Mann= 4 ,-1 , 0
  4126.9    .035       0  4909.6     .12       0  5020.5     .05       0
  5034.8     .12       0
Bank Sta=5020.5,5034.8
XS Rating Curve= 0 ,0
Exp/Cntr=0.3,0.1

Type RM Length L Ch R = 1 ,7754    ,758,758,758
BEGIN DESCRIPTION:
XS7916
END DESCRIPTION:
XS GIS Cut Line= 4
      2214949.86     13811010.16      2213978.85     13810943.04
      2213289.71     13811023.59      2212864.76     13811520.11
#Sta/Elev= 30
  4193.3  944.86  4208.2  944.56  4278.4  936.59  4318.5  929.58    4337  924.81
  4342.1  924.84  4351.8  919.94  4378.6  910.31  4408.7   903.4  4458.1   902.1
  4569.1  899.07  4619.2  899.03  4679.3  896.31  4749.5   898.1  4889.8  897.02
  4917.8  895.73  4929.9  892.43  4939.9  891.42  4962.8  890.67  4963.3  890.17
  4977.2  890.67  5010.1  892.52    5037   892.2  5070.5  893.26  5110.3  898.05
  5150.4  898.88  5864.7  902.74  5900.7  904.19  6261.8  906.48    6514  910.83
#Mann= 6 ,-1 , 0
  4193.3    .035       0  4351.8     .12       0  4458.1    .035       0
  4962.8    .035       0  4977.2    .035       0    5037     .12       0
Bank Sta=4962.8,4977.2
XS Rating Curve= 0 ,0
Exp/Cntr=0.3,0.1

Type RM Length L Ch R = 1 ,6996    ,473,473,473
BEGIN DESCRIPTION:
Upper Dry Comal Tributary 3 15.0
END DESCRIPTION:
XS GIS Cut Line= 4
      2214675.04     13810324.99        2214325.       13810425.
      2213392.64     13810875.91      2212924.06     13811411.43
#Sta/Elev= 30
  4644.3  941.73  4675.5  937.35    4734  925.83  4739.2  926.83  4767.8  920.77
  4800.3  916.73    4812  912.89  4840.6  915.08  4852.3  911.73  4893.9  910.78
  4918.6  907.36  4925.1  904.75  4935.6  892.75  4950.1  884.89  4950.6  884.39
  4965.3  884.89  4991.5  887.19  5016.9  886.61  5039.5  889.33    5045  891.74
  5067.6  894.01  5129.8  895.99  5203.2  893.56  5330.5  895.71    5525  893.75
  5719.3  894.08    6005  897.65  6268.7  903.49  6545.1  905.15  6755.6  908.85
#Mann= 3 ,-1 , 0
  4644.3     .12       0  4950.1     .05       0  4965.3     .12       0
Bank Sta=4950.1,4965.3
XS Rating Curve= 0 ,0
Exp/Cntr=0.3,0.1

Type RM Length L Ch R = 1 ,6523    ,449,449,449
BEGIN DESCRIPTION:
Upper Dry Comal Tributary 3 14.0
END DESCRIPTION:
XS GIS Cut Line= 3
        2214075.       13810075.        2213925.       13810225.
      2212936.23     13811345.75
#Sta/Elev= 30
  4787.9  927.23  4844.5  925.68  4886.9   918.5    4894  916.17    4901  915.44
  4943.5  902.36  4971.7  889.09  4985.9  885.04  5003.4  886.02  5013.8  883.94
  5014.3  883.44    5029  883.94  5035.6  885.72  5056.5  887.45    5064  889.47
  5078.3  890.17  5165.2  889.31    5213  890.97    5277  891.06    5361  892.64
  5403.7  891.96  5587.7   891.9  5673.1  893.86  5687.3  894.96  5736.6  894.65
  5800.2   895.7  5878.9  899.06  5942.5  900.87  6077.2  903.24  6494.6  906.28
#Mann= 5 ,-1 , 0
  4787.9     .12       0  5013.8     .05       0    5029     .12       0
  5165.2     .07       0    5277     .12       0
Bank Sta=5013.8,5029
XS Rating Curve= 0 ,0
Exp/Cntr=0.3,0.1

Type RM Length L Ch R = 1 ,6074    ,420,420,420
BEGIN DESCRIPTION:
Upper Dry Comal Tributary 3 13.0
END DESCRIPTION:
XS GIS Cut Line= 3
       2213616.4     13809891.39        2213525.       13810175.
      2212945.15      13811287.6
#Sta/Elev= 30
  4707.8  926.11  4760.1  925.79  4765.3  928.59  4792.1  925.17  4797.4  927.24
  4824.2  919.93  4829.4  919.95  4861.5  912.56  4900.7  897.12  4932.2  886.45
  4982.1  884.03  4982.6  883.53  4997.4  884.03  5003.1  887.15    5014  887.85
  5063.8  884.61  5080.3  887.59  5105.8  888.51  5124.9  889.13  5190.8  888.95
  5242.6  886.19    5257  887.08  5273.5  890.73  5287.7  890.92  5456.8  889.49
  5637.3  890.41  5731.9  892.72    5829  898.49    5903  901.02  6260.4  904.83
#Mann= 5 ,-1 , 0
  4707.8     .12       0  4982.1     .05       0  4997.4     .12       0
  5105.8     .07       0  5124.9     .12       0
Bank Sta=4982.1,4997.4
XS Rating Curve= 0 ,0
Exp/Cntr=0.3,0.1

Type RM Length L Ch R = 1 ,5654    ,446,446,446
BEGIN DESCRIPTION:
Upper Dry Comal Tributary 3 12.0
END DESCRIPTION:
XS GIS Cut Line= 3
      2213482.11     13809775.11      2213119.67     13810128.61
      2212851.18     13811318.92
#Sta/Elev= 30
  4498.9  924.48  4532.2  924.14  4567.4  927.42  4595.7  927.15  4652.3  923.38
  4666.5  921.82  4673.6  918.92  4680.6  918.26  4687.8  914.99  4716.1  907.74
  4772.6  896.17  4793.8  893.24  4822.1  890.06  4935.2  887.08  4942.2  885.02
  4977.7  882.09  4984.6  879.67  4991.1  879.59  4991.6  879.09  5006.4  879.59
    5022  880.66  5042.5  885.27  5096.7  884.78  5231.5  888.89  5534.5  887.81
  5641.1  888.69  5732.6  890.74  5819.1  895.75  5903.6  898.59  6225.4  904.87
#Mann= 3 ,-1 , 0
  4498.9     .12       0  4991.1     .05       0  5006.4     .12       0
Bank Sta=4991.1,5006.4
XS Rating Curve= 0 ,0
Exp/Cntr=0.3,0.1

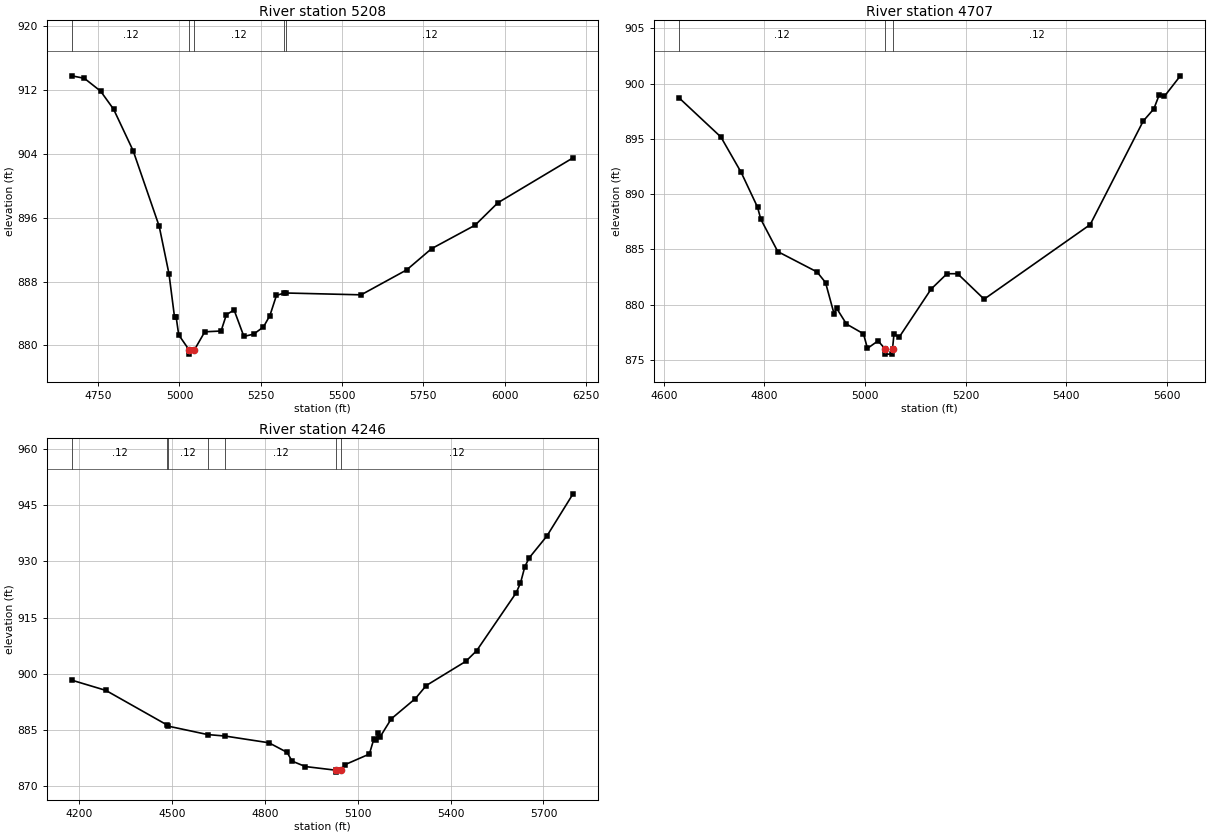
Type RM Length L Ch R = 1 ,5208    ,501,501,501
BEGIN DESCRIPTION:
Upper Dry Comal Tributary 3 11.0
END DESCRIPTION:
XS GIS Cut Line= 3
      2212725.88     13809806.37      2212712.45     13810124.13
      2212770.63      13811345.8
#Sta/Elev= 30
  4668.9  913.81  4707.6   913.5  4757.6  911.89  4797.6  909.62  4857.7  904.41
  4937.8  894.93  4967.8  888.98  4984.9  883.54  4989.9  883.54  4997.8   881.3
  5030.2  879.39  5030.7  878.89  5045.5  879.39  5077.9  881.69    5128  881.79
  5144.3  883.84    5168  884.43  5198.1  881.11  5228.1   881.4  5258.1  882.29
  5278.1  883.73  5298.2  886.26  5322.9  886.56  5327.8  886.56  5558.5  886.33
  5698.6  889.46    5775  892.12  5908.9  895.07  5978.9  897.88    6210  903.52
#Mann= 5 ,-1 , 0
  4668.9     .12       0  5030.2     .05       0  5045.5     .12       0
  5322.9     .07       0  5327.8     .12       0
Bank Sta=5030.2,5045.5
XS Rating Curve= 0 ,0
Exp/Cntr=0.3,0.1

Type RM Length L Ch R = 1 ,4707    ,461,461,461
BEGIN DESCRIPTION:
Upper Dry Comal Tributary 3 10.0
END DESCRIPTION:
XS GIS Cut Line= 3
      2212424.99     13810025.04        2212325.       13810375.
      2212125.01     13810974.98
#Sta/Elev= 30
  4630.2  898.71  4713.4  895.17  4753.7  891.97  4786.2  888.83  4792.7  887.74
  4826.5  884.81  4904.5  882.97  4921.4  882.01  4938.3  879.19  4943.5  879.68
    4963  878.26  4996.8  877.38  5004.7  876.06  5025.8  876.74  5039.2  876.04
  5039.7  875.54  5054.1  875.54  5054.6  876.04  5057.4  877.35    5068  877.09
  5131.2  881.42  5162.8  882.81  5183.9  882.81  5236.6  880.51  5447.4  887.25
  5552.8  896.61  5573.9  897.71  5584.5  898.97    5595  898.85  5626.6   900.7
#Mann= 3 ,-1 , 0
  4630.2     .12       0  5039.2     .05       0  5054.6     .12       0
Bank Sta=5039.2,5054.6
XS Rating Curve= 0 ,0
Exp/Cntr=0.3,0.1

Type RM Length L Ch R = 1 ,4246    ,455,455,455
BEGIN DESCRIPTION:
Upper Dry Comal Tributary 3 9.0
END DESCRIPTION:
XS GIS Cut Line= 3
        2212325.       13809825.        2211925.       13810525.
      2211374.98     13811125.02
#Sta/Elev= 30
  4175.5  898.26  4285.6  895.53  4484.5  886.24  4486.7  885.98  4614.6  883.72
  4671.3  883.32  4812.6  881.53  4871.6  878.96  4887.4  876.63  4930.6  875.17
  5030.3  874.18  5030.8  873.68  5045.9  874.18  5059.7  875.71  5137.4  878.51
  5151.6  882.45  5158.4  882.34  5165.8  884.01  5172.6  883.17  5208.3  887.93
    5286  893.33  5321.2  896.82  5448.8  903.27    5484  906.12  5611.6  921.57
  5625.8  924.21    5640  928.63  5654.2  930.97  5710.9  936.75  5795.7  948.06
#Mann= 7 ,-1 , 0
  4175.5     .12       0  4484.5     .07       0  4486.7     .12       0
  4614.6     .07       0  4671.3     .12       0  5030.3     .05       0
  5045.9     .12       0
Bank Sta=5030.3,5045.9
XS Rating Curve= 0 ,0
Exp/Cntr=0.3,0.1