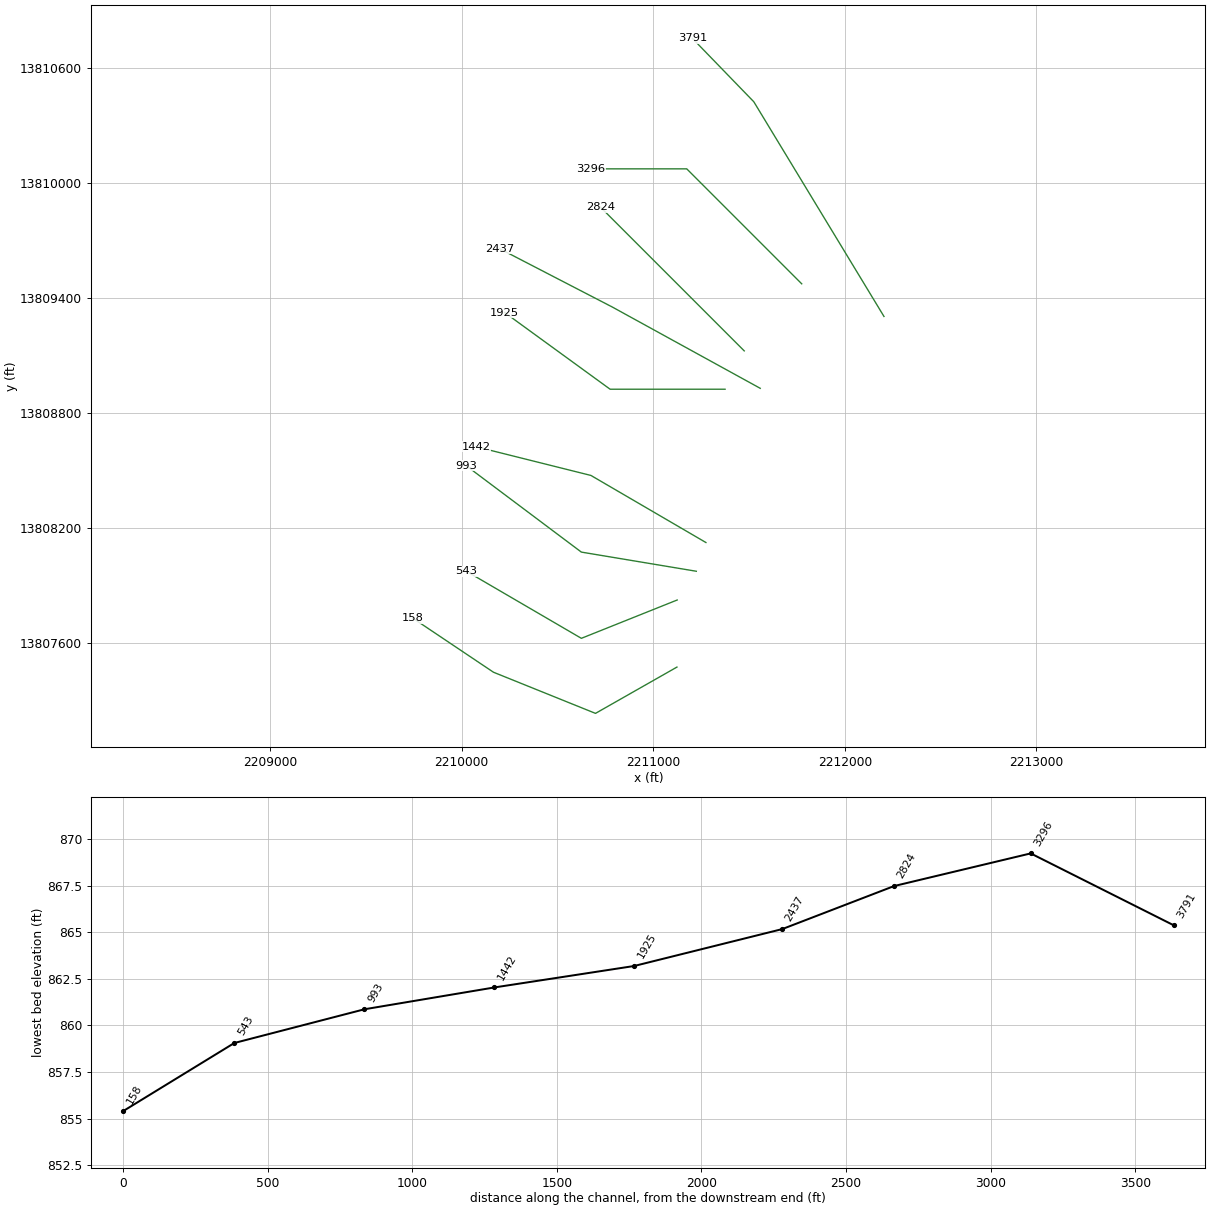
HEC-RAS study Upper Dry Comal Tributary 3.prj: Upper Dry Comal Tributary 3 Base Level Engineering

--- Upper Dry Comal Tributary 3.g01 (geometry) --- (continued)

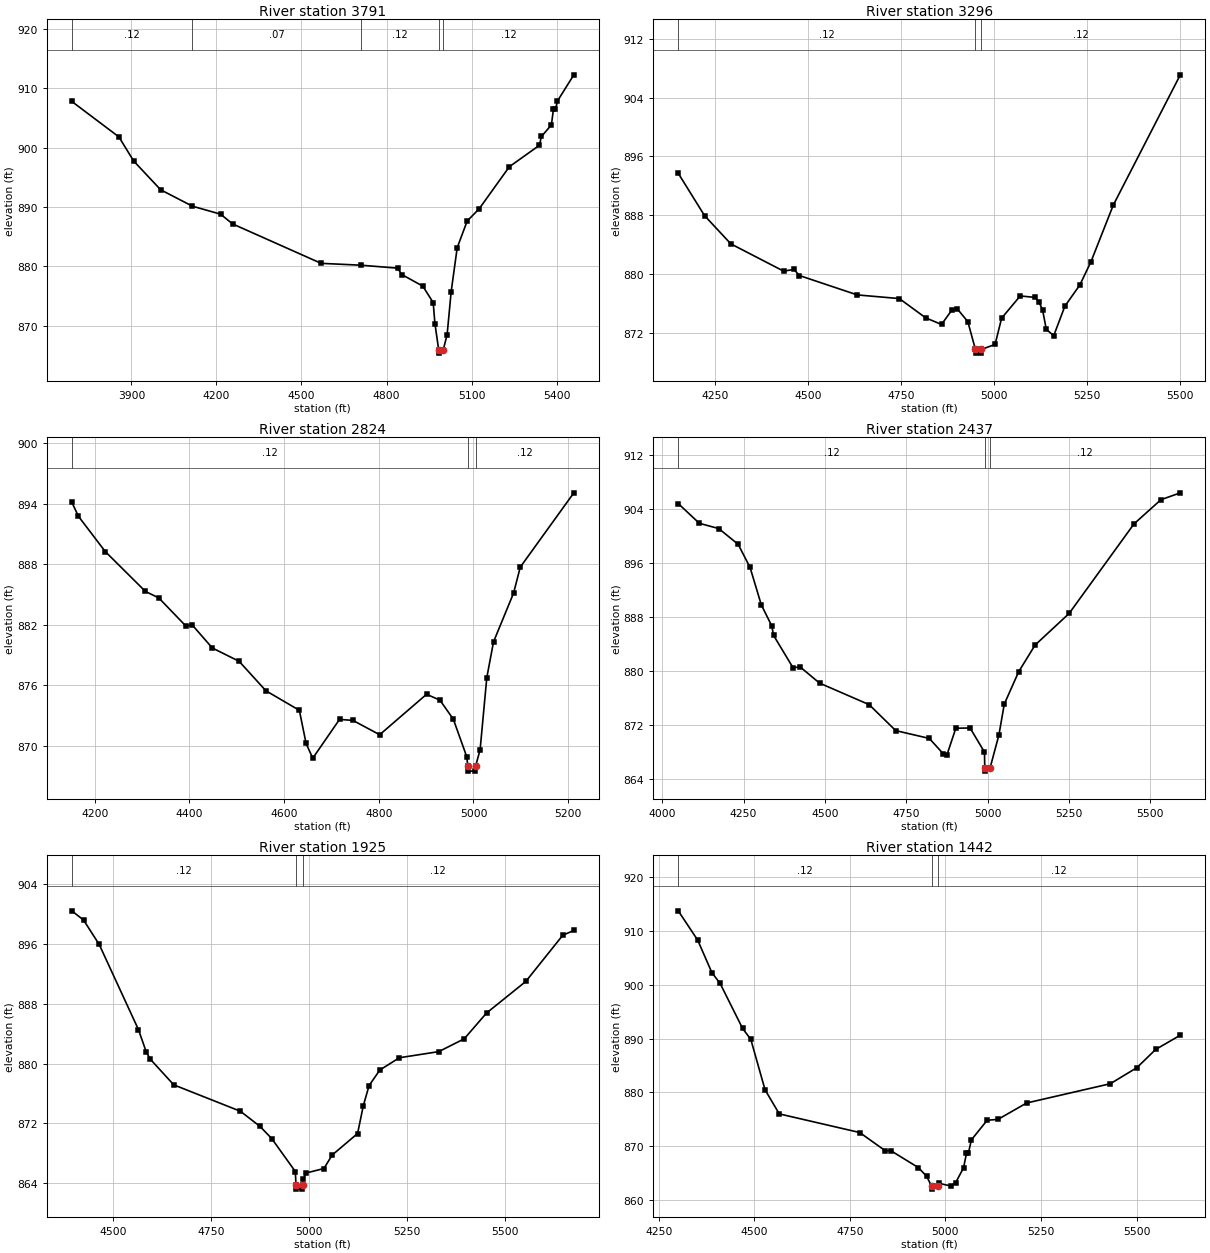
Type RM Length L Ch R = 1 ,3791    ,495,495,495
BEGIN DESCRIPTION:
Upper Dry Comal Tributary 3 8.0
END DESCRIPTION:
XS GIS Cut Line= 3
      2212204.22     13809304.75        2211525.       13810425.
      2211204.23     13810756.13
#Sta/Elev= 30
  3689.7  907.79  3855.9  901.81  3908.2  897.74  4003.2   892.9  4115.4  890.13
  4214.5  888.79  4257.2  887.14  4569.4   880.5  4709.1  880.19  4838.9  879.69
  4854.4   878.6    4928  876.66  4964.7  873.88  4970.7  870.36  4984.2  865.87
  4984.7  865.37  4999.8  865.87  5013.8  868.49    5028  875.71  5049.3  883.13
  5084.5  887.63    5127   889.7  5233.2  896.78  5339.2  900.39  5346.4  901.88
  5381.6  903.82  5388.8  906.47  5395.8  906.46    5403  907.86  5460.8  912.27
#Mann= 5 ,-1 , 0
  3689.7     .12       0  4115.4     .07       0  4709.1     .12       0
  4984.2     .05       0  4999.8     .12       0
Bank Sta=4984.2,4999.8
XS Rating Curve= 0 ,0
Exp/Cntr=0.3,0.1

Type RM Length L Ch R = 1 ,3296    ,472,472,472
BEGIN DESCRIPTION:
Upper Dry Comal Tributary 3 7.0
END DESCRIPTION:
XS GIS Cut Line= 3
      2211774.97     13809475.03        2211175.       13810075.
      2210674.99       13810075.
#Sta/Elev= 30
  4151.5   893.7  4222.2  887.93  4292.9  884.09  4434.3  880.39  4462.6  880.61
  4476.7  879.79  4632.3  877.15  4745.4  876.65  4816.1  874.03  4858.6  873.13
  4886.9  875.12    4901  875.25  4929.3  873.51  4949.7  869.73  4950.2  869.23
  4964.9  869.23  4965.4  869.73  5002.5  870.41    5020  873.98    5070  877.01
    5110  876.81    5120  876.21    5130  875.13    5140  872.47    5160   871.6
    5190  875.62    5230  878.49    5260  881.66    5320  889.37    5500  907.09
#Mann= 3 ,-1 , 0
  4151.5     .12       0  4949.7     .05       0  4965.4     .12       0
Bank Sta=4949.7,4965.4
XS Rating Curve= 0 ,0
Exp/Cntr=0.3,0.1

Type RM Length L Ch R = 1 ,2824    ,387,387,387
BEGIN DESCRIPTION:
Upper Dry Comal Tributary 3 6.0
END DESCRIPTION:
XS GIS Cut Line= 3
        2211475.       13809125.        2210875.       13809725.
      2210724.97     13809875.03
#Sta/Elev= 30
  4151.4  894.16  4165.5  892.75  4222.1  889.26    4307   885.3  4335.2  884.66
  4391.8   881.9    4406  881.97  4448.4  879.69    4505  878.37  4561.5  875.45
  4632.2  873.51  4646.4  870.23  4660.5  868.76  4717.1  872.61  4745.4  872.51
  4801.9  871.09  4900.9   875.1  4929.2  874.52  4957.5  872.63  4985.8  868.91
  4988.1  867.98  4988.6  867.48  5004.1  867.48  5004.6  867.98  5014.1  869.61
  5028.2  876.75  5042.4   880.3  5084.8  885.14  5098.9  887.71  5212.1  895.08
#Mann= 3 ,-1 , 0
  4151.4     .12       0  4988.1     .05       0  5004.6     .12       0
Bank Sta=4988.1,5004.6
XS Rating Curve= 0 ,0
Exp/Cntr=0.3,0.1

Type RM Length L Ch R = 1 ,2437    ,512,512,512
BEGIN DESCRIPTION:
Upper Dry Comal Tributary 3 5.0
END DESCRIPTION:
XS GIS Cut Line= 3
      2211558.41     13808929.73      2210787.57     13809353.34
      2210198.66     13809658.19
#Sta/Elev= 30
  4049.1  904.78  4113.9  901.86  4173.5  901.08  4233.2  898.75  4269.8  895.32
  4304.3  889.79  4336.5  886.67  4342.2  885.25  4401.8  880.48  4423.6   880.6
  4483.3   878.2  4635.8  875.01  4717.3  871.17  4820.6  870.01  4864.1   867.7
  4874.5  867.54    4902  871.52  4945.8  871.56  4990.1  867.99  4990.9  865.67
  4991.4  865.17  5007.4  865.67  5034.4  870.52  5050.9  875.09  5095.1  879.88
  5145.5  883.83  5250.1  888.51  5449.5  901.77  5532.2  905.35  5591.8  906.37
#Mann= 3 ,-1 , 0
  4049.1     .12       0  4990.9     .05       0  5007.4     .12       0
Bank Sta=4990.9,5007.4
XS Rating Curve= 0 ,0
Exp/Cntr=0.3,0.1

Type RM Length L Ch R = 1 ,1925    ,483,483,483
BEGIN DESCRIPTION:
Upper Dry Comal Tributary 3 4.0
END DESCRIPTION:
XS GIS Cut Line= 3
      2211374.99       13808925.        2210775.       13808925.
      2210224.97     13809325.02
#Sta/Elev= 30
  4395.3  900.47  4425.3  899.24  4465.3  895.96  4565.3  884.56  4585.3  881.55
  4595.3  880.61  4655.3  877.16  4825.3  873.62  4875.3  871.59  4905.3  869.95
  4965.3  865.55    4967  863.69  4967.5  863.19  4983.1  863.19  4983.6  863.69
  4985.3  864.48  4992.8  865.35  5038.2  865.95  5059.1  867.75    5124  870.64
  5138.7  874.38  5153.3  877.06  5180.8  879.15  5230.6  880.79  5331.1  881.61
    5396  883.33  5452.8  886.78  5552.9  891.01  5647.2   897.2  5675.4  897.84
#Mann= 3 ,-1 , 0
  4395.3     .12       0    4967     .05       0  4983.6     .12       0
Bank Sta=4967,4983.6
XS Rating Curve= 0 ,0
Exp/Cntr=0.3,0.1

Type RM Length L Ch R = 1 ,1442    ,449,449,449
BEGIN DESCRIPTION:
Upper Dry Comal Tributary 3 3.0
END DESCRIPTION:
XS GIS Cut Line= 3
      2211274.98     13808125.01        2210675.       13808475.
      2210074.96     13808625.01
#Sta/Elev= 30
  4301.2  913.71    4352  908.28  4389.2  902.24  4410.7  900.23  4469.5  891.88
    4491  889.84  4528.2  880.49  4565.4  876.01  4775.8  872.55  4843.2  869.14
  4856.9  869.19  4929.2  866.04  4950.7  864.43  4964.2  862.54  4964.7  862.04
    4981  862.54  4982.1  863.13  5013.8  862.63  5026.7  863.24  5047.3  865.98
  5055.1  868.69  5060.2  868.77  5067.9  871.19  5109.2  874.83  5137.5  874.99
  5212.3  878.03  5431.3  881.61  5500.9   884.6  5549.8  887.97  5614.3  890.62
#Mann= 3 ,-1 , 0
  4301.2     .12       0  4964.2     .05       0    4981     .12       0
Bank Sta=4964.2,4981
XS Rating Curve= 0 ,0
Exp/Cntr=0.3,0.1

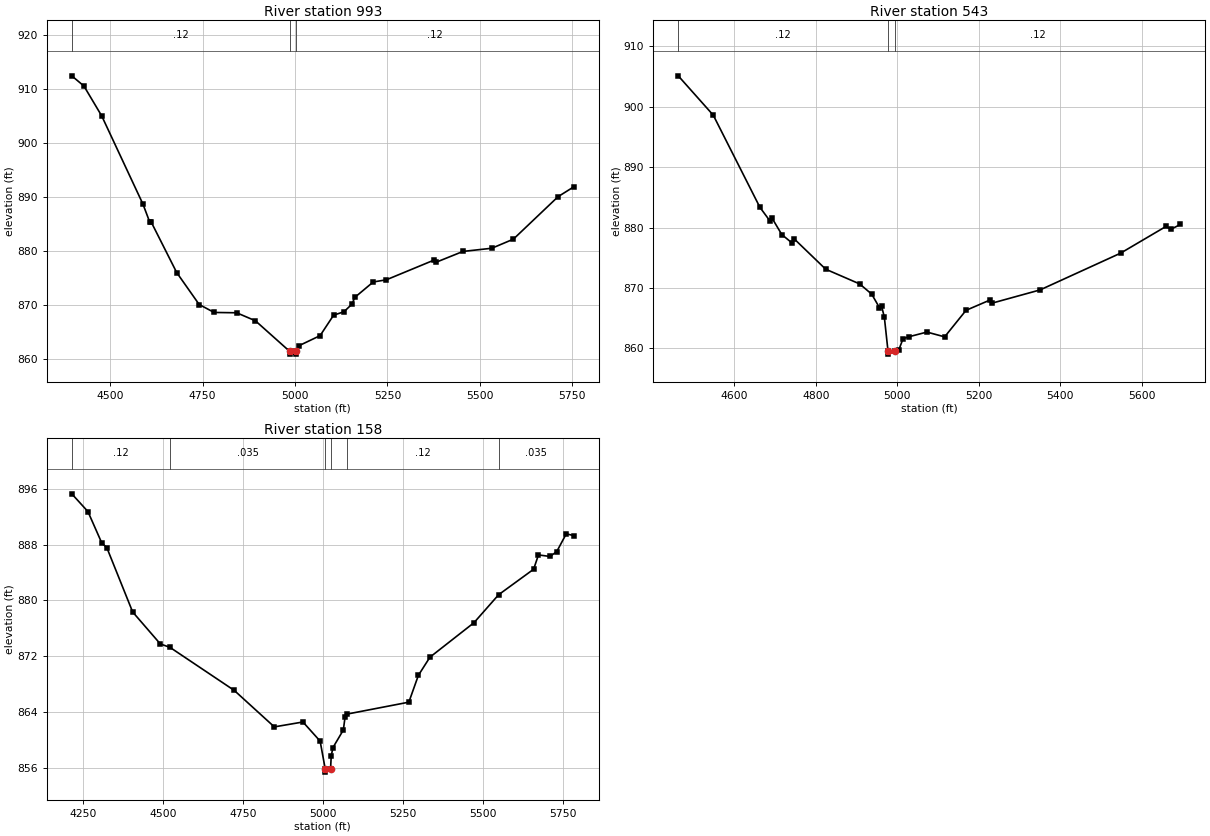
Type RM Length L Ch R = 1 ,993     ,450,450,450
BEGIN DESCRIPTION:
Upper Dry Comal Tributary 3 2.0
END DESCRIPTION:
XS GIS Cut Line= 3
        2211225.       13807975.        2210625.       13808075.
      2210024.98     13808525.02
#Sta/Elev= 30
    4396  912.36  4428.9  910.47  4477.1  904.93  4588.6  888.62  4606.4  885.39
  4611.4  885.24  4679.9  875.96  4740.7  870.05  4781.2  868.58  4842.1  868.52
  4892.8  867.04  4985.7  861.37  4986.2  860.87    5002  860.87  5002.5  861.37
  5011.6  862.46  5067.8  864.29  5104.3  868.07  5132.4  868.71  5154.3  870.14
  5161.6  871.36  5211.6  874.22    5247  874.62  5376.1  878.27  5382.4  877.89
  5454.3  879.87  5532.4  880.46  5590.7  882.14  5711.6     890  5754.3  891.83
#Mann= 3 ,-1 , 0
    4396     .12       0  4985.7     .05       0  5002.5     .12       0
Bank Sta=4985.7,5002.5
XS Rating Curve= 0 ,0
Exp/Cntr=0.3,0.1

Type RM Length L Ch R = 1 ,543     ,385,385,385
BEGIN DESCRIPTION:
Upper Dry Comal Tributary 3 1.0
END DESCRIPTION:
XS GIS Cut Line= 3
      2211124.97     13807824.99        2210625.       13807625.
        2210025.       13807975.
#Sta/Elev= 30
    4462  905.13  4548.1  898.61  4662.6  883.36  4686.8  881.15  4692.2  881.59
  4716.4  878.85  4740.6  877.51    4746  878.19  4824.1  873.12  4907.6  870.68
  4937.2  868.99  4956.1  866.76  4961.4  867.01  4968.2  865.18  4977.2  859.56
  4977.7  859.06  4994.1  859.56  5003.4   859.7  5014.1  861.61  5029.8  861.96
  5072.8  862.71  5116.3  861.92  5168.8  866.31  5227.5  868.01  5233.3  867.51
  5350.7  869.69  5548.3  875.77    5660   880.2  5671.9  879.72  5695.1  880.52
#Mann= 3 ,-1 , 0
    4462     .12       0  4977.2     .05       0  4994.1     .12       0
Bank Sta=4977.2,4994.1
XS Rating Curve= 0 ,0
Exp/Cntr=0.3,0.1

Type RM Length L Ch R = 1 ,158     ,0,0,0
BEGIN DESCRIPTION:
XS7915
END DESCRIPTION:
XS GIS Cut Line= 4
      2211123.85     13807474.98      2210698.75     13807233.35
      2210166.23     13807448.14      2209745.64     13807730.03
#Sta/Elev= 30
  4215.6  895.26  4266.1  892.72  4309.3  888.23  4325.2  887.55  4405.9  878.34
  4492.4  873.76  4522.6  873.27  4723.6   867.1  4848.8  861.88  4938.3  862.58
    4992  859.84  5007.7   855.9  5008.2   855.4  5024.6   855.9  5026.7  857.74
  5032.1  858.92  5064.5  861.43  5069.9  863.28  5076.9  863.72  5269.3  865.42
  5299.2  869.27  5335.2  871.86  5472.9   876.8    5550  880.81  5659.4  884.46
  5674.4  886.51  5710.4  886.29  5731.4  886.97  5761.4  889.53  5785.1  889.28
#Mann= 6 ,-1 , 0
  4215.6     .12       0  4522.6    .035       0  5007.7    .035       0
  5024.6    .035       0  5076.9     .12       0    5550    .035       0
Bank Sta=5007.7,5024.6
XS Rating Curve= 0 ,0
Exp/Cntr=0.3,0.1

Chan Stop Cuts=-1
Use User Specified Reach Order=0
Composite Channel Slope=5