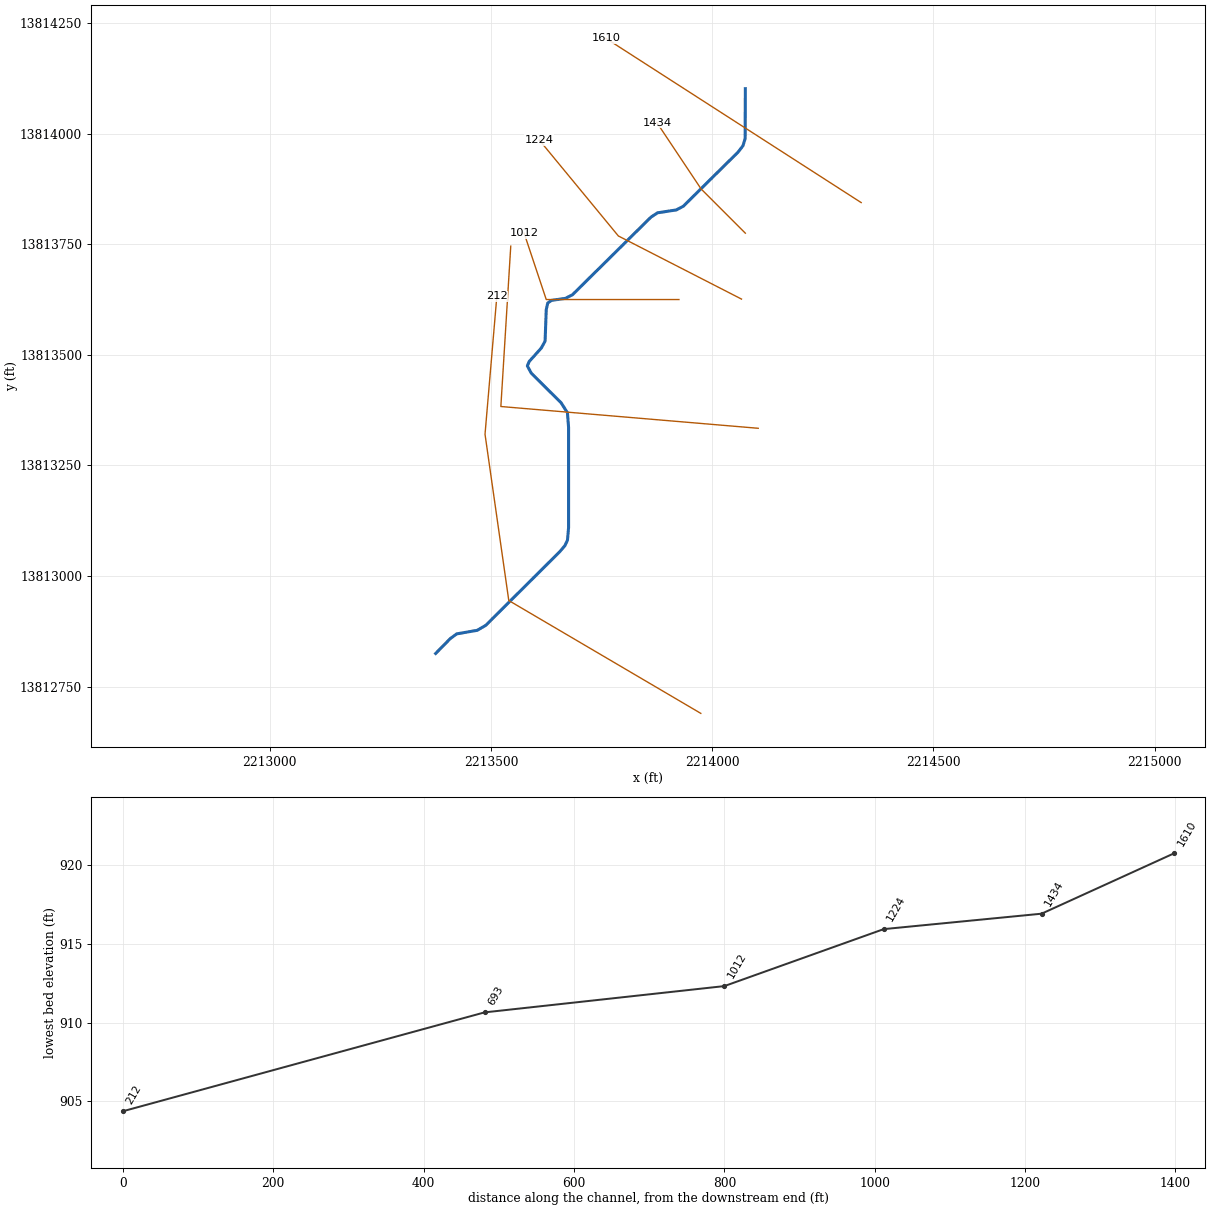
--- Upper Dry Comal Tributary 7.prj (project) ---

Proj Title=Upper Dry Comal Tributary 7 Base Level Engineering
Current Plan=p01
Default Exp/Contr=0.3,0.1
English Units
Geom File=g01
Flow File=f01
Plan File=p01
BEGIN DESCRIPTION:
Upper Dry Comal Tributary 7
END DESCRIPTION:

--- Upper Dry Comal Tributary 7.p01 (plan) ---

Plan Title=Multiple Run
Short Identifier=Multiple
Geom File=g01
Flow File=f01
Subcritical Flow
K Sum by GR= 0
Std Step Tol= 0.01
Critical Tol= 0.01
Num of Std Step Trials= 20
Max Error Tol= 0.3
Flow Tol Ratio= 0.001
Split Flow NTrial= 30
Split Flow Tol= 0.02
Split Flow Ratio= 0.02
Log Output Level= 0
Friction Slope Method= 1
Unsteady Friction Slope Method= 2
Unsteady Bridges Friction Slope Method= 1
Parabolic Critical Depth
Global Vel Dist=  1 , 1 , 1
Global Log Level= 0
CheckData=True
Encroach Param= -1, 0, 0, 0
BEGIN DESCRIPTION:
Multiple Run
END DESCRIPTION:

--- Upper Dry Comal Tributary 7.f01 (steady flow) ---

Flow Title=Multiple
Number of Profiles=7
Profile Names=10-year,25-year,50-year,1pct_min,100-year,1pct_plu,500-year
River Rch & RM= Upper Dry Comal ,Reach-1,1610
     501     798    1063     687    1372    2737    2255
Boundary for River Rch & Prof#=Upper Dry Comal ,Reach-1,1
Up Type=0
Dn Type=3
Dn Slope=0.005
Boundary for River Rch & Prof#=Upper Dry Comal ,Reach-1,2
Up Type=0
Dn Type=3
Dn Slope=0.005
Boundary for River Rch & Prof#=Upper Dry Comal ,Reach-1,3
Up Type=0
Dn Type=3
Dn Slope=0.005
Boundary for River Rch & Prof#=Upper Dry Comal ,Reach-1,4
Up Type=0
Dn Type=3
Dn Slope=0.005
Boundary for River Rch & Prof#=Upper Dry Comal ,Reach-1,5
Up Type=0
Dn Type=3
Dn Slope=0.005
Boundary for River Rch & Prof#=Upper Dry Comal ,Reach-1,6
Up Type=0
Dn Type=3
Dn Slope=0.005
Boundary for River Rch & Prof#=Upper Dry Comal ,Reach-1,7
Up Type=0
Dn Type=3
Dn Slope=0.005

--- Upper Dry Comal Tributary 7.g01 (geometry) ---

Geom Title=Existing Conditions

River Reach=Upper Dry Comal ,Reach-1
Reach XY= 30
      2214075.00     13814101.62      2214074.60     13813988.80
      2214069.60     13813972.52      2214058.58     13813958.23
      2213934.68     13813835.78      2213918.95     13813827.53
      2213876.65     13813821.02      2213861.79     13813811.37
      2213684.38     13813635.90      2213668.48     13813627.73
      2213636.74     13813623.00      2213628.32     13813616.95
      2213624.99     13813602.24      2213622.40     13813530.98
      2213613.71     13813515.25      2213586.33     13813484.85
      2213582.32     13813474.91      2213591.33     13813458.31
      2213658.50     13813391.76      2213672.93     13813369.15
      2213675.50     13813335.21      2213675.49     13813109.80
      2213672.94     13813080.85      2213667.19     13813068.81
      2213655.40     13813054.84      2213488.23     13812888.57
      2213469.03     13812877.34      2213422.65     13812869.29
      2213408.08     13812858.58      2213375.00     13812825.00

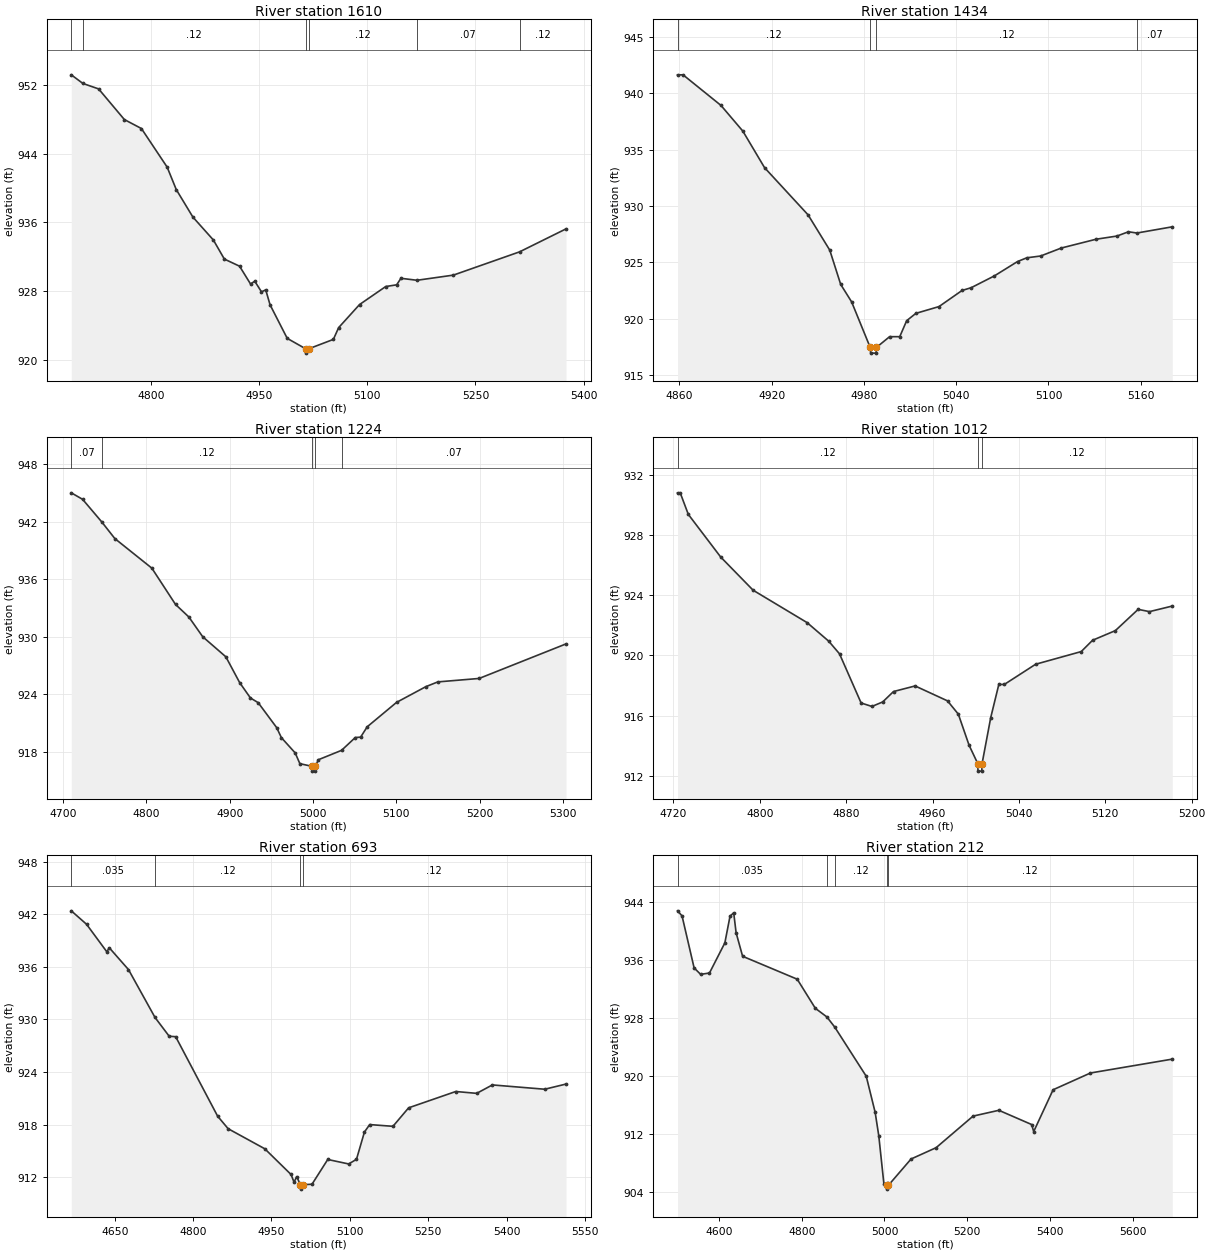
Type RM Length L Ch R = 1,1610,176,176,176
BEGIN DESCRIPTION:
XS7920
END DESCRIPTION:
XS GIS Cut Line= 2
      2214336.87     13813844.10      2213759.79     13814215.39
#Sta/Elev= 30
  4689.4  953.19  4705.6  952.18  4727.3  951.55  4763.0  947.98  4786.7  946.93
  4822.4  942.43  4835.0  939.82  4858.1  936.61  4886.5  933.94  4901.7  931.72
  4922.8  930.89  4938.0  928.82  4943.9  929.14  4953.2  927.90  4959.1  928.13
  4965.1  926.39  4988.9  922.48  5014.6  921.26  5014.8  920.76  5018.6  921.26
  5052.9  922.36  5060.2  923.73  5089.2  926.42  5125.5  928.52  5140.7  928.72
  5146.6  929.48  5168.9  929.25  5219.3  929.85  5311.1  932.56  5375.6  935.24
#Mann=6,-1,0
  4689.4   0.035       0  4705.6    0.12       0  5014.6    0.05       0
  5018.6    0.12       0  5168.9    0.07       0  5311.1    0.12       0
Bank Sta=5014.6,5018.6
Exp/Cntr=0.3,0.1

Type RM Length L Ch R = 1,1434,210,210,210
BEGIN DESCRIPTION:
Upper Dry Comal Tributary 7 2.0
END DESCRIPTION:
XS GIS Cut Line= 3
      2214075.02     13813774.98      2213975.00     13813875.00
      2213875.02     13814024.97
#Sta/Elev= 30
  4858.8  941.63  4862.4  941.63  4887.1  938.91  4901.3  936.63  4915.4  933.39
  4943.7  929.20  4957.8  926.07  4964.9  923.03  4972.0  921.48  4984.1  917.43
  4984.4  916.93  4987.9  916.93  4988.1  917.43  4996.7  918.39  5003.3  918.39
  5007.8  919.81  5013.8  920.46  5028.8  921.06  5043.8  922.49  5049.8  922.74
  5064.9  923.79  5079.9  925.06  5085.9  925.39  5094.9  925.55  5108.4  926.26
  5131.0  927.04  5144.5  927.32  5152.0  927.70  5157.5  927.59  5180.5  928.14
#Mann=4,-1,0
  4858.8    0.12       0  4984.1    0.05       0  4988.1    0.12       0
  5157.5    0.07       0
Bank Sta=4984.1,4988.1
Exp/Cntr=0.3,0.1

Type RM Length L Ch R = 1,1224,212,212,212
BEGIN DESCRIPTION:
H21530
END DESCRIPTION:
XS GIS Cut Line= 3
      2214066.37     13813626.02      2213787.98     13813768.70
      2213609.36     13813985.47
#Sta/Elev= 30
  4709.9  945.02  4723.5  944.34  4746.2  942.01  4762.2  940.24  4806.6  937.15
  4835.0  933.36  4851.0  932.05  4867.6  929.99  4895.4  927.89  4912.0  925.19
  4924.9  923.59  4934.2  923.10  4956.4  920.49  4962.0  919.45  4978.6  917.85
  4984.2  916.73  4998.8  916.45  4999.1  915.95  5002.6  915.95  5002.8  916.45
  5006.4  917.14  5034.2  918.12  5050.7  919.46  5057.1  919.50  5065.0  920.58
  5100.2  923.13  5135.3  924.77  5149.7  925.27  5199.3  925.63  5303.6  929.24
#Mann=5,-1,0
  4709.9    0.07       0  4746.2    0.12       0  4998.8    0.05       0
  5002.8    0.12       0  5034.2    0.07       0
Bank Sta=4998.8,5002.8
Exp/Cntr=0.3,0.1

Type RM Length L Ch R = 1,1012,319,319,319
BEGIN DESCRIPTION:
Upper Dry Comal Tributary 7 1.0
END DESCRIPTION:
XS GIS Cut Line= 3
      2213924.97     13813625.00      2213625.00     13813625.00
      2213574.99     13813775.02
#Sta/Elev= 30
  4723.9  930.79  4726.4  930.79  4733.9  929.36  4763.9  926.53  4793.9  924.33
  4843.9  922.18  4863.9  920.95  4873.9  920.11  4893.9  916.85  4903.9  916.62
  4913.9  916.92  4923.9  917.61  4943.9  917.98  4973.9  916.99  4983.9  916.11
  4993.9  914.04  5001.9  912.83  5002.1  912.33  5005.6  912.33  5005.9  912.83
  5013.9  915.88  5021.4  918.08  5026.5  918.08  5055.5  919.42  5097.7  920.26
  5108.2  921.01  5129.3  921.65  5150.4  923.06  5160.9  922.91  5182.0  923.28
#Mann=3,-1,0
  4723.9    0.12       0  5001.9    0.05       0  5005.9    0.12       0
Bank Sta=5001.9,5005.9
Exp/Cntr=0.3,0.1

Type RM Length L Ch R = 1,693,481,481,481
BEGIN DESCRIPTION:
XS7919
END DESCRIPTION:
XS GIS Cut Line= 3
      2214104.12     13813333.98      2213522.41     13813383.20
      2213544.79     13813745.72
#Sta/Elev= 30
  4566.8  942.39  4596.0  940.86  4634.7  937.73  4639.7  938.17  4676.3  935.69
  4727.1  930.23  4754.2  928.09  4766.6  928.04  4846.9  918.98  4867.0  917.55
  4937.2  915.26  4987.4  912.33  4993.2  911.45  4998.2  912.08  5005.5  911.16
  5005.7  910.66  5009.5  911.16  5027.6  911.22  5057.7  914.04  5097.8  913.53
  5112.7  914.06  5127.9  917.17  5138.0  918.02  5182.5  917.82  5212.5  919.93
  5302.7  921.79  5342.8  921.58  5372.8  922.54  5473.0  922.05  5513.8  922.64
#Mann=4,-1,0
  4566.8   0.035       0  4727.1    0.12       0  5005.5    0.05       0
  5009.5    0.12       0
Bank Sta=5005.5,5009.5
Exp/Cntr=0.3,0.1

Type RM Length L Ch R = 1,212,0,0,0
BEGIN DESCRIPTION:
XS7918
END DESCRIPTION:
XS GIS Cut Line= 4
      2213974.38     13812689.59      2213540.31     13812944.66
      2213486.61     13813320.55      2213513.30     13813631.93
#Sta/Elev= 30
  4499.8  942.72  4510.7  942.03  4539.9  934.86  4555.6  933.97  4577.0  934.15
  4614.2  938.30  4626.7  941.98  4635.6  942.45  4641.4  939.70  4657.1  936.46
  4789.1  933.30  4832.9  929.29  4860.8  928.10  4879.8  926.70  4955.9  919.93
  4977.4  914.97  4986.2  911.73  4998.7  905.04  5005.1  904.88  5005.3  904.38
  5009.1  904.88  5064.2  908.53  5124.8  910.09  5214.1  914.44  5276.4  915.24
  5355.6  913.28  5360.6  912.31  5407.5  918.07  5497.8  920.38  5695.5  922.29
#Mann=5,-1,0
  4499.8   0.035       0  4860.8    0.07       0  4879.8    0.12       0
  5005.1    0.05       0  5009.1    0.12       0
Bank Sta=5005.1,5009.1
Exp/Cntr=0.3,0.1

Chan Stop Cuts=-1