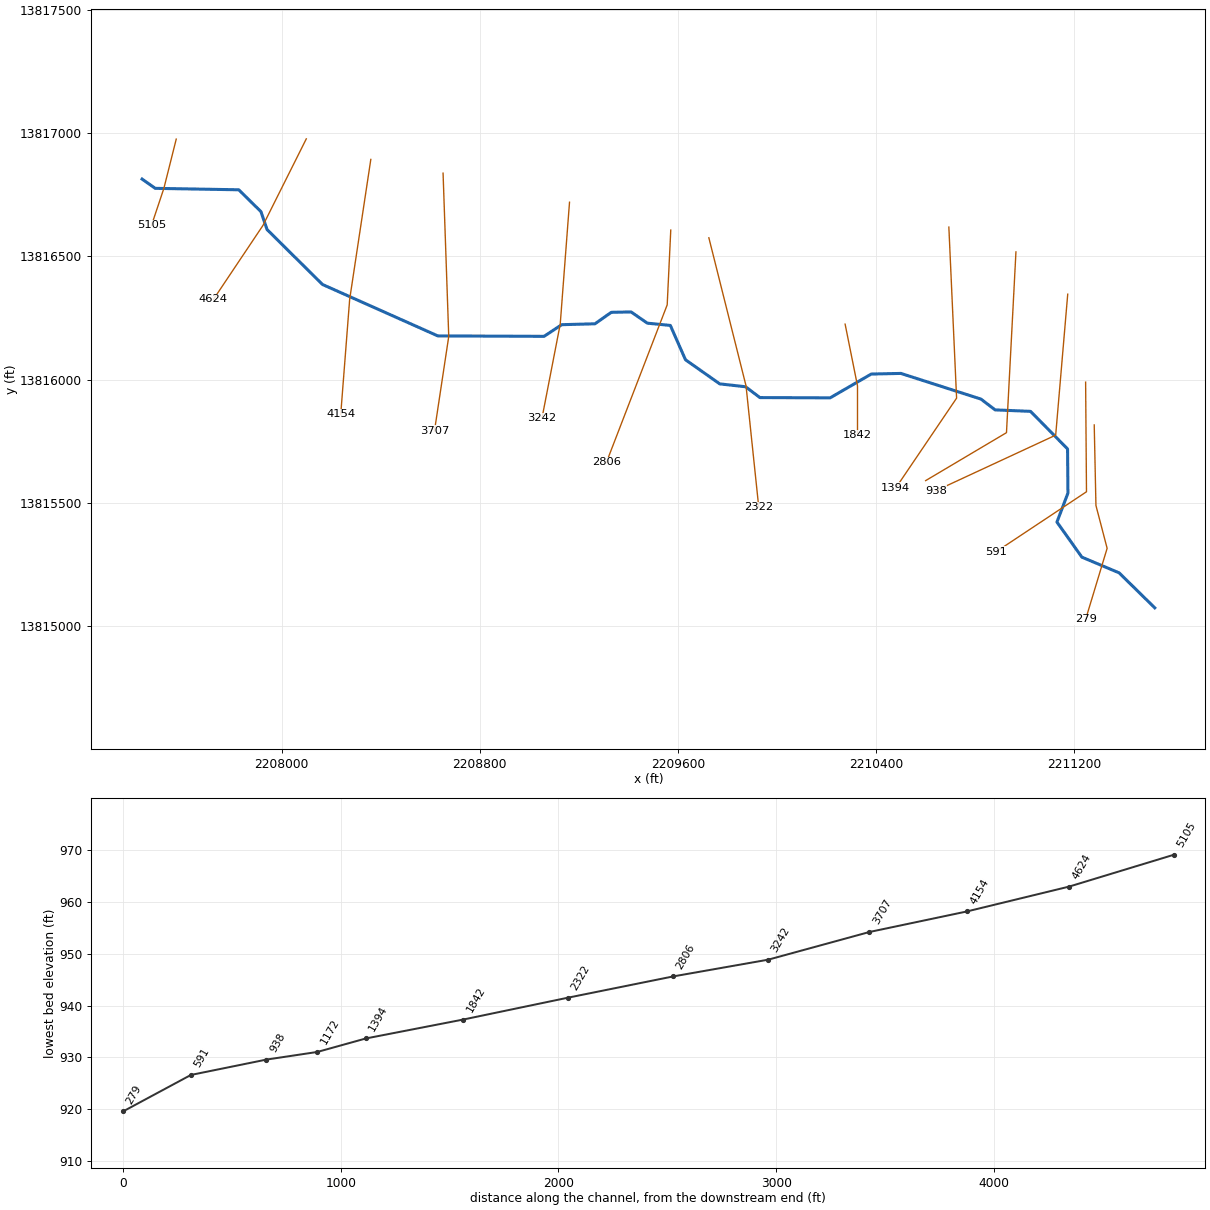
--- Upper Dry Comal Tributary 8.prj (project) ---

Proj Title=Upper Dry Comal Tributary 8 Base Level Engineering
Current Plan=p01
Default Exp/Contr=0.3,0.1
English Units
Geom File=g01
Flow File=f01
Plan File=p01
BEGIN DESCRIPTION:
Upper Dry Comal Tributary 8
END DESCRIPTION:

--- Upper Dry Comal Tributary 8.p01 (plan) ---

Plan Title=Multiple Run
Short Identifier=Multiple
Geom File=g01
Flow File=f01
Subcritical Flow
K Sum by GR= 0
Std Step Tol= 0.01
Critical Tol= 0.01
Num of Std Step Trials= 20
Max Error Tol= 0.3
Flow Tol Ratio= 0.001
Split Flow NTrial= 30
Split Flow Tol= 0.02
Split Flow Ratio= 0.02
Log Output Level= 0
Friction Slope Method= 1
Unsteady Friction Slope Method= 2
Unsteady Bridges Friction Slope Method= 1
Parabolic Critical Depth
Global Vel Dist=  1 , 1 , 1
Global Log Level= 0
CheckData=True
Encroach Param= -1, 0, 0, 0
BEGIN DESCRIPTION:
Multiple Run
END DESCRIPTION:

--- Upper Dry Comal Tributary 8.f01 (steady flow) ---

Flow Title=Multiple
Number of Profiles=7
Profile Names=10-year,25-year,50-year,1pct_min,100-year,1pct_plu,500-year
River Rch & RM= Upper Dry Comal ,Reach-1,5105
     846    1401    1917    1271    2536    5061    4392
Boundary for River Rch & Prof#=Upper Dry Comal ,Reach-1,1
Up Type=0
Dn Type=3
Dn Slope=0.005
Boundary for River Rch & Prof#=Upper Dry Comal ,Reach-1,2
Up Type=0
Dn Type=3
Dn Slope=0.005
Boundary for River Rch & Prof#=Upper Dry Comal ,Reach-1,3
Up Type=0
Dn Type=3
Dn Slope=0.005
Boundary for River Rch & Prof#=Upper Dry Comal ,Reach-1,4
Up Type=0
Dn Type=3
Dn Slope=0.005
Boundary for River Rch & Prof#=Upper Dry Comal ,Reach-1,5
Up Type=0
Dn Type=3
Dn Slope=0.005
Boundary for River Rch & Prof#=Upper Dry Comal ,Reach-1,6
Up Type=0
Dn Type=3
Dn Slope=0.005
Boundary for River Rch & Prof#=Upper Dry Comal ,Reach-1,7
Up Type=0
Dn Type=3
Dn Slope=0.005

--- Upper Dry Comal Tributary 8.g01 (geometry) ---

Geom Title=Existing Conditions

River Reach=Upper Dry Comal ,Reach-1
Reach XY= 30
      2207437.00     13816813.00      2207490.17     13816775.41
      2207827.47     13816769.55      2207916.85     13816681.07
      2207941.65     13816608.33      2208165.32     13816385.76
      2208630.94     13816177.26      2209059.78     13816175.52
      2209130.94     13816222.73      2209265.33     13816226.39
      2209330.98     13816272.83      2209411.03     13816274.45
      2209476.67     13816228.89      2209569.56     13816219.75
      2209630.59     13816080.61      2209768.83     13815982.88
      2209873.40     13815971.14      2209930.94     13815927.26
      2210214.50     13815926.20      2210380.52     13816022.66
      2210500.07     13816025.23      2210823.40     13815921.14
      2210880.53     13815877.39      2211023.53     13815871.46
      2211172.94     13815719.15      2211174.46     13815540.21
      2211130.10     13815422.71      2211230.61     13815280.59
      2211381.06     13815216.86      2211525.00     13815075.00

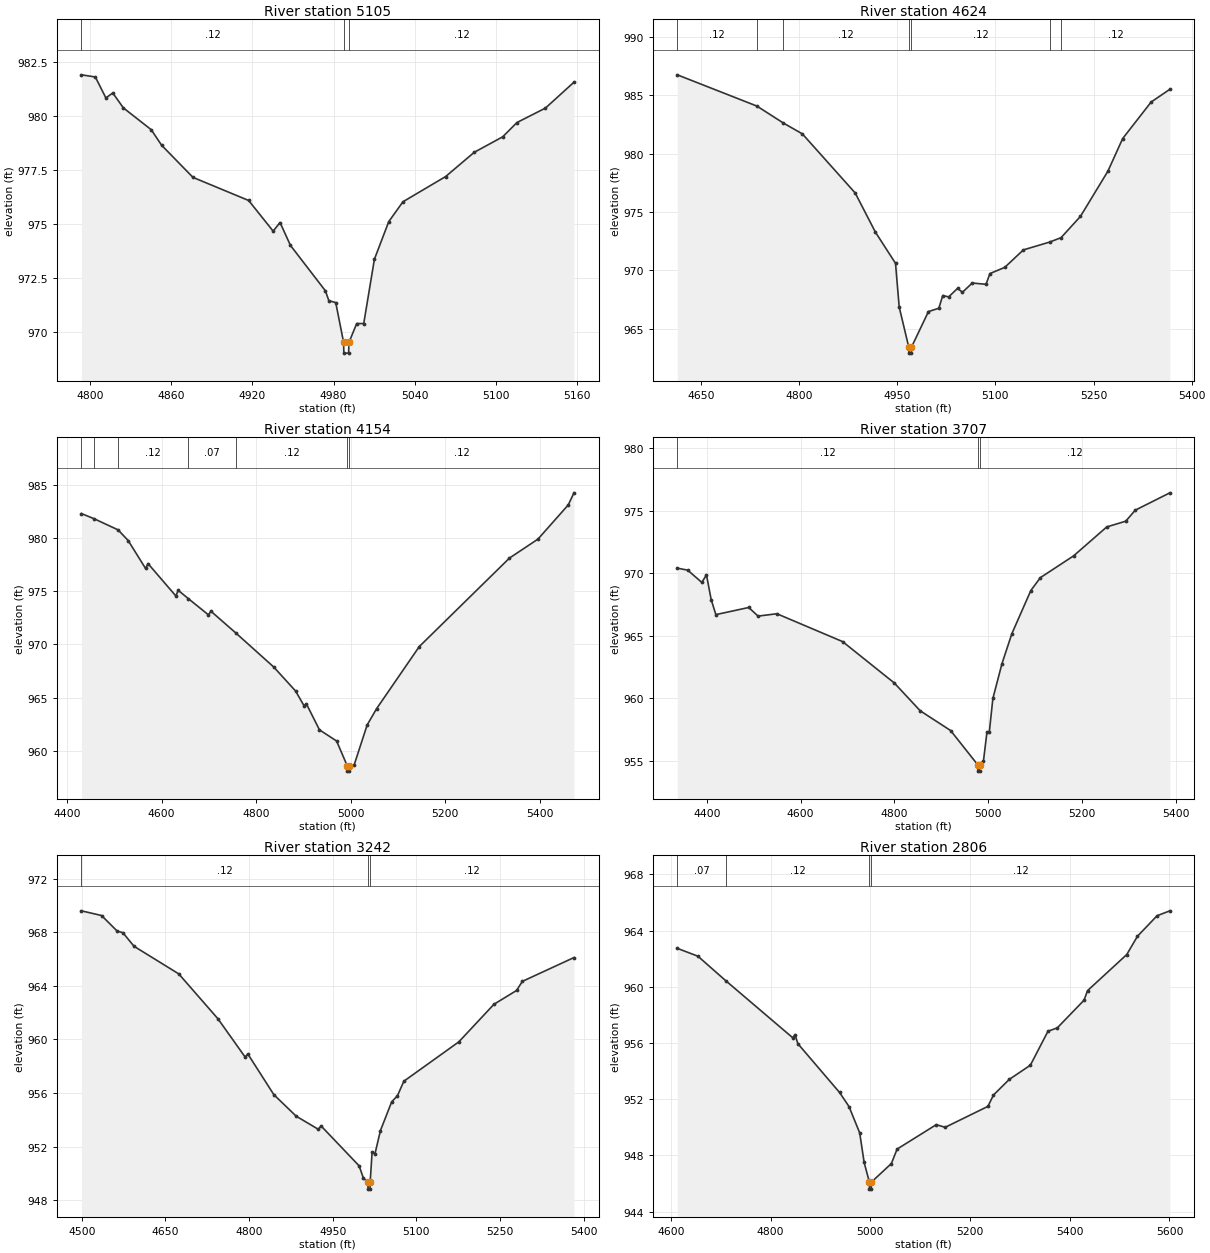
Type RM Length L Ch R = 1,5105,481,481,481
BEGIN DESCRIPTION:
Upper Dry Comal Tributary 8 10.0
END DESCRIPTION:
XS GIS Cut Line= 3
      2207575.01     13816975.03      2207525.00     13816775.00
      2207475.00     13816625.00
#Sta/Elev= 30
  4793.5  981.91  4803.8  981.81  4811.6  980.84  4816.7  981.07  4824.5  980.38
  4845.1  979.37  4852.8  978.65  4876.0  977.16  4917.2  976.09  4935.3  974.67
  4940.4  975.07  4948.1  974.01  4973.9  971.91  4976.5  971.45  4981.6  971.36
  4987.4  969.52  4987.6  969.02  4991.1  969.02  4991.4  969.52  4997.1  970.39
  5002.3  970.39  5010.2  973.37  5020.8  975.11  5031.3  976.03  5062.9  977.20
  5084.0  978.32  5105.1  979.04  5115.6  979.70  5136.7  980.37  5157.8  981.57
#Mann=3,-1,0
  4793.5    0.12       0  4987.4    0.05       0  4991.4    0.12       0
Bank Sta=4987.4,4991.4
Exp/Cntr=0.3,0.1

Type RM Length L Ch R = 1,4624,470,470,470
BEGIN DESCRIPTION:
Upper Dry Comal Tributary 8 9.0
END DESCRIPTION:
XS GIS Cut Line= 3
      2208099.98     13816976.01      2207925.00     13816625.00
      2207724.98     13816324.97
#Sta/Elev= 30
  4613.9  986.75  4735.6  984.07  4776.2  982.61  4805.0  981.69  4885.8  976.62
  4916.7  973.26  4947.4  970.59  4953.0  966.85  4967.7  963.39  4968.0  962.89
  4971.5  962.89  4971.7  963.39  4997.7  966.45  5013.6  966.74  5019.6  967.83
  5028.6  967.71  5042.2  968.44  5049.7  968.11  5064.7  968.90  5085.7  968.79
  5091.7  969.71  5114.3  970.24  5142.8  971.74  5182.9  972.41  5200.4  972.79
  5230.0  974.61  5272.0  978.49  5294.6  981.29  5338.1  984.42  5366.7  985.51
#Mann=7,-1,0
  4613.9    0.12       0  4735.6    0.07       0  4776.2    0.12       0
  4967.7    0.05       0  4971.7    0.12       0  5182.9    0.07       0
  5200.4    0.12       0
Bank Sta=4967.7,4971.7
Exp/Cntr=0.3,0.1

Type RM Length L Ch R = 1,4154,447,447,447
BEGIN DESCRIPTION:
Upper Dry Comal Tributary 8 8.0
END DESCRIPTION:
XS GIS Cut Line= 3
      2208360.42     13816892.72      2208275.00     13816325.00
      2208238.97     13815859.00
#Sta/Elev= 30
  4430.6  982.30  4456.7  981.83  4508.1  980.77  4529.4  979.77  4566.3  977.14
  4571.4  977.60  4630.3  974.56  4635.3  975.09  4656.6  974.31  4699.3  972.78
  4704.3  973.13  4756.6  971.10  4837.3  967.88  4883.4  965.63  4901.2  964.25
  4906.3  964.42  4933.9  961.98  4970.2  960.93  4992.6  958.60  4992.9  958.10
  4996.4  958.10  4996.6  958.60  5007.2  958.67  5034.8  962.44  5054.9  963.98
  5145.1  969.81  5335.7  978.12  5395.9  979.90  5459.9  983.11  5472.1  984.25
#Mann=7,-1,0
  4430.6    0.12       0  4456.7    0.07       0  4508.1    0.12       0
  4656.6    0.07       0  4756.6    0.12       0  4992.6    0.05       0
  4996.6    0.12       0
Bank Sta=4992.6,4996.6
Exp/Cntr=0.3,0.1

Type RM Length L Ch R = 1,3707,465,465,465
BEGIN DESCRIPTION:
Upper Dry Comal Tributary 8 7.0
END DESCRIPTION:
XS GIS Cut Line= 3
      2208652.08     13816837.12      2208675.00     13816175.00
      2208617.36     13815792.03
#Sta/Elev= 30
  4337.1  970.40  4359.2  970.24  4389.3  969.26  4399.3  969.86  4409.3  967.88
  4419.3  966.68  4489.3  967.25  4509.3  966.56  4549.3  966.75  4689.4  964.52
  4799.5  961.21  4854.8  958.98  4919.6  957.40  4977.6  954.65  4977.9  954.15
  4981.4  954.15  4981.6  954.65  4989.6  954.96  4997.1  957.29  5002.1  957.29
  5009.7  959.97  5029.1  962.76  5050.2  965.16  5090.6  968.61  5110.9  969.64
  5181.6  971.38  5252.4  973.70  5292.9  974.16  5313.1  975.04  5386.9  976.43
#Mann=3,-1,0
  4337.1    0.12       0  4977.6    0.05       0  4981.6    0.12       0
Bank Sta=4977.6,4981.6
Exp/Cntr=0.3,0.1

Type RM Length L Ch R = 1,3242,436,436,436
BEGIN DESCRIPTION:
Upper Dry Comal Tributary 8 6.0
END DESCRIPTION:
XS GIS Cut Line= 3
      2209162.50     13816719.11      2209125.00     13816225.00
      2209051.39     13815844.08
#Sta/Elev= 30
  4499.3  969.61  4535.4  969.26  4563.6  968.09  4573.6  967.98  4593.7  966.96
  4673.9  964.90  4744.1  961.55  4792.9  958.69  4797.9  958.91  4844.4  955.88
  4884.5  954.27  4924.2  953.29  4929.2  953.54  4997.4  950.56  5005.0  949.65
  5013.2  949.32  5013.5  948.82  5017.0  948.82  5017.2  949.32  5020.7  951.60
  5025.8  951.45  5035.6  953.19  5055.9  955.35  5066.1  955.79  5077.6  956.88
  5176.2  959.82  5239.3  962.63  5279.8  963.66  5290.2  964.34  5382.8  966.12
#Mann=3,-1,0
  4499.3    0.12       0  5013.2    0.05       0  5017.2    0.12       0
Bank Sta=5013.2,5017.2
Exp/Cntr=0.3,0.1

Type RM Length L Ch R = 1,2806,484,484,484
BEGIN DESCRIPTION:
Upper Dry Comal Tributary 8 5.0
END DESCRIPTION:
XS GIS Cut Line= 3
      2209571.22     13816606.29      2209556.79     13816303.10
      2209311.39     13815664.35
#Sta/Elev= 30
  4613.0  962.74  4654.3  962.18  4709.7  960.45  4844.3  956.38  4849.3  956.59
  4854.6  955.96  4938.4  952.48  4957.3  951.48  4978.8  949.60  4987.7  947.50
  4998.2  946.10  4998.4  945.60  5001.9  945.60  5002.2  946.10  5042.3  947.42
  5053.8  948.45  5132.4  950.19  5150.2  950.00  5235.9  951.49  5247.1  952.30
  5278.7  953.41  5321.0  954.42  5356.4  956.84  5375.1  957.08  5428.7  959.05
  5435.7  959.73  5514.4  962.30  5535.8  963.60  5575.1  965.06  5600.8  965.41
#Mann=4,-1,0
  4613.0    0.07       0  4709.7    0.12       0  4998.2    0.05       0
  5002.2    0.12       0
Bank Sta=4998.2,5002.2
Exp/Cntr=0.3,0.1

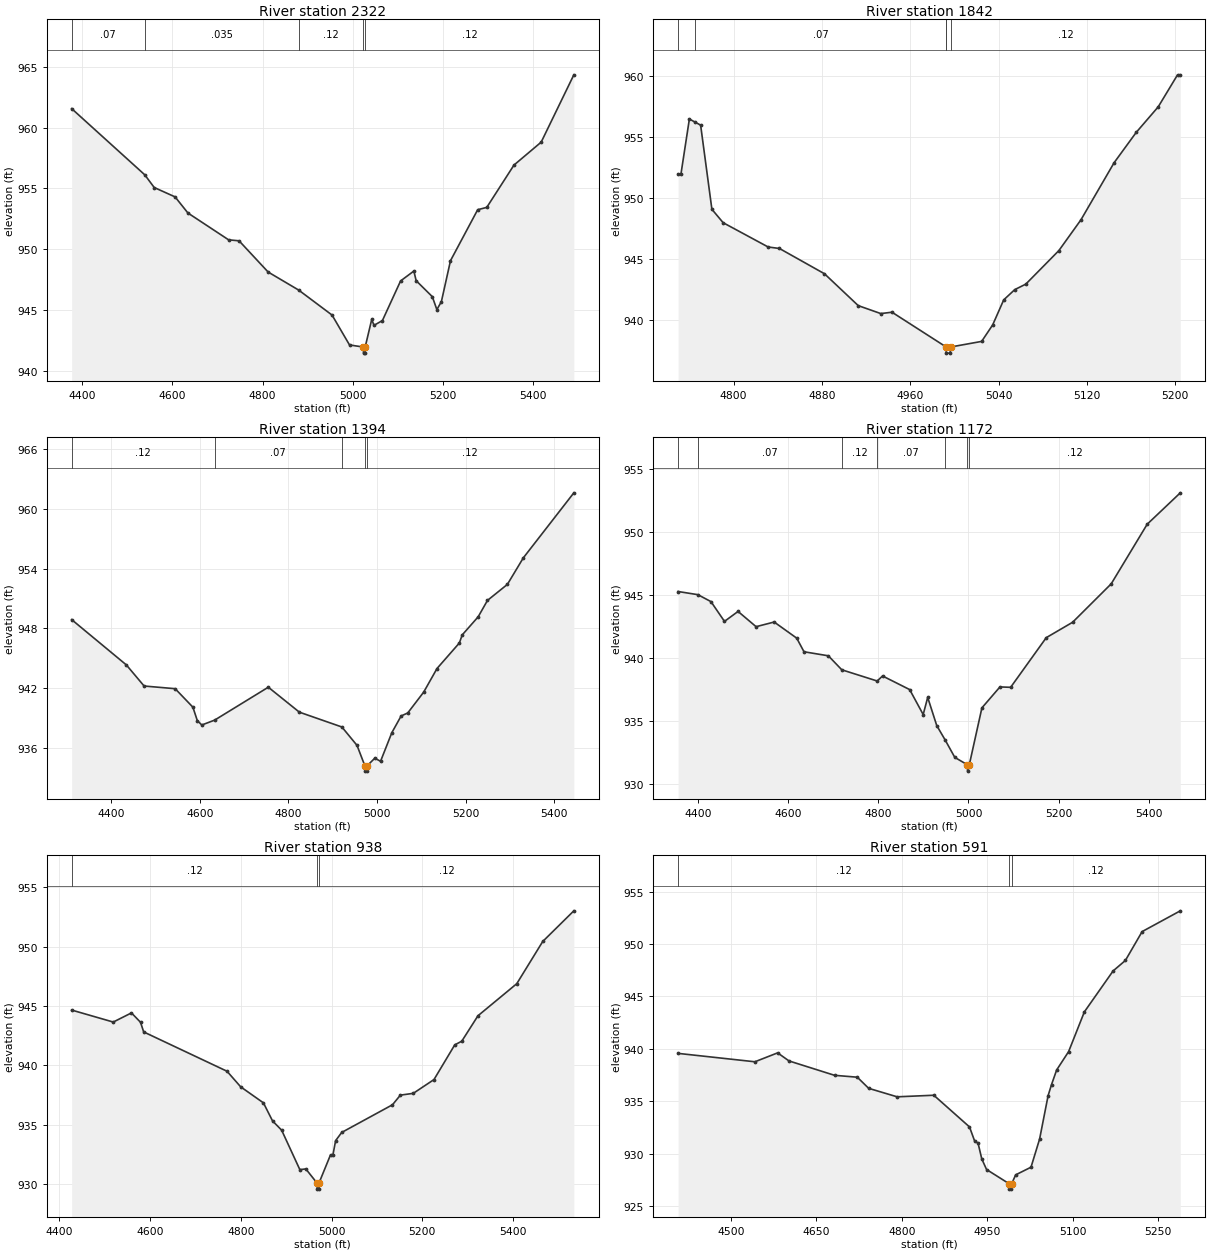
Type RM Length L Ch R = 1,2322,480,480,480
BEGIN DESCRIPTION:
Upper Dry Comal Tributary 8 4.0
END DESCRIPTION:
XS GIS Cut Line= 3
      2209725.00     13816574.99      2209875.00     13815975.00
      2209926.38     13815483.03
#Sta/Elev= 30
  4376.6  961.55  4538.7  956.12  4559.6  955.08  4605.9  954.31  4634.3  952.99
  4724.5  950.79  4747.7  950.71  4812.1  948.15  4879.8  946.67  4953.8  944.62
  4992.5  942.17  5023.2  942.00  5023.5  941.50  5027.0  941.50  5027.2  942.00
  5041.7  944.26  5046.8  943.78  5065.4  944.17  5105.7  947.42  5135.1  948.23
  5140.2  947.44  5176.0  946.13  5186.1  945.07  5196.1  945.72  5216.3  949.08
  5276.6  953.26  5296.7  953.45  5357.0  956.92  5417.3  958.80  5489.7  964.32
#Mann=5,-1,0
  4376.6    0.07       0  4538.7   0.035       0  4879.8    0.12       0
  5023.2    0.05       0  5027.2    0.12       0
Bank Sta=5023.2,5027.2
Exp/Cntr=0.3,0.1

Type RM Length L Ch R = 1,1842,448,448,448
BEGIN DESCRIPTION:
Upper Dry Comal Tributary 8 3.0
END DESCRIPTION:
XS GIS Cut Line= 3
      2210274.99     13816225.03      2210325.00     13815975.00
      2210325.00     13815774.98
#Sta/Elev= 30
  4749.7  951.98  4752.3  951.98  4759.9  956.47  4765.4  956.20  4770.1  955.97
  4780.3  949.08  4790.5  947.98  4831.3  945.99  4841.5  945.87  4882.3  943.80
  4912.9  941.19  4933.3  940.54  4943.5  940.65  4992.1  937.83  4992.5  937.80
  4992.7  937.30  4996.2  937.30  4996.5  937.80  5024.7  938.26  5034.7  939.61
  5044.7  941.66  5054.7  942.50  5064.7  942.95  5094.7  945.70  5114.7  948.22
  5144.7  952.89  5164.7  955.37  5184.7  957.47  5202.2  960.09  5204.7  960.09
#Mann=5,-1,0
  4749.7   0.035       0  4765.4    0.07       0  4992.1    0.12       0
  4992.5    0.05       0  4996.5    0.12       0
Bank Sta=4992.5,4996.5
Exp/Cntr=0.3,0.1

Type RM Length L Ch R = 1,1394,222,222,222
BEGIN DESCRIPTION:
Upper Dry Comal Tributary 8 2.0
END DESCRIPTION:
XS GIS Cut Line= 3
      2210693.75     13816618.36      2210725.00     13815925.00
      2210479.44     13815560.82
#Sta/Elev= 30
  4310.7  948.89  4434.2  944.33  4474.2  942.21  4544.3  941.94  4584.3  940.08
  4594.3  938.73  4604.4  938.29  4633.4  938.78  4754.5  942.09  4824.6  939.58
  4920.5  938.09  4954.7  936.24  4972.7  934.15  4973.0  933.65  4976.5  933.65
  4976.7  934.15  4994.8  934.95  5007.8  934.64  5033.3  937.52  5054.3  939.20
  5069.2  939.50  5105.2  941.60  5135.2  943.97  5185.7  946.54  5192.1  947.35
  5228.1  949.17  5249.1  950.82  5294.0  952.43  5330.0  955.10  5444.0  961.64
#Mann=5,-1,0
  4310.7    0.12       0  4633.4    0.07       0  4920.5    0.12       0
  4972.7    0.05       0  4976.7    0.12       0
Bank Sta=4972.7,4976.7
Exp/Cntr=0.3,0.1

Type RM Length L Ch R = 1,1172,234,234,234
BEGIN DESCRIPTION:
XS7924
END DESCRIPTION:
XS GIS Cut Line= 3
      2210964.58     13816517.68      2210926.39     13815785.07
      2210600.02     13815590.64
#Sta/Elev= 30
  4356.2  945.31  4400.0  945.06  4429.0  944.51  4459.0  942.94  4489.1  943.73
  4529.1  942.52  4569.2  942.89  4619.2  941.61  4635.3  940.53  4689.3  940.21
  4719.1  939.10  4797.6  938.21  4809.5  938.61  4869.6  937.53  4899.6  935.55
  4909.6  936.91  4929.7  934.67  4948.0  933.55  4969.7  932.15  4997.8  931.56
  4998.0  931.06  5001.8  931.56  5029.8  936.08  5069.8  937.74  5093.5  937.71
  5172.5  941.65  5230.9  942.87  5316.5  945.92  5396.3  950.65  5469.7  953.14
#Mann=7,-1,0
  4356.2    0.12       0  4400.0    0.07       0  4719.1    0.12       0
  4797.6    0.07       0  4948.0    0.12       0  4997.8    0.05       0
  5001.8    0.12       0
Bank Sta=4997.8,5001.8
Exp/Cntr=0.3,0.1

Type RM Length L Ch R = 1,938,347,347,347
BEGIN DESCRIPTION:
Upper Dry Comal Tributary 8 1.0
END DESCRIPTION:
XS GIS Cut Line= 3
      2211173.61     13816346.38      2211125.00     13815775.00
      2210640.99     13815549.52
#Sta/Elev= 30
  4426.9  944.66  4518.6  943.65  4558.8  944.42  4578.8  943.63  4585.7  942.82
  4769.5  939.51  4799.6  938.20  4849.8  936.85  4869.9  935.33  4890.0  934.55
  4930.1  931.23  4943.3  931.29  4968.2  930.09  4968.5  929.59  4972.0  929.59
  4972.2  930.09  4997.8  932.48  5003.1  932.48  5009.0  933.67  5022.4  934.36
  5134.4  936.69  5151.8  937.50  5180.2  937.65  5225.9  938.81  5271.7  941.73
  5287.2  942.04  5322.9  944.18  5408.5  946.88  5465.7  950.43  5534.3  953.01
#Mann=3,-1,0
  4426.9    0.12       0  4968.2    0.05       0  4972.2    0.12       0
Bank Sta=4968.2,4972.2
Exp/Cntr=0.3,0.1

Type RM Length L Ch R = 1,591,312,312,312
BEGIN DESCRIPTION:
XS7923
END DESCRIPTION:
XS GIS Cut Line= 3
      2211245.83     13815989.91      2211249.31     13815545.49
      2210884.73     13815302.44
#Sta/Elev= 30
  4406.8  939.57  4541.7  938.77  4581.7  939.62  4601.7  938.85  4681.7  937.48
  4721.7  937.30  4741.7  936.24  4791.7  935.43  4856.2  935.58  4918.9  932.56
  4927.9  931.22  4933.9  931.02  4940.5  929.51  4948.9  928.50  4989.0  927.13
  4989.2  926.63  4992.7  926.63  4993.0  927.13  5000.0  927.99  5027.0  928.72
  5042.1  931.40  5057.1  935.55  5063.1  936.60  5072.1  937.99  5093.1  939.74
  5120.8  943.53  5171.3  947.43  5192.9  948.43  5222.3  951.18  5289.4  953.16
#Mann=3,-1,0
  4406.8    0.12       0  4989.0    0.05       0  4993.0    0.12       0
Bank Sta=4989,4993
Exp/Cntr=0.3,0.1

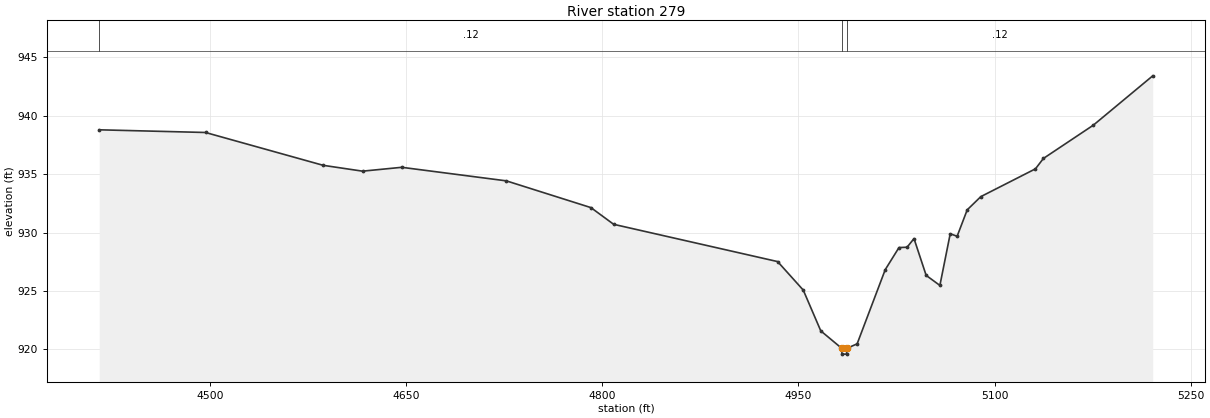
Type RM Length L Ch R = 1,279,0,0,0
BEGIN DESCRIPTION:
XS7922
END DESCRIPTION:
XS GIS Cut Line= 4
      2211280.56     13815816.31      2211287.50     13815489.93
      2211332.64     13815316.32      2211246.13     13815029.10
#Sta/Elev= 30
  4415.2  938.80  4496.5  938.57  4586.5  935.76  4616.6  935.26  4646.6  935.59
  4726.6  934.43  4791.3  932.14  4808.7  930.71  4934.1  927.52  4953.7  925.08
  4967.1  921.59  4983.1  920.10  4983.3  919.60  4986.8  919.60  4987.1  920.10
  4994.9  920.48  5016.4  926.83  5026.9  928.72  5033.1  928.75  5038.4  929.49
  5047.7  926.34  5058.2  925.48  5066.1  929.90  5071.4  929.69  5079.1  931.95
  5089.5  933.08  5131.3  935.46  5137.4  936.35  5175.6  939.20  5221.0  943.42
#Mann=3,-1,0
  4415.2    0.12       0  4983.1    0.05       0  4987.1    0.12       0
Bank Sta=4983.1,4987.1
Exp/Cntr=0.3,0.1

Chan Stop Cuts=-1