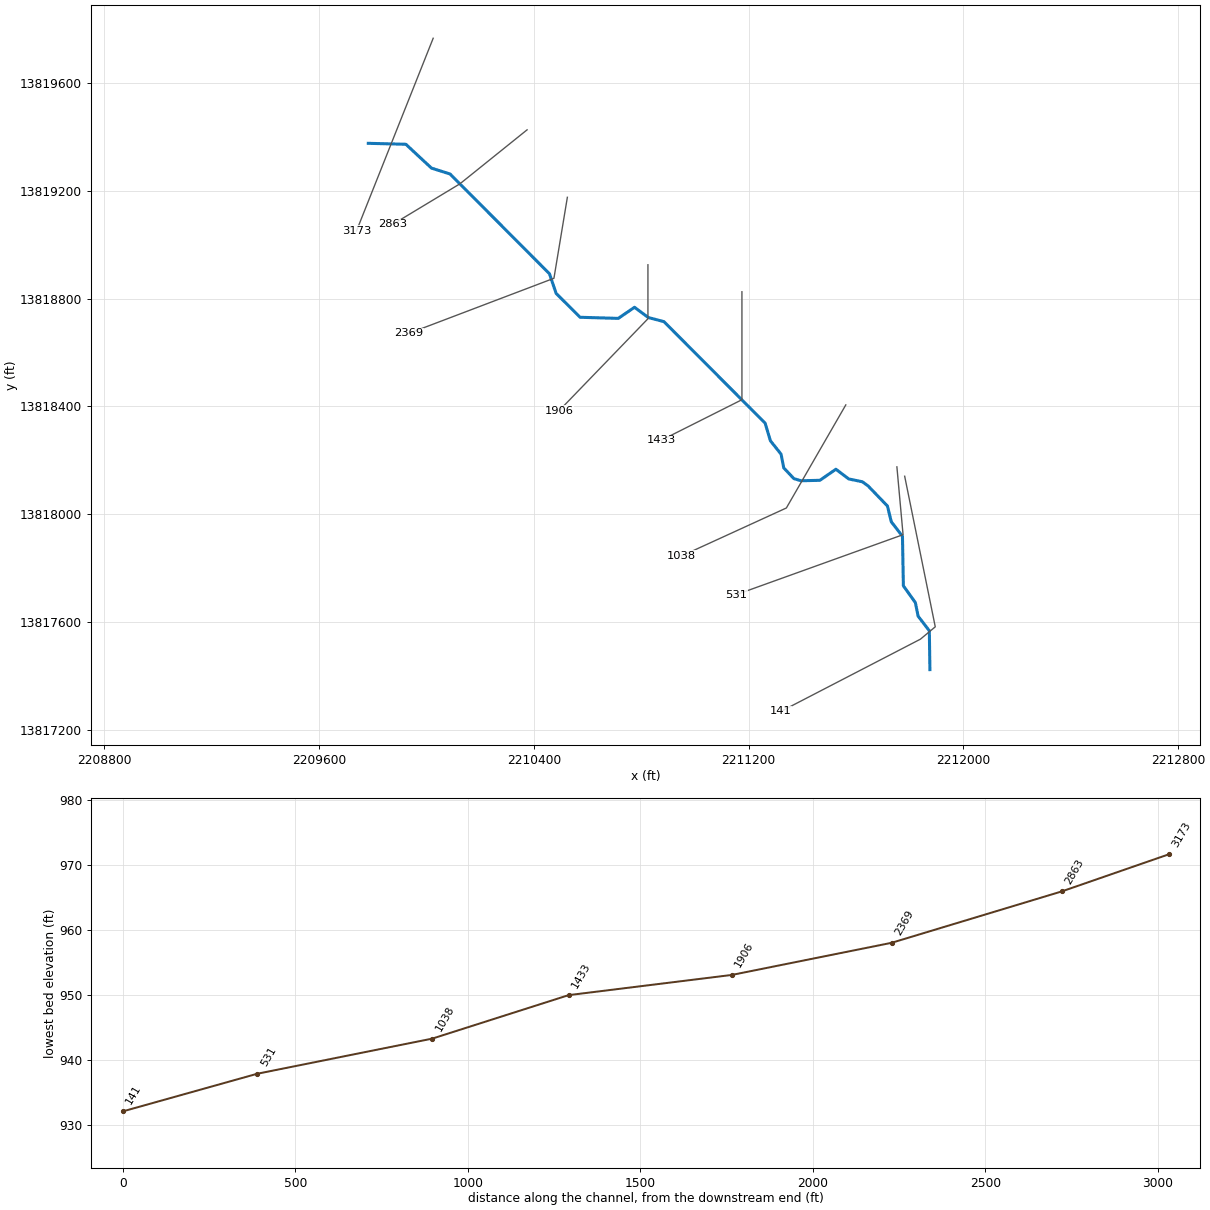
--- Upper Dry Comal Tributary 9.prj (project) ---

Proj Title=Upper Dry Comal Tributary 9 Base Level Engineering
Current Plan=p01
Default Exp/Contr=0.3,0.1
English Units
Geom File=g01
Flow File=f01
Plan File=p01
BEGIN DESCRIPTION:
Upper Dry Comal Tributary 9
END DESCRIPTION:

--- Upper Dry Comal Tributary 9.p01 (plan) ---

Plan Title=Multiple Run
Short Identifier=Multiple
Geom File=g01
Flow File=f01
Subcritical Flow
K Sum by GR= 0
Std Step Tol= 0.01
Critical Tol= 0.01
Num of Std Step Trials= 20
Max Error Tol= 0.3
Flow Tol Ratio= 0.001
Split Flow NTrial= 30
Split Flow Tol= 0.02
Split Flow Ratio= 0.02
Log Output Level= 0
Friction Slope Method= 1
Unsteady Friction Slope Method= 2
Unsteady Bridges Friction Slope Method= 1
Parabolic Critical Depth
Global Vel Dist=  1 , 1 , 1
Global Log Level= 0
CheckData=True
Encroach Param= -1, 0, 0, 0
BEGIN DESCRIPTION:
Multiple Run
END DESCRIPTION:

--- Upper Dry Comal Tributary 9.f01 (steady flow) ---

Flow Title=Multiple
Number of Profiles=7
Profile Names=10-year,25-year,50-year,1pct_min,100-year,1pct_plu,500-year
River Rch & RM= Upper Dry Comal ,Reach-1,3173
     645    1054    1430     942    1880    3752    3210
Boundary for River Rch & Prof#=Upper Dry Comal ,Reach-1,1
Up Type=0
Dn Type=3
Dn Slope=0.005
Boundary for River Rch & Prof#=Upper Dry Comal ,Reach-1,2
Up Type=0
Dn Type=3
Dn Slope=0.005
Boundary for River Rch & Prof#=Upper Dry Comal ,Reach-1,3
Up Type=0
Dn Type=3
Dn Slope=0.005
Boundary for River Rch & Prof#=Upper Dry Comal ,Reach-1,4
Up Type=0
Dn Type=3
Dn Slope=0.005
Boundary for River Rch & Prof#=Upper Dry Comal ,Reach-1,5
Up Type=0
Dn Type=3
Dn Slope=0.005
Boundary for River Rch & Prof#=Upper Dry Comal ,Reach-1,6
Up Type=0
Dn Type=3
Dn Slope=0.005
Boundary for River Rch & Prof#=Upper Dry Comal ,Reach-1,7
Up Type=0
Dn Type=3
Dn Slope=0.005

--- Upper Dry Comal Tributary 9.g01 (geometry) ---

Geom Title=Existing Conditions

River Reach=Upper Dry Comal ,Reach-1
Reach XY= 30
      2209783.67     13819375.00      2209923.55     13819371.50
      2210018.96     13819283.18      2210088.21     13819261.37
      2210458.35     13818891.67      2210483.15     13818818.93
      2210572.54     13818730.45      2210714.56     13818726.37
      2210775.01     13818767.47      2210826.65     13818729.45
      2210884.68     13818714.25      2211261.38     13818338.21
      2211281.10     13818272.81      2211320.80     13818223.23
      2211330.72     13818172.41      2211368.54     13818132.64
      2211394.95     13818124.75      2211465.36     13818126.43
      2211525.01     13818167.47      2211572.72     13818131.41
      2211623.36     13818121.09      2211645.13     13818105.24
      2211716.87     13818031.07      2211731.14     13817972.83
      2211772.76     13817919.07      2211776.20     13817735.50
      2211820.81     13817673.26      2211831.11     13817622.82
      2211872.80     13817569.09      2211875.00     13817425.00

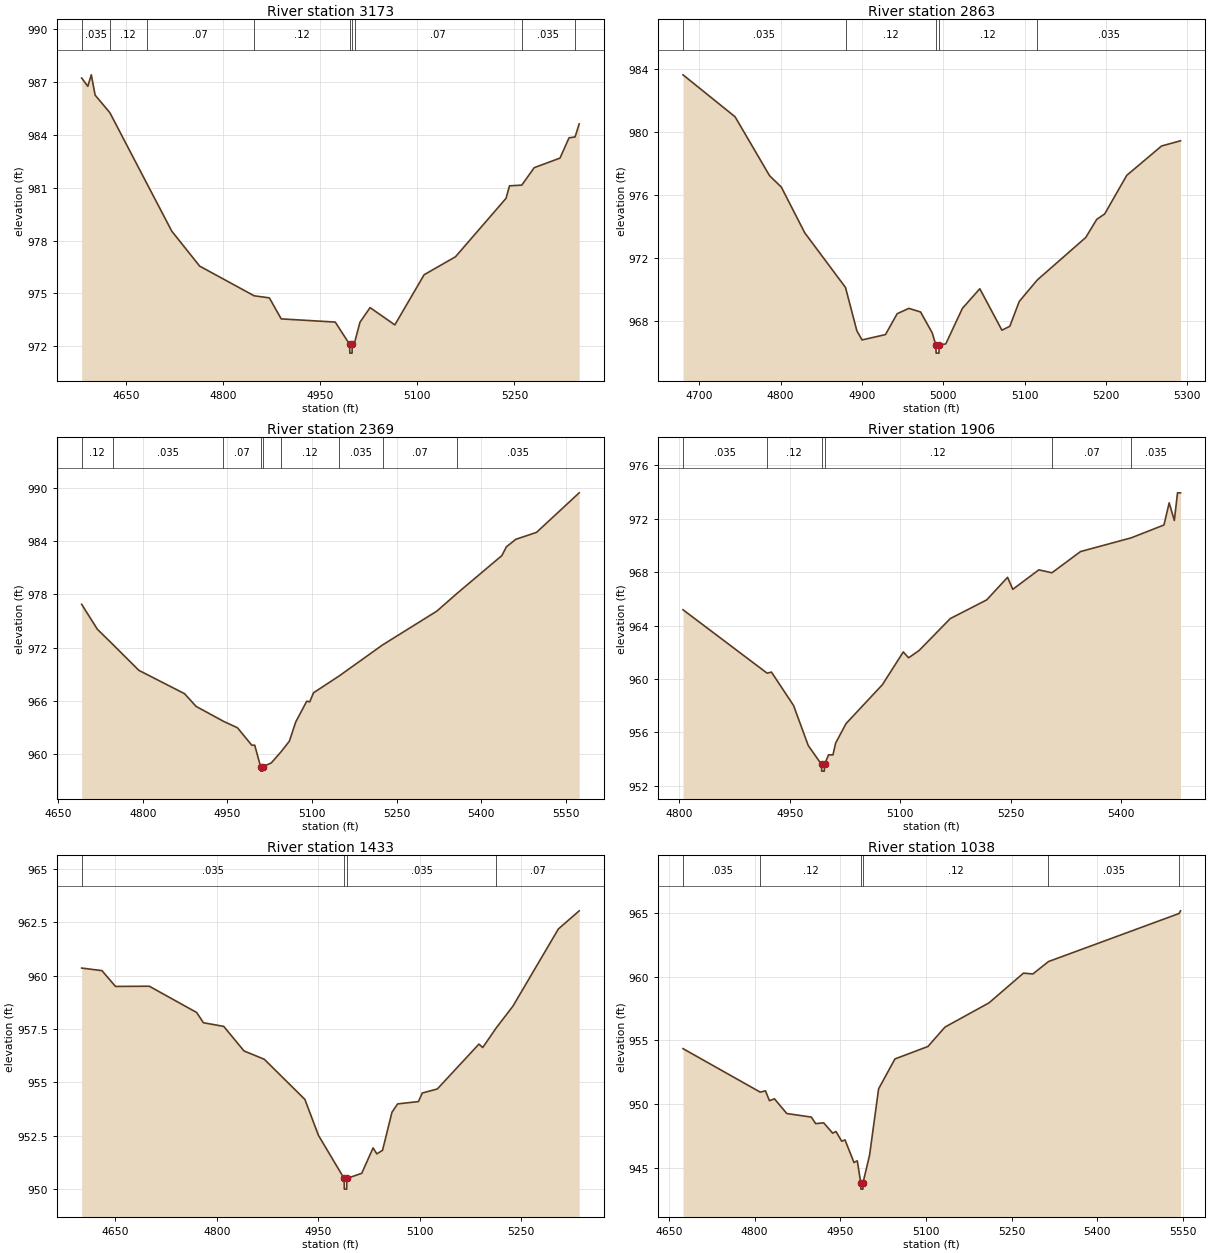
Type RM Length L Ch R = 1,3173,310,310,310
BEGIN DESCRIPTION:
XS7926
END DESCRIPTION:
XS GIS Cut Line= 2
      2210025.35     13819764.34      2209739.79     13819050.44
#Sta/Elev= 30
  4581.2  987.21  4590.7  986.74  4596.1  987.39  4602.0  986.24  4624.7  985.25
  4681.4  981.27  4720.5  978.53  4763.6  976.55  4847.7  974.87  4871.3  974.75
  4889.6  973.56  4973.1  973.38  4995.3  972.12  4995.6  971.62  4999.1  971.62
  4999.3  972.12  5003.2  972.25  5011.3  973.37  5026.9  974.20  5065.2  973.22
  5110.4  976.06  5158.9  977.08  5237.0  980.39  5242.4  981.10  5261.4  981.14
  5280.6  982.13  5320.4  982.67  5334.4  983.82  5343.7  983.87  5350.1  984.61
#Mann=9,-1,0
  4581.2   0.035       0  4624.7    0.12       0  4681.4    0.07       0
  4847.7    0.12       0  4995.3    0.05       0  4999.3    0.12       0
  5003.2    0.07       0  5261.4   0.035       0  5343.7    0.07       0
Bank Sta=4995.3,4999.3
Exp/Cntr=0.3,0.1

Type RM Length L Ch R = 1,2863,494,494,494
BEGIN DESCRIPTION:
Upper Dry Comal Tributary 9 6.0
END DESCRIPTION:
XS GIS Cut Line= 3
      2210374.99     13819424.99      2210125.00     13819225.00
      2209875.00     13819075.00
#Sta/Elev= 30
  4680.1  983.65  4744.1  980.98  4786.5  977.23  4801.0  976.50  4829.8  973.59
  4879.9  970.11  4893.8  967.36  4900.2  966.77  4929.0  967.11  4943.4  968.44
  4957.8  968.78  4972.2  968.55  4986.6  967.21  4991.0  966.43  4991.3  965.93
  4994.8  965.93  4995.0  966.43  5003.2  966.52  5023.6  968.78  5045.0  970.03
  5072.2  967.39  5081.9  967.64  5093.5  969.22  5115.7  970.59  5175.2  973.29
  5188.8  974.45  5198.5  974.79  5225.7  977.25  5268.5  979.12  5291.8  979.45
#Mann=5,-1,0
  4680.1   0.035       0  4879.9    0.12       0  4991.0    0.05       0
  4995.0    0.12       0  5115.7   0.035       0
Bank Sta=4991,4995
Exp/Cntr=0.3,0.1

Type RM Length L Ch R = 1,2369,463,463,463
BEGIN DESCRIPTION:
Upper Dry Comal Tributary 9 5.0
END DESCRIPTION:
XS GIS Cut Line= 3
      2210525.01     13819175.05      2210475.00     13818875.00
      2209934.23     13818670.58
#Sta/Elev= 30
  4691.5  976.88  4719.4  974.06  4746.3  972.38  4792.9  969.42  4874.0  966.78
  4894.3  965.35  4943.0  963.66  4967.8  962.93  4993.2  960.96  4998.4  960.96
  5008.8  958.53  5009.0  958.03  5012.5  958.03  5012.8  958.53  5027.8  958.96
  5044.5  960.17  5059.8  961.41  5071.1  963.58  5090.6  965.93  5096.0  965.86
  5102.6  966.88  5148.7  968.81  5225.1  972.29  5321.3  976.11  5356.9  978.10
  5436.7  982.39  5444.7  983.38  5461.5  984.23  5498.1  985.01  5573.8  989.48
#Mann=9,-1,0
  4691.5    0.12       0  4746.3   0.035       0  4943.0    0.07       0
  5008.8    0.05       0  5012.8    0.07       0  5044.5    0.12       0
  5148.7   0.035       0  5225.1    0.07       0  5356.9   0.035       0
Bank Sta=5008.8,5012.8
Exp/Cntr=0.3,0.1

Type RM Length L Ch R = 1,1906,473,473,473
BEGIN DESCRIPTION:
Upper Dry Comal Tributary 9 4.0
END DESCRIPTION:
XS GIS Cut Line= 3
      2210825.00     13818924.98      2210825.00     13818725.00
      2210494.07     13818384.08
#Sta/Elev= 30
  4805.3  965.19  4919.4  960.44  4925.3  960.52  4955.3  958.02  4975.3  955.01
  4993.3  953.60  4993.5  953.10  4997.0  953.10  4997.3  953.60  5002.8  954.32
  5008.8  954.32  5012.4  955.20  5026.5  956.66  5075.9  959.58  5104.2  962.03
  5111.4  961.59  5125.5  962.13  5168.0  964.53  5217.4  965.93  5245.7  967.62
  5252.8  966.72  5288.1  968.18  5305.9  967.96  5344.7  969.55  5413.6  970.58
  5457.9  971.54  5465.0  973.20  5472.0  971.88  5476.3  973.95  5480.4  973.95
#Mann=6,-1,0
  4805.3   0.035       0  4919.4    0.12       0  4993.3    0.05       0
  4997.3    0.12       0  5305.9    0.07       0  5413.6   0.035       0
Bank Sta=4993.3,4997.3
Exp/Cntr=0.3,0.1

Type RM Length L Ch R = 1,1433,395,395,395
BEGIN DESCRIPTION:
Upper Dry Comal Tributary 9 3.0
END DESCRIPTION:
XS GIS Cut Line= 3
      2211175.00     13818825.04      2211175.00     13818425.00
      2210874.96     13818274.98
#Sta/Elev= 30
  4600.0  960.35  4630.0  960.23  4650.0  959.49  4700.0  959.50  4770.0  958.27
  4780.0  957.79  4810.0  957.62  4840.0  956.47  4870.0  956.08  4930.0  954.20
  4950.0  952.52  4988.0  950.50  4988.3  950.00  4991.8  950.00  4992.0  950.50
  5014.0  950.74  5030.8  951.93  5036.4  951.65  5044.8  951.82  5058.7  953.60
  5067.1  953.99  5097.9  954.10  5103.5  954.50  5125.8  954.69  5187.3  956.79
  5192.9  956.63  5212.9  957.55  5237.6  958.57  5304.7  962.18  5335.5  963.03
#Mann=4,-1,0
  4600.0   0.035       0  4988.0   0.035       0  4992.0   0.035       0
  5212.9    0.07       0
Bank Sta=4988,4992
Exp/Cntr=0.3,0.1

Type RM Length L Ch R = 1,1038,507,507,507
BEGIN DESCRIPTION:
Upper Dry Comal Tributary 9 2.0
END DESCRIPTION:
XS GIS Cut Line= 3
      2211561.81     13818405.82      2211340.45     13818023.87
      2210949.92     13817845.96
#Sta/Elev= 30
  4674.9  954.35  4810.0  950.94  4819.2  951.04  4826.1  950.27  4835.0  950.41
  4856.5  949.26  4899.5  948.98  4907.0  948.47  4921.1  948.53  4936.8  947.72
  4942.6  947.85  4952.6  947.09  4958.4  947.19  4974.1  945.42  4979.9  945.55
  4985.9  943.83  4986.2  943.33  4989.7  943.33  4989.9  943.83  5001.4  946.00
  5017.2  951.20  5045.7  953.54  5103.5  954.52  5133.3  956.04  5210.3  957.94
  5270.6  960.27  5287.2  960.21  5314.4  961.18  5542.9  964.95  5545.5  965.16
#Mann=6,-1,0
  4674.9   0.035       0  4810.0    0.12       0  4985.9    0.05       0
  4989.9    0.12       0  5314.4   0.035       0  5542.9    0.07       0
Bank Sta=4985.9,4989.9
Exp/Cntr=0.3,0.1

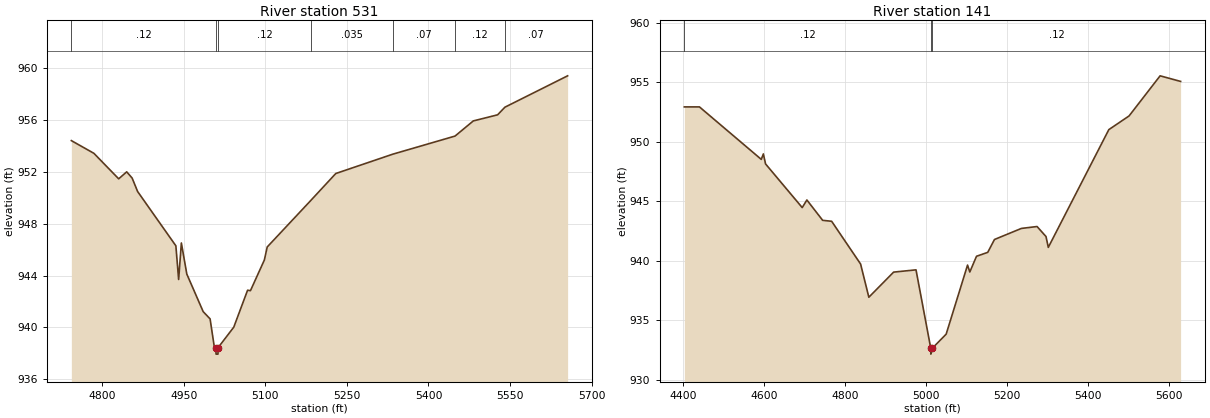
Type RM Length L Ch R = 1,531,390,390,390
BEGIN DESCRIPTION:
Upper Dry Comal Tributary 9 1.0
END DESCRIPTION:
XS GIS Cut Line= 3
      2211752.05     13818176.28      2211775.00     13817925.00
      2211153.80     13817702.69
#Sta/Elev= 30
  4743.6  954.42  4785.0  953.44  4830.6  951.47  4845.3  952.01  4855.3  951.53
  4865.4  950.49  4935.7  946.30  4940.8  943.70  4945.8  946.52  4955.8  944.12
  4985.9  941.22  4998.6  940.66  5006.0  938.59  5009.3  938.44  5009.6  937.94
  5013.1  937.94  5013.3  938.44  5042.1  940.02  5067.5  942.87  5072.8  942.84
  5098.3  945.20  5103.6  946.21  5184.8  949.85  5229.6  951.88  5334.2  953.37
  5448.8  954.77  5482.4  955.94  5527.0  956.41  5540.5  957.00  5655.7  959.42
#Mann=7,-1,0
  4743.6    0.12       0  5009.3    0.05       0  5013.3    0.12       0
  5184.8   0.035       0  5334.2    0.07       0  5448.8    0.12       0
  5540.5    0.07       0
Bank Sta=5009.3,5013.3
Exp/Cntr=0.3,0.1

Type RM Length L Ch R = 1,141,0,0,0
BEGIN DESCRIPTION:
XS7925
END DESCRIPTION:
XS GIS Cut Line= 4
      2211781.01     13818141.58      2211894.93     13817583.55
      2211839.58     13817537.76      2211319.98     13817270.04
#Sta/Elev= 30
  4402.7  952.93  4440.0  952.93  4592.8  948.52  4597.9  948.98  4603.3  948.14
  4693.9  944.47  4705.4  945.11  4744.4  943.40  4766.6  943.32  4838.1  939.73
  4858.5  936.94  4919.7  939.05  4975.0  939.24  5011.4  932.66  5011.6  932.16
  5015.4  932.66  5049.5  933.84  5102.3  939.64  5107.9  939.06  5124.4  940.38
  5152.2  940.71  5168.8  941.79  5235.3  942.72  5274.0  942.88  5296.1  942.04
  5301.8  941.13  5451.3  951.02  5501.3  952.17  5578.0  955.54  5628.6  955.07
#Mann=3,-1,0
  4402.7    0.12       0  5011.4    0.05       0  5015.4    0.12       0
Bank Sta=5011.4,5015.4
Exp/Cntr=0.3,0.1

Chan Stop Cuts=-1