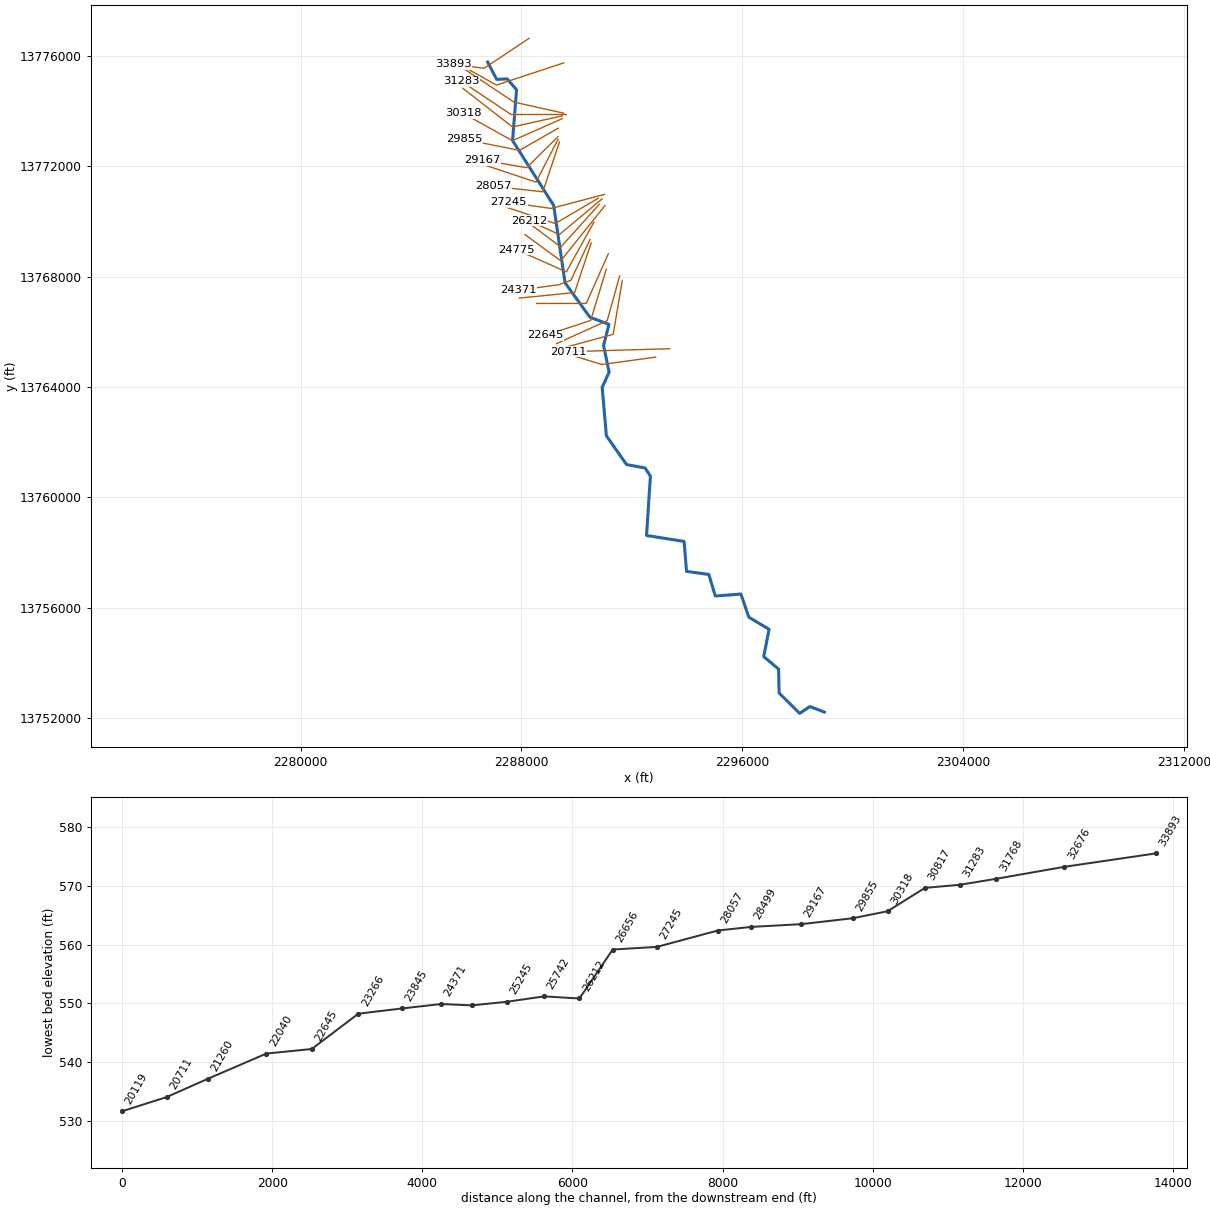
--- WALNUT BRANCH.prj (project) ---

Proj Title=WALNUT BRANCH Base Level Engineering
Current Plan=p01
Default Exp/Contr=0.3,0.1
English Units
Geom File=g01
Flow File=f01
Plan File=p01
Y Axis Title=Elevation
X Axis Title(PF)=Main Channel Distance
X Axis Title(XS)=Station
BEGIN DESCRIPTION:
WALNUT BRANCH
END DESCRIPTION:
DSS Export Rating Curves= 0
DSS Export Rating Curve Sorted= 0
DSS Export Volume Flow Curves= 0
DXF OffsetX= 0
DXF OffsetY= 0
DXF ScaleX= 1
DXF ScaleY= 10

--- WALNUT BRANCH.p01 (plan) ---

Plan Title=Multiple Run
Program Version=4.10
Short Identifier=Multiple
Geom File=g01
Flow File=f01
Subcritical Flow
K Sum by GR= 0
Std Step Tol= 0.01
Critical Tol= 0.01
Num of Std Step Trials= 20
Max Error Tol= 0.3
Flow Tol Ratio= 0.001
Split Flow NTrial= 30
Split Flow Tol= 0.02
Split Flow Ratio= 0.02
Log Output Level= 0
Friction Slope Method= 1
Unsteady Friction Slope Method= 2
Unsteady Bridges Friction Slope Method= 1
Parabolic Critical Depth
Global Vel Dist= 1 , 1 , 1
Global Log Level= 0
CheckData=True
Encroach Param=-1 ,0,0, 0
BEGIN DESCRIPTION:
Multiple Run
END DESCRIPTION:
Computation Interval=1HOUR
Output Interval=1HOUR
Run HTab= 0
Run UNet= 0
Run PostProcess= 0
Run WQNet= 0
UNET Theta= 1
UNET Theta Warmup= 1
UNET ZTol= 0.02
UNET ZSATol= 0.05
UNET MxIter= 20
UNET MaxInSteps= 0
UNET DtIC= 0
UNET DtMin= 0
UNET MaxCRTS= 20
UNET WFStab= 2
UNET SFStab= 1
UNET WFX= 1
UNET SFX= 1
UNET DSS MLevel= 4
UNET DZMax Abort= 100
UNET Convert EG Bridges= 0
UNET Use Existing IB Tables=-1
UNET Froude Reduction=False
UNET Froude Limit= 1
UNET Froude Power= 10
UNET Time Slicing=0,0, 5
UNET Junction Losses=0
Instantaneous Interval=1HOUR
Write IC File= 0
Write IC File at Sim End=0
Echo Input=False
Echo Parameters=False
Echo Output=False
Write Detailed= 0
WQ AD Non Conservative
WQ ULTIMATE=-1
WQ Max Comp Step=1HOUR
WQ Output Interval=15MIN
WQ Output Selected Increments= 0
WQ Output face flow=0
WQ Output face velocity=0
WQ Output face area=0
WQ Output face dispersion=0
WQ Output cell volume=0
WQ Output cell surface area=0
WQ Output cell continuity=0
WQ Output cumulative cell continuity=0
WQ Output face conc=0
WQ Output face dconc_dx=0
WQ Output face courant=0
WQ Output face peclet=0
WQ Output face adv mass=0
WQ Output face disp mass=0
WQ Output cell mass=0
WQ Output cell source sink temp=0
WQ Output cell source sink nsm=0
WQ Output MaxMinRange=-1
WQ Daily Max Min Mean=-1
WQ Daily Range=0
WQ Daily Time=0
WQ Create Restart=0
WQ Fixed Restart=0
WQ System Summary=0
WQ Use Fixed Temperature=0
Sorting and Armoring Iterations= 10
XS Update Threshold= 0.02
Hydraulics Update Threshold= 0.02
Energy Slope Method= 1
Volume Change Method= 0
XS Weighting Method= 0
Number of US Weighted Cross Sections= 1
Number of DS Weighted Cross Sections= 1
Upstream XS Weight=0.25
Main XS Weight=0.5
Downstream XS Weight=0.25
Number of DS XS's Weighted with US Boundary= 1
Upstream Boundary Weight= 1
Weight of XSs Associated with US Boundary= 0
Number of US XS's Weighted with DS Boundary= 1
Downstream Boundary Weight= 0.5
Weight of XSs Associated with DS Boundary= 0.5
Sediment Output Level= 4
Mass or Volume Output= 0
Output Increment Type= 1
Profile and TS Output Increment= 10
XS Output Flag= 0
XS Output Increment= 10
Disregard all LS=0
Disregard all Conn=0
Disregard all Breaches=0
Disregard all Pumps=0

--- WALNUT BRANCH.f01 (steady flow) ---

Flow Title=Multiple
Number of Profiles=7
Profile Names=10-year,25-year,50-year,1pct_min,100-year,1pct_plu,500-year
River Rch & RM= WALNUT BRANCH,Reach-1,33893
     484     757     996     633    1264    2521    2017
River Rch & RM= WALNUT BRANCH,Reach-1,31283
     637    1011    1343     861    1719    3429    2792
River Rch & RM= WALNUT BRANCH,Reach-1,27245
     746    1194    1593    1027    2049    4089    3362
River Rch & RM= WALNUT BRANCH,Reach-1,25742
     844    1361    1827    1184    2361    4712    3914
River Rch & RM= WALNUT BRANCH,Reach-1,22645
    1108    1813    2457    1606    3204    6392    5404
River Rch & RM= WALNUT BRANCH,Reach-1,20711
    1556    2586    3539    2334    4657    9292    8002
River Rch & RM= WALNUT BRANCH,Reach-1,14362
    1719    2865    3927    2594    5176   10328    8920
River Rch & RM= WALNUT BRANCH,Reach-1,9295
    1929    3233    4451    2951    5888   11748   10223
River Rch & RM= WALNUT BRANCH,Reach-1,4402
    2266    3844    5335    3567    7117   14200   12564
Boundary for River Rch & Prof#=WALNUT BRANCH,Reach-1,1
Up Type=0
Dn Type=3
Dn Slope=0.005
Boundary for River Rch & Prof#=WALNUT BRANCH,Reach-1,2
Up Type=0
Dn Type=3
Dn Slope=0.005
Boundary for River Rch & Prof#=WALNUT BRANCH,Reach-1,3
Up Type=0
Dn Type=3
Dn Slope=0.005
Boundary for River Rch & Prof#=WALNUT BRANCH,Reach-1,4
Up Type=0
Dn Type=3
Dn Slope=0.005
Boundary for River Rch & Prof#=WALNUT BRANCH,Reach-1,5
Up Type=0
Dn Type=3
Dn Slope=0.005
Boundary for River Rch & Prof#=WALNUT BRANCH,Reach-1,6
Up Type=0
Dn Type=3
Dn Slope=0.005
Boundary for River Rch & Prof#=WALNUT BRANCH,Reach-1,7
Up Type=0
Dn Type=3
Dn Slope=0.005

--- WALNUT BRANCH.g01 (geometry) ---

Geom Title=Existing Conditions
Program Version=4.10

River Reach=WALNUT BRANCH   ,Reach-1
Reach XY= 30
        2286775.       13775775.      2287101.53     13775148.01
      2287481.74     13775165.87      2287821.46     13774773.54
      2287677.24     13772930.93      2289166.32     13770581.67
      2289578.55     13767776.47      2290480.03     13766530.08
      2291171.39      13766273.5      2290974.51      13765509.8
      2291174.88     13764540.05      2290924.19     13763990.14
      2291075.72     13762235.71      2291808.24     13761191.43
      2292477.67     13761069.58      2292671.25     13760773.45
      2292530.83     13758622.69      2293891.71     13758408.37
      2293980.45     13757322.53      2294788.35     13757211.64
      2295022.53     13756430.45      2295949.03     13756502.35
      2296238.46     13755661.37      2296971.25     13755223.45
      2296776.04     13754235.44      2297315.99     13753782.02
       2297332.8     13752918.79      2298076.47     13752178.55
      2298449.87     13752425.54        2298975.       13752225.

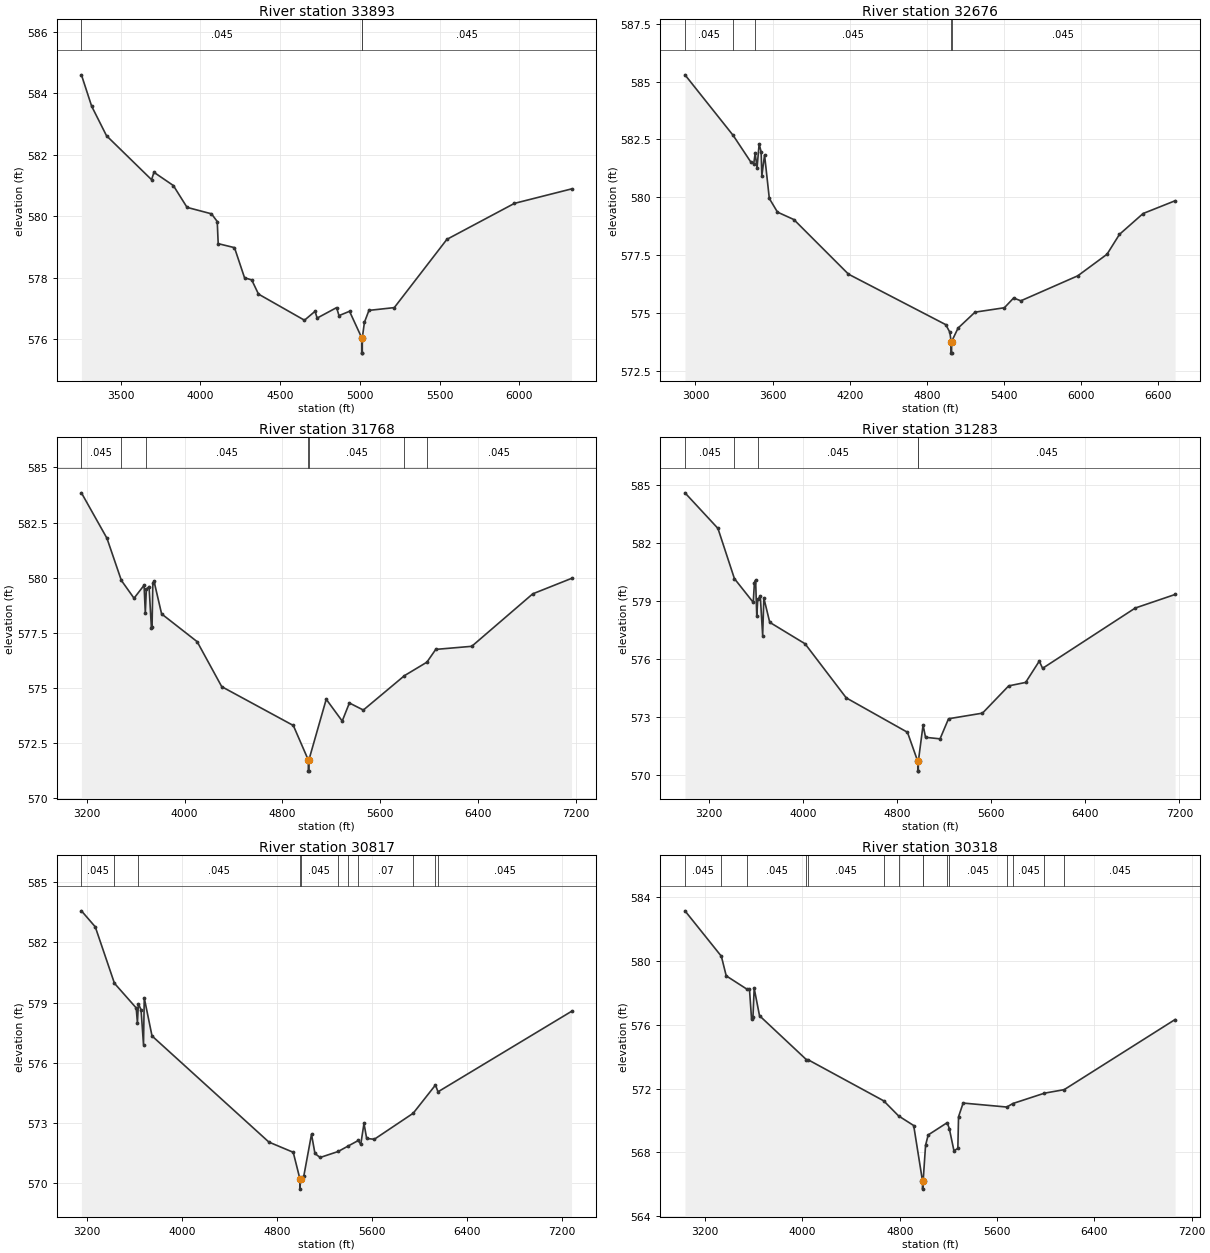
Type RM Length L Ch R = 1 ,33893   ,1217,1217,1217
BEGIN DESCRIPTION:
WALNUT BRANCH 59.0
END DESCRIPTION:
XS GIS Cut Line= 3
      2288274.46     13776634.75      2286646.83     13775549.66
      2285540.06     13775690.72
#Sta/Elev= 30
    3255   584.6  3319.1  583.58  3412.2  582.62  3694.6  581.19  3709.7  581.43
  3831.2     581    3917  580.29  4070.2  580.08  4106.3  579.83  4112.3  579.11
  4214.4  578.98  4277.5     578  4322.6  577.93  4364.7  577.47  4653.1  576.62
  4719.2  576.91  4732.6  576.69  4854.4  577.03  4869.4  576.77  4935.5  576.91
  5011.7  576.05  5011.9  575.55  5015.4  575.55  5015.7  576.05  5028.7  576.55
  5057.1  576.94    5216  577.03  5545.7  579.25  5969.1  580.42  6326.9  580.89
#Mann= 3 ,-1 , 0
    3255    .045       0  5011.7    .045       0  5015.7    .045       0
Bank Sta=5011.7,5015.7
XS Rating Curve= 0 ,0
Exp/Cntr=0.3,0.1

Type RM Length L Ch R = 1 ,32676   ,908,908,908
BEGIN DESCRIPTION:
XS7946
END DESCRIPTION:
XS GIS Cut Line= 3
      2289533.11     13775744.97       2287091.7     13774942.02
      2286008.28     13775548.74
#Sta/Elev= 30
  2918.3  585.29  3293.6  582.67  3432.1  581.51  3453.2  581.46  3464.4   581.9
  3478.9  581.28  3495.3  582.31  3510.7  581.96  3516.3  580.93  3537.3  581.83
  3574.3  579.95  3637.9  579.36  3765.1  579.04  4190.1  576.68  4946.7   574.5
  4978.5  574.17  4988.1  573.77  4988.4  573.27  4991.9  573.27  4992.1  573.77
  5042.1  574.35  5174.5  575.04  5402.4  575.23  5474.4  575.65  5530.7  575.53
  5973.6  576.61  6200.7  577.54  6297.7   578.4  6481.5   579.3  6730.1  579.85
#Mann= 5 ,-1 , 0
  2918.3    .045       0  3293.6    .035       0  3464.4    .045       0
  4988.1    .045       0  4992.1    .045       0
Bank Sta=4988.1,4992.1
XS Rating Curve= 0 ,0
Exp/Cntr=0.3,0.1

Type RM Length L Ch R = 1 ,31768   ,485,485,485
BEGIN DESCRIPTION:
WALNUT BRANCH 58.0
END DESCRIPTION:
XS GIS Cut Line= 3
      2289524.97     13773925.01        2287725.       13774325.
      2285925.01       13775525.
#Sta/Elev= 30
  3156.1  583.85  3364.8  581.79  3482.5  579.88  3586.3  579.07  3668.3  579.66
  3678.5   578.4  3686.9  579.47  3709.2   579.6  3728.4  577.72  3733.6  577.75
    3740  579.76  3750.2  579.83  3811.7  578.36  4102.4   577.1  4303.4  575.06
  4888.6   573.3  5011.4  571.73  5011.6  571.23  5015.3  571.23  5015.6  571.73
  5157.7  574.49  5288.4   573.5    5347  574.32  5461.2     574  5797.5  575.56
  5980.6  576.17  6053.1  576.75  6347.6  576.89  6846.3  579.27  7163.3  579.97
#Mann= 7 ,-1 , 0
  3156.1    .045       0  3482.5    .035       0  3686.9    .045       0
  5011.4    .045       0  5015.6    .045       0  5797.5    .035       0
  5980.6    .045       0
Bank Sta=5011.4,5015.6
XS Rating Curve= 0 ,0
Exp/Cntr=0.3,0.1

Type RM Length L Ch R = 1 ,31283   ,466,466,466
BEGIN DESCRIPTION:
WALNUT BRANCH 57.0
END DESCRIPTION:
XS GIS Cut Line= 3
      2289625.01       13773875.        2287625.       13773875.
      2285825.03     13775074.98
#Sta/Elev= 30
  2999.9  584.61  3279.9  582.77    3420  580.17  3579.9  578.94  3589.9  579.97
  3599.9  580.09  3609.9  578.24  3618.1   579.1  3639.9  579.25  3659.9  577.22
  3669.9  579.17  3719.9  577.91  4019.9   576.8  4369.9     574  4889.9  572.22
  4977.7  570.71    4978  570.21  4981.8  570.21  4982.2  570.71  5022.4  572.59
  5043.5  571.96  5166.7  571.88  5238.8  572.92  5527.2  573.21  5749.6  574.62
  5893.8   574.8  6009.5   575.9    6038  575.53  6825.2  578.65  7163.2  579.35
#Mann= 5 ,-1 , 0
  2999.9    .045       0    3420    .035       0  3618.1    .045       0
  4977.7    .045       0  4982.2    .045       0
Bank Sta=4977.7,4982.2
XS Rating Curve= 0 ,0
Exp/Cntr=0.3,0.1

Type RM Length L Ch R = 1 ,30817   ,499,499,499
BEGIN DESCRIPTION:
WALNUT BRANCH 56.0
END DESCRIPTION:
XS GIS Cut Line= 3
        2289475.       13773825.        2287675.       13773425.
      2285874.97     13774825.03
#Sta/Elev= 30
  3156.1  583.58  3272.6  582.78  3434.1  579.96  3617.1  578.73  3627.3  577.99
  3635.7  578.94    3658  578.63  3678.5   576.9  3684.9  579.23  3750.2  577.33
  4733.7  572.03  4938.5  571.52  4995.1  570.18  4995.5  569.68  4999.7  570.18
  5028.1  570.35  5092.3  572.42  5121.3  571.46  5164.7  571.26    5317  571.56
  5396.6  571.82  5486.3  572.11  5506.7  571.91  5533.9  572.96  5556.5  572.21
  5620.8  572.17    5948  573.47  6135.5  574.88  6156.8  574.54  7280.4  578.56
#Mann= 11 ,-1 , 0
  3156.1    .045       0  3434.1    .035       0  3635.7    .045       0
  4995.1    .045       0  4999.7    .045       0    5317     .07       0
  5396.6    .045       0  5486.3     .07       0    5948    .045       0
  6135.5     .07       0  6156.8    .045       0
Bank Sta=4995.1,4999.7
XS Rating Curve= 0 ,0
Exp/Cntr=0.3,0.1

Type RM Length L Ch R = 1 ,30318   ,463,463,463
BEGIN DESCRIPTION:
WALNUT BRANCH 55.0
END DESCRIPTION:
XS GIS Cut Line= 3
      2289474.99       13773725.        2287675.       13772925.
      2285874.99       13773925.
#Sta/Elev= 30
  3034.3  583.16  3333.4  580.31  3373.5  579.08  3546.7  578.23  3564.4  578.26
  3581.5  576.39  3593.1  576.47  3603.3   578.3  3647.1  576.58  4031.6  573.83
  4045.7  573.82  4667.9  571.24  4790.9  570.29  4914.5  569.69  4987.2   566.2
  4987.6   565.7  4992.2   566.2  5012.1  568.45  5033.8   569.1  5190.1  569.87
  5207.2   569.5  5245.4  568.11  5277.5  568.25  5283.2  570.24  5320.9   571.1
  5680.2  570.85  5729.4  571.07  5989.5  571.72  6151.5  571.94  7063.2  576.34
#Mann= 15 ,-1 , 0
  3034.3    .045       0  3333.4    .035       0  3546.7    .045       0
  4031.6     .07       0  4045.7    .045       0  4667.9    .035       0
  4790.9    .045       0  4987.2    .045       0  4992.2    .045       0
  5190.1    .035       0  5207.2    .045       0  5680.2     .07       0
  5729.4    .045       0  5989.5    .035       0  6151.5    .045       0
Bank Sta=4987.2,4992.2
XS Rating Curve= 0 ,0
Exp/Cntr=0.3,0.1

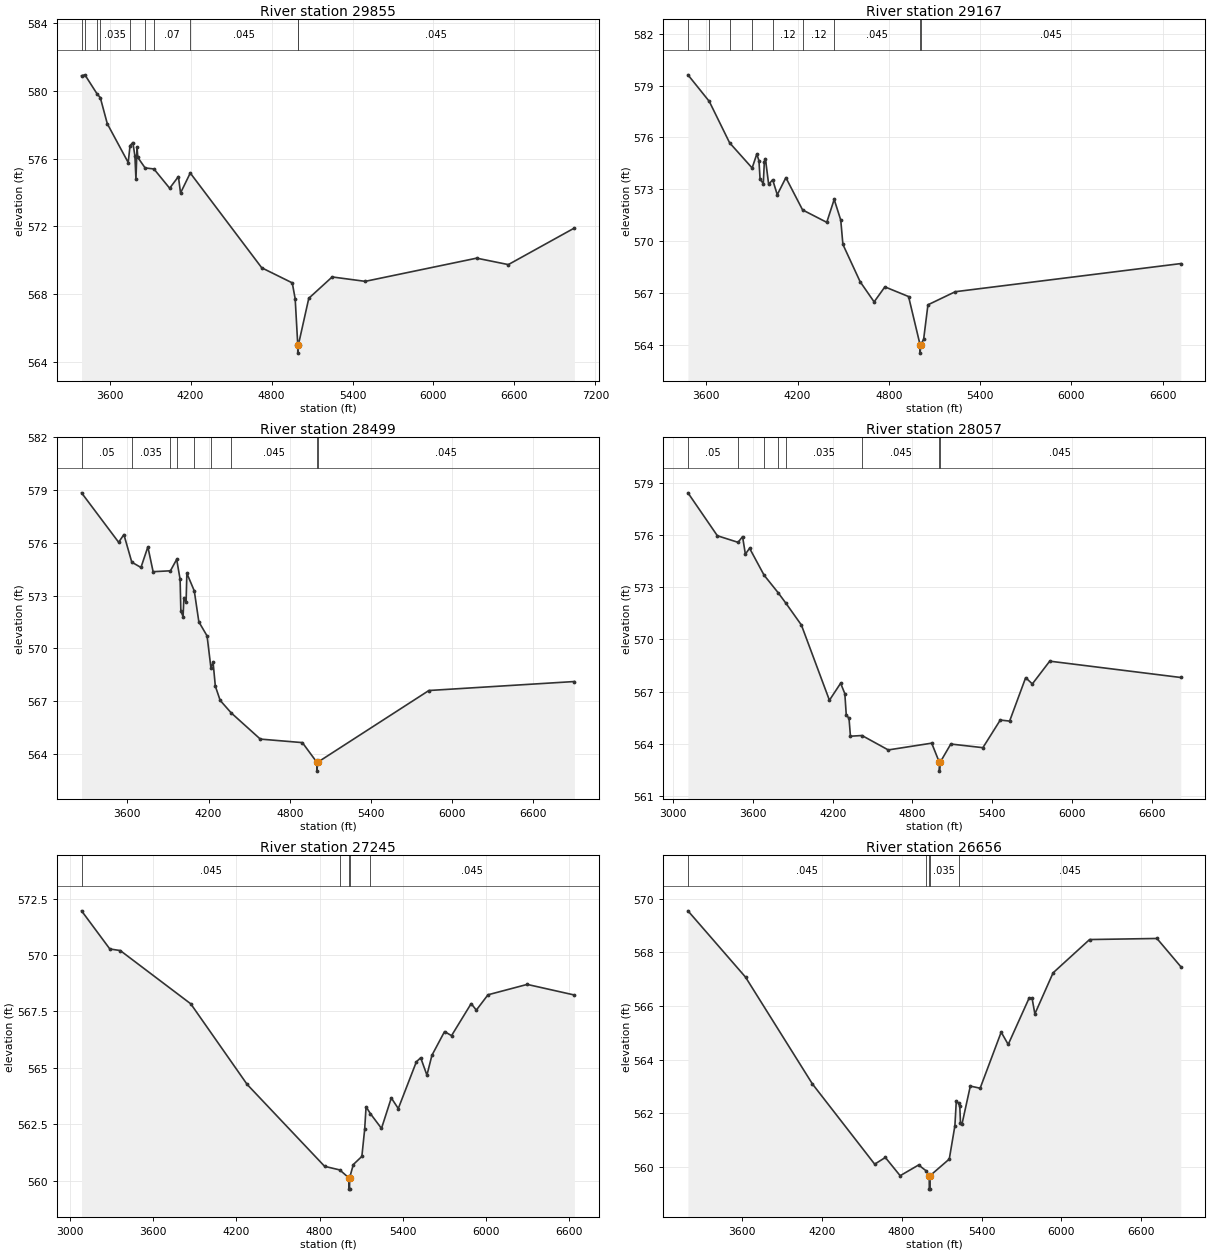
Type RM Length L Ch R = 1 ,29855   ,688,688,688
BEGIN DESCRIPTION:
WALNUT BRANCH 54.0
END DESCRIPTION:
XS GIS Cut Line= 3
      2289325.02     13773375.01        2287925.       13772575.
      2285924.99       13772975.
#Sta/Elev= 30
  3392.1   580.9  3416.9  580.95  3509.8  579.79  3530.7  579.61  3582.9  578.06
  3737.7  575.77  3751.5  576.77  3772.2  576.95  3787.3  576.17  3795.2  574.78
  3803.2  576.69  3808.9  576.07    3863  575.45  3928.2  575.39    4045  574.25
  4109.8  574.94  4125.6  573.97  4197.6  575.15  4727.4  569.55  4953.5  568.66
  4975.1  567.72  4994.2  565.01  4994.5  564.51  4999.2  565.01    5076  567.75
  5249.3  569.01  5494.1  568.75  6320.1  570.12  6554.7  569.74  7044.2   571.9
#Mann= 10 ,-1 , 0
  3392.1     .12       0  3416.9    .035       0  3509.8     .07       0
  3530.7    .035       0  3751.5     .07       0    3863    .045       0
  3928.2     .07       0  4197.6    .045       0  4994.2    .045       0
  4999.2    .045       0
Bank Sta=4994.2,4999.2
XS Rating Curve= 0 ,0
Exp/Cntr=0.3,0.1

Type RM Length L Ch R = 1 ,29167   ,668,668,668
BEGIN DESCRIPTION:
WALNUT BRANCH 52.0
END DESCRIPTION:
XS GIS Cut Line= 3
        2289325.       13773075.      2288187.62     13771947.23
      2286574.99       13772225.
#Sta/Elev= 30
    3480  579.63  3620.2  578.09  3753.8  575.69  3901.9  574.23  3932.5  575.04
  3946.7  574.65  3953.8  573.61    3975  573.31  3982.1   574.6  3989.1  574.77
  4010.4  573.28  4036.7  573.55  4066.9  572.68  4123.5  573.67  4233.3   571.8
  4392.2  571.08  4440.9  572.41  4484.1  571.21  4498.2   569.8  4611.4  567.64
  4703.3  566.47    4774  567.34  4929.6  566.78  5004.8     564  5005.2   563.5
  5009.9     564  5028.6   564.3  5056.9   566.3  5236.6  567.06  6718.1  568.69
#Mann= 9 ,-1 , 0
    3480     .07       0  3620.2     .05       0  3753.8    .035       0
  3901.9     .07       0  4036.7     .12       0  4233.3     .12       0
  4440.9    .045       0  5004.8    .045       0  5009.9    .045       0
Bank Sta=5004.8,5009.9
XS Rating Curve= 0 ,0
Exp/Cntr=0.3,0.1

Type RM Length L Ch R = 1 ,28499   ,442,442,442
BEGIN DESCRIPTION:
WALNUT BRANCH 51.0
END DESCRIPTION:
XS GIS Cut Line= 3
        2289325.       13772975.        2288525.       13771425.
      2286725.04     13772024.99
#Sta/Elev= 30
  3261.7  578.84  3535.8  576.03  3574.5  576.47  3632.9   574.9  3700.6   574.6
  3751.7  575.77  3790.4  574.36  3918.3  574.41  3964.6  575.06  3989.8  573.93
  3995.5  572.11    4012  571.81  4017.6  572.86  4034.1  572.62  4039.8  574.27
  4094.6  573.27  4128.4  571.51  4189.2  570.71  4217.7  568.89  4233.5  569.22
  4250.1  567.86  4285.8  567.05  4367.2  566.34  4582.4  564.85  4893.4  564.65
  5000.6  563.53    5001  563.03  5005.7  563.53  5828.2  567.61  6903.3  568.12
#Mann= 9 ,-1 , 0
  3261.7     .05       0  3632.9    .035       0  3918.3     .12       0
  3964.6    .035       0  4094.6     .12       0  4217.7     .12       0
  4367.2    .045       0  5000.6    .045       0  5005.7    .045       0
Bank Sta=5000.6,5005.7
XS Rating Curve= 0 ,0
Exp/Cntr=0.3,0.1

Type RM Length L Ch R = 1 ,28057   ,812,812,812
BEGIN DESCRIPTION:
WALNUT BRANCH 50.0
END DESCRIPTION:
XS GIS Cut Line= 3
      2289375.01     13772875.03        2288775.       13771075.
      2286974.98       13771275.
#Sta/Elev= 30
  3110.3  578.44  3331.7  575.97  3487.5  575.59  3521.4  575.92  3542.5  574.91
  3574.1  575.25  3683.3   573.7  3788.1   572.7  3848.1  572.08  3964.1  570.83
    4175   566.5  4259.3  567.48  4290.9  566.88  4301.5  565.67  4322.5  565.45
  4333.1  564.43  4420.1  564.47  4617.7  563.64  4944.5  564.03  5002.5  562.92
  5002.9  562.42  5007.6  562.92  5088.2  563.98  5329.7  563.77  5460.5  565.36
  5530.9   565.3  5651.6   567.8  5701.9  567.44  5832.7  568.75  6818.8  567.81
#Mann= 8 ,-1 , 0
  3110.3     .05       0  3487.5    .035       0  3683.3     .05       0
  3788.1     .07       0  3848.1    .035       0  4420.1    .045       0
  5002.5    .045       0  5007.6    .045       0
Bank Sta=5002.5,5007.6
XS Rating Curve= 0 ,0
Exp/Cntr=0.3,0.1

Type RM Length L Ch R = 1 ,27245   ,589,589,589
BEGIN DESCRIPTION:
WALNUT BRANCH 49.0
END DESCRIPTION:
XS GIS Cut Line= 3
      2291008.77     13770981.51      2289077.38     13770471.54
      2287538.25     13770688.31
#Sta/Elev= 30
  3084.7  571.96  3288.4  570.27  3363.7   570.2  3871.7  567.84    4278  564.27
  4836.5  560.64  4945.8  560.48  5010.8  560.13  5011.3  559.63  5016.1  559.63
  5016.6  560.13  5043.4  560.72  5104.9  561.08  5125.1  562.28  5135.2  563.28
  5165.7  562.98  5246.3  562.32    5317  563.67  5367.4   563.2  5497.6  565.27
    5529  565.45  5573.8  564.68  5609.8  565.56  5700.7  566.61  5751.2  566.43
  5892.6  567.85  5929.8  567.56  6013.8  568.24  6296.5   568.7  6636.6  568.23
#Mann= 5 ,-1 , 0
  3084.7    .045       0  4945.8    .035       0  5010.8     .05       0
  5016.6    .035       0  5165.7    .045       0
Bank Sta=5010.8,5016.6
XS Rating Curve= 0 ,0
Exp/Cntr=0.3,0.1

Type RM Length L Ch R = 1 ,26656   ,444,444,444
BEGIN DESCRIPTION:
WALNUT BRANCH 48.0
END DESCRIPTION:
XS GIS Cut Line= 3
      2290780.95     13770840.46        2289225.       13769925.
      2287425.04     13770524.99
#Sta/Elev= 30
  3194.3  569.55  3626.9  567.08  4129.4   563.1  4597.3  560.11  4677.4  560.36
  4788.7  559.68  4927.4  560.08  4981.7  559.87  5007.1  559.68  5007.6  559.18
  5012.6  559.18  5013.1  559.68  5157.7   560.3  5199.9  561.54  5210.4  562.46
    5227  562.38  5236.8  562.26    5242  561.64  5252.6  561.59  5315.8  563.02
  5389.6  562.94  5547.7  565.03  5600.4  564.57  5758.5  566.31  5779.6   566.3
  5800.7  565.71  5937.7  567.24  6211.8  568.48  6717.8  568.52  6896.9  567.47
#Mann= 5 ,-1 , 0
  3194.3    .045       0  4981.7    .035       0  5007.1     .05       0
  5013.1    .035       0    5227    .045       0
Bank Sta=5007.1,5013.1
XS Rating Curve= 0 ,0
Exp/Cntr=0.3,0.1

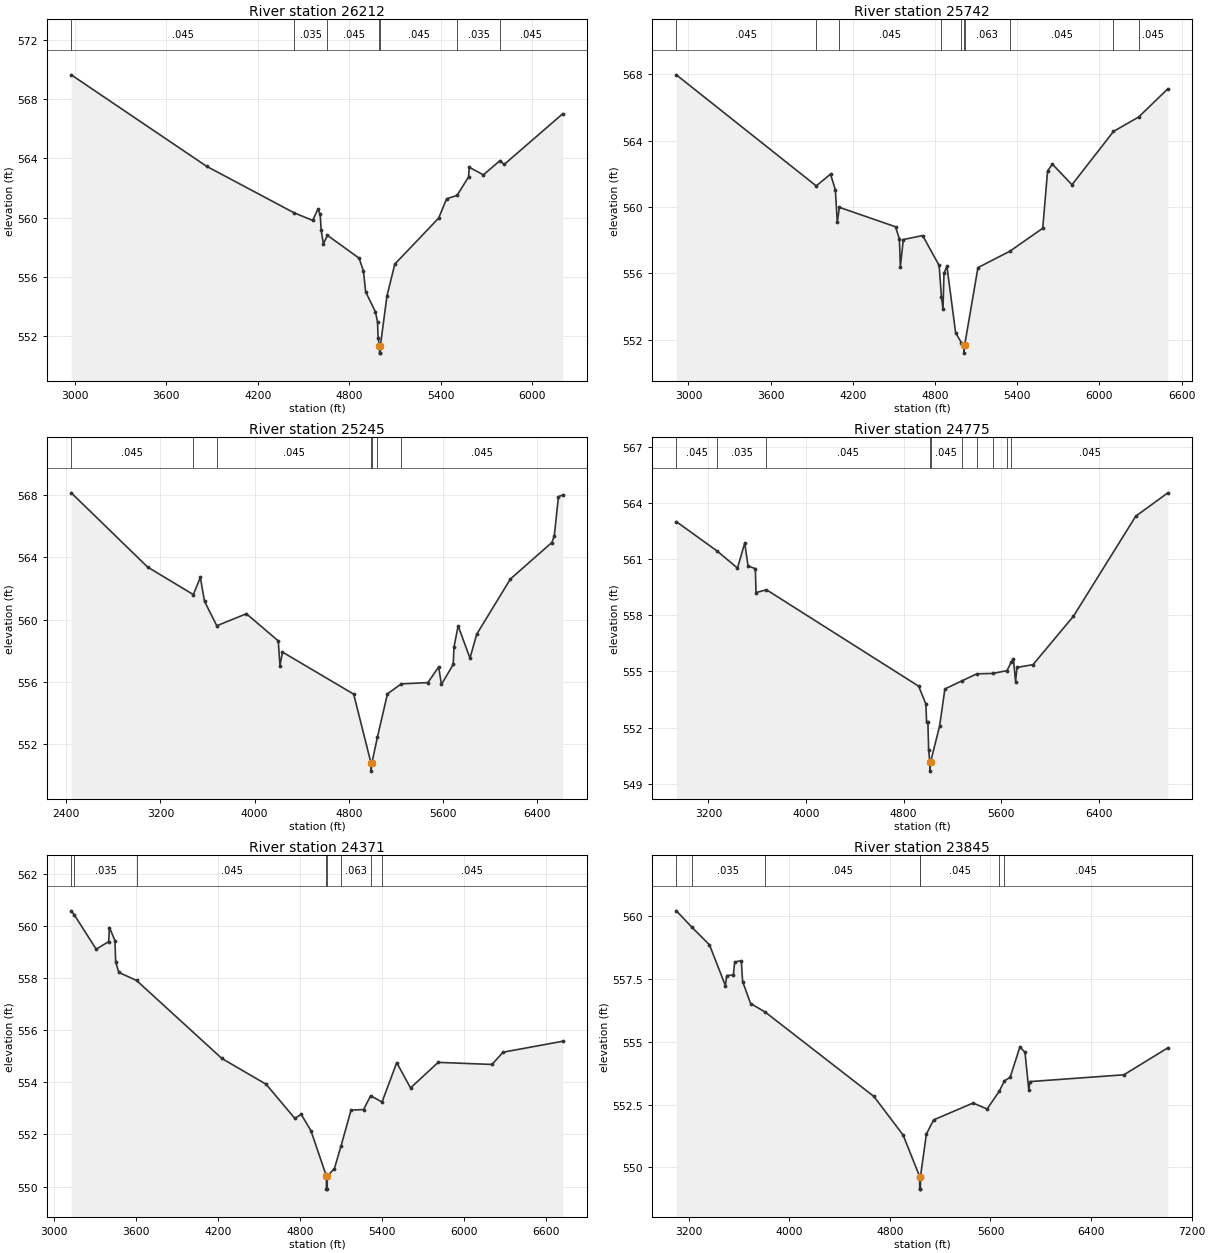
Type RM Length L Ch R = 1 ,26212   ,470,470,470
BEGIN DESCRIPTION:
WALNUT BRANCH 47.0
END DESCRIPTION:
XS GIS Cut Line= 3
      2290922.01     13770818.77        2289375.       13769525.
      2288275.01       13770025.
#Sta/Elev= 30
  2976.7  569.65  3864.5  563.47  4437.7  560.33  4560.7  559.81  4595.9  560.58
  4610.2  560.21  4616.7  559.15    4631  558.23  4657.9   558.8  4865.2  557.26
  4893.9   556.4  4908.2  554.99  4971.9  553.65  4986.2  552.97  4990.1  551.87
  4999.1  551.34  4999.6  550.84  5004.7  550.84  5005.2  551.34  5048.3  554.71
    5100  556.86  5387.8  559.97  5439.4  561.27  5508.1   561.5  5583.3  562.74
  5588.8   563.4    5681  562.89  5789.9  563.85  5817.2  563.59  6201.7  567.02
#Mann= 7 ,-1 , 0
  2976.7    .045       0  4437.7    .035       0  4657.9    .045       0
  4999.1    .045       0  5005.2    .045       0  5508.1    .035       0
  5789.9    .045       0
Bank Sta=4999.1,5005.2
XS Rating Curve= 0 ,0
Exp/Cntr=0.3,0.1

Type RM Length L Ch R = 1 ,25742   ,497,497,497
BEGIN DESCRIPTION:
WALNUT BRANCH 46.0
END DESCRIPTION:
XS GIS Cut Line= 3
      2290825.03     13770625.04        2289425.       13769075.
      2288225.01       13769975.
#Sta/Elev= 30
  2911.3  567.96  3932.6  561.27  4037.1  561.98  4072.3  561.04  4086.5  559.08
  4101.9  559.98  4511.7  558.81    4540  558.07  4546.8  556.39  4568.4  558.04
  4709.7  558.28    4830  556.48  4846.5  554.61  4858.4  553.85  4865.3     556
  4886.8  556.44  4950.3  552.43  4992.2  551.83  5010.3   551.7  5010.8   551.2
  5016.7   551.7  5113.5  556.35    5347  557.34  5586.5  558.72  5621.9  562.18
  5657.3  562.58    5800  561.34  6103.1  564.55  6286.8  565.42    6500  567.12
#Mann= 10 ,-1 , 0
  2911.3    .045       0  3932.6    .035       0  4101.9    .045       0
  4846.5    .035       0  4992.2    .063       0  5010.3     .05       0
  5016.7    .063       0    5347    .045       0  6103.1    .035       0
  6286.8    .045       0
Bank Sta=5010.3,5016.7
XS Rating Curve= 0 ,0
Exp/Cntr=0.3,0.1

Type RM Length L Ch R = 1 ,25245   ,470,470,470
BEGIN DESCRIPTION:
WALNUT BRANCH 45.0
END DESCRIPTION:
XS GIS Cut Line= 3
      2291025.03     13770575.03        2289425.       13768575.
      2288125.01     13769524.99
#Sta/Elev= 30
  2443.5  568.14  3091.1  563.38  3479.5  561.61  3539.3  562.71  3574.5  561.18
  3678.7  559.61  3929.9  560.38  4200.4  558.64  4214.8  557.05  4236.4  557.92
  4840.7  555.22    4988  550.78  4988.5  550.28  4994.4  550.78  5041.7  552.45
  5127.2  555.24  5244.5  555.88  5470.1  555.96  5562.1  556.97  5585.1  555.84
  5685.5  557.13  5691.7  558.25  5727.2   559.6  5827.6  557.53  5884.2  559.06
  6170.5  562.61  6521.9  564.95  6542.7  565.35  6578.2  567.89  6614.9  568.01
#Mann= 7 ,-1 , 0
  2443.5    .045       0  3479.5    .035       0  3678.7    .045       0
    4988    .045       0  4994.4    .045       0  5041.7    .063       0
  5244.5    .045       0
Bank Sta=4988,4994.4
XS Rating Curve= 0 ,0
Exp/Cntr=0.3,0.1

Type RM Length L Ch R = 1 ,24775   ,404,404,404
BEGIN DESCRIPTION:
WALNUT BRANCH 44.0
END DESCRIPTION:
XS GIS Cut Line= 3
      2290625.02     13769975.03        2289625.       13768175.
      2287825.03     13768974.99
#Sta/Elev= 30
  2936.8     563  3271.3  561.43  3437.9  560.52  3497.4  561.86  3524.8  560.63
  3584.3  560.49    3590  559.21  3675.6  559.36  4922.8  554.21  4982.2  553.26
    4988  552.29  4998.7  552.31  5004.9  550.81  5014.6  550.17  5015.1  549.67
  5021.1  550.17  5094.5  552.07  5138.2  554.06  5276.3  554.49  5400.6  554.87
  5531.4  554.89  5647.2  555.04    5683  555.51  5699.7  555.68  5717.5  554.45
  5729.2  555.21  5860.5  555.36  6192.2  557.95  6702.4  563.29  6965.7  564.54
#Mann= 10 ,-1 , 0
  2936.8    .045       0  3271.3    .035       0  3675.6    .045       0
  5014.6    .045       0  5021.1    .045       0  5276.3    .063       0
  5400.6    .035       0  5531.4    .045       0  5647.2    .063       0
    5683    .045       0
Bank Sta=5014.6,5021.1
XS Rating Curve= 0 ,0
Exp/Cntr=0.3,0.1

Type RM Length L Ch R = 1 ,24371   ,526,526,526
BEGIN DESCRIPTION:
H21555
END DESCRIPTION:
XS GIS Cut Line= 4
      2290486.89     13769355.67      2289792.46     13767869.59
      2289361.91     13767709.87      2287882.71     13767508.48
#Sta/Elev= 30
  3128.3  560.57  3151.4  560.41  3310.5   559.1  3401.9  559.39  3407.5  559.93
  3447.6  559.43  3453.2  558.61    3476  558.21  3605.7   557.9  4229.2  554.91
  4552.9  553.92  4762.7  552.61  4808.6  552.77  4880.2  552.14  4993.1   550.4
  4993.6   549.9  4999.1   549.9  4999.6   550.4  5051.8  550.69  5099.3  551.54
  5173.3  552.93  5265.1  552.95  5316.4  553.48  5399.9  553.24  5507.3  554.75
  5608.2  553.78  5810.1  554.76  6203.7  554.68  6284.4  555.15  6720.7  555.57
#Mann= 8 ,-1 , 0
  3128.3    .045       0  3151.4    .035       0  3605.7    .045       0
  4993.1    .045       0  4999.6    .045       0  5099.3    .063       0
  5316.4    .035       0  5399.9    .045       0
Bank Sta=4993.1,4999.6
XS Rating Curve= 0 ,0
Exp/Cntr=0.3,0.1

Type RM Length L Ch R = 1 ,23845   ,579,579,579
BEGIN DESCRIPTION:
WALNUT BRANCH 43.0
END DESCRIPTION:
XS GIS Cut Line= 3
      2290524.99     13769224.98        2289925.       13767425.
      2287925.02       13767225.
#Sta/Elev= 30
  3102.9  560.19  3224.6  559.55  3366.4  558.84  3492.9  557.22  3503.4  557.62
  3556.1  557.64  3566.7  558.16  3619.4  558.21  3629.9  557.38  3693.2  556.51
  3809.4  556.17  4673.5  552.82  4905.4  551.29  5037.1  549.64  5037.6  549.14
  5043.2  549.14  5043.7  549.64  5090.7  551.33  5148.5  551.89  5462.5  552.56
  5573.1  552.32  5670.3  553.03  5711.2  553.44  5756.5  553.58  5834.4  554.79
  5874.6  554.57  5904.7  553.08  5914.8  553.41    6661  553.68  7010.2  554.75
#Mann= 7 ,-1 , 0
  3102.9    .045       0  3224.6    .035       0  3809.4    .045       0
  5037.1    .045       0  5043.7    .045       0  5670.3    .035       0
  5711.2    .045       0
Bank Sta=5037.1,5043.7
XS Rating Curve= 0 ,0
Exp/Cntr=0.3,0.1

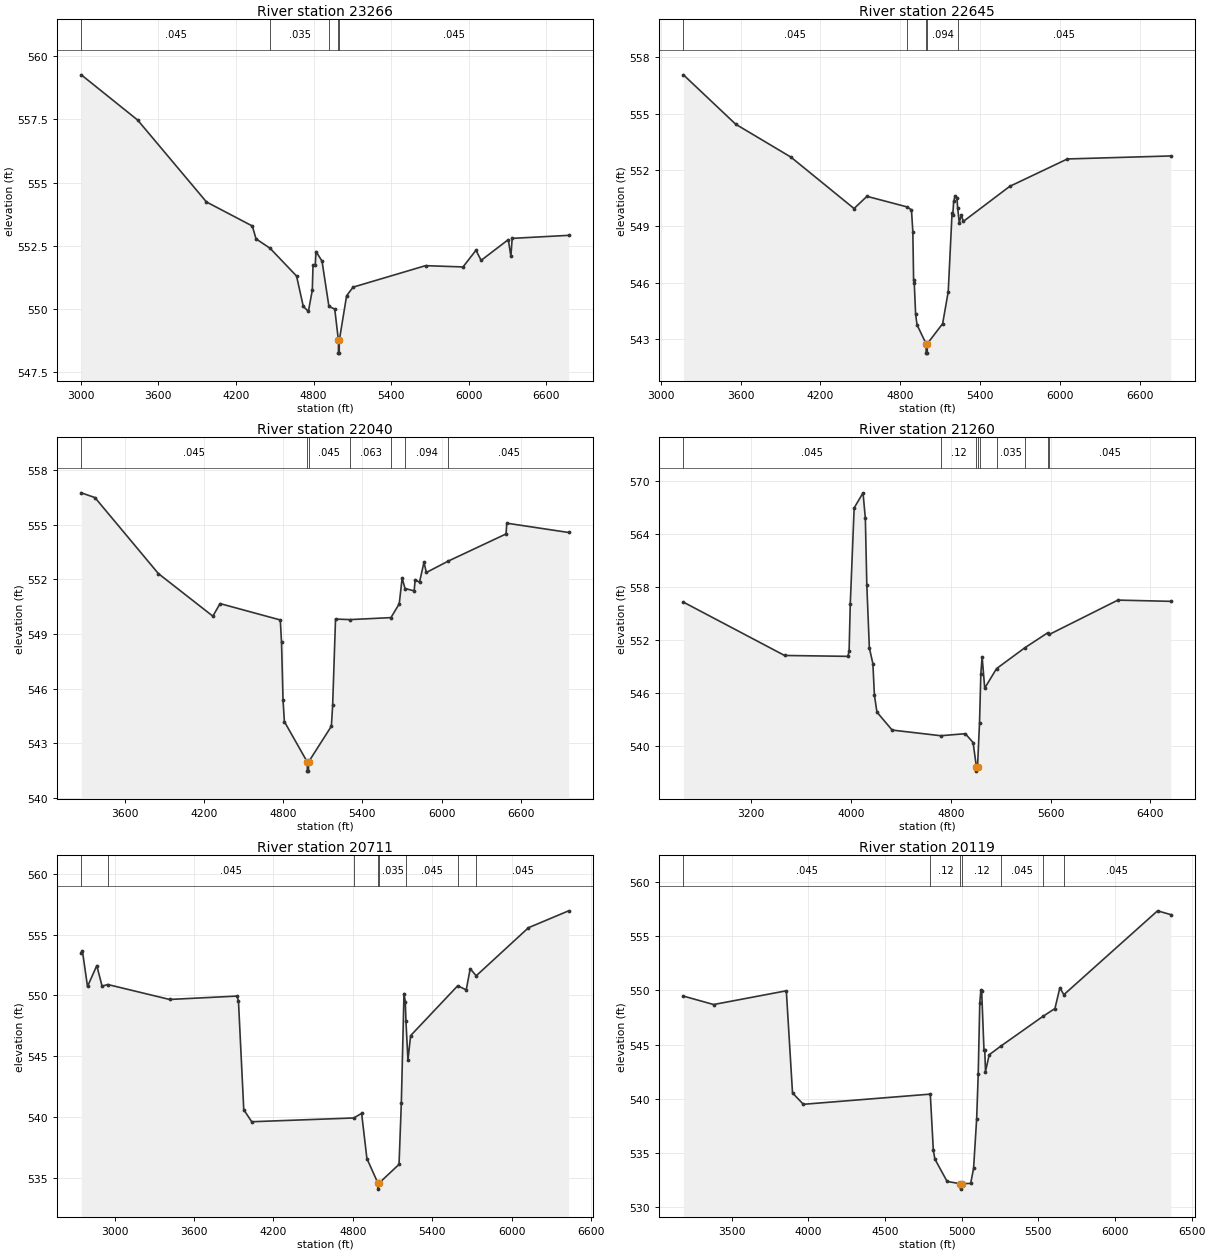
Type RM Length L Ch R = 1 ,23266   ,621,621,621
BEGIN DESCRIPTION:
WALNUT BRANCH 42.0
END DESCRIPTION:
XS GIS Cut Line= 3
      2291146.51     13768829.48      2290346.53     13767029.51
      2288548.26     13767029.51
#Sta/Elev= 30
  3004.5  559.26  3440.4  557.47  3972.4  554.23  4326.8  553.28  4355.5  552.77
  4463.7   552.4  4668.8   551.3  4720.7   550.1  4760.3   549.9  4790.5  550.74
    4796  551.72  4813.7  551.75  4819.2  552.27  4865.7  551.89    4919   550.1
  4964.2  549.99  4992.5  548.75    4993  548.25  4998.6  548.25  4999.1  548.75
  5055.8  550.52  5105.8  550.86  5665.8  551.71  5955.8  551.66  6055.8  552.32
  6095.8  551.92  6305.8  552.74  6325.8  552.08  6335.8  552.79  6772.5  552.91
#Mann= 5 ,-1 , 0
  3004.5    .045       0  4463.7    .035       0    4919    .045       0
  4992.5    .045       0  4999.1    .045       0
Bank Sta=4992.5,4999.1
XS Rating Curve= 0 ,0
Exp/Cntr=0.3,0.1

Type RM Length L Ch R = 1 ,22645   ,605,605,605
BEGIN DESCRIPTION:
WALNUT BRANCH 40.0
END DESCRIPTION:
XS GIS Cut Line= 3
        2291075.     13768274.99       2290507.5     13766414.46
      2288874.98     13765874.99
#Sta/Elev= 30
  3170.4  557.06  3563.5  554.43  3978.3  552.68  4453.4  549.94  4550.4  550.59
  4850.3  550.03    4885  549.87  4895.4  548.71    4901  546.16  4906.2  545.95
  4916.3  544.31  4926.8  543.75  4994.9  542.74  4995.4  542.24  5003.5  542.24
    5004  542.74  5119.5  543.81  5161.6  545.52  5190.1  549.69  5195.3  549.58
  5202.4  550.32    5213  550.61  5227.1  550.49  5232.4  549.97  5244.6  549.18
  5258.8  549.58  5276.2  549.26  5623.7  551.12  6057.4  552.58  6834.9  552.74
#Mann= 5 ,-1 , 0
  3170.4    .045       0  4850.3    .094       0  4994.9     .05       0
    5004    .094       0  5232.4    .045       0
Bank Sta=4994.9,5004
XS Rating Curve= 0 ,0
Exp/Cntr=0.3,0.1

Type RM Length L Ch R = 1 ,22040   ,780,780,780
BEGIN DESCRIPTION:
WALNUT BRANCH 39.0
END DESCRIPTION:
XS GIS Cut Line= 3
      2291557.84     13768029.02      2291106.46     13766405.78
      2289275.01     13765575.01
#Sta/Elev= 30
  3268.2  556.76  3371.6   556.5  3852.9  552.32  4265.8  549.98  4320.7  550.67
  4777.4  549.77  4786.6  548.54  4798.2  545.35  4808.5  544.18  4982.1  541.96
  4982.6  541.46  4990.8  541.46  4991.3  541.96  5164.7  543.93  5174.3  545.07
  5196.2  549.82  5305.3  549.79  5616.5   549.9  5679.4  550.66  5701.3  552.07
  5723.2   551.5  5792.4  551.37  5800.2  551.99    5833  551.84  5867.1  552.95
  5884.7  552.38  6051.8  553.01  6489.3   554.5  6494.8  555.09  6964.1  554.58
#Mann= 7 ,-1 , 0
  3268.2    .045       0  4982.1    .045       0  4991.3    .045       0
  5305.3    .063       0  5616.5    .035       0  5723.2    .094       0
  6051.8    .045       0
Bank Sta=4982.1,4991.3
XS Rating Curve= 0 ,0
Exp/Cntr=0.3,0.1

Type RM Length L Ch R = 1 ,21260   ,549,549,549
BEGIN DESCRIPTION:
WALNUT BRANCH 37.0
END DESCRIPTION:
XS GIS Cut Line= 3
      2291653.33      13767864.1      2291323.47     13765910.99
      2289465.86     13765407.52
#Sta/Elev= 30
  2657.8   556.3  3468.2  550.26  3975.3  550.16  3985.4  550.73  3994.7  556.05
    4026  566.97    4097  568.68  4115.6   565.8  4127.4  558.22  4147.7  551.12
    4176  549.33  4188.3  545.76  4208.6  543.84  4330.3  541.81  4720.1  541.17
  4916.7   541.4  4978.9   540.4  5005.4  537.66  5005.9  537.16  5014.6  537.66
  5030.5  542.62  5041.1   548.2  5051.4   550.1  5072.1  546.56  5166.9  548.77
  5392.5  551.12  5577.1  552.83  5590.9  552.65  6139.3  556.53  6563.2  556.39
#Mann= 9 ,-1 , 0
  2657.8    .045       0  4720.1     .12       0  5005.4     .05       0
  5014.6     .12       0  5030.5     .07       0  5166.9    .035       0
  5392.5    .063       0  5577.1    .035       0  5590.9    .045       0
Bank Sta=5005.4,5014.6
XS Rating Curve= 0 ,0
Exp/Cntr=0.3,0.1

Type RM Length L Ch R = 1 ,20711   ,592,592,592
BEGIN DESCRIPTION:
WALNUT BRANCH 36.0
END DESCRIPTION:
XS GIS Cut Line= 3
      2293372.07     13765390.16        2291125.       13765325.
      2289691.51     13765277.31
#Sta/Elev= 30
  2748.1  553.53  2756.8  553.65  2795.2  550.74  2865.2  552.46  2905.2  550.77
  2948.6   550.9  3415.5  549.67  3925.7  549.95  3935.7  549.52  3975.7  540.59
  4035.7   539.6  4807.2  539.91  4866.1  540.29  4906.1  536.57    4989  534.55
  4989.5  534.05  4998.3  534.55  5148.8  536.09  5166.2  541.15  5186.2  550.15
  5196.2  549.49    5201   547.9  5216.2  544.67  5236.2  546.69  5592.3   550.8
  5656.5  550.46  5686.5   552.2  5731.9  551.62  6126.7  555.58  6430.4  556.97
#Mann= 8 ,-1 , 0
  2748.1    .035       0  2948.6    .045       0  4807.2    .035       0
    4989     .05       0  4998.3    .035       0    5201    .045       0
  5592.3    .035       0  5731.9    .045       0
Bank Sta=4989,4998.3
XS Rating Curve= 0 ,0
Exp/Cntr=0.3,0.1

Type RM Length L Ch R = 1 ,20119   ,765,765,765
BEGIN DESCRIPTION:
WALNUT BRANCH 35.0
END DESCRIPTION:
XS GIS Cut Line= 3
      2292859.94     13765086.34      2290915.49     13764817.24
       2289752.3     13765173.14
#Sta/Elev= 30
  3184.5  549.48  3381.5   548.7  3855.8  549.97  3896.2  540.53  3966.8  539.48
    4795  540.42  4814.8  535.23  4824.9  534.42  4904.6  532.35  4991.8  532.14
  4992.3  531.64  5001.2  532.14  5058.3  532.17  5077.3  533.55  5097.5  538.16
  5107.6  542.26  5117.7  548.81    5125  550.05  5130.1  549.96  5145.2  544.51
  5150.3  544.51  5155.1  542.51  5179.4  544.06  5258.3  544.89  5529.2   547.6
  5608.1  548.33  5640.1  550.24  5666.4  549.61  6277.4  557.36  6363.9  557.01
#Mann= 7 ,-1 , 0
  3184.5    .045       0    4795     .12       0  4991.8     .05       0
  5001.2     .12       0  5258.3    .045       0  5529.2    .035       0
  5666.4    .045       0
Bank Sta=4991.8,5001.2
XS Rating Curve= 0 ,0
Exp/Cntr=0.3,0.1