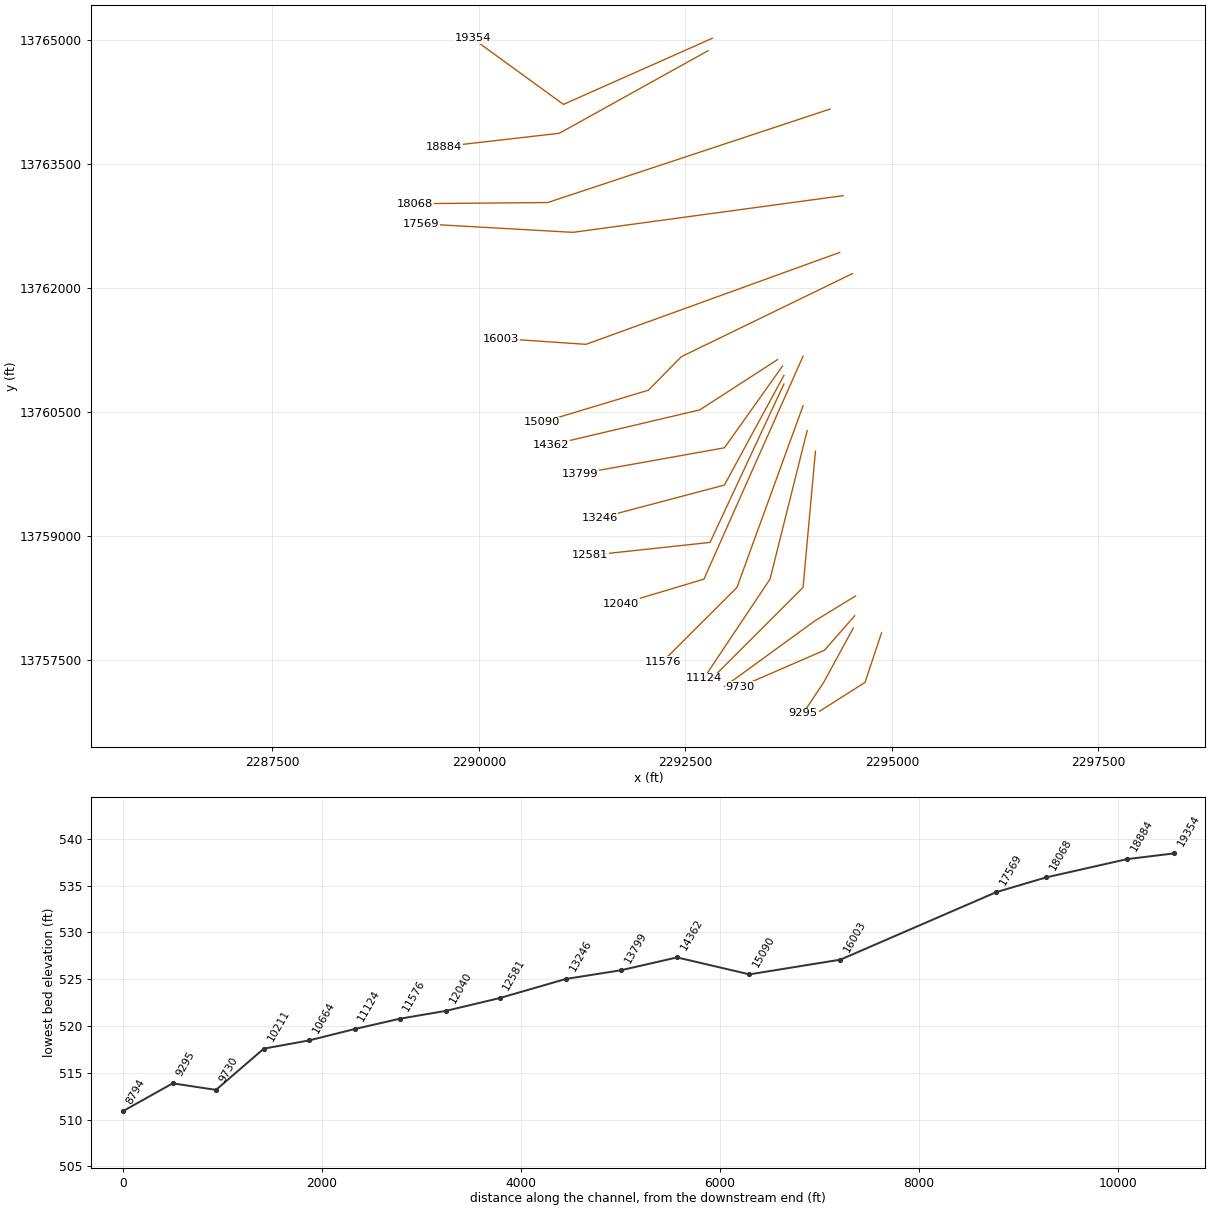
HEC-RAS study WALNUT BRANCH.prj: WALNUT BRANCH Base Level Engineering

--- WALNUT BRANCH.g01 (geometry) --- (continued)

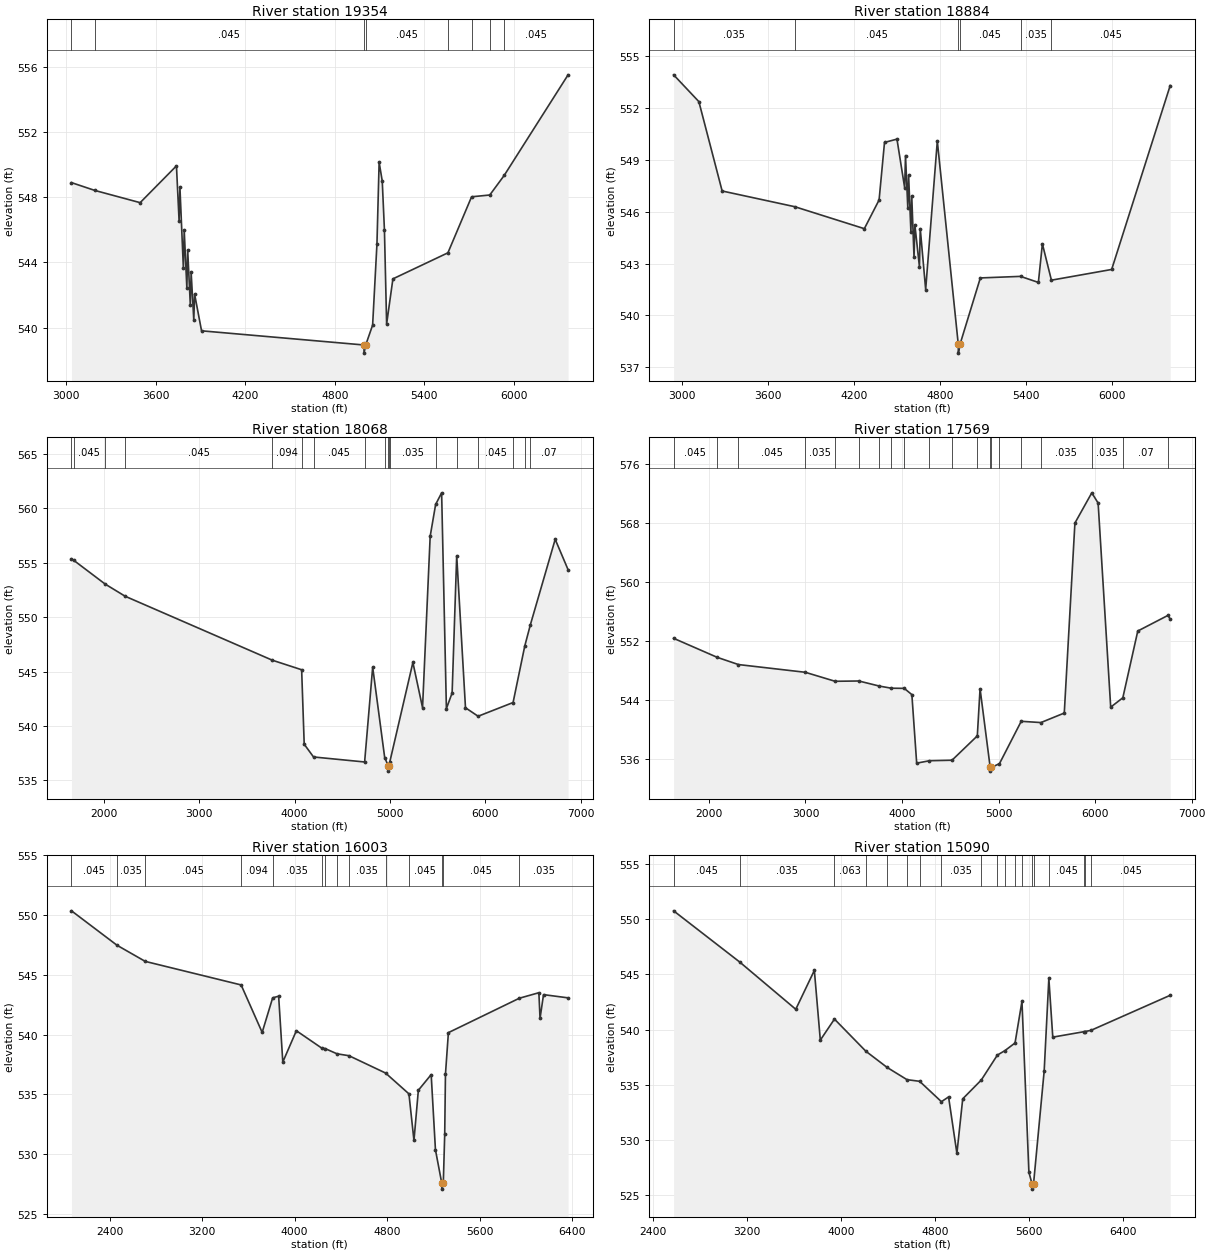
Type RM Length L Ch R = 1 ,19354   ,470,470,470
BEGIN DESCRIPTION:
WALNUT BRANCH 33.0
END DESCRIPTION:
XS GIS Cut Line= 3
      2292825.04     13765025.02        2291025.       13764225.
      2289924.97     13765025.02
#Sta/Elev= 30
  3034.3   548.9  3191.1  548.42  3494.6  547.67  3738.1  549.93  3755.9  546.54
  3761.4  548.61  3784.6  543.64  3790.1  545.98  3807.9  542.42  3813.4  544.77
  3831.1  541.39  3836.6  543.39  3854.4  540.46  3859.9  542.05  3906.4   539.8
  4995.5  538.93    4996  538.43  5007.2  538.93  5053.6  540.15  5082.6  545.13
  5097.2  550.15  5118.1     549  5132.8  545.99  5147.5  540.22  5189.6  542.99
  5558.5  544.59  5717.2  548.03  5839.2  548.14  5935.7  549.34  6364.3  555.52
#Mann= 8 ,-1 , 0
  3034.3    .035       0  3191.1    .045       0  4995.5    .045       0
  5007.2    .045       0  5558.5    .035       0  5717.2    .045       0
  5839.2    .035       0  5935.7    .045       0
Bank Sta=4995.5,5007.2
XS Rating Curve= 0 ,0
Exp/Cntr=0.3,0.1

Type RM Length L Ch R = 1 ,18884   ,816,816,816
BEGIN DESCRIPTION:
WALNUT BRANCH 32.0
END DESCRIPTION:
XS GIS Cut Line= 3
      2292775.03     13764875.02        2290975.       13763875.
      2289579.32     13763714.88
#Sta/Elev= 30
  2940.8  553.92    3117  552.37  3279.4   547.2  3786.4  546.29  4271.3  545.02
  4374.2  546.68    4412  550.01  4498.9   550.2  4552.7  547.38  4558.4  549.25
  4574.4  546.23  4580.1   548.1  4596.1  544.85  4601.9  546.92  4617.9  543.36
  4623.6  545.25  4655.6  542.82  4661.3  545.02  4699.1   541.5  4780.3  550.09
  4926.6  538.32  4927.1  537.82  4938.3  538.32  5080.5  542.17  5360.8  542.26
  5485.3  541.91  5513.3  544.14  5576.2  542.04  5996.5  542.66  6404.8   553.3
#Mann= 6 ,-1 , 0
  2940.8    .035       0  3786.4    .045       0  4926.6    .045       0
  4938.3    .045       0  5360.8    .035       0  5576.2    .045       0
Bank Sta=4926.6,4938.3
XS Rating Curve= 0 ,0
Exp/Cntr=0.3,0.1

Type RM Length L Ch R = 1 ,18068   ,499,499,499
BEGIN DESCRIPTION:
H21554
END DESCRIPTION:
XS GIS Cut Line= 3
      2294250.84     13764168.22      2290834.13     13763036.26
      2289229.93     13763022.37
#Sta/Elev= 30
  1663.1  555.35  1685.2  555.23  2015.8  553.04  2225.7  551.92  3766.6  546.05
  4074.8  545.17  4101.6  538.33  4199.2  537.16  4734.7   536.7  4819.1  545.41
  4944.9  537.11  4981.5  536.36    4982  535.86  4993.7  536.36  4999.4  536.74
  5240.5  545.84  5341.6  541.69  5421.6  557.43  5478.7  560.35  5541.6  561.42
  5591.6   541.6  5651.6  543.04  5699.6  555.65  5791.6  541.68  5923.9   540.9
  6290.3  542.16  6412.8  547.35  6472.1  549.32  6731.6  557.15  6866.7  554.36
#Mann= 18 ,-1 , 0
  1663.1    .063       0  1685.2    .045       0  2015.8    .035       0
  2225.7    .045       0  3766.6    .094       0  4074.8    .035       0
  4199.2    .045       0  4734.7    .035       0  4944.9    .063       0
  4981.5     .05       0  4993.7    .063       0  4999.4    .035       0
  5478.7    .063       0  5699.6    .035       0  5923.9    .045       0
  6290.3     .07       0  6412.8     .12       0  6472.1     .07       0
Bank Sta=4981.5,4993.7
XS Rating Curve= 0 ,0
Exp/Cntr=0.3,0.1

Type RM Length L Ch R = 1 ,17569   ,1566,1566,1566
BEGIN DESCRIPTION:
H21553
END DESCRIPTION:
XS GIS Cut Line= 3
      2294410.49     13763119.59      2291139.68     13762675.15
       2289299.7      13762779.3
#Sta/Elev= 30
  1633.9  552.31  2085.5  549.73  2305.2  548.75  2998.1   547.7  3306.6  546.48
  3552.3  546.52    3765  545.83  3888.9  545.54  4022.8  545.52  4101.9  544.67
  4151.7  535.37  4284.3   535.7  4517.8  535.77  4779.8  539.07  4808.3  545.47
  4913.2  534.79  4913.7  534.29  4925.4  534.79  5009.5  535.31  5234.6  541.05
  5438.6  540.88  5680.6  542.17  5790.8  567.95  5965.6  572.05  6031.2  570.66
  6161.4  542.97  6287.1  544.24  6441.9   553.3    6756  555.43  6777.7  554.89
#Mann= 20 ,-1 , 0
  1633.9    .045       0  2085.5    .035       0  2305.2    .045       0
  2998.1    .035       0  3306.6    .063       0  3552.3    .045       0
    3765    .094       0  3888.9     .12       0  4022.8    .063       0
  4284.3    .035       0  4517.8    .035       0  4779.8    .094       0
  4913.2     .05       0  4925.4    .094       0  5009.5    .063       0
  5234.6    .045       0  5438.6    .035       0  5965.6    .035       0
  6287.1     .07       0    6756     .07       0
Bank Sta=4913.2,4925.4
XS Rating Curve= 0 ,0
Exp/Cntr=0.3,0.1

Type RM Length L Ch R = 1 ,16003   ,913,913,913
BEGIN DESCRIPTION:
XS7945
END DESCRIPTION:
XS GIS Cut Line= 3
      2294368.84     13762432.09      2291297.43     13761318.97
      2290273.08     13761388.42
#Sta/Elev= 30
  2070.6  550.36  2464.2  547.48  2708.3  546.13  3537.3  544.16  3719.2  540.19
  3809.9  543.08  3861.6  543.22  3897.6  537.71  4014.8  540.33  4233.8  538.88
  4262.7  538.84  4366.3   538.4    4470  538.24  4786.3  536.79  4988.1  535.05
  5031.6  531.15  5069.6  535.35  5180.5  536.66  5217.4  530.37    5272  527.58
  5272.5  527.08  5285.3  527.58  5297.5  531.67    5304   536.7  5329.3  540.17
    5943  543.05  6111.7  543.51  6121.7  541.36  6151.8  543.35  6364.2  543.08
#Mann= 14 ,-1 , 0
  2070.6    .045       0  2464.2    .035       0  2708.3    .045       0
  3537.3    .094       0  3809.9    .035       0  4233.8    .063       0
  4262.7    .035       0  4366.3    .063       0    4470    .035       0
  4786.3     .07       0  4988.1    .045       0    5272    .045       0
  5285.3    .045       0    5943    .035       0
Bank Sta=5272,5285.3
XS Rating Curve= 0 ,0
Exp/Cntr=0.3,0.1

Type RM Length L Ch R = 1 ,15090   ,728,728,728
BEGIN DESCRIPTION:
WALNUT BRANCH 27.0
END DESCRIPTION:
XS GIS Cut Line= 4
      2294521.63     13762175.15      2292451.45     13761168.93
      2292052.64     13760763.42      2290759.65     13760372.92
#Sta/Elev= 30
  2579.1  550.78  3141.1  546.13  3617.6  541.84  3775.5  545.37  3826.2  539.04
  3946.3  540.95  4213.5  538.03  4394.1  536.56  4562.9  535.45  4670.5   535.3
  4855.6  533.45  4916.4  533.88  4987.2  528.76  5036.7  533.71  5194.8  535.42
  5331.1  537.68  5395.7  538.09  5481.4  538.78  5540.3  542.56  5599.2  527.04
  5625.5  526.01    5626  525.51  5638.9  526.01  5729.2  536.25  5768.8  544.64
  5802.2  539.31    6070  539.81  6074.7  539.82  6125.4  539.92  6800.3  543.11
#Mann= 19 ,-1 , 0
  2579.1    .045       0  3141.1    .035       0  3946.3    .063       0
  4213.5    .035       0  4394.1    .063       0  4562.9    .035       0
  4670.5    .063       0  4855.6    .035       0  5194.8    .063       0
  5331.1    .094       0  5395.7    .035       0  5481.4    .045       0
  5540.3    .035       0  5625.5     .05       0  5638.9    .035       0
  5768.8    .045       0    6070    .094       0  6074.7    .035       0
  6125.4    .045       0
Bank Sta=5625.5,5638.9
XS Rating Curve= 0 ,0
Exp/Cntr=0.3,0.1

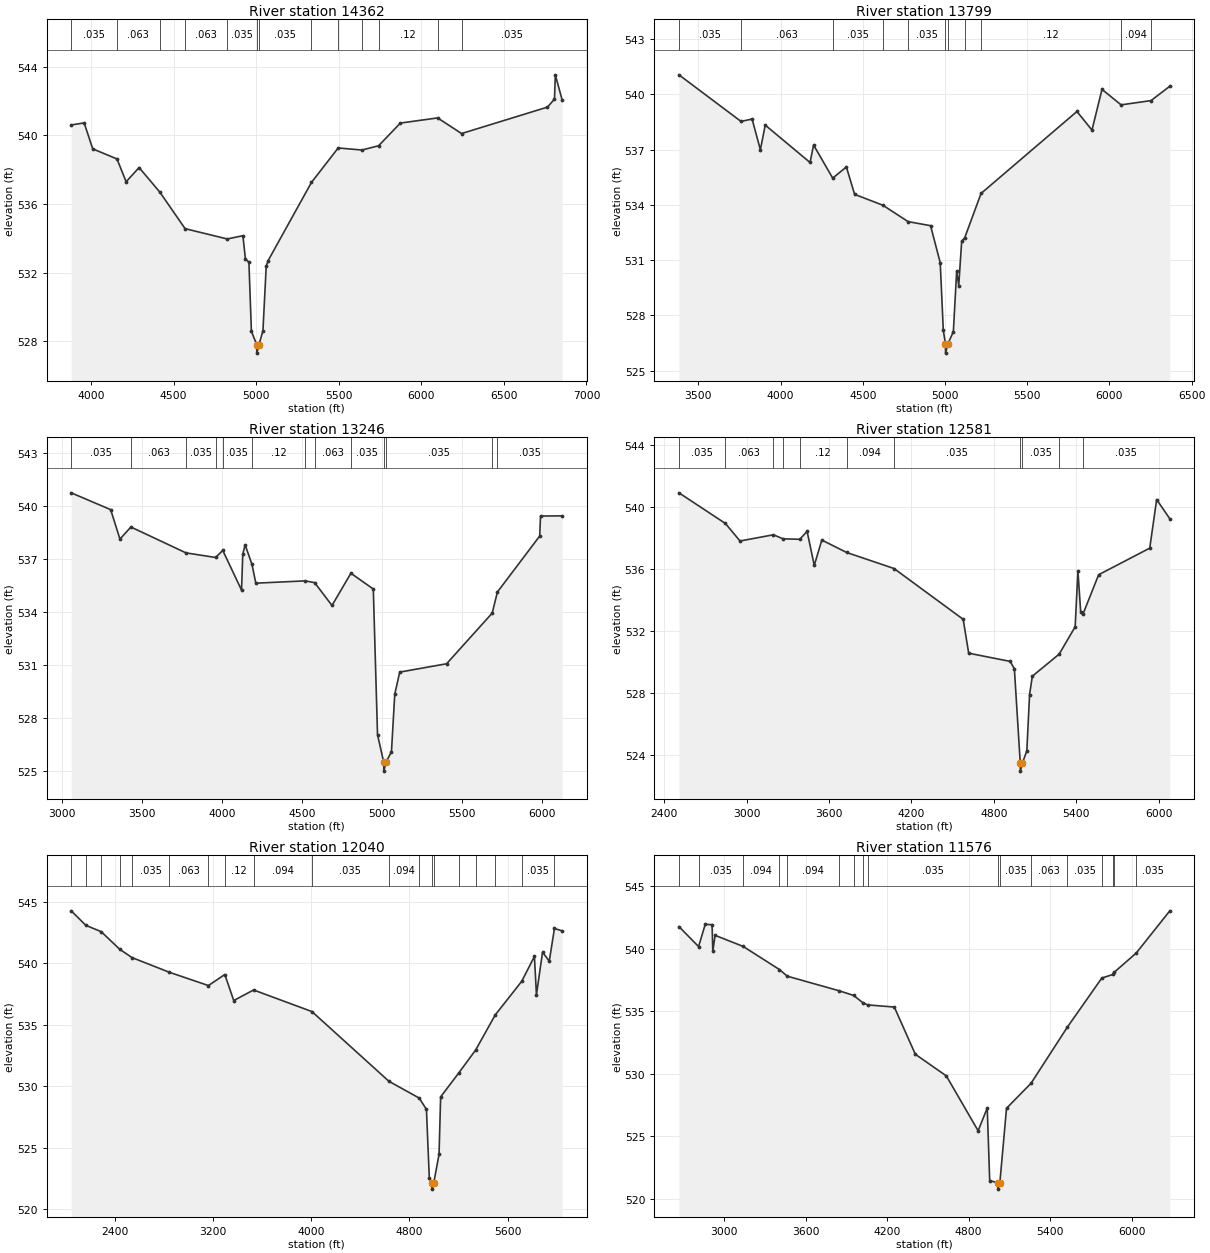
Type RM Length L Ch R = 1 ,14362   ,563,563,563
BEGIN DESCRIPTION:
WALNUT BRANCH 26.0
END DESCRIPTION:
XS GIS Cut Line= 3
      2293615.15     13761133.22        2292675.       13760525.
       2290872.1     13760100.23
#Sta/Elev= 30
  3880.3  540.61  3958.9  540.73  4010.3  539.22  4157.6  538.63  4212.8   537.3
  4291.3  538.13  4416.8   536.7  4569.8  534.57  4824.9  533.97  4919.9  534.16
  4935.1   532.8  4956.2  532.62  4971.3  528.59  5003.3  527.82  5003.8  527.32
  5017.4  527.82  5041.1  528.62    5061  532.37    5072   532.7  5334.7  537.26
  5496.7  539.27    5641  539.15  5741.5   539.4  5873.3  540.72  6098.7  541.02
  6243.8  540.11    6764  541.65  6806.4  542.12  6811.5  543.53  6852.3  542.08
#Mann= 13 ,-1 , 0
  3880.3    .035       0  4157.6    .063       0  4416.8    .035       0
  4569.8    .063       0  4824.9    .035       0  5003.3     .05       0
  5017.4    .035       0  5334.7    .063       0  5496.7    .094       0
    5641    .063       0  5741.5     .12       0  6098.7    .094       0
  6243.8    .035       0
Bank Sta=5003.3,5017.4
XS Rating Curve= 0 ,0
Exp/Cntr=0.3,0.1

Type RM Length L Ch R = 1 ,13799   ,553,553,553
BEGIN DESCRIPTION:
XS7944
END DESCRIPTION:
XS GIS Cut Line= 3
      2293675.92      13761055.1      2292972.78      13760065.5
      2291228.99     13759753.18
#Sta/Elev= 30
  3381.6  541.06  3759.2  538.53  3826.5  538.66  3876.9  536.99  3906.4  538.33
  4179.1   536.3  4200.4  537.25  4316.9  535.45  4399.9  536.06    4450  534.57
    4622  533.98  4775.2  533.09  4911.9  532.87  4970.7  530.86  4989.5  527.18
  5002.7  526.45  5003.2  525.95  5016.9  526.45  5050.5  527.11  5070.8   530.4
  5083.3  529.62  5101.3  532.03  5119.5  532.21  5219.1  534.62  5802.2  539.07
  5893.7  538.06  5954.6  540.27  6070.8  539.43  6252.6  539.66  6367.1  540.44
#Mann= 11 ,-1 , 0
  3381.6    .035       0  3759.2    .063       0  4316.9    .035       0
    4622    .063       0  4775.2    .035       0  5002.7     .05       0
  5016.9    .035       0  5119.5    .063       0  5219.1     .12       0
  6070.8    .094       0  6252.6    .035       0
Bank Sta=5002.7,5016.9
XS Rating Curve= 0 ,0
Exp/Cntr=0.3,0.1

Type RM Length L Ch R = 1 ,13246   ,665,665,665
BEGIN DESCRIPTION:
XS7943
END DESCRIPTION:
XS GIS Cut Line= 3
      2293693.26     13760942.22      2292972.78     13759614.11
      2291462.32      13759214.8
#Sta/Elev= 30
  3055.1  540.73  3302.2  539.78  3360.2  538.12  3428.9   538.8  3773.8  537.34
  3959.3  537.08    4004  537.48  4121.4  535.24  4129.3  537.27  4144.1  537.79
  4186.9  536.69    4211  535.63    4520  535.76  4579.2  535.66  4687.9  534.37
  4806.1  536.19  4946.5   535.3  4972.9  527.08  5011.7  525.52  5012.2  525.02
    5026  525.52  5060.2  526.12  5080.9  529.37    5112  530.61  5405.3  531.08
  5690.9  533.94  5723.5  535.13  5988.3  538.29  5993.5  539.42  6128.4  539.43
#Mann= 13 ,-1 , 0
  3055.1    .035       0  3428.9    .063       0  3773.8    .035       0
  3959.3    .094       0    4004    .035       0  4186.9     .12       0
    4520    .094       0  4579.2    .063       0  4806.1    .035       0
  5011.7     .05       0    5026    .035       0  5690.9    .094       0
  5723.5    .035       0
Bank Sta=5011.7,5026
XS Rating Curve= 0 ,0
Exp/Cntr=0.3,0.1

Type RM Length L Ch R = 1 ,12581   ,541,541,541
BEGIN DESCRIPTION:
XS7942
END DESCRIPTION:
XS GIS Cut Line= 3
      2293693.25     13760838.05      2292799.17     13758919.67
      2291349.76     13758763.45
#Sta/Elev= 30
  2506.8  540.89  2844.9  538.92  2951.5  537.79  3194.6  538.19  3265.1  537.93
  3386.4   537.9  3440.1  538.41  3492.1  536.22  3547.2  537.85  3728.2  537.05
  4072.7  536.02  4576.4  532.75  4616.6  530.57  4919.2  530.04  4949.3  529.56
  4992.3  523.48  4992.8  522.98    5007  523.48  5039.9  524.29    5060  527.91
  5080.1  529.09  5275.5  530.51  5391.9  532.27    5412  535.87  5432.1  533.23
  5447.7  533.06  5562.9  535.62    5935  537.33  5985.3  540.46  6081.1  539.22
#Mann= 11 ,-1 , 0
  2506.8    .035       0  2844.9    .063       0  3194.6    .035       0
  3265.1    .094       0  3386.4     .12       0  3728.2    .094       0
  4072.7    .035       0  4992.3     .05       0    5007    .035       0
  5275.5    .063       0  5447.7    .035       0
Bank Sta=4992.3,5007
XS Rating Curve= 0 ,0
Exp/Cntr=0.3,0.1

Type RM Length L Ch R = 1 ,12040   ,464,464,464
BEGIN DESCRIPTION:
WALNUT BRANCH 25.0
END DESCRIPTION:
XS GIS Cut Line= 3
      2293925.01     13761175.01        2292725.       13758475.
        2291725.       13758175.
#Sta/Elev= 30
  2045.3  544.29  2164.2  543.11  2289.8  542.59  2441.3  541.15  2540.6  540.48
  2845.7  539.28  3163.1   538.2  3296.5   539.1  3369.4  536.98  3530.9  537.84
  4006.4  536.08  4633.3   530.4  4880.2  529.03  4939.1  528.11  4962.4  522.52
  4983.7  522.11  4984.2  521.61  4998.4  522.11  5041.7  524.44  5054.8  529.13
  5204.1   531.1  5340.1  532.95  5499.1   535.8  5714.8  538.54  5818.7  540.57
  5835.2  537.45  5884.8  540.92  5939.6  540.19  5981.9  542.85    6044  542.66
#Mann= 19 ,-1 , 0
  2045.3     .12       0  2164.2    .094       0  2289.8    .035       0
  2441.3    .063       0  2540.6    .035       0  2845.7    .063       0
  3163.1    .094       0  3296.5     .12       0  3530.9    .094       0
  4006.4    .035       0  4633.3    .094       0  4880.2    .035       0
  4983.7     .05       0  4998.4    .035       0  5204.1    .063       0
  5340.1    .035       0  5499.1    .063       0  5714.8    .035       0
  5981.9    .094       0
Bank Sta=4983.7,4998.4
XS Rating Curve= 0 ,0
Exp/Cntr=0.3,0.1

Type RM Length L Ch R = 1 ,11576   ,452,452,452
BEGIN DESCRIPTION:
WALNUT BRANCH 24.0
END DESCRIPTION:
XS GIS Cut Line= 3
      2293924.99     13760574.96        2293125.       13758375.
        2292225.       13757475.
#Sta/Elev= 30
  2667.9  541.78  2812.5  540.18  2861.4  541.96  2911.9  541.93  2917.3  539.79
  2933.9  541.08  3140.9  540.19    3408  538.34  3465.4  537.81  3847.9  536.64
  3953.8  536.27  4023.8  535.67  4059.6  535.51  4253.3  535.34  4408.3  531.56
  4636.4  529.83  4870.5  525.44  4937.6  527.26  4955.6  521.46  5015.5  521.27
    5016  520.77  5030.3  521.27  5079.5  527.24  5260.7  529.25  5527.8  533.74
    5781  537.66  5863.3  537.95  5870.8  538.11  6034.2  539.66  6281.6  543.04
#Mann= 17 ,-1 , 0
  2667.9    .063       0  2812.5    .035       0  3140.9    .094       0
    3408    .063       0  3465.4    .094       0  3847.9    .063       0
  3953.8    .094       0  4023.8    .063       0  4059.6    .035       0
  5015.5     .05       0  5030.3    .035       0  5260.7    .063       0
  5527.8    .035       0    5781    .063       0  5863.3    .035       0
  5870.8    .063       0  6034.2    .035       0
Bank Sta=5015.5,5030.3
XS Rating Curve= 0 ,0
Exp/Cntr=0.3,0.1

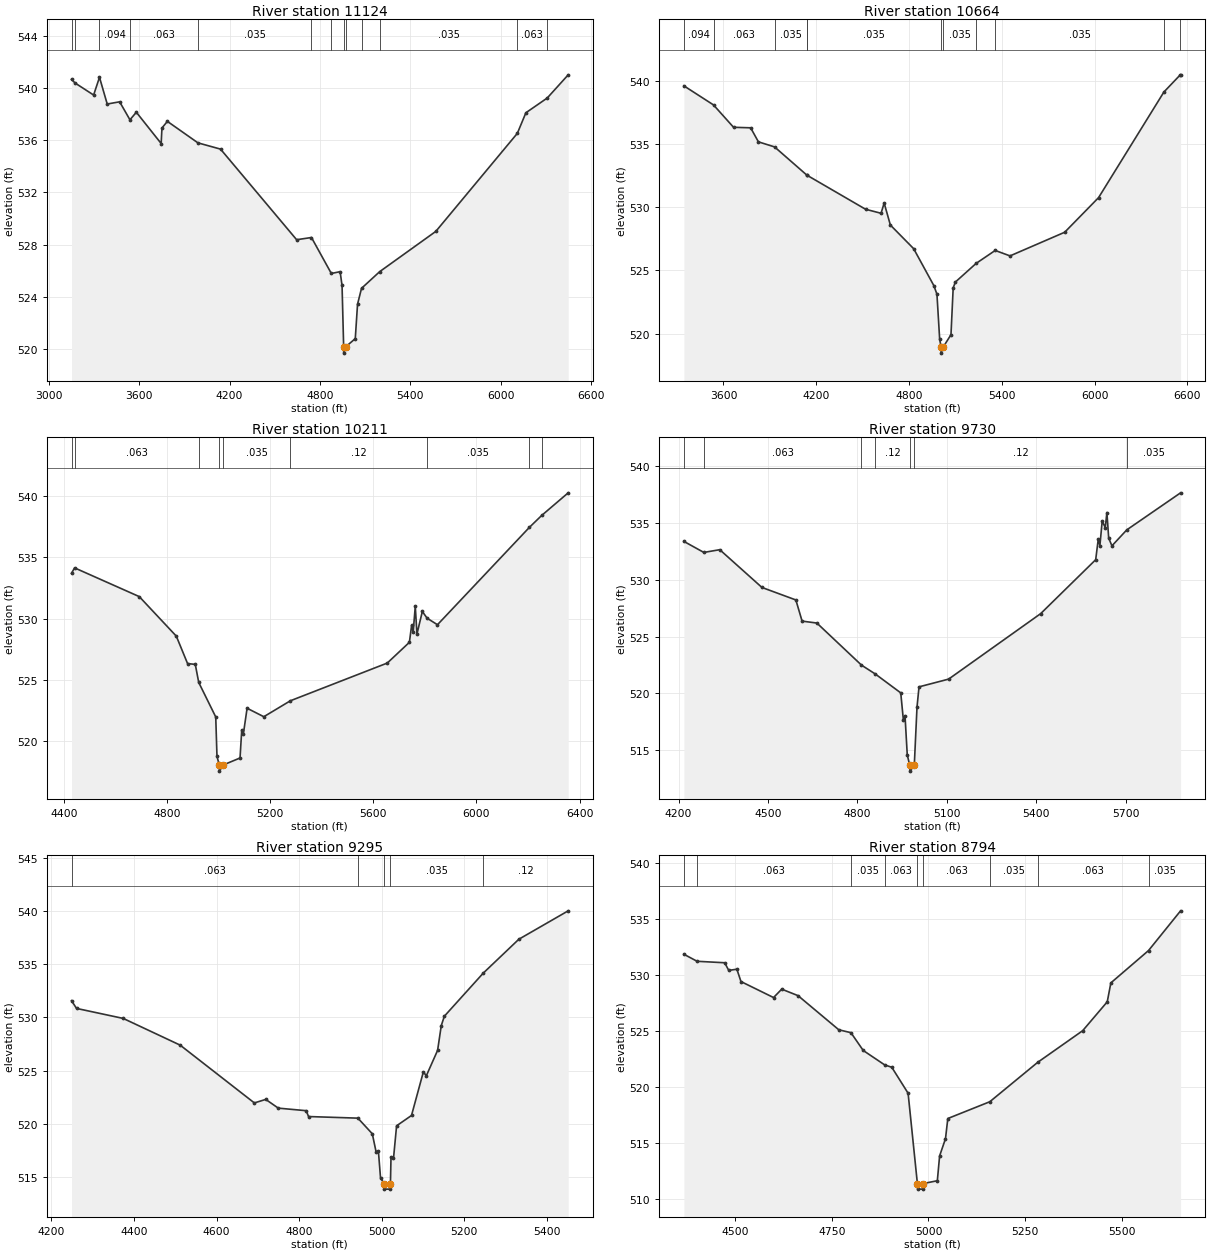
Type RM Length L Ch R = 1 ,11124   ,460,460,460
BEGIN DESCRIPTION:
WALNUT BRANCH 23.0
END DESCRIPTION:
XS GIS Cut Line= 3
      2293975.01     13760275.03        2293525.       13758475.
      2292725.03     13757275.04
#Sta/Elev= 30
  3150.3  540.67  3174.3  540.39  3297.2  539.47  3336.1  540.83  3387.4  538.78
  3469.9  538.95  3538.3  537.57  3580.7  538.15  3745.6  535.75  3750.8  536.94
  3786.8  537.45  3989.8   535.8  4139.9  535.32    4645  528.37  4743.5  528.54
  4875.4  525.78  4933.6  525.92  4946.5  524.86  4957.1  520.17  4957.6  519.67
  4971.9  520.17  5034.3  520.78  5049.3  523.42  5075.7  524.64  5196.3  525.92
  5569.1  529.01  6110.2  536.53    6167  538.11  6308.6  539.24  6447.9  541.02
#Mann= 13 ,-1 , 0
  3150.3    .063       0  3174.3    .035       0  3336.1    .094       0
  3538.3    .063       0  3989.8    .035       0  4743.5    .063       0
  4875.4    .035       0  4957.1     .05       0  4971.9    .035       0
  5075.7     .12       0  5196.3    .035       0  6110.2    .063       0
  6308.6    .035       0
Bank Sta=4957.1,4971.9
XS Rating Curve= 0 ,0
Exp/Cntr=0.3,0.1

Type RM Length L Ch R = 1 ,10664   ,453,453,453
BEGIN DESCRIPTION:
WALNUT BRANCH 22.0
END DESCRIPTION:
XS GIS Cut Line= 3
        2294075.       13760025.        2293925.       13758375.
      2292825.03     13757275.03
#Sta/Elev= 30
  3343.8  539.59  3535.4  538.08  3665.1  536.31  3775.6  536.27  3825.8  535.16
  3930.3  534.76    4138  532.54  4138.7  532.53  4518.6  529.83    4619  529.51
  4639.1  530.32  4679.3  528.58  4829.9  526.71  4960.4  523.79  4980.5  523.11
  4998.1  519.55  5007.2  518.95  5007.7  518.45  5022.2  518.95  5071.3  519.91
  5085.5  523.61  5099.6  524.07  5234.2  525.55  5357.2  526.57  5453.2  526.14
  5806.7  528.01  6025.9  530.75  6448.3   539.1  6551.2  540.42  6556.2  540.46
#Mann= 11 ,-1 , 0
  3343.8    .094       0  3535.4    .063       0  3930.3    .035       0
    4138    .063       0  4138.7    .035       0  5007.2     .05       0
  5022.2    .035       0  5234.2     .12       0  5357.2    .035       0
  6448.3    .063       0  6551.2    .035       0
Bank Sta=5007.2,5022.2
XS Rating Curve= 0 ,0
Exp/Cntr=0.3,0.1

Type RM Length L Ch R = 1 ,10211   ,481,481,481
BEGIN DESCRIPTION:
WALNUT BRANCH 21.0
END DESCRIPTION:
XS GIS Cut Line= 3
      2294559.61     13758270.38        2294075.       13757975.
      2292974.98     13757174.99
#Sta/Elev= 30
  4428.2  533.69  4440.2  534.13  4691.2  531.79    4835  528.57  4878.6  526.34
  4908.6  526.27    4922   524.8    4988  521.99  4992.8  518.78  5001.7  518.08
  5002.2  517.58  5016.8  518.08  5082.3  518.65  5088.9  520.93    5095  520.58
  5109.7   522.7  5174.6  522.01  5277.8  523.31  5653.8  526.38  5739.6  528.07
  5748.1  529.44  5754.2  528.89  5762.4     531  5768.9  528.74  5789.8  530.58
  5808.4  530.03  5848.5   529.5  6204.9  537.42  6253.1   538.4  6355.9  540.24
#Mann= 9 ,-1 , 0
  4428.2    .035       0  4440.2    .063       0    4922    .035       0
  5001.7     .05       0  5016.8    .035       0  5277.8     .12       0
  5808.4    .035       0  6204.9     .12       0  6253.1    .035       0
Bank Sta=5001.7,5016.8
XS Rating Curve= 0 ,0
Exp/Cntr=0.3,0.1

Type RM Length L Ch R = 1 ,9730    ,435,435,435
BEGIN DESCRIPTION:
XS7941
END DESCRIPTION:
XS GIS Cut Line= 3
      2294549.17     13758030.79      2294184.59     13757614.11
      2293163.71     13757171.39
#Sta/Elev= 30
  4217.8  533.37  4284.7   532.4  4338.2  532.64  4479.7  529.32  4593.5  528.22
  4614.4  526.36    4664  526.19  4813.7  522.49    4860  521.71  4945.4  520.05
  4954.3  517.64  4959.7  518.05  4967.2  514.61  4975.6  513.67  4976.1  513.17
  4990.8  513.67  4999.9  518.79  5006.7  520.58    5106  521.26  5414.9  527.02
  5599.4  531.76    5608  533.56  5613.5     533  5621.2  535.15  5631.5  534.59
    5637  535.91    5643  533.66  5653.9  532.98  5703.6  534.38  5884.2  537.64
#Mann= 7 ,-1 , 0
  4217.8    .035       0  4284.7    .063       0  4813.7    .035       0
    4860     .12       0  4975.6     .05       0  4990.8     .12       0
  5703.6    .035       0
Bank Sta=4975.6,4990.8
XS Rating Curve= 0 ,0
Exp/Cntr=0.3,0.1

Type RM Length L Ch R = 1 ,9295    ,501,501,501
BEGIN DESCRIPTION:
WALNUT BRANCH 20.0
END DESCRIPTION:
XS GIS Cut Line= 3
      2294533.56     13757884.97        2294175.       13757225.
      2293924.67     13756849.23
#Sta/Elev= 30
  4248.8  531.58    4261  530.85    4374  529.91  4511.9   527.4  4691.5  521.97
  4719.1   522.3  4749.5  521.48    4817  521.24  4822.7  520.69  4942.2  520.54
  4977.1  519.07  4986.1   517.4  4991.8  517.47    4997  514.93  5005.8  514.37
  5006.3  513.87  5020.5  513.87    5021  514.37  5022.4   516.9  5028.4  516.75
  5035.9  519.82    5072  520.79  5100.6  524.87    5108  524.53  5135.2  526.91
  5144.1  529.24  5151.6  530.12  5245.8  534.17  5331.9  537.35  5451.4  540.02
#Mann= 5 ,-1 , 0
  4248.8    .063       0  4942.2    .035       0  5005.8     .05       0
    5021    .035       0  5245.8     .12       0
Bank Sta=5005.8,5021
XS Rating Curve= 0 ,0
Exp/Cntr=0.3,0.1

Type RM Length L Ch R = 1 ,8794    ,452,452,452
BEGIN DESCRIPTION:
WALNUT BRANCH 19.0
END DESCRIPTION:
XS GIS Cut Line= 3
      2294875.01     13757825.04        2294675.       13757225.
      2294125.02     13756875.01
#Sta/Elev= 30
  4367.6  531.88  4401.8  531.25  4473.1  531.12  4483.6  530.44  4504.7  530.54
  4515.2  529.44  4599.5  528.01  4620.6  528.76  4662.8  528.18  4768.2  525.13
  4799.6  524.87  4831.4  523.28  4886.9  521.99  4905.2  521.78  4947.4  519.46
  4971.4  511.39  4971.9  510.89  4986.1  510.89  4986.6  511.39    5023  511.64
  5028.9  513.86  5044.1   515.4  5050.1   517.2  5158.7   518.7  5282.5  522.22
  5398.9  525.05  5462.4  527.63  5471.7  529.32  5569.1  532.21    5652  535.76
#Mann= 9 ,-1 , 0
  4367.6    .035       0  4401.8    .063       0  4799.6    .035       0
  4886.9    .063       0  4971.4     .05       0  4986.6    .063       0
  5158.7    .035       0  5282.5    .063       0  5569.1    .035       0
Bank Sta=4971.4,4986.6
XS Rating Curve= 0 ,0
Exp/Cntr=0.3,0.1