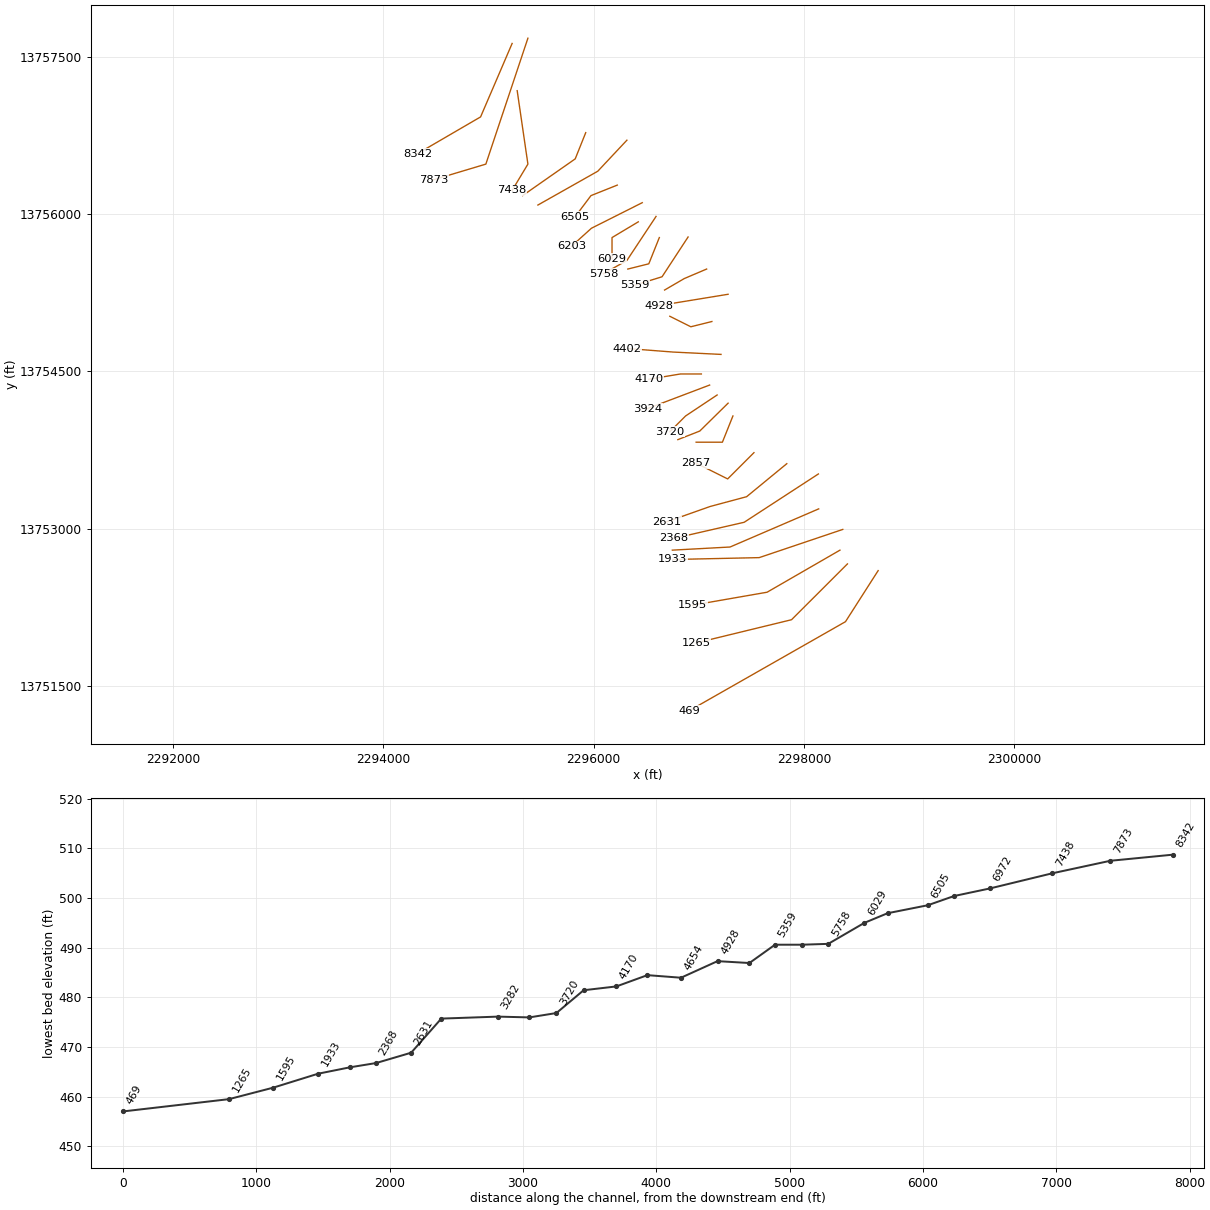
HEC-RAS study WALNUT BRANCH.prj: WALNUT BRANCH Base Level Engineering

--- WALNUT BRANCH.g01 (geometry) --- (continued)

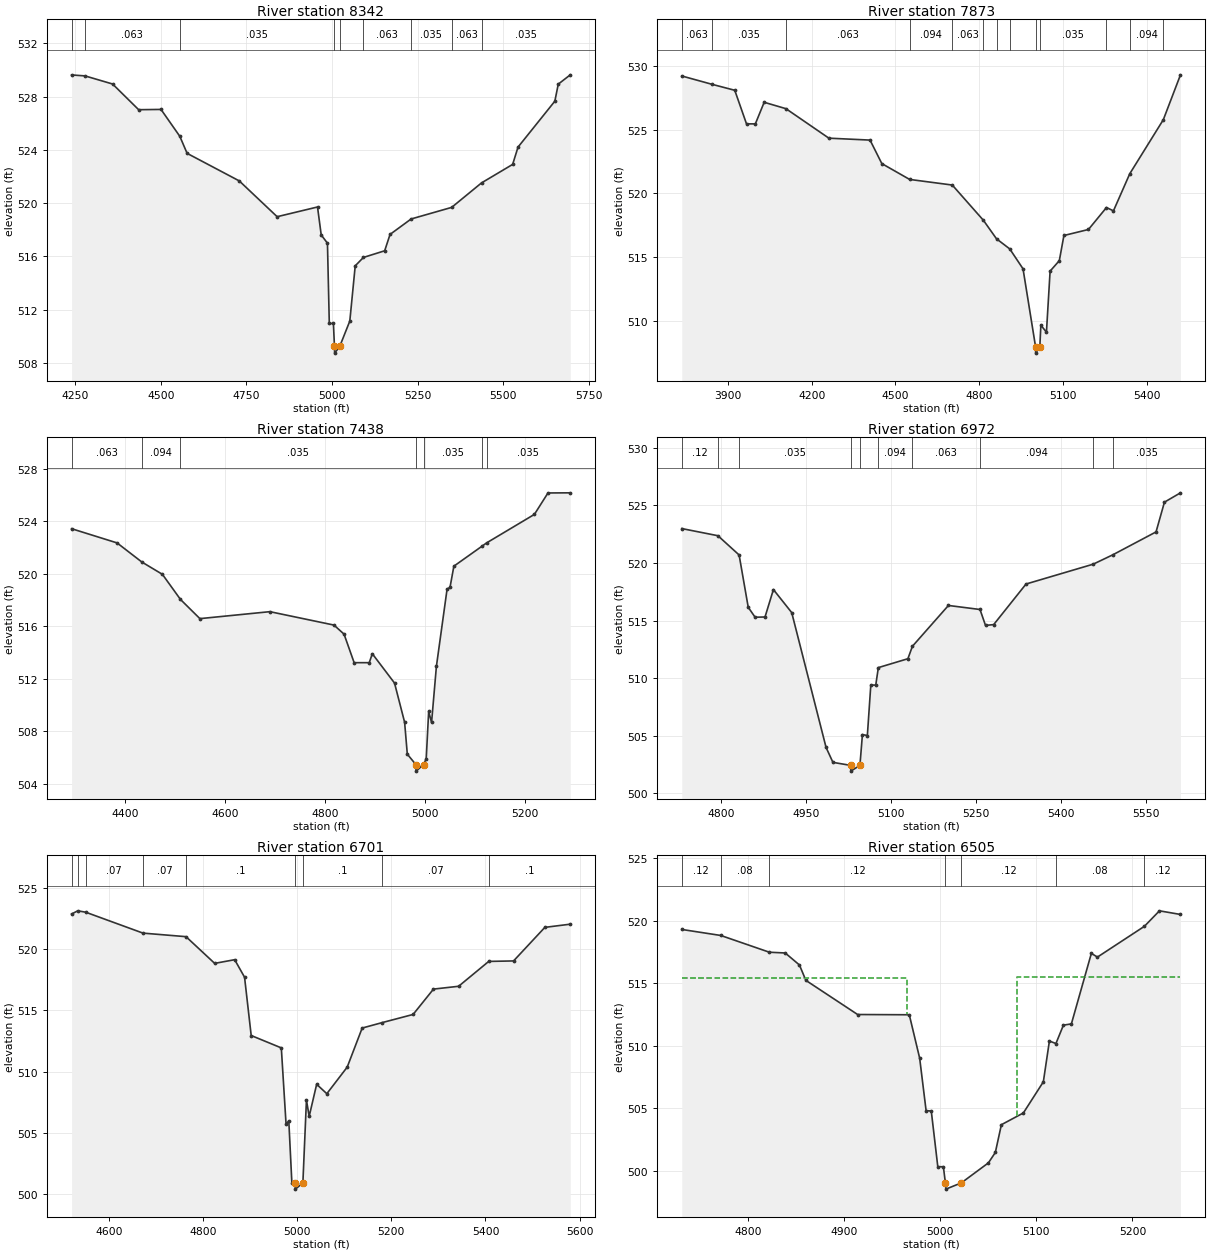
Type RM Length L Ch R = 1 ,8342    ,469,469,469
BEGIN DESCRIPTION:
WALNUT BRANCH 18.0
END DESCRIPTION:
XS GIS Cut Line= 3
        2295225.       13757625.        2294925.       13756925.
        2294325.       13756575.
#Sta/Elev= 30
  4239.4  529.63  4278.5  529.56  4359.1  528.95  4435.2  527.02  4500.5  527.04
  4555.4  525.02  4576.7  523.74    4729  521.67  4839.6  518.98  4957.5  519.71
  4968.3  517.61  4986.5  516.99  4991.9  510.96  5003.9  510.96    5007  509.23
  5007.5  508.73  5022.3  509.23  5051.8  511.14  5067.6  515.29  5091.6  515.92
  5153.6  516.42  5169.3  517.65  5230.9  518.81  5349.2  519.68  5436.4  521.52
  5527.3  522.91    5543  524.21  5650.5  527.66  5660.5  528.94  5695.6  529.64
#Mann= 9 ,-1 , 0
  4239.4    .035       0  4278.5    .063       0  4555.4    .035       0
    5007     .05       0  5022.3    .035       0  5091.6    .063       0
  5230.9    .035       0  5349.2    .063       0  5436.4    .035       0
Bank Sta=5007,5022.3
XS Rating Curve= 0 ,0
Exp/Cntr=0.3,0.1

Type RM Length L Ch R = 1 ,7873    ,435,435,435
BEGIN DESCRIPTION:
WALNUT BRANCH 17.0
END DESCRIPTION:
XS GIS Cut Line= 3
      2295375.01     13757675.03        2294975.       13756475.
      2294474.96     13756324.99
#Sta/Elev= 30
  3734.5   529.2  3842.3  528.55  3924.3  528.08  3966.4  525.45  3998.1  525.45
  4029.7  527.14  4107.7  526.64  4261.6  524.33  4409.1  524.18  4451.3  522.34
  4550.9   521.1  4703.8  520.66  4815.3   517.9  4862.3  516.45  4909.7  515.66
  4957.3   514.1  5002.2     508  5002.7   507.5  5017.5     508  5021.2  509.69
  5041.2  509.14  5054.3  513.92  5087.3  514.74  5103.8  516.71  5191.7  517.18
  5256.3   518.9  5281.3  518.64  5339.9  521.55  5460.1  525.78  5521.5  529.29
#Mann= 13 ,-1 , 0
  3734.5    .063       0  3842.3    .035       0  4107.7    .063       0
  4550.9    .094       0  4703.8    .063       0  4815.3    .094       0
  4862.3    .063       0  4909.7    .035       0  5002.2     .05       0
  5017.5    .035       0  5256.3    .063       0  5339.9    .094       0
  5460.1    .063       0
Bank Sta=5002.2,5017.5
XS Rating Curve= 0 ,0
Exp/Cntr=0.3,0.1

Type RM Length L Ch R = 1 ,7438    ,466,466,466
BEGIN DESCRIPTION:
WALNUT BRANCH 16.0
END DESCRIPTION:
XS GIS Cut Line= 3
      2295273.09     13757175.12        2295375.       13756475.
      2295225.02     13756225.04
#Sta/Elev= 30
  4292.5  523.42  4383.6  522.34  4433.1  520.89  4474.4  519.95  4510.6  518.04
  4549.5  516.58  4689.7  517.11  4818.1  516.09  4838.3   515.4  4858.5  513.23
  4888.8  513.23  4894.9  513.91  4939.4  511.68  4959.6   508.7    4965  506.27
  4982.1  505.48  4982.6  504.98  4997.6  505.48  5002.9  505.92  5007.8  509.52
  5013.6  508.68  5023.3  512.95  5044.7  518.83  5050.5  518.95  5058.3  520.57
  5113.9  522.07  5123.8  522.34  5219.6  524.51  5246.8  526.14  5291.5  526.15
#Mann= 7 ,-1 , 0
  4292.5    .063       0  4433.1    .094       0  4510.6    .035       0
  4982.1     .05       0  4997.6    .035       0  5113.9    .063       0
  5123.8    .035       0
Bank Sta=4982.1,4997.6
XS Rating Curve= 0 ,0
Exp/Cntr=0.3,0.1

Type RM Length L Ch R = 1 ,6972    ,271,271,271
BEGIN DESCRIPTION:
WALNUT BRANCH 15.0
END DESCRIPTION:
XS GIS Cut Line= 3
      2295925.02     13756775.04        2295825.       13756525.
      2295325.02     13756175.02
#Sta/Elev= 30
  4730.8  522.98  4794.5  522.36  4831.9  520.69    4848  516.15  4860.1  515.29
  4877.6  515.31  4892.4  517.69  4924.7  515.69  4985.3  503.99  4997.4   502.7
  5028.5  502.44    5029  501.94    5045  502.44  5049.4  505.11  5058.1  505.03
  5064.2  509.41  5072.9   509.4  5077.5  510.92  5129.6  511.69  5137.6  512.77
  5201.1  516.31  5256.8  515.96  5266.5  514.58  5280.9  514.65    5338  518.17
  5456.4  519.89  5490.9   520.7  5567.3  522.69  5582.1  525.27  5610.4  526.08
#Mann= 10 ,-1 , 0
  4730.8     .12       0  4794.5    .094       0  4831.9    .035       0
  5028.5     .05       0    5045    .035       0  5077.5    .094       0
  5137.6    .063       0  5256.8    .094       0  5456.4    .063       0
  5490.9    .035       0
Bank Sta=5028.5,5045
XS Rating Curve= 0 ,0
Exp/Cntr=0.3,0.1

Type RM Length L Ch R = 1 ,6701    ,196,196,196
BEGIN DESCRIPTION:
H21552
END DESCRIPTION:
XS GIS Cut Line= 3
      2296316.61      13756703.1      2296039.45     13756407.21
      2295470.09     13756085.07
#Sta/Elev= 30
  4520.6  522.86  4533.6  523.12  4550.4  523.01  4672.3   521.3  4763.7  521.01
  4824.6  518.83  4867.1  519.13  4888.1   517.7  4902.2  512.94  4966.2  511.93
  4976.3  505.69  4982.1  505.98  4988.6  500.92  4995.5   500.9    4996   500.4
    5012   500.9  5019.6  507.67  5025.4  506.34  5041.3  508.96  5062.9  508.19
  5106.2  510.36    5138  513.55    5181     514  5246.2  514.66  5289.5  516.73
  5342.9  516.96  5406.9  518.99  5459.7  519.03  5526.2  521.77  5580.2  522.03
#Mann= 9 ,-1 , 0
  4520.6     .07       0  4533.6     .07       0  4550.4     .07       0
  4672.3     .07       0  4763.7      .1       0  4995.5     .05       0
    5012      .1       0    5181     .07       0  5406.9      .1       0
Bank Sta=4995.5,5012
XS Rating Curve= 0 ,0
Exp/Cntr=0.3,0.1

Type RM Length L Ch R = 1 ,6505    ,302,302,302
BEGIN DESCRIPTION:
WALNUT BRANCH 14.0
END DESCRIPTION:
XS GIS Cut Line= 3
        2296225.       13756275.        2295975.       13756175.
      2295824.97     13755974.97
#Sta/Elev= 30
  4730.7  519.31  4771.3  518.83  4821.9  517.49  4838.4  517.43  4853.2  516.47
  4859.9  515.24  4913.8  512.51  4967.6  512.49  4978.4  509.02  4985.1  504.83
  4990.5  504.79  4997.3  500.34  5003.1  500.34  5005.2  499.05  5005.7  498.55
  5021.8  499.05    5050  500.65  5057.2  501.48  5063.5   503.7  5086.4  504.64
  5107.2  507.13  5113.5  510.39  5120.3  510.19  5128.1  511.66  5136.4  511.76
  5157.2   517.4  5163.5   517.1  5212.4  519.56  5228.1   520.8    5250  520.51
#Mann= 7 ,-1 , 0
  4730.7     .12       0  4771.3     .08       0  4821.9     .12       0
  5005.2     .05       0  5021.8     .12       0  5120.3     .08       0
  5212.4     .12       0
#XS Ineff= 2 , 0
       0    4965   515.4    5080       0   515.5
Permanent Ineff=
       F       F
Bank Sta=5005.2,5021.8
XS Rating Curve= 0 ,0
Exp/Cntr=0.3,0.1

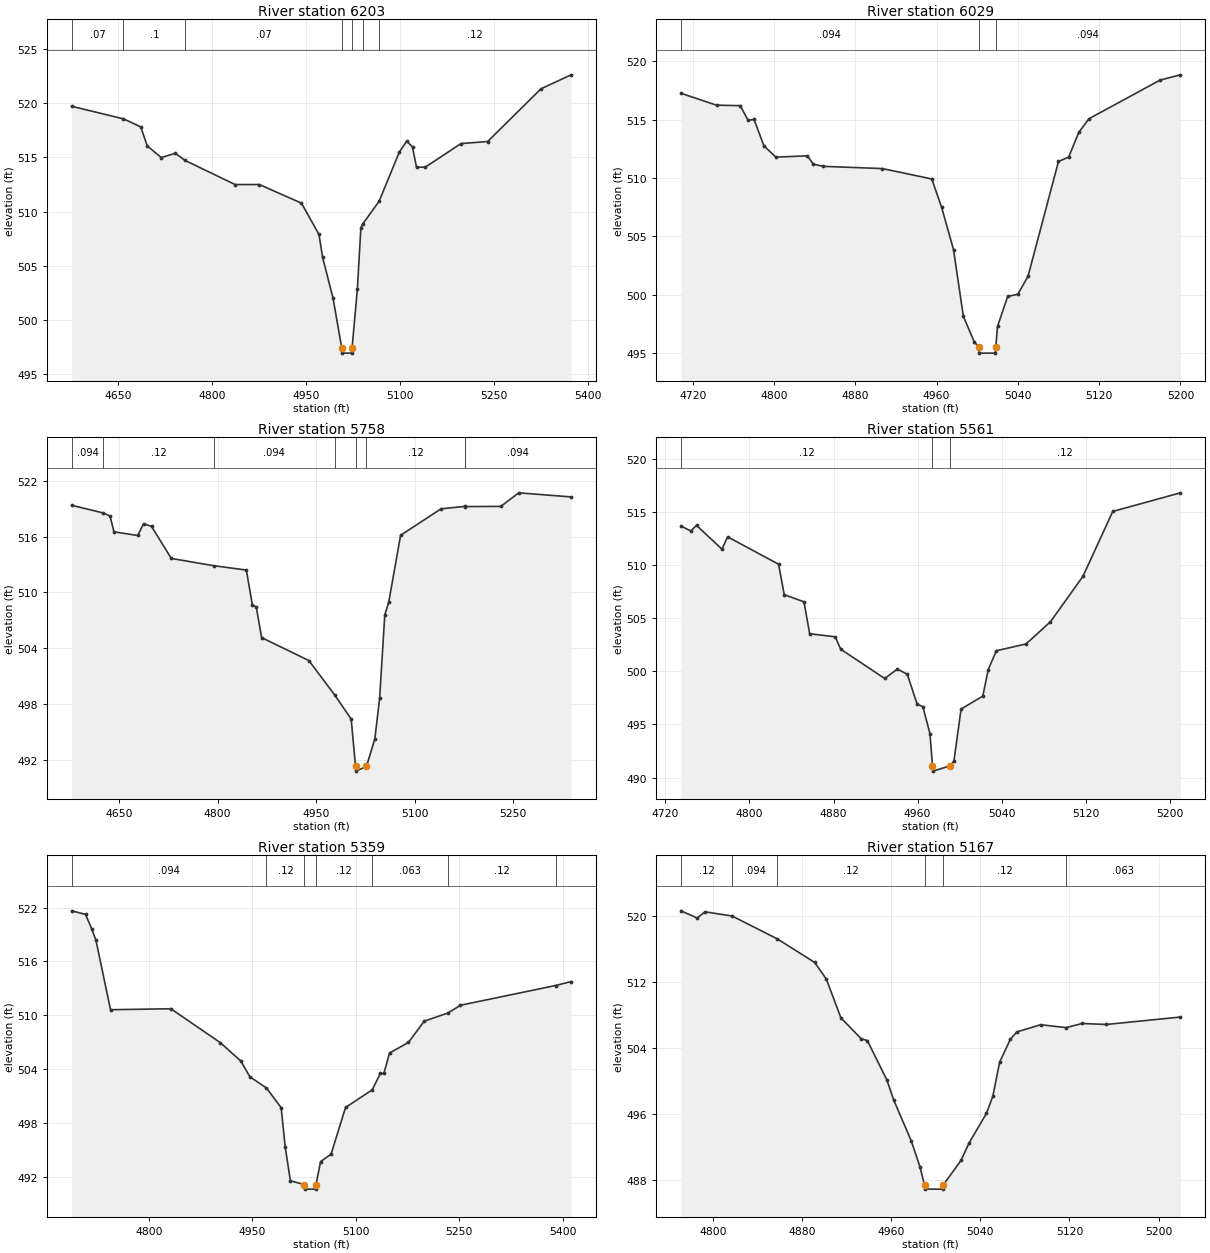
Type RM Length L Ch R = 1 ,6203    ,174,174,174
BEGIN DESCRIPTION:
H21551
END DESCRIPTION:
XS GIS Cut Line= 3
      2296462.73     13756107.54      2295979.51     13755864.05
      2295789.27     13755692.46
#Sta/Elev= 30
  4575.7  519.71  4658.4  518.55    4686  517.81  4696.3  516.06  4718.7  514.98
  4741.1  515.37  4756.9  514.71  4836.6  512.49  4875.5  512.49  4942.6  510.77
  4970.5  507.89  4976.3  505.77  4992.8  502.05  5006.8  497.44  5007.3  496.94
  5022.9  496.94  5023.4  497.44  5031.8  502.85  5037.4  508.51  5040.5  508.86
  5066.6  510.96  5098.7  515.48  5110.7   516.5  5119.8  515.95  5126.2  514.08
  5140.4   514.1  5197.2  516.27  5239.8  516.46  5324.9  521.32    5373  522.61
#Mann= 7 ,-1 , 0
  4575.7     .07       0  4658.4      .1       0  4756.9     .07       0
  5006.8     .05       0  5023.4     .07       0  5040.5      .1       0
  5066.6     .12       0
Bank Sta=5006.8,5023.4
XS Rating Curve= 0 ,0
Exp/Cntr=0.3,0.1

Type RM Length L Ch R = 1 ,6029    ,271,271,271
BEGIN DESCRIPTION:
WALNUT BRANCH 13.0
END DESCRIPTION:
XS GIS Cut Line= 3
      2296424.97     13755924.98        2296175.       13755775.
        2296175.     13755575.01
#Sta/Elev= 30
  4708.5  517.26  4743.5  516.24  4766.8   516.2  4774.5  514.95  4780.4  515.02
  4790.1  512.77  4801.8  511.79  4832.9   511.9  4838.7  511.19  4848.4     511
  4906.7  510.81  4955.3  509.92    4965  507.49  4976.7  503.87  4986.4  498.15
  4997.1  495.97  5001.7   495.5  5002.2     495  5017.8     495  5018.3   495.5
    5020  497.29    5030  499.86    5040  500.04    5050  501.58    5080  511.42
    5090  511.79    5100  513.91    5110  515.08    5180  518.39    5200  518.84
#Mann= 3 ,-1 , 0
  4708.5    .094       0  5001.7     .05       0  5018.3    .094       0
Bank Sta=5001.7,5018.3
XS Rating Curve= 0 ,0
Exp/Cntr=0.3,0.1

Type RM Length L Ch R = 1 ,5758    ,197,197,197
BEGIN DESCRIPTION:
H21550
END DESCRIPTION:
XS GIS Cut Line= 3
      2296593.83     13755976.41      2296316.65     13755556.89
      2296092.29     13755429.75
#Sta/Elev= 30
  4577.8  519.38  4626.2  518.55  4636.3  518.22  4642.3  516.52  4678.4  516.13
  4687.4   517.4  4699.5   517.1  4729.6  513.66  4793.9  512.88  4843.9  512.41
    4853  508.68    4859  508.43  4867.1  505.14  4939.1  502.67  4978.4  498.97
  5003.5  496.38  5010.2  491.27  5010.7  490.77  5026.8  491.27  5039.6  494.26
  5046.9  498.64  5054.7  507.59  5060.7  508.95  5078.8  516.15  5140.4     519
  5176.4  519.26  5177.4  519.24  5231.4  519.26  5258.8  520.72  5338.5  520.28
#Mann= 8 ,-1 , 0
  4577.8    .094       0  4626.2     .12       0  4793.9    .094       0
  4978.4     .12       0  5010.2     .05       0  5026.8     .12       0
  5176.4    .063       0  5177.4    .094       0
Bank Sta=5010.2,5026.8
XS Rating Curve= 0 ,0
Exp/Cntr=0.3,0.1

Type RM Length L Ch R = 1 ,5561    ,202,202,202
BEGIN DESCRIPTION:
WALNUT BRANCH 12.0
END DESCRIPTION:
XS GIS Cut Line= 3
        2296625.     13755775.01        2296525.       13755525.
      2296325.02       13755475.
#Sta/Elev= 30
  4734.8  513.67  4744.2   513.2  4749.6  513.73  4773.8  511.49  4779.2  512.65
  4827.7  510.07  4833.1  507.21  4851.9  506.53  4857.3  503.53  4881.6  503.24
  4886.9  502.07  4928.7  499.32  4940.8   500.2  4950.2  499.72  4959.6   496.9
    4965  496.67  4971.8  494.13  4974.2   491.1  4974.7   490.6  4990.9   491.1
  4994.6  491.54  5001.4  496.44  5022.1  497.66  5027.3  500.16    5035  501.93
  5063.3  502.57  5086.5  504.66  5117.4  508.93  5145.8  515.04  5210.2  516.79
#Mann= 3 ,-1 , 0
  4734.8     .12       0  4974.2     .05       0  4990.9     .12       0
Bank Sta=4974.2,4990.9
XS Rating Curve= 0 ,0
Exp/Cntr=0.3,0.1

Type RM Length L Ch R = 1 ,5359    ,192,192,192
BEGIN DESCRIPTION:
H21549
END DESCRIPTION:
XS GIS Cut Line= 3
      2296898.65     13755780.63      2296650.92     13755401.51
      2296391.54     13755320.89
#Sta/Elev= 30
  4687.8  521.64    4708  521.24  4717.2  519.58  4723.1  518.34  4744.2  510.61
  4831.7  510.72  4903.6  506.93  4933.4  504.87  4946.3  503.13  4970.4  501.88
  4991.7  499.69  4997.6   495.3  5005.1  491.53  5025.5   491.1    5026   490.6
  5041.7   490.6  5042.2   491.1  5048.9  493.67  5064.1   494.5  5085.1  499.71
  5123.7  501.67  5135.6   503.5  5140.7   503.5  5148.9  505.78  5176.3  506.96
  5199.2  509.33  5233.8  510.25  5251.8  511.11  5389.8  513.31  5412.3  513.75
#Mann= 7 ,-1 , 0
  4687.8    .094       0  4970.4     .12       0  5025.5     .05       0
  5042.2     .12       0  5123.7    .063       0  5233.8     .12       0
  5389.8    .063       0
Bank Sta=5025.5,5042.2
XS Rating Curve= 0 ,0
Exp/Cntr=0.3,0.1

Type RM Length L Ch R = 1 ,5167    ,239,239,239
BEGIN DESCRIPTION:
WALNUT BRANCH 11.0
END DESCRIPTION:
XS GIS Cut Line= 3
      2297074.96     13755474.98      2296862.45     13755384.51
      2296674.97     13755274.98
#Sta/Elev= 30
  4771.5  520.63    4786  519.76  4793.2  520.51  4817.4     520  4858.1  517.22
  4891.4  514.38  4901.9  512.37    4915  507.66  4933.2  505.13  4938.7  504.91
  4956.2  500.15  4962.3  497.73    4978  492.79  4985.9  489.62    4990  487.41
  4990.5  486.91  5006.3  486.91  5006.8  487.41  5022.7  490.38  5029.9  492.48
  5045.6   496.1  5051.3  498.16  5057.4   502.3    5067  505.06  5072.8  505.96
  5094.3  506.83    5117  506.48  5131.5  506.98    5153  506.86  5219.6  507.76
#Mann= 6 ,-1 , 0
  4771.5     .12       0  4817.4    .094       0  4858.1     .12       0
    4990     .05       0  5006.8     .12       0    5117    .063       0
Bank Sta=4990,5006.8
XS Rating Curve= 0 ,0
Exp/Cntr=0.3,0.1

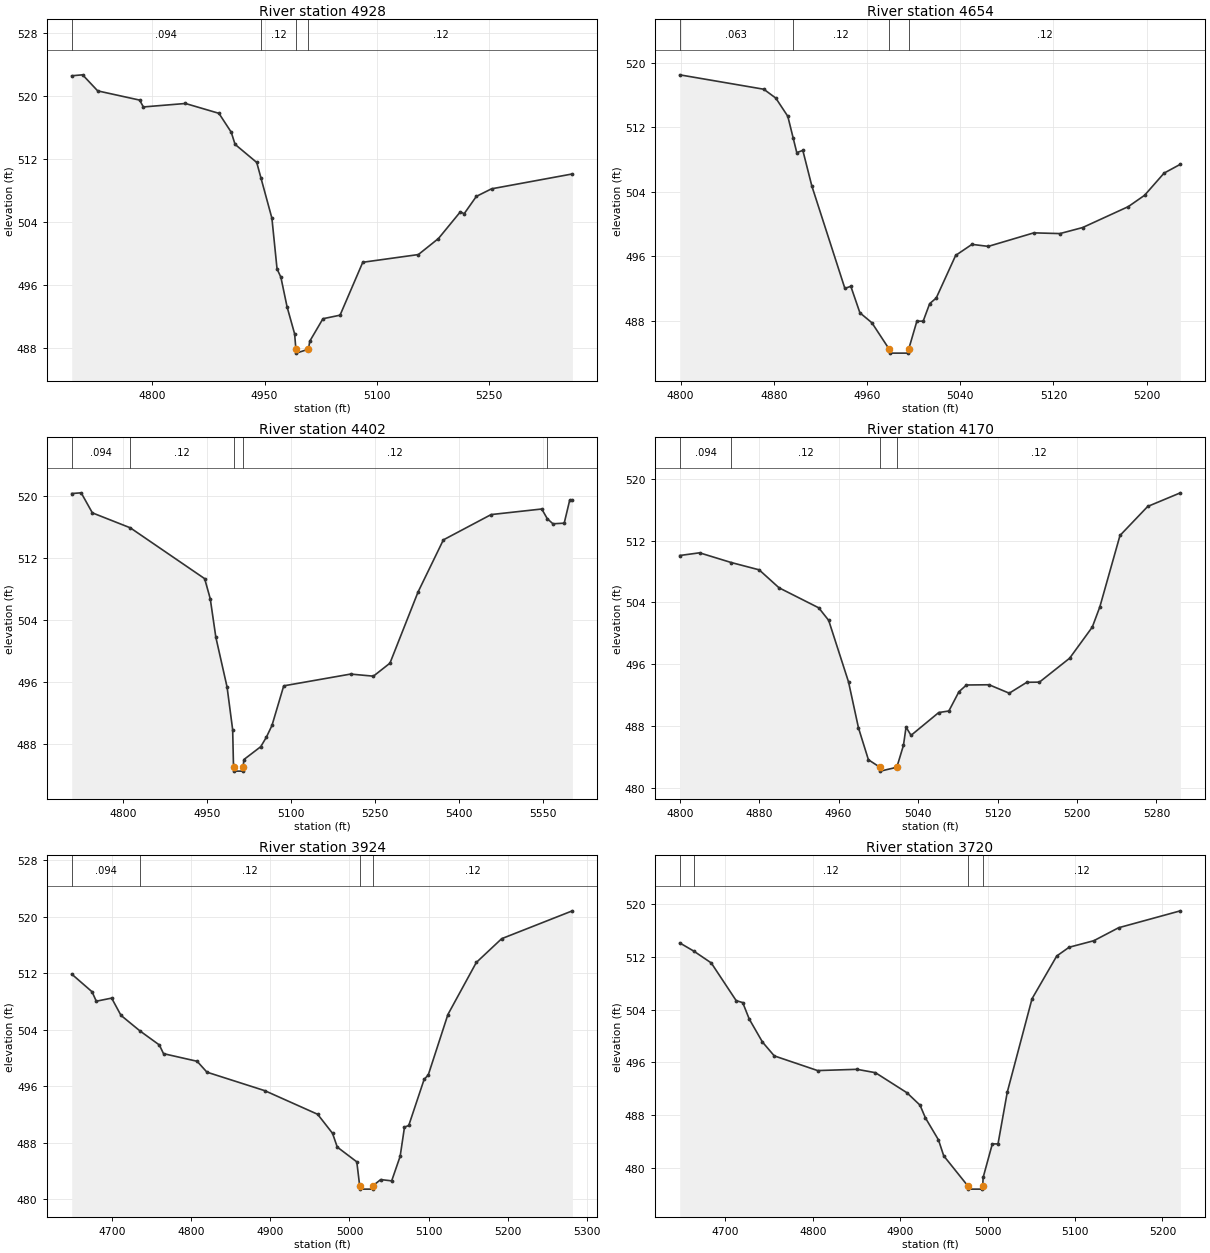
Type RM Length L Ch R = 1 ,4928    ,274,274,274
BEGIN DESCRIPTION:
H21548
END DESCRIPTION:
XS GIS Cut Line= 2
      2297279.37     13755234.74      2296618.18     13755126.41
#Sta/Elev= 30
    4692  522.52  4706.6  522.64  4726.8   520.6  4782.9  519.43  4787.9  518.56
  4844.2     519    4889  517.75  4905.5  515.35  4910.6  513.81  4939.6  511.51
  4945.2  509.56  4959.9  504.43  4966.8  497.98  4971.9  496.94  4980.2  493.17
  4990.3  489.74    4992  487.79  4992.5  487.29  5008.8  487.79  5010.6  488.81
  5028.2  491.66  5051.1  492.11  5081.5  498.83  5155.9  499.81  5182.8  501.85
  5212.1  505.24  5217.2     505  5233.5   507.2  5253.8  508.16    5362  510.05
#Mann= 4 ,-1 , 0
    4692    .094       0  4945.2     .12       0    4992     .05       0
  5008.8     .12       0
Bank Sta=4992,5008.8
XS Rating Curve= 0 ,0
Exp/Cntr=0.3,0.1

Type RM Length L Ch R = 1 ,4654    ,252,252,252
BEGIN DESCRIPTION:
WALNUT BRANCH 10.0
END DESCRIPTION:
XS GIS Cut Line= 3
      2297125.03     13754975.01        2296925.       13754925.
        2296725.       13755025.
#Sta/Elev= 30
  4799.2  518.52  4871.4  516.73  4881.7  515.63    4892  513.37  4896.6  510.68
  4899.7  508.86  4904.9  509.13  4912.6  504.73    4941  491.99  4946.1  492.25
  4953.9  488.96  4964.2  487.72    4979  484.45  4979.5  483.95  4995.3  483.95
  4995.8  484.45  5002.8  487.92  5008.2  487.92  5013.8   490.1  5019.4  490.79
  5036.1  496.09  5050.1  497.46  5064.1  497.21  5103.2  498.89  5125.6   498.8
  5145.1  499.55  5184.3  502.15  5198.3  503.56    5215  506.31    5229  507.41
#Mann= 4 ,-1 , 0
  4799.2    .063       0  4896.6     .12       0    4979     .05       0
  4995.8     .12       0
Bank Sta=4979,4995.8
XS Rating Curve= 0 ,0
Exp/Cntr=0.3,0.1

Type RM Length L Ch R = 1 ,4402    ,232,232,232
BEGIN DESCRIPTION:
H21547
END DESCRIPTION:
XS GIS Cut Line= 3
      2297211.88     13754661.62      2296754.92     13754684.09
      2296320.44      13754717.8
#Sta/Elev= 30
  4708.7  520.34  4725.6  520.43  4745.6  517.84  4813.2  515.91  4945.9  509.34
  4955.9  506.74  4965.9  501.76  4985.9  495.34  4995.9  489.81  4997.4  484.97
  4997.9  484.47  5013.9  484.47  5014.4  484.97    5016  485.97    5046  487.63
    5056  488.85    5066  490.37    5087  495.49  5206.3  497.01    5247  496.74
  5276.5  498.42  5326.6  507.61  5371.8  514.35    5457  517.62  5547.3  518.34
  5557.3  517.08  5567.3  516.43  5587.4  516.51  5597.2  519.48    5602  519.48
#Mann= 5 ,-1 , 0
  4708.7    .094       0  4813.2     .12       0  4997.4     .05       0
  5014.4     .12       0  5557.3    .063       0
Bank Sta=4997.4,5014.4
XS Rating Curve= 0 ,0
Exp/Cntr=0.3,0.1

Type RM Length L Ch R = 1 ,4170    ,246,246,246
BEGIN DESCRIPTION:
WALNUT BRANCH 9.0
END DESCRIPTION:
XS GIS Cut Line= 3
        2297025.       13754475.        2296825.       13754475.
      2296525.03     13754425.01
#Sta/Elev= 30
    4800  510.06    4820  510.41    4852  509.15    4880  508.21    4900  505.89
    4940   503.3    4950  501.68    4970  493.72    4980  487.79    4990  483.67
  5001.6   482.7  5002.1   482.2  5018.6   482.7  5025.3  485.54  5027.9  487.89
  5032.9  486.82  5060.8  489.77    5071  489.97  5081.1  492.45  5088.7  493.33
  5111.5  493.36  5131.8  492.27  5149.5  493.68  5162.2   493.7  5192.6  496.79
  5215.4  500.81    5223  503.42  5243.3  512.65  5271.2   516.4  5304.1  518.16
#Mann= 4 ,-1 , 0
    4800    .094       0    4852     .12       0  5001.6     .05       0
  5018.6     .12       0
Bank Sta=5001.6,5018.6
XS Rating Curve= 0 ,0
Exp/Cntr=0.3,0.1

Type RM Length L Ch R = 1 ,3924    ,204,204,204
BEGIN DESCRIPTION:
H21546
END DESCRIPTION:
XS GIS Cut Line= 2
      2297103.29     13754369.43      2296511.42     13754144.68
#Sta/Elev= 30
  4648.8  511.86  4674.5  509.36  4679.9  508.02  4699.3  508.46  4711.1  506.02
  4735.3   503.8  4759.6  501.83  4764.9   500.6  4807.4  499.52  4819.8  497.98
    4893  495.36  4959.8  492.02  4978.6  489.33  4984.6  487.38  5009.3  485.29
  5012.9  481.93  5013.4  481.43  5029.4  481.43  5029.9  481.93  5039.5  482.78
  5053.4   482.6  5064.1  486.07  5069.6   490.2    5075  490.44  5094.4  496.95
  5099.7   497.6  5124.5  506.14  5160.4   513.5  5192.5  516.87  5281.9  520.81
#Mann= 4 ,-1 , 0
  4648.8    .094       0  4735.3     .12       0  5012.9     .05       0
  5029.9     .12       0
Bank Sta=5012.9,5029.9
XS Rating Curve= 0 ,0
Exp/Cntr=0.3,0.1

Type RM Length L Ch R = 1 ,3720    ,203,203,203
BEGIN DESCRIPTION:
WALNUT BRANCH 8.0
END DESCRIPTION:
XS GIS Cut Line= 3
      2297175.02     13754275.01        2296875.       13754075.
      2296725.01     13753925.01
#Sta/Elev= 30
  4647.8  514.08  4663.9  512.84  4683.9  511.05  4712.4  505.35  4719.9  505.05
  4727.4  502.55  4742.5  499.08    4756  496.99  4805.6  494.77  4850.6  494.96
  4871.7  494.45  4907.7  491.42  4922.7  489.54  4928.8  487.63  4943.8  484.29
  4949.8  481.88  4977.3  477.34  4977.8  476.84  4993.9  476.84  4994.4  477.34
  4994.9  478.61  5005.4  483.68  5011.9  483.68  5022.5  491.51  5050.8  505.63
  5079.1   512.1  5093.2  513.42  5121.5  514.41  5149.8  516.37  5220.5  518.93
#Mann= 4 ,-1 , 0
  4647.8    .094       0  4663.9     .12       0  4977.3     .05       0
  4994.4     .12       0
Bank Sta=4977.3,4994.4
XS Rating Curve= 0 ,0
Exp/Cntr=0.3,0.1

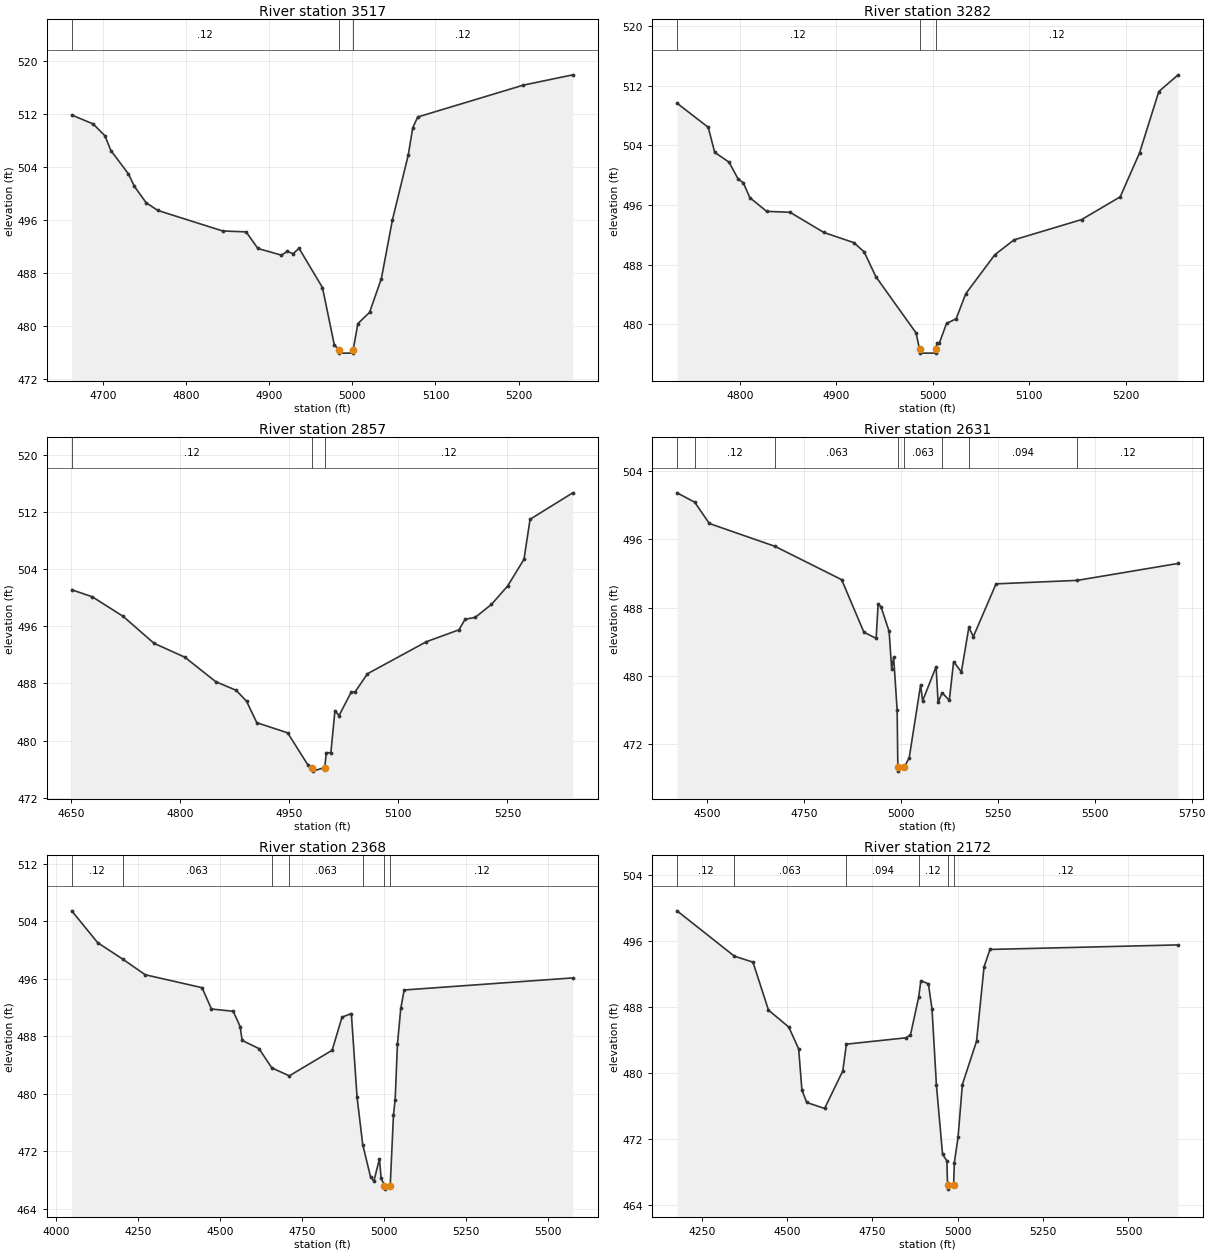
Type RM Length L Ch R = 1 ,3517    ,235,235,235
BEGIN DESCRIPTION:
H21545
END DESCRIPTION:
XS GIS Cut Line= 3
      2297279.36     13754197.14      2297009.64     13753931.16
      2296801.53     13753849.41
#Sta/Elev= 30
  4662.7  511.88  4688.5  510.53  4702.6  508.75  4709.8  506.52  4730.9     503
  4738.1  501.11  4752.2  498.64  4766.3  497.48  4844.1  494.39  4872.4  494.25
  4886.5  491.75  4914.8  490.74  4921.8  491.31  4928.9  490.96    4936  491.77
  4964.2  485.84  4978.4   477.2    4984  476.46  4984.5  475.96  5000.6  475.96
  5001.1  476.46  5006.7  480.41  5020.8  482.11    5035  487.21  5048.3  496.07
  5067.3  505.84  5072.7  509.95  5078.7  511.58  5205.5  516.38  5265.1  517.94
#Mann= 3 ,-1 , 0
  4662.7     .12       0    4984     .05       0  5001.1     .12       0
Bank Sta=4984,5001.1
XS Rating Curve= 0 ,0
Exp/Cntr=0.3,0.1

Type RM Length L Ch R = 1 ,3282    ,425,425,425
BEGIN DESCRIPTION:
WALNUT BRANCH 7.0
END DESCRIPTION:
XS GIS Cut Line= 3
        2297325.     13754074.99        2297225.       13753825.
      2296975.05       13753825.
#Sta/Elev= 30
  4735.1  509.65  4767.4  506.42  4774.1  503.06  4788.9  501.75  4798.4  499.48
  4803.7  498.99  4810.5  496.98    4828  495.14  4852.2  495.02  4887.2  492.31
  4918.2  490.95    4929   489.7  4941.1  486.38  4982.8  478.82  4986.4  476.62
  4986.9  476.12    5003  476.12  5003.5  476.62  5004.3  477.44  5006.8  477.44
  5014.3   480.1  5024.3  480.73  5034.3   484.1  5064.3  489.31  5084.3  491.32
  5154.3  494.04  5194.3  497.09  5214.3  502.97  5234.3  511.22  5254.3  513.46
#Mann= 3 ,-1 , 0
  4735.1     .12       0  4986.4     .05       0  5003.5     .12       0
Bank Sta=4986.4,5003.5
XS Rating Curve= 0 ,0
Exp/Cntr=0.3,0.1

Type RM Length L Ch R = 1 ,2857    ,226,226,226
BEGIN DESCRIPTION:
WALNUT BRANCH 6.0
END DESCRIPTION:
XS GIS Cut Line= 3
      2297524.97     13753724.97        2297275.       13753475.
      2296975.01     13753624.99
#Sta/Elev= 30
    4651  501.11  4679.2  500.13  4721.7  497.39  4764.1  493.62  4806.5  491.67
  4848.9  488.25  4877.2  487.03  4891.4   485.5  4905.5   482.5  4947.9  481.08
  4976.2  476.51  4981.8  476.22  4982.3  475.72  4998.9  476.22    5001   478.3
  5007.3   478.3  5012.9  484.18  5018.5  483.49  5035.3  486.78  5040.8  486.84
  5057.6  489.35  5138.7  493.84  5183.4   495.5  5191.8  496.97  5205.8  497.25
  5228.1  499.06  5250.5  501.66  5272.8  505.37  5281.2  510.98  5339.9  514.68
#Mann= 3 ,-1 , 0
    4651     .12       0  4981.8     .05       0  4998.9     .12       0
Bank Sta=4981.8,4998.9
XS Rating Curve= 0 ,0
Exp/Cntr=0.3,0.1

Type RM Length L Ch R = 1 ,2631    ,263,263,263
BEGIN DESCRIPTION:
H21544
END DESCRIPTION:
XS GIS Cut Line= 4
       2297837.5     13753620.26       2297455.4      13753305.6
      2297107.03     13753211.95      2296694.99     13753065.86
#Sta/Elev= 30
  4422.2  501.44  4467.8  500.34  4505.5  497.85    4675  495.17  4846.9  491.27
  4904.3  485.12  4935.9   484.4  4941.1  488.45  4948.7  488.07  4969.4  485.22
  4975.9  480.84  4981.1  482.19  4990.1  475.98  4991.9  469.35  4992.4  468.85
    5009  469.35  5021.2  470.41  5050.7  478.96  5055.8  477.07  5090.6  481.09
  5095.8  476.89  5106.2  478.03  5124.7  477.14  5135.8  481.66  5155.8  480.47
  5175.1  485.67  5186.8  484.61  5245.3  490.78  5455.1  491.19  5715.1  493.17
#Mann= 8 ,-1 , 0
  4422.2    .063       0  4467.8     .12       0    4675    .063       0
  4991.9     .05       0    5009    .063       0  5106.2     .12       0
  5175.1    .094       0  5455.1     .12       0
Bank Sta=4991.9,5009
XS Rating Curve= 0 ,0
Exp/Cntr=0.3,0.1

Type RM Length L Ch R = 1 ,2368    ,196,196,196
BEGIN DESCRIPTION:
WALNUT BRANCH 5.0
END DESCRIPTION:
XS GIS Cut Line= 3
      2298138.06      13753522.3      2297432.03     13753061.85
      2296763.53     13752908.37
#Sta/Elev= 30
  4046.8  505.44  4126.1  501.01  4202.4  498.73    4271  496.56  4444.4  494.76
  4473.2   491.8  4539.6  491.48  4560.7  489.36  4566.7  487.44    4618   486.3
  4657.5  483.61  4710.7  482.51  4841.3  486.06  4871.5  490.66    4900  491.17
  4917.4  479.56  4934.7  472.96  4958.5  468.48  4968.7  467.88  4985.7  470.96
  4990.9   468.3  5000.9  467.27  5001.4  466.77  5018.6  467.27  5028.6  477.13
  5033.7  479.22  5040.6  486.87  5050.8  491.88  5061.1  494.44  5575.6  496.12
#Mann= 7 ,-1 , 0
  4046.8     .12       0  4202.4    .063       0  4657.5    .094       0
  4710.7    .063       0  4934.7     .12       0  5000.9     .05       0
  5018.6     .12       0
Bank Sta=5000.9,5018.6
XS Rating Curve= 0 ,0
Exp/Cntr=0.3,0.1

Type RM Length L Ch R = 1 ,2172    ,239,239,239
BEGIN DESCRIPTION:
H21543
END DESCRIPTION:
XS GIS Cut Line= 3
      2298140.92     13753189.48      2297298.08     13752826.12
      2296748.72     13752796.22
#Sta/Elev= 30
  4177.4  499.64  4345.1  494.15  4399.8  493.42  4445.2  487.61  4504.8  485.55
  4533.7   482.9  4543.2  477.92  4557.3  476.41  4609.7  475.69    4663  480.24
  4673.5  483.48  4848.1  484.25  4861.3  484.61  4885.3  489.17  4891.7  491.18
  4913.8  490.79  4924.3  487.78  4937.3  478.51  4955.3  470.12  4967.9  469.34
  4969.9  466.41  4970.4  465.91  4987.6  466.41  4989.8  469.13  5000.6  472.17
  5013.3  478.59  5054.9  483.85  5076.8  492.85  5094.2  494.96  5645.4  495.51
#Mann= 6 ,-1 , 0
  4177.4     .12       0  4345.1    .063       0  4673.5    .094       0
  4885.3     .12       0  4969.9     .05       0  4987.6     .12       0
Bank Sta=4969.9,4987.6
XS Rating Curve= 0 ,0
Exp/Cntr=0.3,0.1

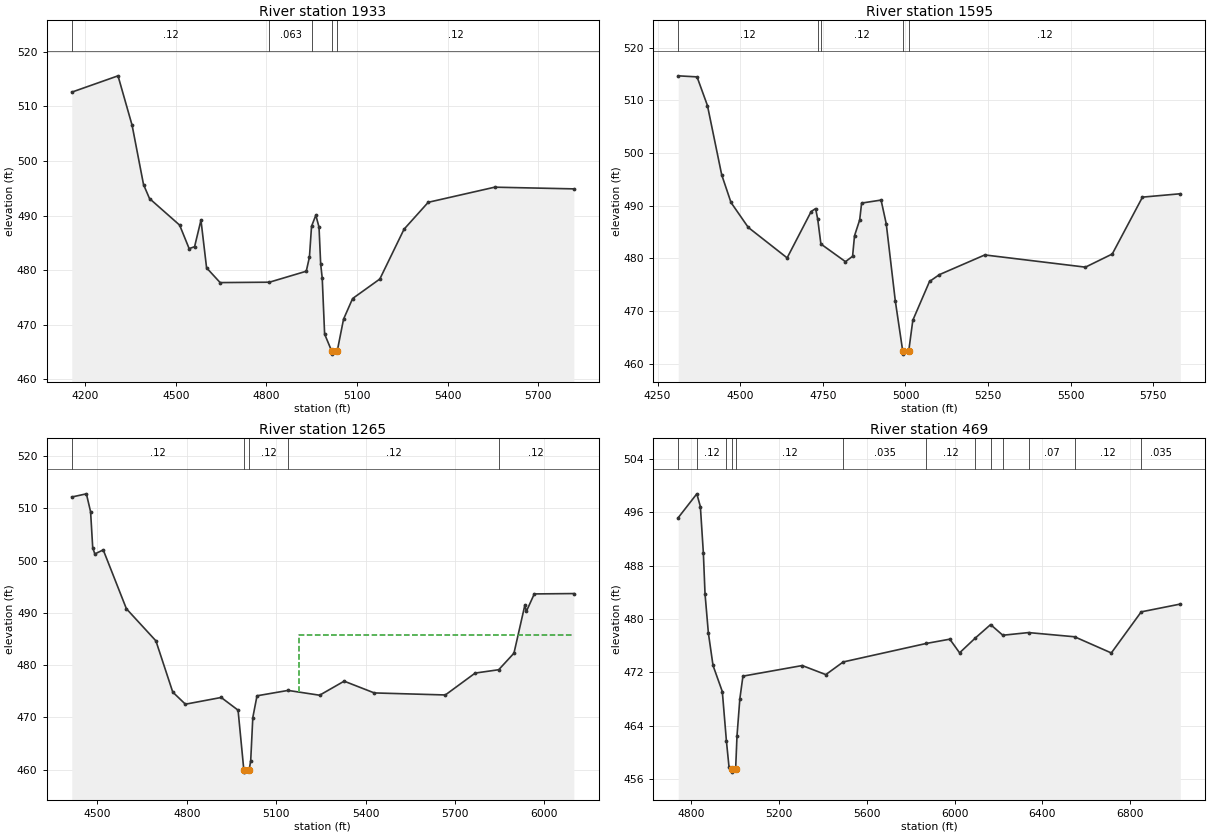
Type RM Length L Ch R = 1 ,1933    ,338,338,338
BEGIN DESCRIPTION:
WALNUT BRANCH 4.0
END DESCRIPTION:
XS GIS Cut Line= 3
      2298369.94     13752993.63        2297575.       13752725.
      2296753.29     13752707.14
#Sta/Elev= 30
  4156.2  512.59  4309.2  515.58  4355.8  506.52  4393.6  495.67  4413.4  493.11
  4513.1  488.24  4544.5  483.94  4562.5  484.29  4583.6  489.15  4602.2  480.42
    4647  477.72  4810.1  477.79    4932   479.8  4942.5   482.4  4949.4  488.02
  4963.6  490.06  4974.2  487.86  4979.6  481.15  4984.8  478.52  4992.7  468.29
  5016.5  465.12    5017  464.62  5034.2  465.12  5055.3  471.02  5085.3   474.8
  5175.3  478.37  5255.4  487.49  5335.4  492.42  5555.4  495.19  5817.2  494.88
#Mann= 5 ,-1 , 0
  4156.2     .12       0  4810.1    .063       0  4949.4     .12       0
  5016.5     .05       0  5034.2     .12       0
Bank Sta=5016.5,5034.2
XS Rating Curve= 0 ,0
Exp/Cntr=0.3,0.1

Type RM Length L Ch R = 1 ,1595    ,330,330,330
BEGIN DESCRIPTION:
H21542
END DESCRIPTION:
XS GIS Cut Line= 3
      2298343.22     13752796.17      2297650.19     13752395.34
      2296942.19     13752271.72
#Sta/Elev= 30
  4312.4  514.66  4369.3  514.46  4400.8  509.01  4443.9  495.86  4472.1   490.6
  4524.3  485.87  4641.9  480.08  4714.7  488.89  4728.1  489.44  4734.5  487.42
  4744.1  482.72  4818.5  479.36    4840  480.39  4845.8  484.27  4861.5   487.3
  4867.3  490.49  4926.2  491.06  4941.9  486.54  4969.2  471.93  4991.9   462.3
  4992.4   461.8  5009.7   462.3  5022.3  468.24  5072.8   475.6  5102.7   476.9
  5240.1  480.64  5544.6  478.32  5625.8  480.82  5717.2  491.62  5831.7  492.26
#Mann= 5 ,-1 , 0
  4312.4     .12       0  4734.5    .063       0  4744.1     .12       0
  4991.9     .05       0  5009.7     .12       0
Bank Sta=4991.9,5009.7
XS Rating Curve= 0 ,0
Exp/Cntr=0.3,0.1

Type RM Length L Ch R = 1 ,1265    ,796,796,796
BEGIN DESCRIPTION:
H21541
END DESCRIPTION:
XS GIS Cut Line= 3
      2298414.35     13752665.04      2297882.44     13752133.13
      2296975.93     13751912.12
#Sta/Elev= 30
  4413.8  512.16  4462.9  512.77    4477  509.33  4484.1  502.47  4491.2  501.26
  4519.4  502.04  4597.2  490.77  4696.2  484.63  4752.8  474.82  4795.2   472.5
  4915.4  473.79    4972  471.36  4991.2     460  4991.7   459.5  5009.4     460
  5014.4  461.67  5021.5  469.95  5035.6  474.11  5139.8  475.14  5245.7  474.22
  5328.1  476.91  5429.2  474.66  5667.8  474.27  5767.9  478.46  5846.9   479.1
  5898.1  482.27  5934.7  491.47  5939.8  490.28  5966.3  493.61  6099.1  493.68
#Mann= 5 ,-1 , 0
  4413.8     .12       0  4991.2     .05       0  5009.4     .12       0
  5139.8     .12       0  5846.9     .12       0
#XS Ineff= 2 , 0
       0                    5176       0  485.72
Permanent Ineff=
       F       F
Bank Sta=4991.2,5009.4
XS Rating Curve= 0 ,0
Exp/Cntr=0.3,0.1

Type RM Length L Ch R = 1 ,469     ,0,0,0
BEGIN DESCRIPTION:
H21540
END DESCRIPTION:
XS GIS Cut Line= 3
      2298706.56      13752601.4      2298395.63      13752114.4
      2296912.21      13751267.8
#Sta/Elev= 30
  4742.1  495.22  4826.7   498.8  4842.9  496.88  4856.5  489.91  4864.1  483.77
  4879.3  477.91  4900.5  473.03  4942.8  469.11  4961.4  461.71  4973.2  457.83
  4985.3  457.52  4985.8  457.02  5003.5  457.52  5009.6  462.44  5022.6  468.03
  5036.7  471.43  5306.6  473.02    5414  471.66  5493.1  473.56  5871.8  476.34
  5978.5  476.98    6023  474.93  6094.8  477.16  6164.2  479.17  6219.8  477.57
    6337  477.97  6546.5  477.34  6713.8  474.91  6849.9  481.08  7027.9  482.25
#Mann= 13 ,-1 , 0
  4742.1    .035       0  4826.7     .12       0  4961.4     .12       0
  4985.3     .05       0  5003.5     .12       0  5493.1    .035       0
  5871.8     .12       0  6094.8     .12       0  6164.2     .12       0
  6219.8     .12       0    6337     .07       0  6546.5     .12       0
  6849.9    .035       0
Bank Sta=4985.3,5003.5
XS Rating Curve= 0 ,0
Exp/Cntr=0.3,0.1

Chan Stop Cuts=-1
Use User Specified Reach Order=0
Composite Channel Slope=5