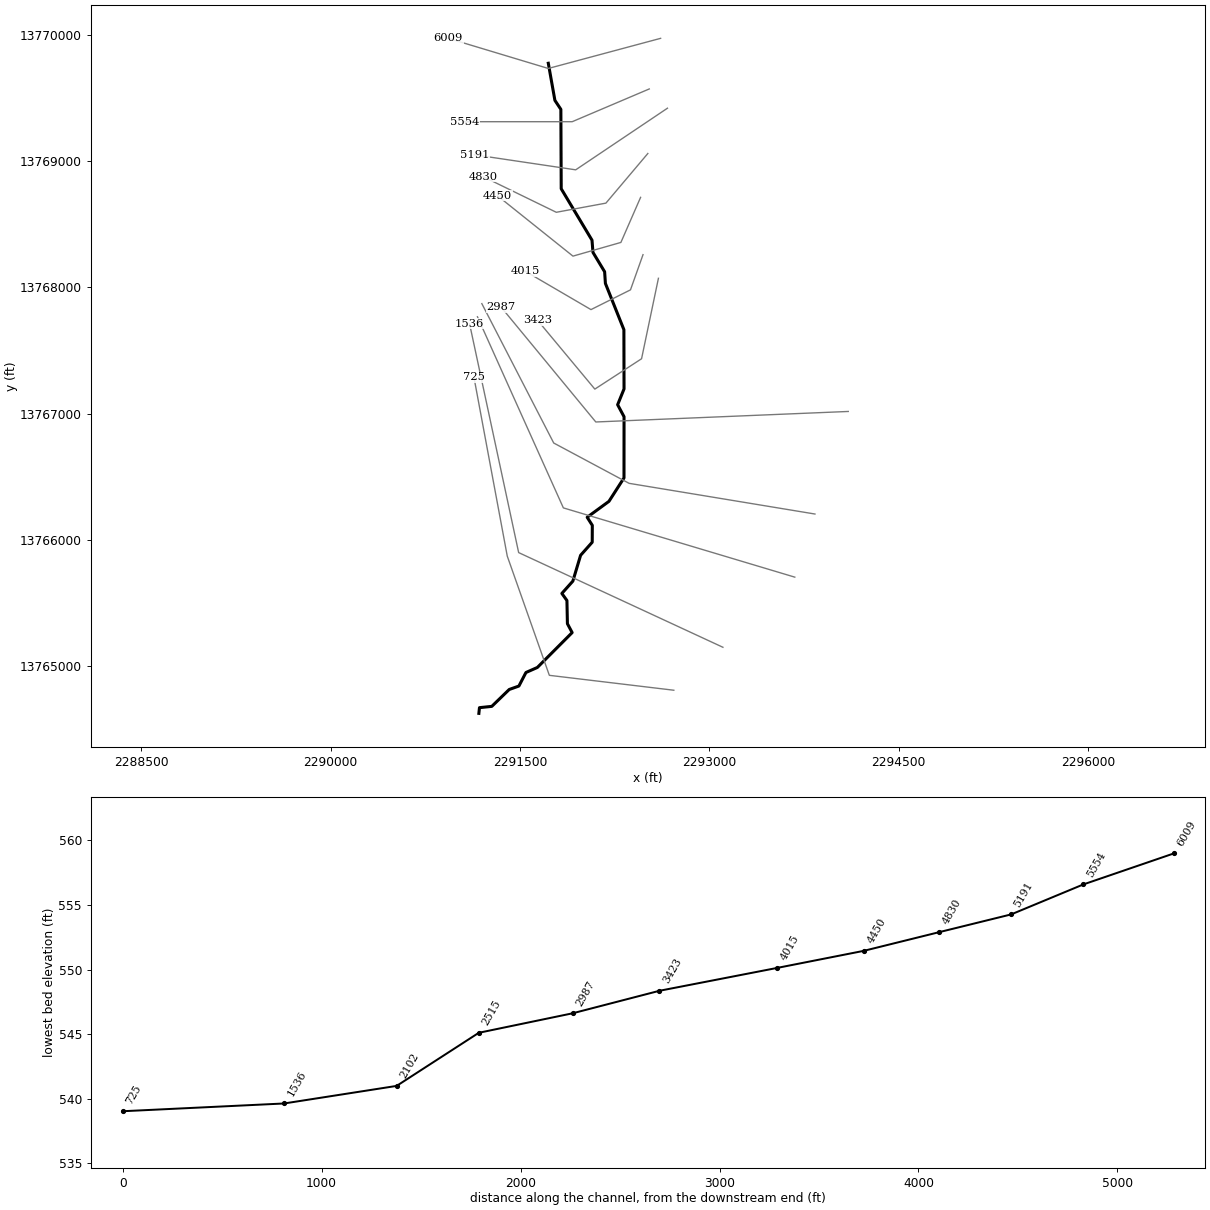
--- WALNUT TRIBUTARY 1.prj (project) ---

Proj Title=WALNUT TRIBUTARY 1 Base Level Engineering
Current Plan=p01
Default Exp/Contr=0.3,0.1
English Units
Geom File=g01
Flow File=f01
Plan File=p01
BEGIN DESCRIPTION:
WALNUT TRIBUTARY 1
END DESCRIPTION:

--- WALNUT TRIBUTARY 1.p01 (plan) ---

Plan Title=Multiple Run
Short Identifier=Multiple
Geom File=g01
Flow File=f01
Subcritical Flow
K Sum by GR= 0
Std Step Tol= 0.01
Critical Tol= 0.01
Num of Std Step Trials= 20
Max Error Tol= 0.3
Flow Tol Ratio= 0.001
Split Flow NTrial= 30
Split Flow Tol= 0.02
Split Flow Ratio= 0.02
Log Output Level= 0
Friction Slope Method= 1
Unsteady Friction Slope Method= 2
Unsteady Bridges Friction Slope Method= 1
Parabolic Critical Depth
Global Vel Dist=  1 , 1 , 1
Global Log Level= 0
CheckData=True
Encroach Param= -1, 0, 0, 0
BEGIN DESCRIPTION:
Multiple Run
END DESCRIPTION:

--- WALNUT TRIBUTARY 1.f01 (steady flow) ---

Flow Title=Multiple
Number of Profiles=7
Profile Names=10-year,25-year,50-year,1pct_min,100-year,1pct_plu,500-year
River Rch & RM= WALNUT TRIBUTARY,Reach-1,6009
     296     454     589     371     741    1478    1158
River Rch & RM= WALNUT TRIBUTARY,Reach-1,2987
     566     903    1204     777    1551    3094    2548
Boundary for River Rch & Prof#=WALNUT TRIBUTARY,Reach-1,1
Up Type=0
Dn Type=3
Dn Slope=0.005
Boundary for River Rch & Prof#=WALNUT TRIBUTARY,Reach-1,2
Up Type=0
Dn Type=3
Dn Slope=0.005
Boundary for River Rch & Prof#=WALNUT TRIBUTARY,Reach-1,3
Up Type=0
Dn Type=3
Dn Slope=0.005
Boundary for River Rch & Prof#=WALNUT TRIBUTARY,Reach-1,4
Up Type=0
Dn Type=3
Dn Slope=0.005
Boundary for River Rch & Prof#=WALNUT TRIBUTARY,Reach-1,5
Up Type=0
Dn Type=3
Dn Slope=0.005
Boundary for River Rch & Prof#=WALNUT TRIBUTARY,Reach-1,6
Up Type=0
Dn Type=3
Dn Slope=0.005
Boundary for River Rch & Prof#=WALNUT TRIBUTARY,Reach-1,7
Up Type=0
Dn Type=3
Dn Slope=0.005

--- WALNUT TRIBUTARY 1.g01 (geometry) ---

Geom Title=Existing Conditions

River Reach=WALNUT TRIBUTARY,Reach-1
Reach XY= 30
      2291725.00     13769775.00      2291777.27     13769480.94
      2291824.48     13769409.78      2291827.24     13768780.93
      2292071.17     13768373.42      2292078.83     13768276.58
      2292171.17     13768123.42      2292177.35     13768030.97
      2292323.78     13767664.50      2292324.93     13767195.03
      2292274.19     13767070.01      2292325.00     13766975.00
      2292324.61     13766490.16      2292205.37     13766304.53
      2292032.79     13766178.43      2292073.62     13766114.56
      2292072.94     13765980.86      2291980.85     13765877.29
      2291919.45     13765672.57      2291832.33     13765575.10
      2291872.53     13765519.15      2291876.39     13765335.43
      2291913.90     13765264.94      2291638.20     13764988.64
      2291547.86     13764948.83      2291492.05     13764841.50
      2291415.34     13764814.21      2291277.40     13764680.49
      2291179.68     13764670.25      2291175.00     13764625.00

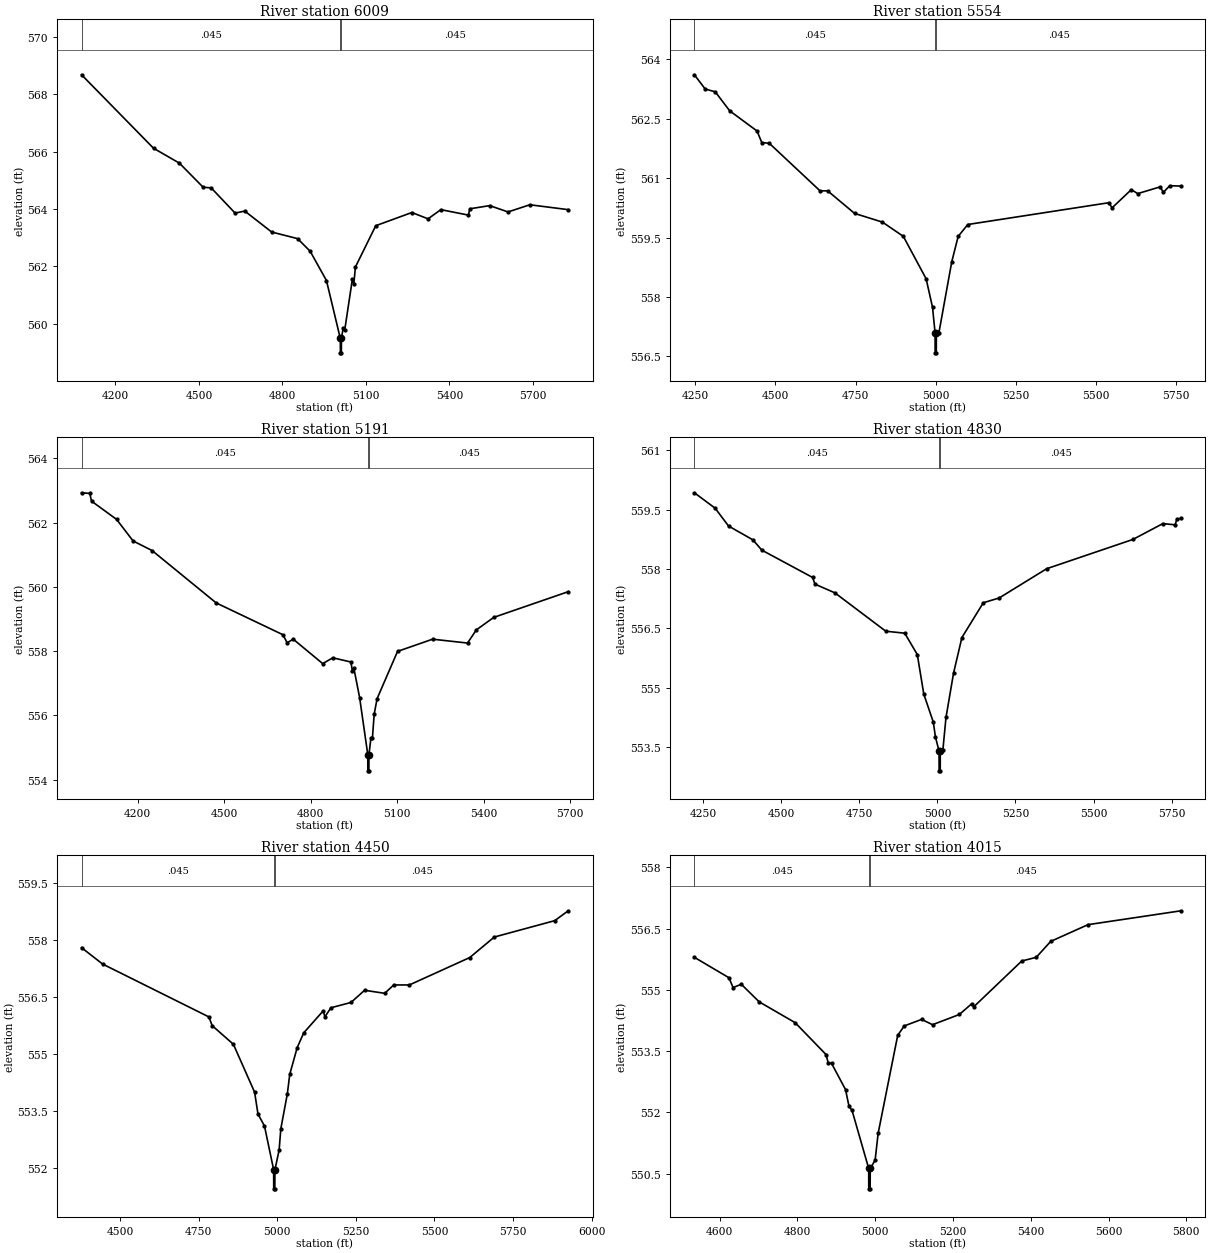
Type RM Length L Ch R = 1,6009,455,455,455
BEGIN DESCRIPTION:
XS7958
END DESCRIPTION:
XS GIS Cut Line= 3
      2292614.71     13769972.40      2291724.95     13769733.69
      2290932.86     13769972.40
#Sta/Elev= 30
  4078.3  568.68  4336.8  566.12  4429.9  565.60  4515.1  564.76  4543.9  564.74
  4629.9  563.86  4664.7  563.93  4761.3  563.20  4854.4  562.97  4899.6  562.53
  4958.1  561.51  5007.9  559.49  5008.2  558.99  5011.7  558.99  5011.9  559.49
  5018.3  559.86  5023.5  559.77  5051.3  561.56  5056.5  561.39  5062.1  561.98
  5135.2  563.42  5264.9  563.88  5323.2  563.66  5369.1  563.98  5468.1  563.79
  5473.3  564.01  5544.5  564.12  5610.5  563.90  5688.8  564.15  5826.8  563.98
#Mann=3,-1,0
  4078.3   0.045       0  5007.9   0.045       0  5011.9   0.045       0
Bank Sta=5007.9,5011.9
Exp/Cntr=0.3,0.1

Type RM Length L Ch R = 1,5554,363,363,363
BEGIN DESCRIPTION:
H21559
END DESCRIPTION:
XS GIS Cut Line= 3
      2292524.89     13769571.52      2291914.19     13769311.98
      2291059.65     13769311.98
#Sta/Elev= 30
  4247.3  563.61  4281.0  563.25  4312.4  563.18  4357.4  562.70  4442.8  562.19
  4457.4  561.90  4481.0  561.88  4639.2  560.68  4662.9  560.68  4747.0  560.11
  4833.9  559.89  4899.1  559.53  4970.1  558.46  4990.1  557.74  4998.1  557.09
  4998.3  556.59  5001.8  556.59  5002.1  557.09  5010.1  557.10  5050.1  558.89
  5070.1  559.53  5100.1  559.83  5540.1  560.38  5550.1  560.25  5610.1  560.71
  5630.1  560.61  5700.1  560.78  5710.1  560.64  5730.1  560.81  5765.4  560.80
#Mann=3,-1,0
  4247.3   0.045       0  4998.1   0.045       0  5002.1   0.045       0
Bank Sta=4998.1,5002.1
Exp/Cntr=0.3,0.1

Type RM Length L Ch R = 1,5191,361,361,361
BEGIN DESCRIPTION:
XS7957
END DESCRIPTION:
XS GIS Cut Line= 3
      2292668.95     13769419.01      2291941.96     13768930.74
      2291139.81     13769049.98
#Sta/Elev= 30
  4006.0  562.93  4034.5  562.91  4040.5  562.67  4127.5  562.10  4184.5  561.43
  4250.5  561.13  4472.5  559.50  4703.6  558.51  4718.5  558.26  4739.6  558.37
  4841.6  557.61  4876.9  557.79  4939.3  557.66  4944.6  557.39  4949.6  557.47
  4969.7  556.55  4998.0  554.77  4998.2  554.27  5001.7  554.27  5002.0  554.77
  5008.9  555.30  5013.9  555.28  5020.2  556.04  5030.3  556.52  5101.1  557.99
  5222.4  558.37  5343.7  558.25  5374.1  558.66  5434.7  559.05  5692.7  559.85
#Mann=3,-1,0
  4006.0   0.045       0  4998.0   0.045       0  5002.0   0.045       0
Bank Sta=4998,5002
Exp/Cntr=0.3,0.1

Type RM Length L Ch R = 1,4830,380,380,380
BEGIN DESCRIPTION:
H21558
END DESCRIPTION:
XS GIS Cut Line= 4
      2292513.39     13769060.07      2292181.35     13768666.97
      2291788.24     13768594.45      2291209.04     13768876.43
#Sta/Elev= 30
  4221.9  559.93  4288.3  559.54  4331.2  559.09  4409.2  558.74  4437.8  558.48
  4600.3  557.79  4608.1  557.62  4671.8  557.40  4834.8  556.43  4895.5  556.38
  4935.7  555.84  4956.5  554.84  4987.0  554.13  4993.7  553.76  5005.3  553.40
  5005.6  552.90  5009.1  552.90  5009.3  553.40  5017.5  553.42  5027.6  554.25
  5051.8  555.37  5078.5  556.27  5147.1  557.15  5197.8  557.27  5350.0  558.01
  5626.1  558.75  5721.9  559.15  5761.4  559.12  5767.0  559.27  5780.4  559.28
#Mann=3,-1,0
  4221.9   0.045       0  5005.3   0.045       0  5009.3   0.045       0
Bank Sta=5005.3,5009.3
Exp/Cntr=0.3,0.1

Type RM Length L Ch R = 1,4450,435,435,435
BEGIN DESCRIPTION:
XS7956
END DESCRIPTION:
XS GIS Cut Line= 4
      2292456.14     13768712.74      2292300.04     13768355.65
      2291920.26     13768247.14      2291323.44     13768724.60
#Sta/Elev= 30
  4376.8  557.79  4443.7  557.36  4782.0  555.97  4792.6  555.74  4860.0  555.25
  4927.6  553.99  4938.2  553.42  4959.0  553.10  4988.2  551.95  4988.4  551.45
  4991.9  551.45  4992.2  551.95  5005.6  552.47  5011.0  553.03  5031.8  553.95
  5039.4  554.46  5063.0  555.16  5083.8  555.55  5146.0  556.13  5151.2  555.97
  5170.3  556.21  5234.4  556.35  5277.6  556.67  5341.6  556.59  5370.4  556.81
  5420.1  556.81  5612.2  557.53  5690.6  558.07  5882.7  558.50  5925.8  558.76
#Mann=3,-1,0
  4376.8   0.045       0  4988.2   0.045       0  4992.2   0.045       0
Bank Sta=4988.2,4992.2
Exp/Cntr=0.3,0.1

Type RM Length L Ch R = 1,4015,592,592,592
BEGIN DESCRIPTION:
H21557
END DESCRIPTION:
XS GIS Cut Line= 4
      2292475.25     13768258.64      2292376.00     13767979.98
      2292063.04     13767823.50      2291540.16     13768128.83
#Sta/Elev= 30
  4535.3  555.80  4624.1  555.30  4634.7  555.06  4655.9  555.14  4701.8  554.71
  4794.3  554.20  4873.6  553.42  4879.2  553.22  4888.1  553.20  4923.9  552.56
  4932.8  552.15  4940.6  552.05  4983.4  550.63  4983.6  550.13  4987.1  550.13
  4987.4  550.63  4999.9  550.83  5007.7  551.49  5058.0  553.89  5074.8  554.12
  5119.5  554.28  5147.5  554.15  5216.5  554.40  5247.9  554.66  5253.7  554.59
  5376.9  555.71  5414.1  555.80  5451.3  556.19  5547.2  556.60  5786.5  556.94
#Mann=3,-1,0
  4535.3   0.045       0  4983.4   0.045       0  4987.4   0.045       0
Bank Sta=4983.4,4987.4
Exp/Cntr=0.3,0.1

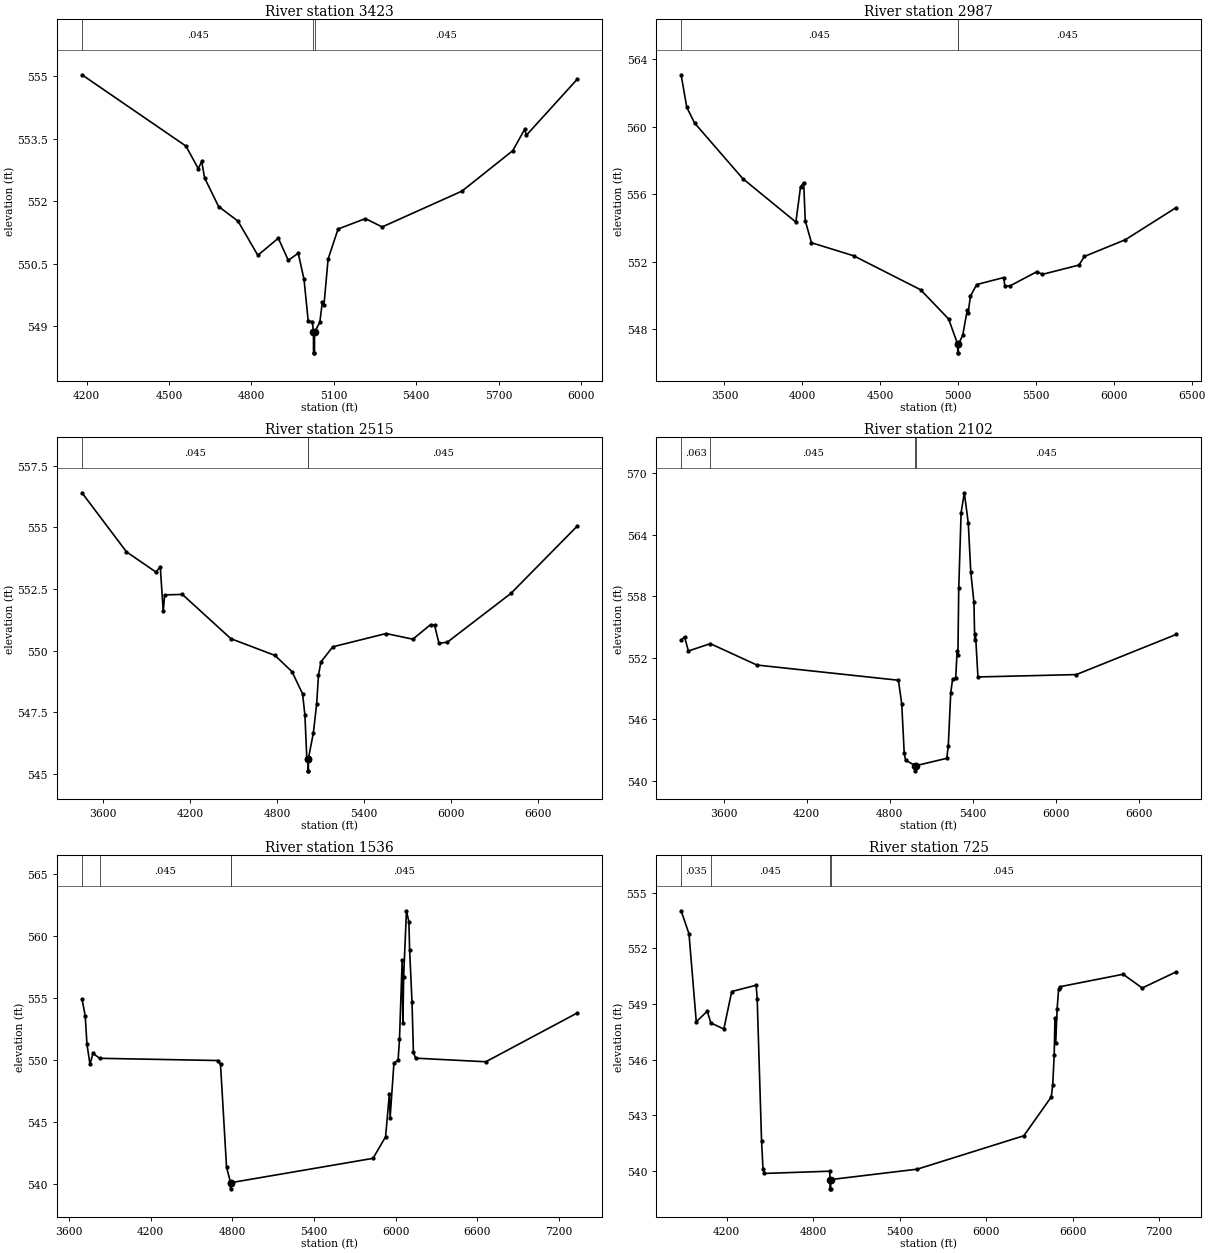
Type RM Length L Ch R = 1,3423,436,436,436
BEGIN DESCRIPTION:
H21556
END DESCRIPTION:
XS GIS Cut Line= 4
      2292597.37     13768071.61      2292463.78     13767434.21
      2292093.57     13767193.76      2291639.67     13767739.21
#Sta/Elev= 30
  4183.3  555.03  4561.7  553.32  4606.5  552.78  4619.2  552.95  4629.4  552.56
  4680.5  551.87  4751.2  551.52  4823.5  550.70  4898.0  551.11  4934.3  550.58
  4970.5  550.75  4991.6  550.12  5006.8  549.12  5021.9  549.11  5025.9  548.86
  5026.1  548.36  5029.6  548.36  5029.9  548.86  5049.0  549.09  5058.1  549.57
  5064.1  549.50  5079.2  550.61  5115.5  551.33  5215.0  551.58  5276.0  551.38
  5566.6  552.24  5751.5  553.21  5794.5  553.72  5801.0  553.58  5985.6  554.92
#Mann=3,-1,0
  4183.3   0.045       0  5025.9   0.045       0  5029.9   0.045       0
Bank Sta=5025.9,5029.9
Exp/Cntr=0.3,0.1

Type RM Length L Ch R = 1,2987,472,472,472
BEGIN DESCRIPTION:
H21564
END DESCRIPTION:
XS GIS Cut Line= 3
      2294101.26     13767016.67      2292101.26     13766933.33
      2291352.51     13767841.54
#Sta/Elev= 30
  3222.2  563.06  3258.5  561.14  3308.5  560.21  3618.2  556.92  3959.1  554.35
  3989.1  556.44  4009.1  556.69  4019.2  554.43  4059.2  553.13  4329.4  552.36
  4759.8  550.35  4939.9  548.62  4998.0  547.12  4998.3  546.62  5001.8  546.62
  5002.0  547.12  5030.0  547.65  5059.4  549.15  5064.4  548.96  5080.1  549.98
  5120.1  550.66  5293.1  551.07  5300.9  550.56  5336.1  550.59  5506.8  551.42
  5542.0  551.26  5776.5  551.81  5811.7  552.32  6074.9  553.31  6401.0  555.21
#Mann=3,-1,0
  3222.2   0.045       0  4998.0   0.045       0  5002.0   0.045       0
Bank Sta=4998,5002
Exp/Cntr=0.3,0.1

Type RM Length L Ch R = 1,2515,413,413,413
BEGIN DESCRIPTION:
H21563
END DESCRIPTION:
XS GIS Cut Line= 4
      2293837.39     13766204.16      2292365.15     13766447.22
      2291767.93     13766766.67      2291198.49     13767870.82
#Sta/Elev= 30
  3455.6  556.41  3762.1  554.01  3964.8  553.19  3995.2  553.40  4015.5  551.59
  4025.6  552.26  4147.2  552.28  4481.7  550.48  4785.8  549.80  4902.9  549.14
  4975.6  548.24  4991.8  547.37  5004.6  545.65  5011.8  545.61  5012.0  545.11
  5015.5  545.11  5015.8  545.61  5050.0  546.65  5072.7  547.83  5085.3  548.99
  5101.6  549.53  5183.6  550.15  5551.0  550.69  5735.7  550.46  5857.2  551.05
  5885.0  551.03  5915.7  550.29  5973.6  550.34  6411.2  552.32  6867.4  555.05
#Mann=3,-1,0
  3455.6   0.045       0  5011.8   0.045       0  5015.8   0.045       0
Bank Sta=5011.8,5015.8
Exp/Cntr=0.3,0.1

Type RM Length L Ch R = 1,2102,566,566,566
BEGIN DESCRIPTION:
H21562
END DESCRIPTION:
XS GIS Cut Line= 3
      2293677.63     13765704.17      2291844.32     13766252.78
      2291163.75     13767766.70
#Sta/Elev= 30
  3293.5  553.70  3318.1  554.05  3346.0  552.67  3504.3  553.38  3840.7  551.30
  4862.0  549.82  4885.8  547.52  4903.7  542.75  4913.7  542.04  4983.1  541.50
  4983.3  541.00  4987.1  541.50  5211.1  542.22  5221.8  543.43  5239.5  548.59
  5253.4  549.96  5275.4  550.03  5285.8  552.71  5291.3  552.32  5297.3  558.76
  5314.5  566.15  5337.6  568.07  5366.3  565.10  5384.0  560.39  5406.9  557.40
  5412.6  553.77  5418.1  554.36  5435.8  550.14  6145.7  550.37  6867.0  554.28
#Mann=4,-1,0
  3293.5   0.063       0  3504.3   0.045       0  4983.1   0.045       0
  4987.1   0.045       0
Bank Sta=4983.1,4987.1
Exp/Cntr=0.3,0.1

Type RM Length L Ch R = 1,1536,811,811,811
BEGIN DESCRIPTION:
H21561
END DESCRIPTION:
XS GIS Cut Line= 3
      2293108.22     13765148.60      2291490.15     13765898.61
      2291101.39     13767710.53
#Sta/Elev= 30
  3695.8  554.96  3719.4  553.60  3732.4  551.30  3754.5  549.69  3776.5  550.57
  3824.9  550.17  4697.3  549.99  4713.4  549.67  4757.5  541.39  4787.0  540.14
  4787.2  539.64  4791.0  540.14  5833.5  542.10  5925.6  543.84  5953.9  547.33
  5959.0  545.35  5986.9  549.77  6017.6  550.02  6027.8  551.69  6047.6  558.11
  6052.7  553.00  6058.5  556.74  6079.0  562.07  6097.0  561.17  6102.1  558.94
  6119.9  554.69  6130.1  550.65  6146.4  550.18  6662.0  549.89  7332.4  553.82
#Mann=4,-1,0
  3695.8   0.035       0  3824.9   0.045       0  4787.0   0.045       0
  4791.0   0.045       0
Bank Sta=4787,4791
Exp/Cntr=0.3,0.1

Type RM Length L Ch R = 1,725,0,0,0
BEGIN DESCRIPTION:
H21560
END DESCRIPTION:
XS GIS Cut Line= 4
      2292719.36     13764808.33      2291733.20     13764926.39
      2291399.87     13765870.83      2291135.98     13767287.53
#Sta/Elev= 30
  3884.0  554.02  3938.7  552.78  3989.1  548.04  4065.5  548.61  4090.1  547.98
  4180.5  547.65  4235.2  549.67  4404.9  550.01  4412.1  549.25  4442.3  541.60
  4452.4  540.11  4462.5  539.87  4914.9  539.99  4918.2  539.54  4918.4  539.04
  4921.9  539.04  4922.2  539.54  5522.8  540.10  6262.4  541.90  6452.6  543.99
  6462.8  544.65  6473.0  546.26  6478.4  548.26  6483.5  546.87  6493.3  548.73
  6503.5  549.78  6513.6  549.93  6951.0  550.60  7083.9  549.86  7319.8  550.73
#Mann=4,-1,0
  3884.0   0.035       0  4090.1   0.045       0  4918.2   0.045       0
  4922.2   0.045       0
Bank Sta=4918.2,4922.2
Exp/Cntr=0.3,0.1

Chan Stop Cuts=-1