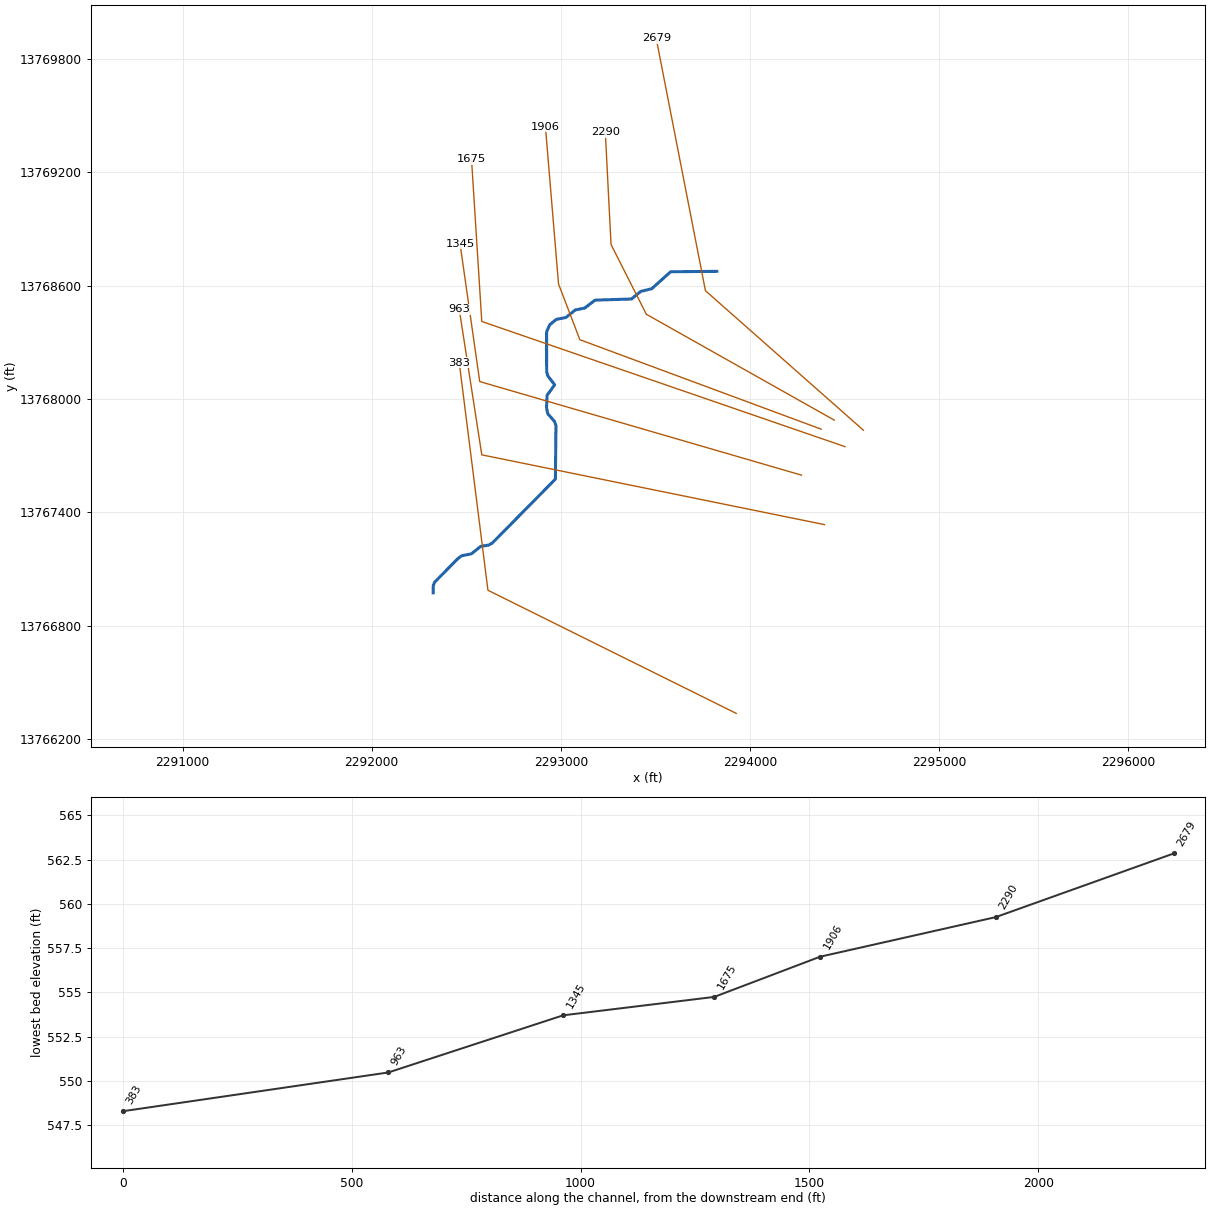
--- WALNUT TRIBUTARY 2.prj (project) ---

Proj Title=WALNUT TRIBUTARY 2 Base Level Engineering
Current Plan=p01
Default Exp/Contr=0.3,0.1
English Units
Geom File=g01
Flow File=f01
Plan File=p01
BEGIN DESCRIPTION:
WALNUT TRIBUTARY 2
END DESCRIPTION:

--- WALNUT TRIBUTARY 2.p01 (plan) ---

Plan Title=Multiple Run
Short Identifier=Multiple
Geom File=g01
Flow File=f01
Subcritical Flow
K Sum by GR= 0
Std Step Tol= 0.01
Critical Tol= 0.01
Num of Std Step Trials= 20
Max Error Tol= 0.3
Flow Tol Ratio= 0.001
Split Flow NTrial= 30
Split Flow Tol= 0.02
Split Flow Ratio= 0.02
Log Output Level= 0
Friction Slope Method= 1
Unsteady Friction Slope Method= 2
Unsteady Bridges Friction Slope Method= 1
Parabolic Critical Depth
Global Vel Dist=  1 , 1 , 1
Global Log Level= 0
CheckData=True
Encroach Param= -1, 0, 0, 0
BEGIN DESCRIPTION:
Multiple Run
END DESCRIPTION:

--- WALNUT TRIBUTARY 2.f01 (steady flow) ---

Flow Title=Multiple
Number of Profiles=7
Profile Names=10-year,25-year,50-year,1pct_min,100-year,1pct_plu,500-year
River Rch & RM= WALNUT TRIBUTARY,Reach-1,2679
     272     415     537     338     674    1346    1050
Boundary for River Rch & Prof#=WALNUT TRIBUTARY,Reach-1,1
Up Type=0
Dn Type=3
Dn Slope=0.005
Boundary for River Rch & Prof#=WALNUT TRIBUTARY,Reach-1,2
Up Type=0
Dn Type=3
Dn Slope=0.005
Boundary for River Rch & Prof#=WALNUT TRIBUTARY,Reach-1,3
Up Type=0
Dn Type=3
Dn Slope=0.005
Boundary for River Rch & Prof#=WALNUT TRIBUTARY,Reach-1,4
Up Type=0
Dn Type=3
Dn Slope=0.005
Boundary for River Rch & Prof#=WALNUT TRIBUTARY,Reach-1,5
Up Type=0
Dn Type=3
Dn Slope=0.005
Boundary for River Rch & Prof#=WALNUT TRIBUTARY,Reach-1,6
Up Type=0
Dn Type=3
Dn Slope=0.005
Boundary for River Rch & Prof#=WALNUT TRIBUTARY,Reach-1,7
Up Type=0
Dn Type=3
Dn Slope=0.005

--- WALNUT TRIBUTARY 2.g01 (geometry) ---

Geom Title=Existing Conditions

River Reach=WALNUT TRIBUTARY,Reach-1
Reach XY= 30
      2293825.00     13768675.00      2293580.85     13768672.94
      2293481.05     13768583.16      2293422.83     13768568.86
      2293373.45     13768528.75      2293180.93     13768522.76
      2293127.18     13768481.12      2293076.72     13768470.84
      2293027.16     13768431.12      2292976.39     13768421.15
      2292941.27     13768392.14      2292924.91     13768355.12
      2292925.18     13768144.98      2292931.02     13768122.55
      2292967.44     13768075.00      2292927.36     13768019.11
      2292924.42     13767954.96      2292930.69     13767922.69
      2292966.85     13767881.06      2292974.48     13767859.78
      2292971.46     13767576.46      2292638.21     13767238.62
      2292618.96     13767227.50      2292576.74     13767220.81
      2292527.19     13767181.10      2292476.63     13767171.05
      2292454.91     13767155.22      2292332.76     13767031.21
      2292325.59     13767013.16      2292325.00     13766975.00

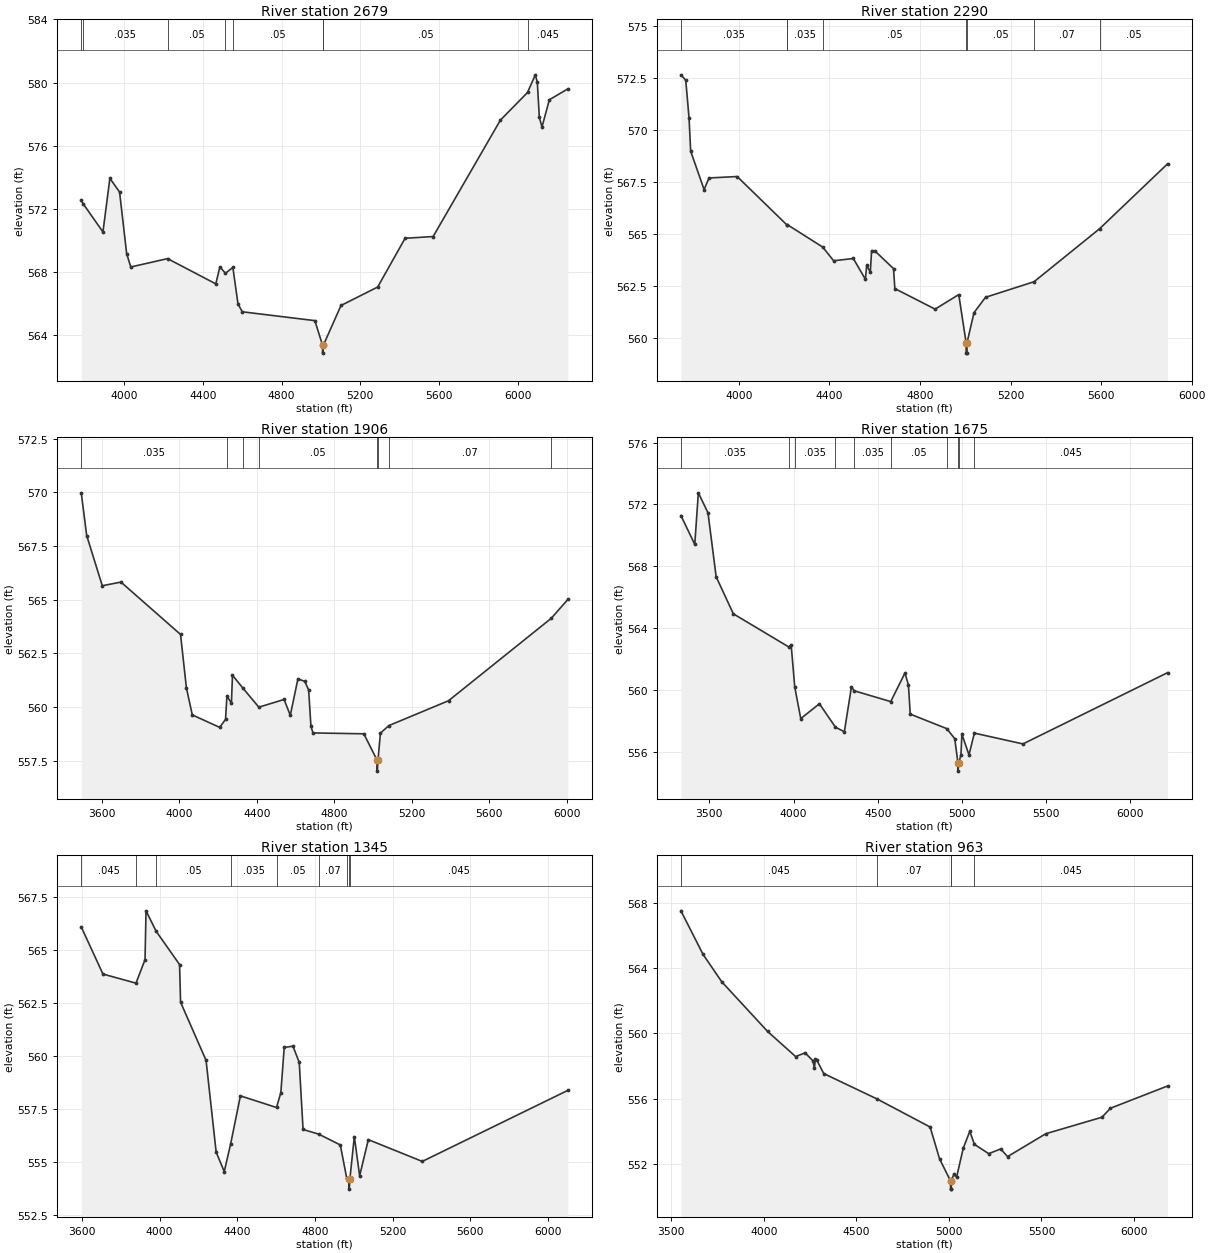
Type RM Length L Ch R = 1,2679,389,389,389
BEGIN DESCRIPTION:
XS7962
END DESCRIPTION:
XS GIS Cut Line= 3
      2294600.41     13767834.79      2293764.88     13768572.66
      2293504.47     13769907.29
#Sta/Elev= 30
  3781.0  572.54  3791.2  572.31  3891.4  570.53  3926.6  573.93  3975.9  573.06
  4011.9  569.16  4032.8  568.31  4220.0  568.84  4465.3  567.24  4486.2  568.32
  4514.1  567.91  4552.1  568.28  4578.2  565.96  4600.0  565.47  4968.9  564.91
  5008.2  563.35  5008.4  562.85  5012.2  563.35  5101.9  565.87  5288.5  567.04
  5427.9  570.13  5570.5  570.24  5912.6  577.62  6050.4  579.37  6090.1  580.49
  6100.3  580.02  6110.5  577.80  6124.0  577.18  6161.5  578.91  6255.5  579.60
#Mann=8,-1,0
  3781.0    0.05       0  3791.2   0.035       0  4220.0    0.05       0
  4514.1   0.035       0  4552.1    0.05       0  5008.2    0.05       0
  5012.2    0.05       0  6050.4   0.045       0
Bank Sta=5008.2,5012.2
Exp/Cntr=0.3,0.1

Type RM Length L Ch R = 1,2290,384,384,384
BEGIN DESCRIPTION:
H21567
END DESCRIPTION:
XS GIS Cut Line= 4
      2294446.24     13767888.20      2293452.35     13768448.08
      2293265.72     13768817.00      2293235.38     13769410.84
#Sta/Elev= 30
  3744.6  572.66  3765.9  572.40  3780.5  570.57  3787.6  568.98  3846.9  567.13
  3868.5  567.69  3992.8  567.76  4212.4  565.43  4214.5  565.44  4370.7  564.36
  4419.0  563.70  4505.7  563.81  4559.2  562.81  4565.0  563.48  4580.9  563.15
  4586.6  564.19  4602.6  564.16  4683.5  563.32  4689.2  562.36  4867.0  561.37
  4971.5  562.07  5004.0  559.75  5004.3  559.25  5007.8  559.25  5008.0  559.75
  5038.8  561.20  5089.6  561.94  5303.9  562.69  5593.0  565.24  5893.4  568.37
#Mann=8,-1,0
  3744.6   0.035       0  4212.4    0.05       0  4214.5   0.035       0
  4370.7    0.05       0  5004.0    0.05       0  5008.0    0.05       0
  5303.9    0.07       0  5593.0    0.05       0
Bank Sta=5004,5008
Exp/Cntr=0.3,0.1

Type RM Length L Ch R = 1,1906,231,231,231
BEGIN DESCRIPTION:
H21566
END DESCRIPTION:
XS GIS Cut Line= 4
      2294376.85     13767840.43      2293100.79     13768313.53
      2292987.94     13768608.67      2292918.59     13769440.97
#Sta/Elev= 30
  3494.0  569.98  3522.1  567.99  3602.6  565.65  3699.0  565.82  4006.6  563.38
  4036.9  560.89  4067.3  559.63  4208.6  559.05  4238.9  559.42  4246.2  560.52
  4269.3  560.17  4274.7  561.48  4328.5  560.88  4410.8  559.99  4541.2  560.35
  4573.2  559.61  4612.6  561.31  4648.3  561.19  4668.0  560.79  4679.8  559.10
  4690.5  558.79  4952.9  558.75  5021.8  557.51  5022.1  557.01  5025.8  557.51
  5038.5  558.78  5081.6  559.13  5390.0  560.29  5920.2  564.13  6006.1  565.01
#Mann=8,-1,0
  3494.0   0.035       0  4246.2    0.05       0  4328.5   0.035       0
  4410.8    0.05       0  5021.8    0.05       0  5025.8    0.05       0
  5081.6    0.07       0  5920.2    0.05       0
Bank Sta=5021.8,5025.8
Exp/Cntr=0.3,0.1

Type RM Length L Ch R = 1,1675,330,330,330
BEGIN DESCRIPTION:
XS7961
END DESCRIPTION:
XS GIS Cut Line= 3
      2294502.76     13767748.00      2292582.16     13768409.90
      2292527.90     13769267.13
#Sta/Elev= 30
  3331.0  571.28  3413.2  569.41  3434.4  572.75  3491.6  571.46  3540.2  567.32
  3642.3  564.92  3972.6  562.77  3985.7  562.92  4007.1  560.18  4042.8  558.14
  4153.6  559.10  4249.1  557.58  4301.7  557.29  4344.0  560.20  4360.0  559.94
  4577.2  559.24  4661.7  561.09  4682.4  560.31  4693.1  558.43  4910.1  557.49
  4957.5  556.84  4976.7  555.24  4976.9  554.74  4980.7  555.24  4994.5  555.81
  4999.8  557.14  5042.1  555.79  5073.9  557.20  5362.5  556.50  6221.4  561.11
#Mann=10,-1,0
  3331.0   0.035       0  3972.6   0.045       0  4007.1   0.035       0
  4249.1    0.05       0  4360.0   0.035       0  4577.2    0.05       0
  4910.1    0.07       0  4976.7    0.05       0  4980.7    0.07       0
  5073.9   0.045       0
Bank Sta=4976.7,4980.7
Exp/Cntr=0.3,0.1

Type RM Length L Ch R = 1,1345,382,382,382
BEGIN DESCRIPTION:
H21565
END DESCRIPTION:
XS GIS Cut Line= 3
      2294272.68     13767597.38      2292571.28     13768092.17
      2292467.20     13768820.68
#Sta/Elev= 30
  3595.8  566.10  3707.7  563.87  3877.9  563.44  3924.5  564.55  3929.7  566.86
  3981.4  565.90  4102.5  564.32  4107.7  562.54  4239.1  559.79  4291.1  555.45
  4332.8  554.53  4365.8  555.84  4416.1  558.11  4602.1  557.56  4624.4  558.26
  4641.9  560.40  4686.9  560.46  4719.3  559.69  4739.0  556.52  4819.7  556.30
  4930.9  555.79  4964.0  554.22  4976.5  554.20  4976.7  553.70  4980.5  554.20
  5003.2  556.18  5030.6  554.33  5075.4  556.04  5353.4  555.01  6103.6  558.37
#Mann=9,-1,0
  3595.8   0.045       0  3877.9   0.035       0  3981.4    0.05       0
  4365.8   0.035       0  4602.1    0.05       0  4819.7    0.07       0
  4964.0   0.045       0  4976.5   0.045       0  4980.5   0.045       0
Bank Sta=4976.5,4980.5
Exp/Cntr=0.3,0.1

Type RM Length L Ch R = 1,963,580,580,580
BEGIN DESCRIPTION:
XS7960
END DESCRIPTION:
XS GIS Cut Line= 3
      2294394.24     13767335.68      2292582.16     13767704.61
      2292462.80     13768474.96
#Sta/Elev= 30
  3552.1  567.50  3671.3  564.84  3772.5  563.16  4020.3  560.12  4172.0  558.58
  4222.6  558.81  4265.7  558.32  4273.1  557.88  4278.2  558.41  4286.1  558.37
  4323.7  557.54  4611.2  555.99  4898.4  554.27  4949.4  552.32  5008.7  550.97
  5008.9  550.47  5012.4  550.47  5012.7  550.97  5026.7  551.38  5041.3  551.20
  5077.2  552.97  5112.7  554.01  5137.6  553.21  5214.8  552.64  5279.5  552.93
  5316.8  552.46  5523.2  553.86  5826.8  554.87  5872.5  555.42  6180.9  556.78
#Mann=5,-1,0
  3552.1   0.045       0  4611.2    0.07       0  5008.7    0.05       0
  5012.7    0.07       0  5137.6   0.045       0
Bank Sta=5008.7,5012.7
Exp/Cntr=0.3,0.1

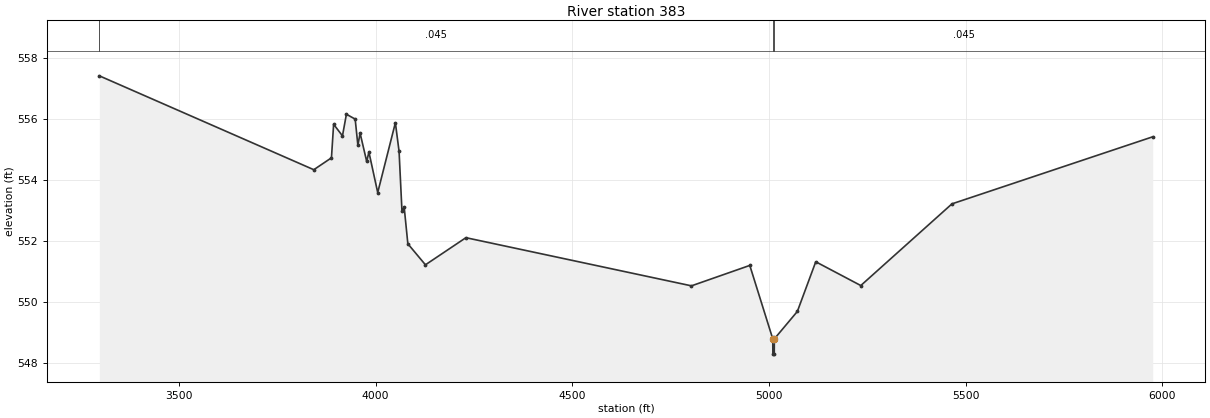
Type RM Length L Ch R = 1,383,0,0,0
BEGIN DESCRIPTION:
XS7959
END DESCRIPTION:
XS GIS Cut Line= 3
      2293927.69     13766337.40      2292614.71     13766988.46
      2292462.99     13768191.40
#Sta/Elev= 30
  3297.9  557.41  3843.1  554.33  3888.0  554.72  3893.5  555.82  3916.0  555.44
  3926.0  556.15  3948.3  555.99  3955.2  555.13  3960.8  555.53  3977.6  554.60
  3983.2  554.91  4005.6  553.58  4050.5  555.87  4059.9  554.93  4067.3  552.96
  4072.9  553.10  4082.2  551.90  4126.9  551.21  4229.8  552.10  4803.2  550.52
  4951.5  551.19  5009.9  548.78  5010.2  548.28  5013.7  548.28  5013.9  548.78
  5072.4  549.68  5119.2  551.31  5233.7  550.53  5465.5  553.21  5975.9  555.41
#Mann=3,-1,0
  3297.9   0.045       0  5009.9   0.045       0  5013.9   0.045       0
Bank Sta=5009.9,5013.9
Exp/Cntr=0.3,0.1

Chan Stop Cuts=-1