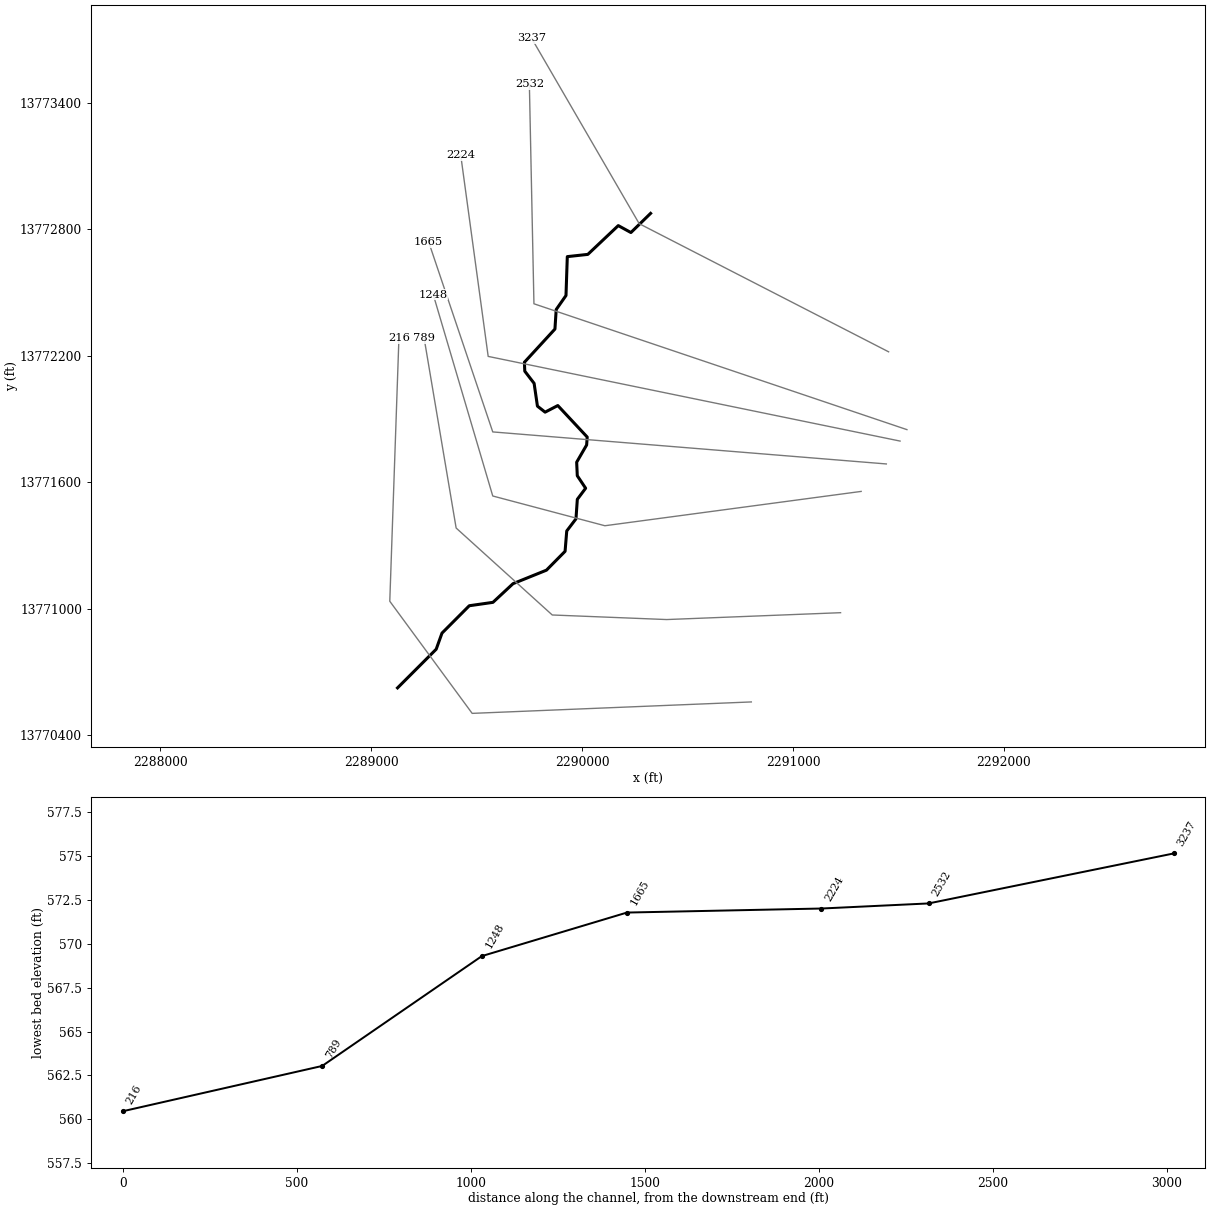
--- WALNUT TRIBUTARY 4.prj (project) ---

Proj Title=WALNUT TRIBUTARY 4 Base Level Engineering
Current Plan=p01
Default Exp/Contr=0.3,0.1
English Units
Geom File=g01
Flow File=f01
Plan File=p01
BEGIN DESCRIPTION:
WALNUT TRIBUTARY 4
END DESCRIPTION:

--- WALNUT TRIBUTARY 4.p01 (plan) ---

Plan Title=Multiple Run
Short Identifier=Multiple
Geom File=g01
Flow File=f01
Subcritical Flow
K Sum by GR= 0
Std Step Tol= 0.01
Critical Tol= 0.01
Num of Std Step Trials= 20
Max Error Tol= 0.3
Flow Tol Ratio= 0.001
Split Flow NTrial= 30
Split Flow Tol= 0.02
Split Flow Ratio= 0.02
Log Output Level= 0
Friction Slope Method= 1
Unsteady Friction Slope Method= 2
Unsteady Bridges Friction Slope Method= 1
Parabolic Critical Depth
Global Vel Dist=  1 , 1 , 1
Global Log Level= 0
CheckData=True
Encroach Param= -1, 0, 0, 0
BEGIN DESCRIPTION:
Multiple Run
END DESCRIPTION:

--- WALNUT TRIBUTARY 4.f01 (steady flow) ---

Flow Title=Multiple
Number of Profiles=7
Profile Names=10-year,25-year,50-year,1pct_min,100-year,1pct_plu,500-year
River Rch & RM= WALNUT TRIBUTARY,Reach-1,3237
     179     265     336     207     413     823     616
Boundary for River Rch & Prof#=WALNUT TRIBUTARY,Reach-1,1
Up Type=0
Dn Type=3
Dn Slope=0.005
Boundary for River Rch & Prof#=WALNUT TRIBUTARY,Reach-1,2
Up Type=0
Dn Type=3
Dn Slope=0.005
Boundary for River Rch & Prof#=WALNUT TRIBUTARY,Reach-1,3
Up Type=0
Dn Type=3
Dn Slope=0.005
Boundary for River Rch & Prof#=WALNUT TRIBUTARY,Reach-1,4
Up Type=0
Dn Type=3
Dn Slope=0.005
Boundary for River Rch & Prof#=WALNUT TRIBUTARY,Reach-1,5
Up Type=0
Dn Type=3
Dn Slope=0.005
Boundary for River Rch & Prof#=WALNUT TRIBUTARY,Reach-1,6
Up Type=0
Dn Type=3
Dn Slope=0.005
Boundary for River Rch & Prof#=WALNUT TRIBUTARY,Reach-1,7
Up Type=0
Dn Type=3
Dn Slope=0.005

--- WALNUT TRIBUTARY 4.g01 (geometry) ---

Geom Title=Existing Conditions

River Reach=WALNUT TRIBUTARY,Reach-1
Reach XY= 30
      2290325.00     13772875.00      2290231.67     13772784.17
      2290171.67     13772817.01      2290027.36     13772680.55
      2289930.03     13772669.92      2289923.78     13772485.51
      2289877.36     13772419.02      2289871.39     13772326.50
      2289726.62     13772168.97      2289728.34     13772126.75
      2289772.62     13772069.03      2289788.40     13771960.91
      2289824.76     13771932.46      2289884.99     13771963.75
      2290024.40     13771814.38      2290021.66     13771776.75
      2289974.43     13771695.05      2289977.36     13771630.89
      2290016.92     13771571.70      2289977.55     13771519.11
      2289971.15     13771426.60      2289927.36     13771369.02
      2289919.48     13771272.56      2289831.07     13771183.13
      2289672.71     13771119.15      2289577.42     13771030.54
      2289465.21     13771014.48      2289335.78     13770884.68
      2289308.35     13770808.33      2289125.00     13770625.00

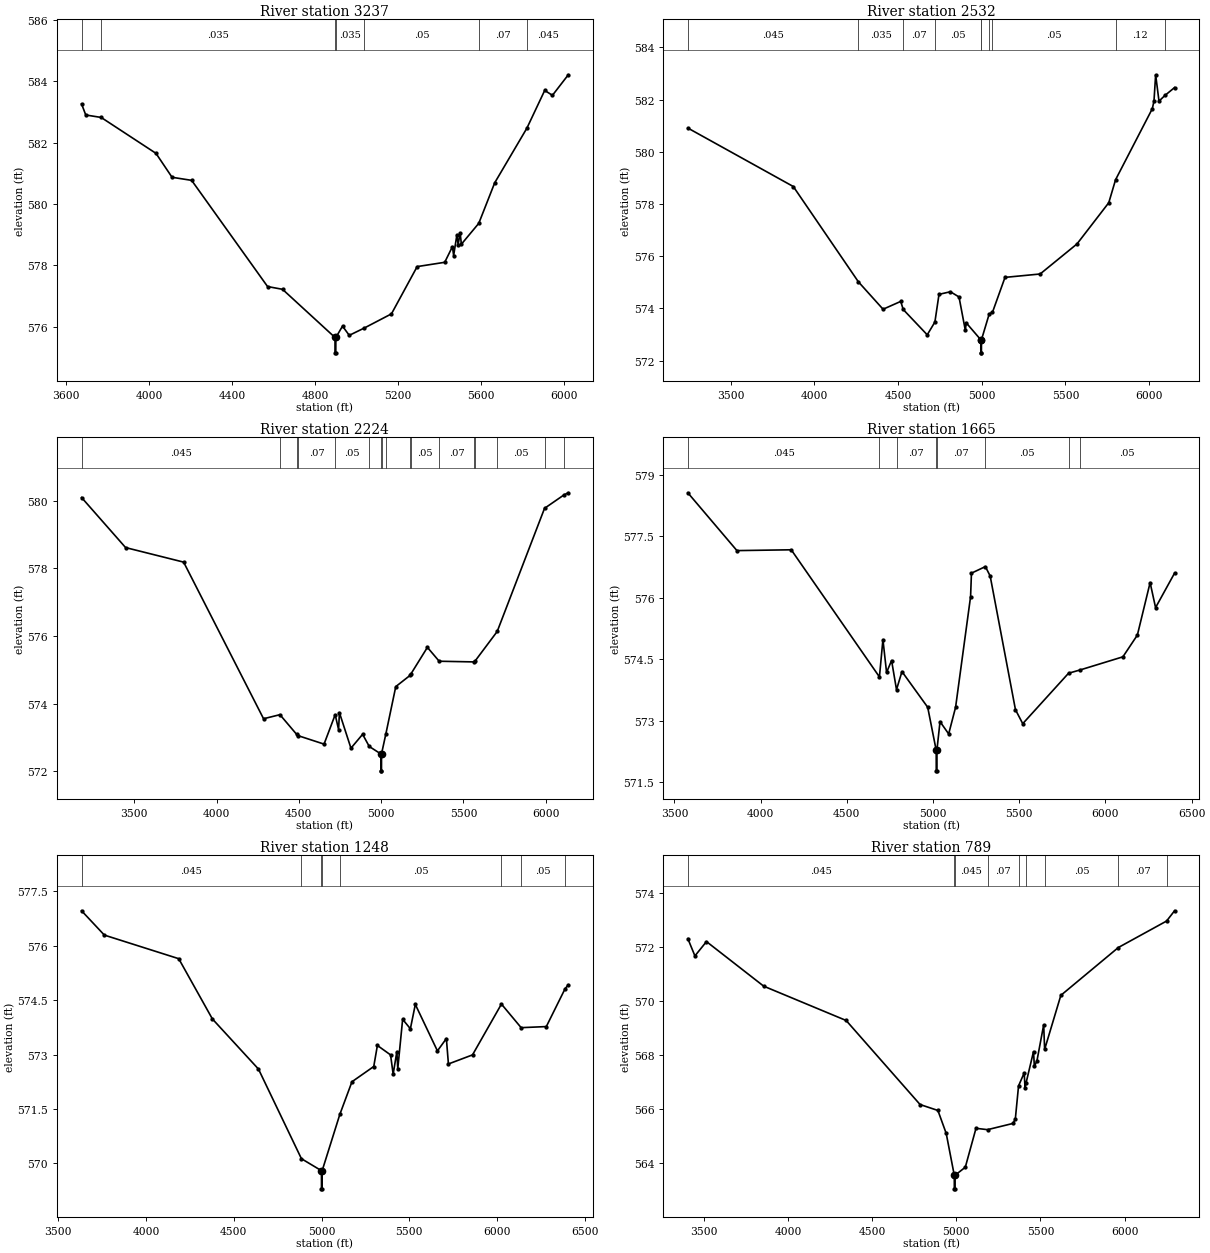
Type RM Length L Ch R = 1,3237,705,705,705
BEGIN DESCRIPTION:
WALNUT TRIBUTARY 4 2.0
END DESCRIPTION:
XS GIS Cut Line= 3
      2291453.65     13772218.51      2290270.96     13772826.14
      2289760.98     13773705.04
#Sta/Elev= 30
  3674.7  583.26  3694.9  582.90  3769.1  582.82  4033.3  581.65  4110.8  580.87
  4205.2  580.77  4571.1  577.31  4643.2  577.22  4896.2  575.65  4896.4  575.15
  4899.9  575.15  4900.2  575.65  4932.4  576.02  4964.8  575.72  5037.7  575.96
  5168.2  576.42  5292.1  577.96  5424.9  578.10  5462.1  578.61  5467.9  578.32
  5483.7  579.00  5489.4  578.68  5499.4  579.05  5505.2  578.69  5589.1  579.37
  5665.8  580.69  5820.9  582.47  5906.8  583.70  5944.0  583.54  6020.5  584.21
#Mann=7,-1,0
  3674.7   0.045       0  3769.1   0.035       0  4896.2   0.035       0
  4900.2   0.035       0  5037.7    0.05       0  5589.1    0.07       0
  5820.9   0.045       0
Bank Sta=4896.2,4900.2
Exp/Cntr=0.3,0.1

Type RM Length L Ch R = 1,2532,308,308,308
BEGIN DESCRIPTION:
WALNUT TRIBUTARY 4 1.0
END DESCRIPTION:
XS GIS Cut Line= 3
      2291540.48     13771849.58      2289771.83     13772446.36
      2289750.12     13773488.01
#Sta/Elev= 30
  3243.2  580.91  3873.5  578.67  4262.4  575.02  4409.9  573.97  4515.5  574.27
  4530.3  573.96  4673.8  572.99  4719.6  573.48  4744.1  574.54  4812.3  574.64
  4863.7  574.44  4901.5  573.16  4906.7  573.45  4993.9  572.80  4994.1  572.30
  4997.6  572.30  4997.9  572.80  5044.2  573.79  5063.5  573.85  5138.5  575.19
  5348.5  575.32  5568.6  576.47  5758.6  578.05  5799.2  578.93  6018.7  581.65
  6028.7  581.94  6038.7  582.95  6058.7  581.94  6094.4  582.16  6151.7  582.46
#Mann=10,-1,0
  3243.2   0.045       0  4262.4   0.035       0  4530.3    0.07       0
  4719.6    0.05       0  4993.9    0.05       0  4997.9    0.05       0
  5044.2    0.07       0  5063.5    0.05       0  5799.2    0.12       0
  6094.4   0.045       0
Bank Sta=4993.9,4997.9
Exp/Cntr=0.3,0.1

Type RM Length L Ch R = 1,2224,559,559,559
BEGIN DESCRIPTION:
XS7951
END DESCRIPTION:
XS GIS Cut Line= 3
      2291507.97     13771795.31      2289554.81     13772196.80
      2289424.71     13773150.88
#Sta/Elev= 30
  3180.0  580.09  3447.5  578.61  3800.0  578.18  4285.6  573.55  4385.1  573.67
  4486.3  573.09  4495.4  573.05  4653.1  572.80  4720.7  573.67  4741.4  573.23
  4746.5  573.73  4816.5  572.68  4887.4  573.09  4927.7  572.73  4998.2  572.51
  4998.5  572.01  5002.0  572.01  5002.2  572.51  5028.5  573.10  5088.8  574.50
  5175.2  574.83  5181.5  574.88  5280.9  575.66  5352.6  575.25  5565.1  575.23
  5569.6  575.25  5705.0  576.13  5992.5  579.77  6111.6  580.17  6136.9  580.23
#Mann=17,-1,0
  3180.0   0.045       0  4385.1    0.07       0  4486.3    0.05       0
  4495.4    0.07       0  4720.7    0.05       0  4927.7    0.07       0
  4998.2    0.05       0  5002.2    0.07       0  5028.5    0.05       0
  5175.2    0.07       0  5181.5    0.05       0  5352.6    0.07       0
  5565.1    0.05       0  5569.6    0.07       0  5705.0    0.05       0
  5992.5    0.07       0  6111.6    0.12       0
Bank Sta=4998.2,5002.2
Exp/Cntr=0.3,0.1

Type RM Length L Ch R = 1,1665,417,417,417
BEGIN DESCRIPTION:
XS7950
END DESCRIPTION:
XS GIS Cut Line= 3
      2291442.87     13771686.81      2289576.51     13771838.72
      2289272.69     13772739.33
#Sta/Elev= 30
  3577.9  578.56  3862.7  577.15  4177.7  577.17  4689.2  574.07  4709.5  574.98
  4730.6  574.18  4759.7  574.47  4788.2  573.76  4819.9  574.20  4969.2  573.33
  5018.5  572.28  5018.8  571.78  5022.3  571.78  5022.5  572.28  5040.6  572.98
  5090.8  572.68  5130.9  573.33  5217.9  576.03  5222.9  576.60  5303.7  576.76
  5331.5  576.53  5478.2  573.27  5520.4  572.93  5786.1  574.16  5853.2  574.24
  6101.3  574.56  6185.2  575.09  6259.1  576.37  6290.8  575.76  6400.9  576.60
#Mann=8,-1,0
  3577.9   0.045       0  4689.2    0.05       0  4788.2    0.07       0
  5018.5    0.05       0  5022.5    0.07       0  5303.7    0.05       0
  5786.1    0.07       0  5853.2    0.05       0
Bank Sta=5018.5,5022.5
Exp/Cntr=0.3,0.1

Type RM Length L Ch R = 1,1248,459,459,459
BEGIN DESCRIPTION:
XS7949
END DESCRIPTION:
XS GIS Cut Line= 4
      2291323.43     13771556.60      2290108.20     13771393.84
      2289576.51     13771534.90      2289294.40     13772489.74
#Sta/Elev= 30
  3633.3  576.96  3763.1  576.29  4186.6  575.64  4378.3  573.98  4640.6  572.60
  4885.3  570.13  4999.4  569.80  4999.6  569.30  5003.1  569.30  5003.4  569.80
  5104.0  571.35  5173.1  572.25  5297.2  572.67  5317.9  573.25  5392.9  572.99
  5407.7  572.46  5428.8  573.08  5434.0  572.61  5461.7  573.97  5505.8  573.71
  5533.9  574.38  5659.8  573.10  5710.8  573.44  5722.4  572.74  5859.6  572.99
  6024.3  574.39  6136.5  573.74  6279.9  573.77  6386.5  574.81  6405.1  574.92
#Mann=8,-1,0
  3633.3   0.045       0  4885.3    0.07       0  4999.4    0.05       0
  5003.4    0.07       0  5104.0    0.05       0  6024.3    0.07       0
  6136.5    0.05       0  6386.5   0.035       0
Bank Sta=4999.4,5003.4
Exp/Cntr=0.3,0.1

Type RM Length L Ch R = 1,789,573,573,573
BEGIN DESCRIPTION:
XS7948
END DESCRIPTION:
XS GIS Cut Line= 5
      2291225.81     13770981.52      2290401.17     13770948.97
      2289858.63     13770970.67      2289402.90     13771382.99
      2289251.30     13772281.77
#Sta/Elev= 30
  3403.2  572.30  3445.4  571.66  3514.1  572.19  3854.4  570.54  4344.7  569.27
  4784.2  566.16  4890.3  565.94  4939.7  565.09  4987.7  563.54  4988.0  563.04
  4991.5  563.04  4991.7  563.54  5053.2  563.84  5116.8  565.28  5185.5  565.23
  5336.4  565.46  5350.6  565.62  5369.8  566.85  5403.4  567.33  5408.4  566.78
  5414.9  566.97  5458.8  568.12  5463.9  567.57  5479.3  567.78  5519.3  569.11
  5524.9  568.20  5621.3  570.20  5963.1  571.97  6250.0  572.95  6297.5  573.33
#Mann=9,-1,0
  3403.2   0.045       0  4987.7   0.045       0  4991.7   0.045       0
  5185.5    0.07       0  5369.8    0.05       0  5414.9    0.07       0
  5524.9    0.05       0  5963.1    0.07       0  6250.0   0.035       0
Bank Sta=4987.7,4991.7
Exp/Cntr=0.3,0.1

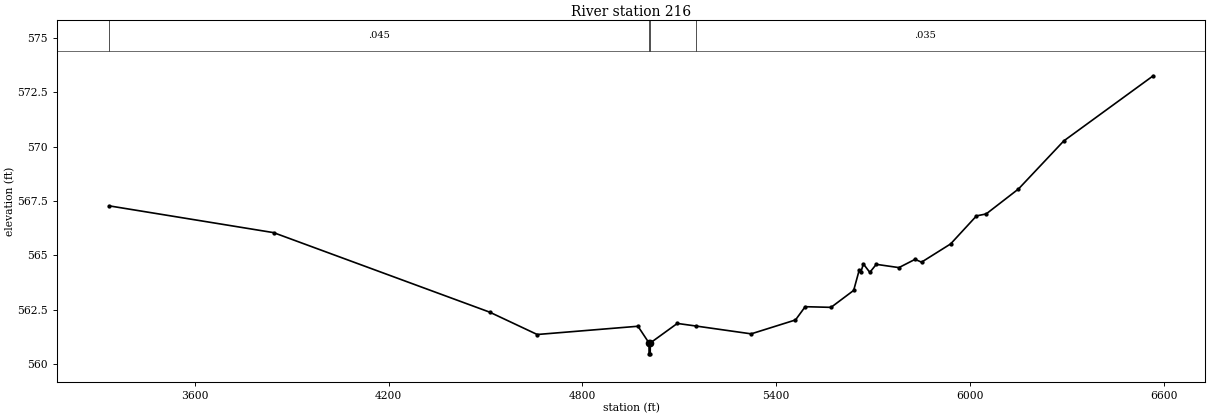
Type RM Length L Ch R = 1,216,0,0,0
BEGIN DESCRIPTION:
XS7947
END DESCRIPTION:
XS GIS Cut Line= 4
      2290802.67     13770558.34      2289478.86     13770504.09
      2289088.23     13771035.77      2289131.57     13772281.84
#Sta/Elev= 30
  3335.7  567.27  3843.8  566.04  4512.8  562.38  4660.1  561.35  4972.0  561.73
  5006.2  560.96  5006.4  560.46  5009.9  560.46  5010.2  560.96  5093.8  561.86
  5151.8  561.74  5322.5  561.38  5459.7  562.02  5489.7  562.63  5569.8  562.60
  5639.8  563.38  5656.9  564.31  5661.9  564.21  5669.8  564.60  5689.8  564.21
  5709.8  564.58  5779.9  564.43  5829.9  564.81  5849.9  564.68  5940.0  565.52
  6020.0  566.81  6050.0  566.90  6150.1  568.05  6290.2  570.26  6567.2  573.26
#Mann=4,-1,0
  3335.7   0.045       0  5006.2   0.045       0  5010.2   0.045       0
  5151.8   0.035       0
Bank Sta=5006.2,5010.2
Exp/Cntr=0.3,0.1

Chan Stop Cuts=-1