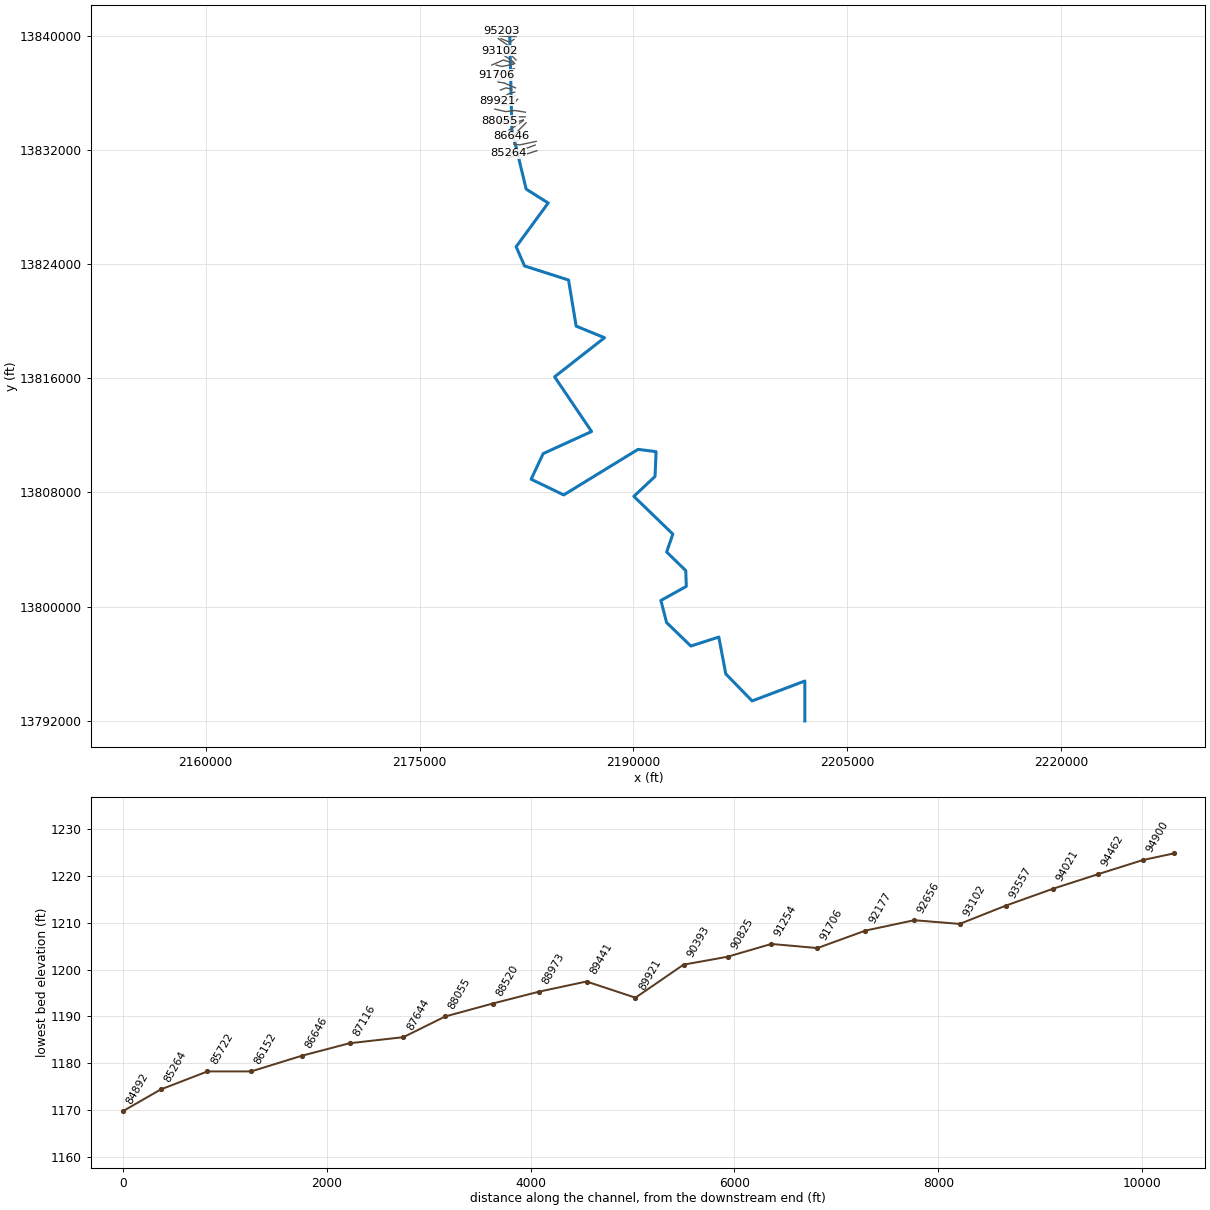
--- West Fork Dry Comal Creek.prj (project) ---

Proj Title=West Fork Dry Comal Creek
Current Plan=p01
Default Exp/Contr=0.3,0.1
English Units
Geom File=g01
Flow File=f01
Plan File=p01
Y Axis Title=Elevation
X Axis Title(PF)=Main Channel Distance
X Axis Title(XS)=Station
BEGIN DESCRIPTION:
West Fork
END DESCRIPTION:
DSS Export Rating Curves= 0
DSS Export Rating Curve Sorted= 0
DSS Export Volume Flow Curves= 0
DXF OffsetX= 0
DXF OffsetY= 0
DXF ScaleX= 1
DXF ScaleY= 10

--- West Fork Dry Comal Creek.p01 (plan) ---

Plan Title=Multiple Run
Program Version=4.10
Short Identifier=Multiple
Geom File=g01
Flow File=f01
Subcritical Flow
K Sum by GR= 0
Std Step Tol= 0.01
Critical Tol= 0.01
Num of Std Step Trials= 20
Max Error Tol= 0.3
Flow Tol Ratio= 0.001
Split Flow NTrial= 30
Split Flow Tol= 0.02
Split Flow Ratio= 0.02
Log Output Level= 0
Friction Slope Method= 1
Unsteady Friction Slope Method= 2
Unsteady Bridges Friction Slope Method= 1
Parabolic Critical Depth
Global Vel Dist= 1 , 1 , 1
Global Log Level= 0
CheckData=True
Encroach Param=-1 ,0,0, 0
BEGIN DESCRIPTION:
Multiple Run
END DESCRIPTION:
Computation Interval=1HOUR
Output Interval=1HOUR
Run HTab= 0
Run UNet= 0
Run PostProcess= 0
Run WQNet= 0
UNET Theta= 1
UNET Theta Warmup= 1
UNET ZTol= 0.02
UNET ZSATol= 0.05
UNET MxIter= 20
UNET MaxInSteps= 0
UNET DtIC= 0
UNET DtMin= 0
UNET MaxCRTS= 20
UNET WFStab= 2
UNET SFStab= 1
UNET WFX= 1
UNET SFX= 1
UNET DSS MLevel= 4
UNET DZMax Abort= 100
UNET Convert EG Bridges= 0
UNET Use Existing IB Tables=-1
UNET Froude Reduction=False
UNET Froude Limit= 1
UNET Froude Power= 10
UNET Time Slicing=0,0, 5
UNET Junction Losses=0
Instantaneous Interval=1HOUR
Write IC File= 0
Write IC File at Sim End=0
Echo Input=False
Echo Parameters=False
Echo Output=False
Write Detailed= 0
WQ AD Non Conservative
WQ ULTIMATE=-1
WQ Max Comp Step=1HOUR
WQ Output Interval=15MIN
WQ Output Selected Increments= 0
WQ Output face flow=0
WQ Output face velocity=0
WQ Output face area=0
WQ Output face dispersion=0
WQ Output cell volume=0
WQ Output cell surface area=0
WQ Output cell continuity=0
WQ Output cumulative cell continuity=0
WQ Output face conc=0
WQ Output face dconc_dx=0
WQ Output face courant=0
WQ Output face peclet=0
WQ Output face adv mass=0
WQ Output face disp mass=0
WQ Output cell mass=0
WQ Output cell source sink temp=0
WQ Output cell source sink nsm=0
WQ Output MaxMinRange=-1
WQ Daily Max Min Mean=-1
WQ Daily Range=0
WQ Daily Time=0
WQ Create Restart=0
WQ Fixed Restart=0
WQ System Summary=0
WQ Use Fixed Temperature=0
Sorting and Armoring Iterations= 10
XS Update Threshold= 0.02
Hydraulics Update Threshold= 0.02
Energy Slope Method= 1
Volume Change Method= 0
XS Weighting Method= 0
Number of US Weighted Cross Sections= 1
Number of DS Weighted Cross Sections= 1
Upstream XS Weight=0.25
Main XS Weight=0.5
Downstream XS Weight=0.25
Number of DS XS's Weighted with US Boundary= 1
Upstream Boundary Weight= 1
Weight of XSs Associated with US Boundary= 0
Number of US XS's Weighted with DS Boundary= 1
Downstream Boundary Weight= 0.5
Weight of XSs Associated with DS Boundary= 0.5
Sediment Output Level= 4
Mass or Volume Output= 0
Output Increment Type= 1
Profile and TS Output Increment= 10
XS Output Flag= 0
XS Output Increment= 10
Disregard all LS=0
Disregard all Conn=0
Disregard all Breaches=0
Disregard all Pumps=0

--- West Fork Dry Comal Creek.f01 (steady flow) ---

Flow Title=Multiple
Program Version=4.10
Number of Profiles= 7
Profile Names=10-year,25-year,50-year,1pct_min,100-year,1pct_plu,500-year
River Rch & RM=West Fork,Reach-1         ,95203
     922    1534    2105    1399    2791    5569    4854
River Rch & RM=West Fork,Reach-1         ,94021
    1574    2697    3774    2554    5096   10167    9195
River Rch & RM=West Fork,Reach-1         ,92656
    1678    2866    4001    2697    5382   10738    9646
River Rch & RM=West Fork,Reach-1         ,88055
    1903    3249    4533    3052    6089   12149   10882
River Rch & RM=West Fork,Reach-1         ,81125
    1893    3228    4498    3025    6035   12041   10760
River Rch & RM=West Fork,Reach-1         ,80390
    2496    4307    6051    4098    8177   16315   14793
River Rch & RM=West Fork,Reach-1         ,74287
    3298    5761    8160    5567   11107   22162   20393
River Rch & RM=West Fork,Reach-1         ,71071
    3796    6656    9454    6464   12898   25735   23788
River Rch & RM=West Fork,Reach-1         ,64193
    4013    7046   10017    6854   13676   27288   25259
River Rch & RM=West Fork,Reach-1         ,60302
    4087    7183   10218    6996   13959   27851   25811
River Rch & RM=West Fork,Reach-1         ,59204
    4113    7216   10252    7010   13987   27907   25790
River Rch & RM=West Fork,Reach-1         ,55270
    4230    7422   10545    7209   14383   28698   26514
River Rch & RM=West Fork,Reach-1         ,49140
    4129    7259   10326    7067   14100   28133   26061
River Rch & RM=West Fork,Reach-1         ,48597
    4597    8109   11560    7927   15816   31557   29343
River Rch & RM=West Fork,Reach-1         ,37478
    4924    8671   12350    8459   16879   33677   31235
River Rch & RM=West Fork,Reach-1         ,32324
    4868    8598   12268    8418   16797   33513   31207
River Rch & RM=West Fork,Reach-1         ,26372
    5239    9272   13246    9100   18156   36226   33805
River Rch & RM=West Fork,Reach-1         ,18008
    5522    9801   14031    9658   19271   38451   36028
River Rch & RM=West Fork,Reach-1         ,16142
    1108    1831    2496    1643    3278    6541    5602
River Rch & RM=West Fork,Reach-1         ,10938
    1395    2334    3208    2128    4246    8471    7369
River Rch & RM=West Fork,Reach-1         ,2810
    2348    4025    5627    3790    7562   15087   13533
Boundary for River Rch & Prof#=West Fork,Reach-1         , 1
Up Type= 0
Dn Type= 3
Dn Slope=0.005
Boundary for River Rch & Prof#=West Fork,Reach-1         , 2
Up Type= 0
Dn Type= 3
Dn Slope=0.005
Boundary for River Rch & Prof#=West Fork,Reach-1         , 3
Up Type= 0
Dn Type= 3
Dn Slope=0.005
Boundary for River Rch & Prof#=West Fork,Reach-1         , 4
Up Type= 0
Dn Type= 3
Dn Slope=0.005
Boundary for River Rch & Prof#=West Fork,Reach-1         , 5
Up Type= 0
Dn Type= 3
Dn Slope=0.005
Boundary for River Rch & Prof#=West Fork,Reach-1         , 6
Up Type= 0
Dn Type= 3
Dn Slope=0.005
Boundary for River Rch & Prof#=West Fork,Reach-1         , 7
Up Type= 0
Dn Type= 3
Dn Slope=0.005
DSS Import GetInterval= 0
DSS Import GetPeak= 0
DSS Import FillOption= 0

--- West Fork Dry Comal Creek.g01 (geometry) ---

Geom Title=Existing Conditions
Program Version=4.10

River Reach=West Fork       ,Reach-1
Reach XY= 30
        2181325.     13840295.88      2181476.35     13833434.66
      2182480.45     13829272.53      2184025.21     13828300.09
      2181777.06     13825230.86      2182368.94     13823883.14
      2185452.12     13822898.52      2185986.11     13819664.92
      2187975.24     13818850.08      2184475.09     13816109.61
      2187069.17      13812272.7        2183675.       13810725.
      2182828.53     13808926.47       2185114.5     13807826.22
       2190326.4     13811021.62      2191591.71     13810858.36
      2191519.17      13809122.7      2190032.56       13807725.
      2192767.24     13805081.17      2192332.81     13803821.59
      2193673.42     13802518.95      2193711.51     13801411.44
      2191928.54     13800423.54      2192330.45     13798872.55
      2194030.85     13797227.06      2195991.68     13797858.36
      2196480.84     13795272.71       2198326.5     13793378.61
        2202025.       13794775.        2202025.       13791975.

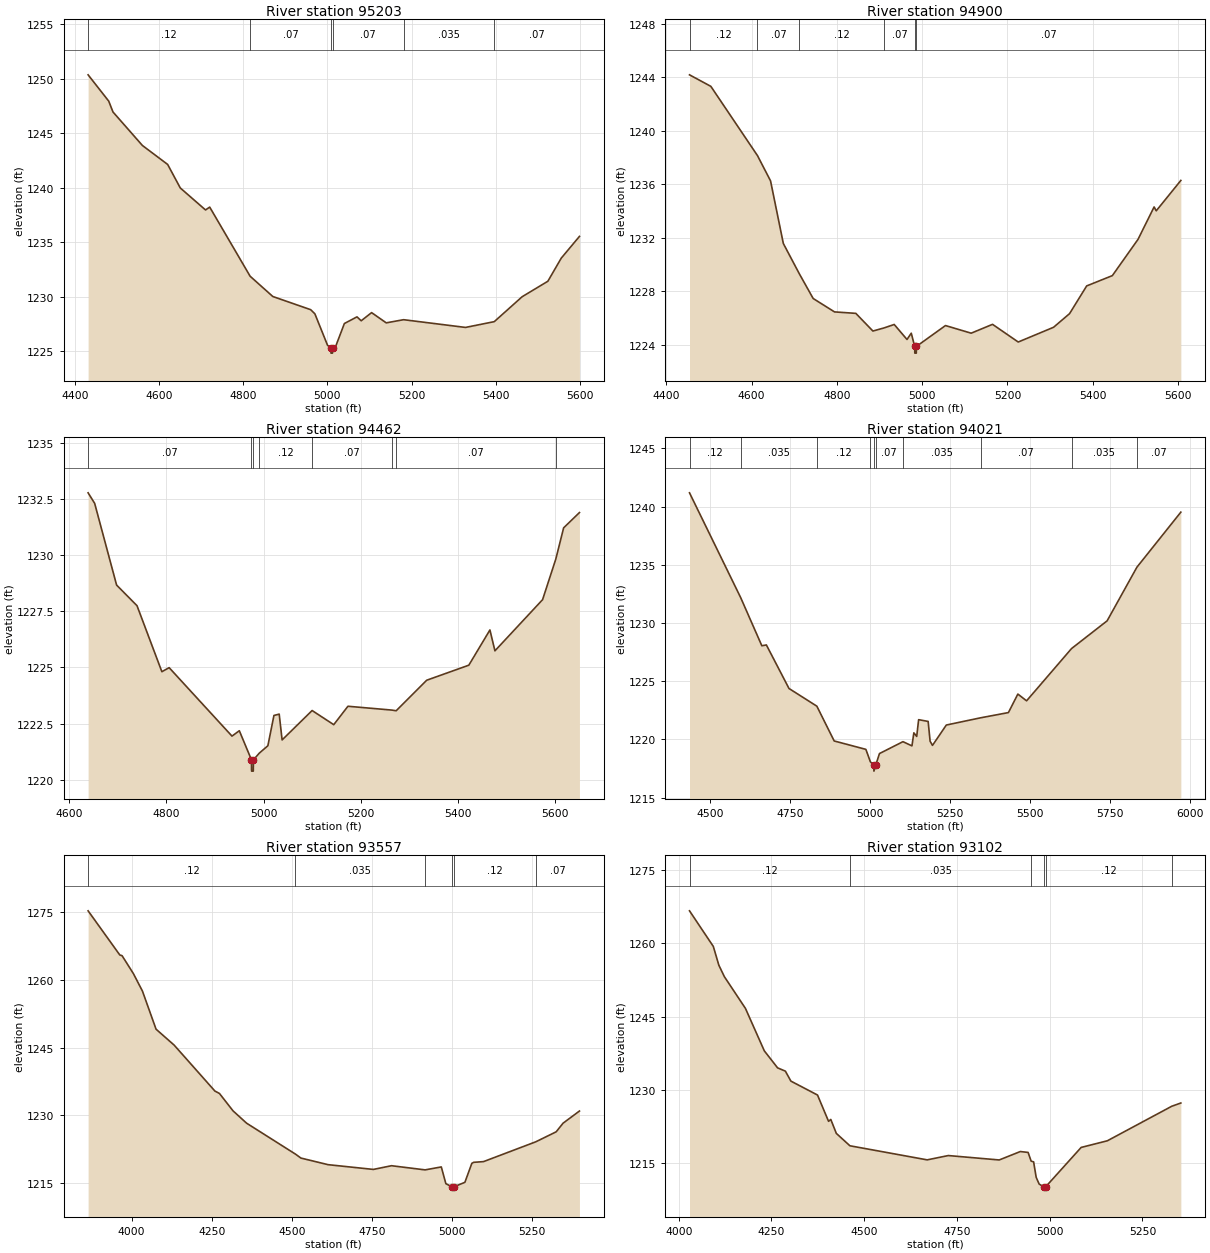
Type RM Length L Ch R = 1 ,95203   ,303,303,303
BEGIN DESCRIPTION:
H21678
END DESCRIPTION:
XS GIS Cut Line= 3
      2181894.13     13840242.41      2181229.88     13840247.64
      2180743.42     13840378.41
#Sta/Elev= 30
  4431.2 1250.36  4480.3 1247.94  4490.3 1246.95  4560.3 1243.87  4620.3 1242.13
  4650.3 1239.97  4710.3 1237.95  4720.3 1238.21  4816.4 1231.86  4870.3    1230
  4960.3 1228.79  4970.3 1228.41  5000.4 1225.52  5008.4  1225.3  5008.6  1224.8
  5012.1  1224.8  5012.4  1225.3  5020.4 1225.49  5040.4 1227.52  5070.4 1228.13
  5080.4 1227.77  5105.1 1228.52  5139.9 1227.58  5181.2 1227.87  5328.3 1227.16
  5396.7 1227.69    5463 1229.98  5524.1  1231.4  5556.1 1233.53  5599.2 1235.52
#Mann= 6 ,-1 , 0
  4431.2     .12       0  4816.4     .07       0  5008.4     .05       0
  5012.4     .07       0  5181.2    .035       0  5396.7     .07       0
Bank Sta=5008.4,5012.4
XS Rating Curve= 0 ,0
Exp/Cntr=0.3,0.1

Type RM Length L Ch R = 1 ,94900   ,438,438,438
BEGIN DESCRIPTION:
West Fork 167.0
END DESCRIPTION:
XS GIS Cut Line= 3
      2181775.01       13839975.        2181225.       13839975.
      2180624.99       13840025.
#Sta/Elev= 30
  4454.5 1244.18  4504.5 1243.32  4613.8 1238.15  4644.5 1236.26  4674.5 1231.58
  4712.3  1229.3  4744.5 1227.47  4794.5 1226.47  4844.5 1226.36  4884.5 1225.04
  4910.4 1225.27  4934.5 1225.53  4964.5 1224.41  4974.5 1224.88  4982.5 1223.89
  4982.8 1223.39  4986.3 1223.39  4986.5 1223.89  5054.7 1225.45  5114.9 1224.88
  5165.1 1225.54  5225.3 1224.22  5308.1 1225.32  5345.7 1226.34  5385.8 1228.41
    5446 1229.18  5506.2 1231.89  5543.9 1234.31  5548.9 1234.02  5606.6 1236.29
#Mann= 6 ,-1 , 0
  4454.5     .12       0  4613.8     .07       0  4712.3     .12       0
  4910.4     .07       0  4982.5     .05       0  4986.5     .07       0
Bank Sta=4982.5,4986.5
XS Rating Curve= 0 ,0
Exp/Cntr=0.3,0.1

Type RM Length L Ch R = 1 ,94462   ,441,441,441
BEGIN DESCRIPTION:
West Fork 166.0
END DESCRIPTION:
XS GIS Cut Line= 3
      2181624.98     13839774.99        2181325.       13839575.
      2180725.03     13839824.99
#Sta/Elev= 30
    4639 1232.78  4652.5 1232.31  4697.6 1228.67  4739.6 1227.75  4790.7 1224.81
  4805.7 1224.99  4934.9 1221.94    4950 1222.18    4975 1220.88  4975.2 1220.38
  4978.7 1220.38    4979 1220.88    4991 1221.18  5008.7 1221.51  5021.2 1222.86
    5032 1222.92    5038 1221.77  5099.7 1223.08  5144.2 1222.45  5173.4 1223.27
  5263.7  1223.1  5272.6 1223.07  5335.4 1224.43    5422  1225.1  5465.4 1226.67
  5475.7 1225.74  5573.7 1228.02  5600.9 1229.83    5617 1231.22  5649.5  1231.9
#Mann= 8 ,-1 , 0
    4639     .07       0    4975     .05       0    4979     .07       0
    4991     .12       0  5099.7     .07       0  5263.7    .035       0
  5272.6     .07       0  5600.9    .035       0
Bank Sta=4975,4979
XS Rating Curve= 0 ,0
Exp/Cntr=0.3,0.1

Type RM Length L Ch R = 1 ,94021   ,464,464,464
BEGIN DESCRIPTION:
West Fork 165.0
END DESCRIPTION:
XS GIS Cut Line= 3
      2181724.98     13838875.02        2181325.       13839275.
      2180524.98     13839825.01
#Sta/Elev= 30
  4435.5 1241.19  4595.8 1232.17  4661.7 1228.05  4675.9 1228.12  4746.6 1224.38
  4833.7 1222.86    4888 1219.87    4987 1219.15    5001 1218.09  5011.7 1217.78
  5012.2 1217.28  5017.6 1217.78  5029.6 1218.79    5103 1219.81  5131.1 1219.45
  5137.1 1220.57    5146 1220.26    5152  1221.7  5181.8 1221.55  5187.9 1219.85
  5195.3 1219.49  5238.6 1221.24  5345.6 1221.86  5432.8 1222.31  5462.3  1223.9
  5489.6 1223.32  5630.2 1227.81  5741.4 1230.19  5834.6  1234.8    5972 1239.53
#Mann= 10 ,-1 , 0
  4435.5     .12       0  4595.8    .035       0  4833.7     .12       0
    5001     .07       0  5011.7     .05       0  5017.6     .07       0
    5103    .035       0  5345.6     .07       0  5630.2    .035       0
  5834.6     .07       0
Bank Sta=5011.7,5017.6
XS Rating Curve= 0 ,0
Exp/Cntr=0.3,0.1

Type RM Length L Ch R = 1 ,93557   ,455,455,455
BEGIN DESCRIPTION:
West Fork 164.0
END DESCRIPTION:
XS GIS Cut Line= 3
      2181775.03     13838324.97        2180975.       13839125.
      2180625.02     13839324.99
#Sta/Elev= 30
  3864.2 1275.25  3963.2 1265.48  3970.3 1265.32  4005.7 1261.35  4033.9 1257.49
  4076.4 1249.06  4132.9 1245.54  4260.2 1235.37  4274.4 1234.84  4316.8 1230.99
  4359.2 1228.26  4511.5 1221.43  4528.9 1220.54  4613.8 1219.08  4755.2 1218.03
  4811.8 1218.85  4916.7 1217.93  4967.3 1218.58  4981.5 1214.88  5000.6 1214.17
    5001 1213.67  5006.5 1214.17    5041 1215.18  5062.6 1219.37  5068.3  1219.6
  5099.3 1219.76  5262.3 1224.14    5326 1226.35  5347.6 1228.26  5398.7 1230.95
#Mann= 6 ,-1 , 0
  3864.2     .12       0  4511.5    .035       0  4916.7     .12       0
  5000.6     .05       0  5006.5     .12       0  5262.3     .07       0
Bank Sta=5000.6,5006.5
XS Rating Curve= 0 ,0
Exp/Cntr=0.3,0.1

Type RM Length L Ch R = 1 ,93102   ,446,446,446
BEGIN DESCRIPTION:
West Fork 163.0
END DESCRIPTION:
XS GIS Cut Line= 3
      2181624.96     13838175.03        2180825.       13838725.
      2180575.02     13838974.98
#Sta/Elev= 30
  4029.1 1266.61  4093.3 1259.33  4108.2 1255.49  4123.1 1253.15  4179.9 1246.67
  4230.7    1238  4266.5 1234.52  4287.5 1233.85  4302.4 1231.81  4374.1 1228.97
  4403.9 1223.59  4409.9 1223.98  4424.8 1221.13  4461.4  1218.6  4669.7 1215.72
  4726.6  1216.6  4863.9  1215.7  4920.7 1217.42  4941.7 1217.24  4949.9 1215.46
  4956.6 1215.31  4963.5 1212.15  4971.5 1210.77  4983.4 1210.24  4983.9 1209.74
  4989.4 1210.24  5084.7 1218.26  5155.4 1219.62  5328.8 1226.67  5353.4 1227.34
#Mann= 6 ,-1 , 0
  4029.1     .12       0  4461.4    .035       0  4949.9     .12       0
  4983.4     .05       0  4989.4     .12       0  5328.8     .07       0
Bank Sta=4983.4,4989.4
XS Rating Curve= 0 ,0
Exp/Cntr=0.3,0.1

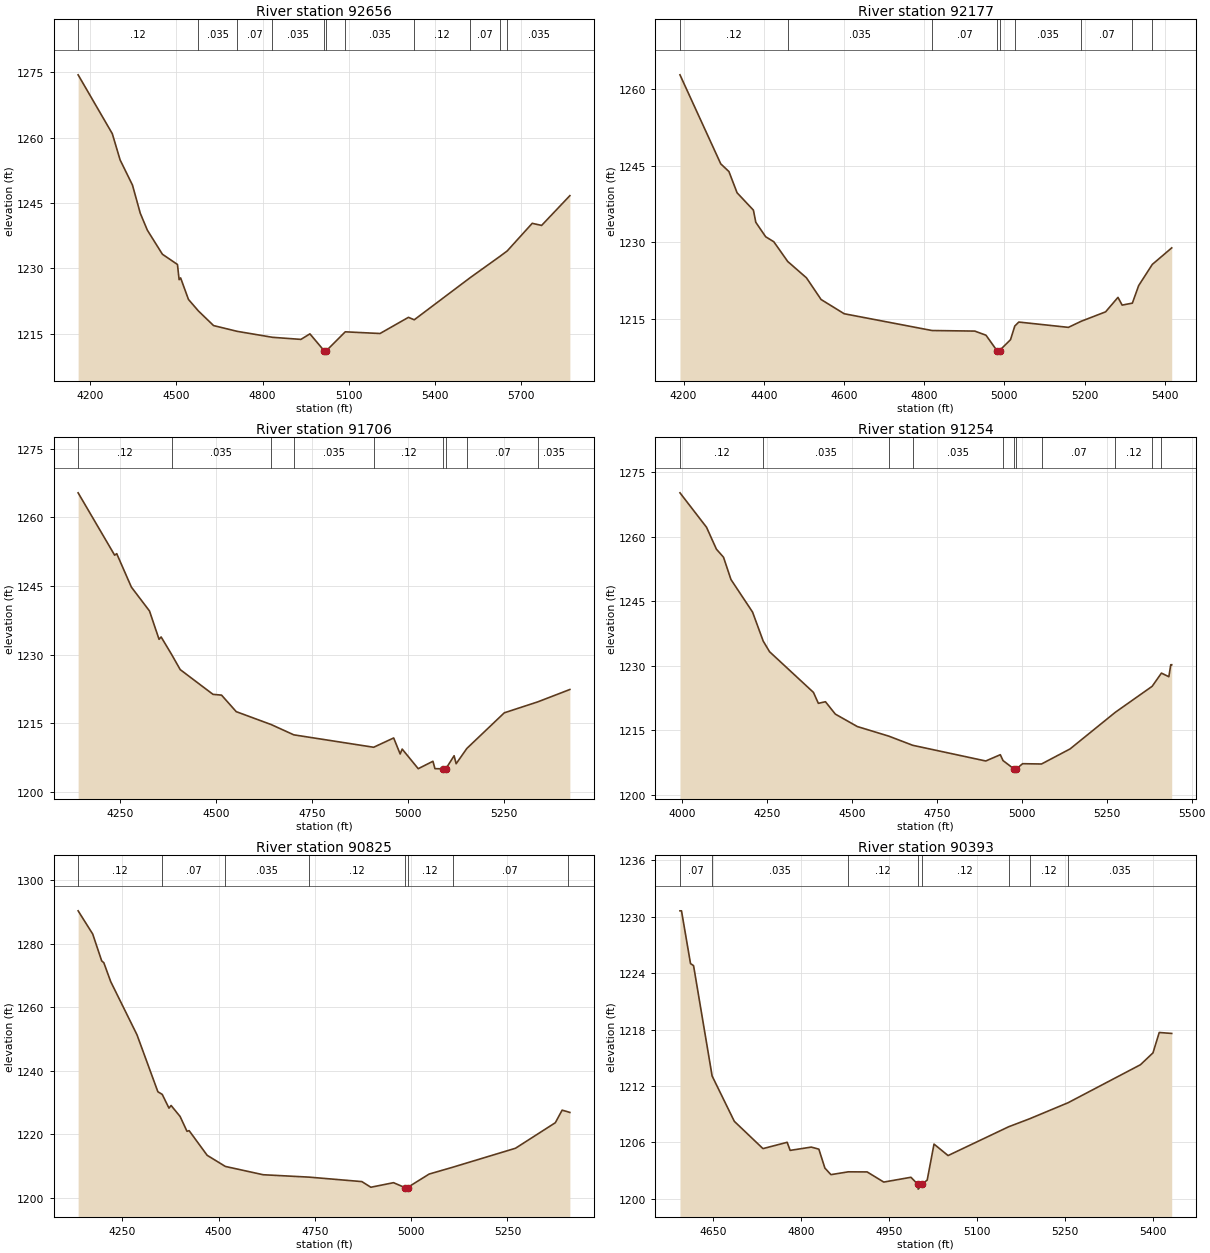
Type RM Length L Ch R = 1 ,92656   ,479,479,479
BEGIN DESCRIPTION:
West Fork 162.0
END DESCRIPTION:
XS GIS Cut Line= 3
      2181674.99       13838075.        2180875.       13838325.
      2180074.96     13837974.98
#Sta/Elev= 30
  4157.8 1274.38  4276.7 1260.88  4303.9 1254.86  4346.9 1249.09  4374.1 1242.62
  4398.8 1238.73  4451.1 1233.22  4503.5 1230.87  4509.3 1227.38  4514.5 1227.79
  4541.8 1222.85  4576.5  1220.2  4629.2 1216.85  4711.3 1215.53  4834.2 1214.16
  4933.1 1213.68  4964.5 1214.95  5014.6 1211.03  5015.1 1210.53  5020.9 1211.03
  5087.5 1215.42  5208.4 1215.03  5307.4 1218.74  5327.6 1218.18  5521.8 1227.82
  5624.7 1232.68  5651.1 1233.97  5738.2 1240.31  5770.9 1239.83  5869.2 1246.66
#Mann= 11 ,-1 , 0
  4157.8     .12       0  4576.5    .035       0  4711.3     .07       0
  4834.2    .035       0  5014.6    .035       0  5020.9    .035       0
  5087.5    .035       0  5327.6     .12       0  5521.8     .07       0
  5624.7     .12       0  5651.1    .035       0
Bank Sta=5014.6,5020.9
XS Rating Curve= 0 ,0
Exp/Cntr=0.3,0.1

Type RM Length L Ch R = 1 ,92177   ,471,471,471
BEGIN DESCRIPTION:
West Fork 161.0
END DESCRIPTION:
XS GIS Cut Line= 3
      2181574.99       13838025.        2180775.       13837875.
      2180375.04     13837974.99
#Sta/Elev= 30
  4191.2 1262.86  4292.9 1245.41  4313.3  1243.9  4333.6 1239.74  4374.3 1236.34
  4380.3 1233.95  4404.9 1231.12  4425.2 1230.14  4459.9 1226.27  4506.6 1223.07
  4543.1 1218.82  4600.7 1216.03  4819.7 1212.74  4926.3 1212.63  4954.3 1211.82
  4981.6 1208.81  4982.1 1208.31    4988 1208.81  5015.4 1210.94  5026.1 1213.62
  5036.1  1214.4  5159.8 1213.36  5191.5 1214.55  5252.5  1216.4  5283.4 1219.24
  5293.8 1217.72  5319.3 1218.11    5335 1221.55    5369  1225.7  5417.4 1228.94
#Mann= 9 ,-1 , 0
  4191.2     .12       0  4459.9    .035       0  4819.7     .07       0
  4981.6     .05       0    4988    .035       0  5026.1    .035       0
  5191.5     .07       0  5319.3    .035       0    5369     .07       0
Bank Sta=4981.6,4988
XS Rating Curve= 0 ,0
Exp/Cntr=0.3,0.1

Type RM Length L Ch R = 1 ,91706   ,452,452,452
BEGIN DESCRIPTION:
West Fork 160.0
END DESCRIPTION:
XS GIS Cut Line= 3
      2181624.99       13837725.        2180825.       13837425.
      2180424.99       13837275.
#Sta/Elev= 30
  4139.6 1265.33  4234.8 1251.72  4240.2 1252.05  4278.4 1244.75  4325.6 1239.54
  4350.5 1233.36  4355.9 1233.87  4383.1 1230.07  4405.7 1226.74  4491.1 1221.34
  4513.4 1221.17  4551.7 1217.56  4642.6 1214.75  4701.7  1212.5  4909.8 1209.79
    4962 1211.82  4978.9 1208.32  4984.2 1209.39    5026 1205.11  5064.3 1206.73
  5069.6 1205.12  5091.3 1205.08  5091.8 1204.58  5097.9 1205.08  5119.5 1207.94
  5124.8 1206.19  5152.7 1209.53  5250.3 1217.31  5337.6  1219.7  5421.2  1222.4
#Mann= 9 ,-1 , 0
  4139.6     .12       0  4383.1    .035       0  4642.6     .07       0
  4701.7    .035       0  4909.8     .12       0  5091.3     .05       0
  5097.9     .12       0  5152.7     .07       0  5337.6    .035       0
Bank Sta=5091.3,5097.9
XS Rating Curve= 0 ,0
Exp/Cntr=0.3,0.1

Type RM Length L Ch R = 1 ,91254   ,429,429,429
BEGIN DESCRIPTION:
West Fork 159.0
END DESCRIPTION:
XS GIS Cut Line= 3
      2181675.04     13837675.03        2180875.       13837075.
      2180474.97     13836874.98
#Sta/Elev= 30
    3994 1270.24  4072.2 1262.22  4101.3 1257.12  4122.2 1255.24    4144 1250.07
  4207.6 1242.49  4238.9 1235.74  4257.6 1233.26  4386.8 1223.79  4401.3 1221.24
  4422.2 1221.61  4451.3 1218.73  4515.9 1215.84  4608.8  1213.6  4679.1 1211.47
    4894 1207.82  4936.8 1209.28  4944.8 1207.92  4977.2 1205.96  4977.7 1205.46
  4983.9 1205.96  5002.4 1207.19  5058.1 1207.12  5142.2 1210.63  5275.2 1219.15
  5383.7  1225.2  5411.1 1228.28  5432.9 1227.43  5438.5 1230.23  5441.3 1230.23
#Mann= 11 ,-1 , 0
    3994     .12       0  4238.9    .035       0  4608.8     .07       0
  4679.1    .035       0  4944.8     .12       0  4977.2     .05       0
  4983.9     .12       0  5058.1     .07       0  5275.2     .12       0
  5383.7    .035       0  5411.1    .063       0
Bank Sta=4977.2,4983.9
XS Rating Curve= 0 ,0
Exp/Cntr=0.3,0.1

Type RM Length L Ch R = 1 ,90825   ,432,432,432
BEGIN DESCRIPTION:
West Fork 158.0
END DESCRIPTION:
XS GIS Cut Line= 3
      2181724.99       13836375.        2180925.       13836725.
      2180525.02       13836775.
#Sta/Elev= 30
  4135.6 1290.34  4173.4 1283.05  4196.8 1274.57  4202.3 1274.01  4220.2 1268.05
  4288.4 1251.31  4342.6 1233.38  4353.9 1232.56  4371.4 1228.22  4376.9 1229.06
  4400.3  1225.6  4418.2 1220.93  4423.7 1221.14  4470.5 1213.38  4517.8 1209.87
  4615.9 1207.26  4734.6 1206.51    4872  1205.1  4895.4 1203.32  4954.2 1204.76
  4983.5 1203.23    4984 1202.73  4990.5 1203.23  5046.6 1207.47  5107.5 1209.61
  5270.8  1215.6  5374.1 1223.63  5391.8 1227.59  5406.5 1227.08  5411.9 1226.87
#Mann= 8 ,-1 , 0
  4135.6     .12       0  4353.9     .07       0  4517.8    .035       0
  4734.6     .12       0  4983.5     .05       0  4990.5     .12       0
  5107.5     .07       0  5406.5    .063       0
Bank Sta=4983.5,4990.5
XS Rating Curve= 0 ,0
Exp/Cntr=0.3,0.1

Type RM Length L Ch R = 1 ,90393   ,472,472,472
BEGIN DESCRIPTION:
West Fork 157.0
END DESCRIPTION:
XS GIS Cut Line= 3
        2181475.       13836275.        2181075.       13836375.
      2180675.01       13836225.
#Sta/Elev= 30
  4593.2 1230.64  4595.8 1230.64  4611.2 1225.03  4616.4 1224.81  4648.1 1213.07
    4686 1208.25  4734.9 1205.35  4776.2 1206.02  4781.3 1205.16  4817.4 1205.51
  4830.3 1205.29  4840.6 1203.28  4850.9 1202.58  4880.6 1202.88  4912.7 1202.87
  4941.1 1201.79  4987.5  1202.3  4999.4 1201.54  4999.9 1201.04  5006.4 1201.54
  5015.3 1202.01  5026.9 1205.83  5050.9 1204.61  5154.2 1207.67    5190 1208.52
  5255.8 1210.23  5379.3 1214.27  5400.7 1215.53  5411.4  1217.7  5432.7  1217.6
#Mann= 8 ,-1 , 0
  4593.2     .07       0  4648.1    .035       0  4880.6     .12       0
  4999.4     .05       0  5006.4     .12       0  5154.2    .035       0
    5190     .12       0  5255.8    .035       0
Bank Sta=4999.4,5006.4
XS Rating Curve= 0 ,0
Exp/Cntr=0.3,0.1

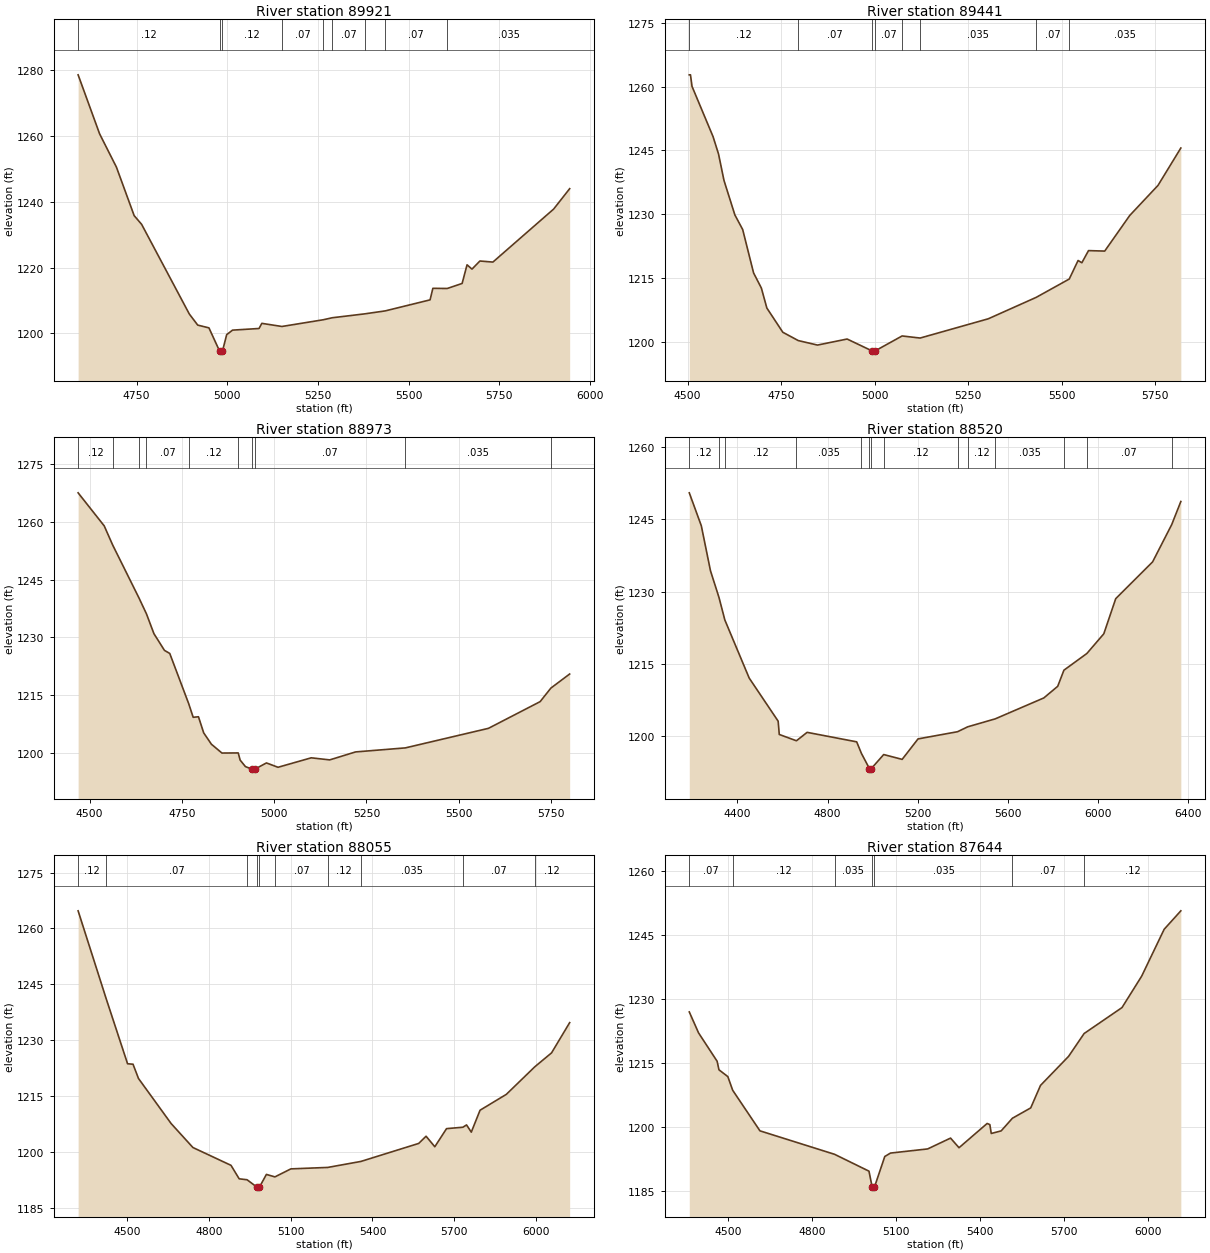
Type RM Length L Ch R = 1 ,89921   ,480,480,480
BEGIN DESCRIPTION:
West Fork 156.0
END DESCRIPTION:
XS GIS Cut Line= 3
      2181675.01       13836075.        2181275.       13835975.
      2180475.02     13835475.01
#Sta/Elev= 30
  4588.5 1278.58  4647.8 1260.63  4694.2 1250.51  4743.1 1235.77  4763.7 1233.12
  4895.2 1205.87  4918.4  1202.5  4949.3 1201.66  4979.2 1194.48  4979.7 1193.98
  4986.4 1194.48  4998.2 1199.59  5014.4 1200.97  5087.5 1201.47  5095.2 1203.03
  5150.5 1202.08  5264.5 1204.12  5289.3 1204.73  5378.5 1205.91  5435.6 1206.82
  5559.2 1210.17  5566.9 1213.68  5606.6 1213.63  5647.6 1215.16  5661.2 1220.83
  5674.8 1219.52  5696.6 1221.98  5732.5 1221.66    5900 1237.77  5944.2 1243.97
#Mann= 9 ,-1 , 0
  4588.5     .12       0  4979.2     .05       0  4986.4     .12       0
  5150.5     .07       0  5264.5    .035       0  5289.3     .07       0
  5378.5    .035       0  5435.6     .07       0  5606.6    .035       0
Bank Sta=4979.2,4986.4
XS Rating Curve= 0 ,0
Exp/Cntr=0.3,0.1

Type RM Length L Ch R = 1 ,89441   ,468,468,468
BEGIN DESCRIPTION:
West Fork 155.0
END DESCRIPTION:
XS GIS Cut Line= 3
      2181675.02     13835825.02        2181275.       13835525.
      2180474.97     13835374.99
#Sta/Elev= 30
  4504.7 1262.76  4507.9 1262.76    4512 1260.05  4568.3 1248.24  4582.9 1244.17
  4597.4 1237.99  4626.6 1229.87  4647.4 1226.46  4676.6 1216.26  4697.4 1212.71
    4712 1208.03  4754.7 1202.34  4795.9 1200.39  4847.4 1199.33  4926.6 1200.75
  4993.8 1197.94  4994.3 1197.44    5001 1197.94  5073.6 1201.47  5121.8 1200.98
    5304  1205.5  5432.1 1210.53  5520.4 1214.83    5544 1219.18  5554.1 1218.65
  5571.9  1221.5  5615.2 1221.39  5682.2 1229.76  5757.6  1236.8  5818.7 1245.58
#Mann= 8 ,-1 , 0
  4504.7     .12       0  4795.9     .07       0  4993.8     .05       0
    5001     .07       0  5073.6     .12       0  5121.8    .035       0
  5432.1     .07       0  5520.4    .035       0
Bank Sta=4993.8,5001
XS Rating Curve= 0 ,0
Exp/Cntr=0.3,0.1

Type RM Length L Ch R = 1 ,88973   ,453,453,453
BEGIN DESCRIPTION:
West Fork 154.0
END DESCRIPTION:
XS GIS Cut Line= 3
      2181874.97     13835574.97        2181525.       13835175.
      2180724.96       13835175.
#Sta/Elev= 30
    4469 1267.59  4539.7    1259  4562.5 1254.05  4634.1 1240.22    4654 1236.16
  4674.4 1230.98  4702.9 1226.64  4717.2 1225.85  4768.4 1212.83  4780.7 1209.25
    4795 1209.39  4809.2  1205.2  4830.1 1202.25  4858.6 1199.96  4902.7 1199.99
  4907.9 1198.13  4922.2 1196.44  4940.3 1195.76  4940.8 1195.26  4947.6 1195.76
  4979.1 1197.39  5010.5 1196.26  5100.5 1198.72  5150.5 1198.18  5220.5 1200.25
  5355.5  1201.3  5580.5 1206.38  5720.5 1213.32  5749.6 1216.84  5800.5  1220.5
#Mann= 10 ,-1 , 0
    4469     .12       0  4562.5     .07       0  4634.1     .12       0
    4654     .07       0  4768.4     .12       0  4902.7     .07       0
  4940.3     .05       0  4947.6     .07       0  5355.5    .035       0
  5749.6    .063       0
Bank Sta=4940.3,4947.6
XS Rating Curve= 0 ,0
Exp/Cntr=0.3,0.1

Type RM Length L Ch R = 1 ,88520   ,465,465,465
BEGIN DESCRIPTION:
H21677
END DESCRIPTION:
XS GIS Cut Line= 4
      2182427.69     13834666.82      2181684.93     13834787.12
      2181046.82     13834708.67       2180283.2     13834886.49
#Sta/Elev= 30
  4187.2  1250.5  4240.6 1243.65  4281.1 1234.33  4318.8 1228.79  4344.9  1224.1
  4452.8 1212.05  4581.2  1203.1  4586.2 1200.34  4662.3 1199.03  4709.6 1200.78
  4929.4 1198.81  4950.3 1196.42  4986.2 1193.23  4986.7 1192.73  4993.6 1193.23
  5049.2 1196.17    5131 1195.17  5201.5 1199.42  5376.6 1200.91  5421.8 1201.93
  5543.7 1203.58    5759 1207.92  5820.6 1210.33  5848.2 1213.68    5950 1217.15
  6025.1 1221.24  6077.9 1228.53  6241.5 1236.17  6326.1  1243.9  6366.6  1248.7
#Mann= 14 ,-1 , 0
  4187.2     .12       0  4318.8     .07       0  4344.9     .12       0
  4662.3    .035       0  4950.3     .07       0  4986.2     .05       0
  4993.6     .07       0  5049.2     .12       0  5376.6    .035       0
  5421.8     .12       0  5543.7    .035       0  5848.2    .063       0
    5950     .07       0  6326.1    .035       0
Bank Sta=4986.2,4993.6
XS Rating Curve= 0 ,0
Exp/Cntr=0.3,0.1

Type RM Length L Ch R = 1 ,88055   ,411,411,411
BEGIN DESCRIPTION:
H21676
END DESCRIPTION:
XS GIS Cut Line= 3
      2182406.73     13834342.54      2181512.32     13834347.77
      2180644.13     13834070.57
#Sta/Elev= 30
  4318.6 1264.74  4422.2 1241.02  4500.3 1223.65  4520.3 1223.53  4540.3 1219.71
  4660.3 1207.59  4740.3 1201.15  4880.3 1196.36  4910.3 1192.74  4939.2 1192.49
  4976.2 1190.47  4976.7 1189.97  4984.4 1190.47  5010.3 1193.92  5041.6 1193.26
  5100.3 1195.41  5235.7  1195.8  5357.5 1197.41  5569.9 1202.25  5596.8 1204.18
    5629 1201.36  5672.1 1206.22  5732.1  1206.6  5745.6 1207.22    5763 1205.28
  5795.2 1211.17  5891.7 1215.43  5996.5 1222.85  6057.9 1226.58  6124.4  1234.7
#Mann= 10 ,-1 , 0
  4318.6     .12       0  4422.2     .07       0  4939.2     .12       0
  4976.2     .05       0  4984.4     .12       0  5041.6     .07       0
  5235.7     .12       0  5357.5    .035       0  5732.1     .07       0
  5996.5     .12       0
Bank Sta=4976.2,4984.4
XS Rating Curve= 0 ,0
Exp/Cntr=0.3,0.1

Type RM Length L Ch R = 1 ,87644   ,528,528,528
BEGIN DESCRIPTION:
H21675
END DESCRIPTION:
XS GIS Cut Line= 4
      2182286.46      13834128.1      2181763.38     13833971.18
      2181376.33     13834049.64       2180565.6      13833992.1
#Sta/Elev= 30
  4362.9 1226.98    4396 1222.08  4462.2 1215.45  4468.8 1213.45  4500.4 1211.86
  4517.8 1208.66    4615 1199.18  4881.3 1193.69    5004 1189.75  5015.4 1186.05
  5015.9 1185.55  5023.7 1186.05  5060.4 1193.18  5080.8 1193.98  5213.5 1194.95
  5295.1 1197.48  5325.3 1195.23  5425.6  1200.9  5435.3 1200.64  5440.3 1198.56
  5475.7 1199.17  5515.9 1202.13  5581.1 1204.54    5616  1209.8  5716.3  1216.6
  5771.6 1221.93  5906.8    1228    5977 1235.35  6057.2  1246.3  6116.7 1250.62
#Mann= 7 ,-1 , 0
  4362.9     .07       0  4517.8     .12       0  4881.3    .035       0
  5015.4    .035       0  5023.7    .035       0  5515.9     .07       0
  5771.6     .12       0
Bank Sta=5015.4,5023.7
XS Rating Curve= 0 ,0
Exp/Cntr=0.3,0.1

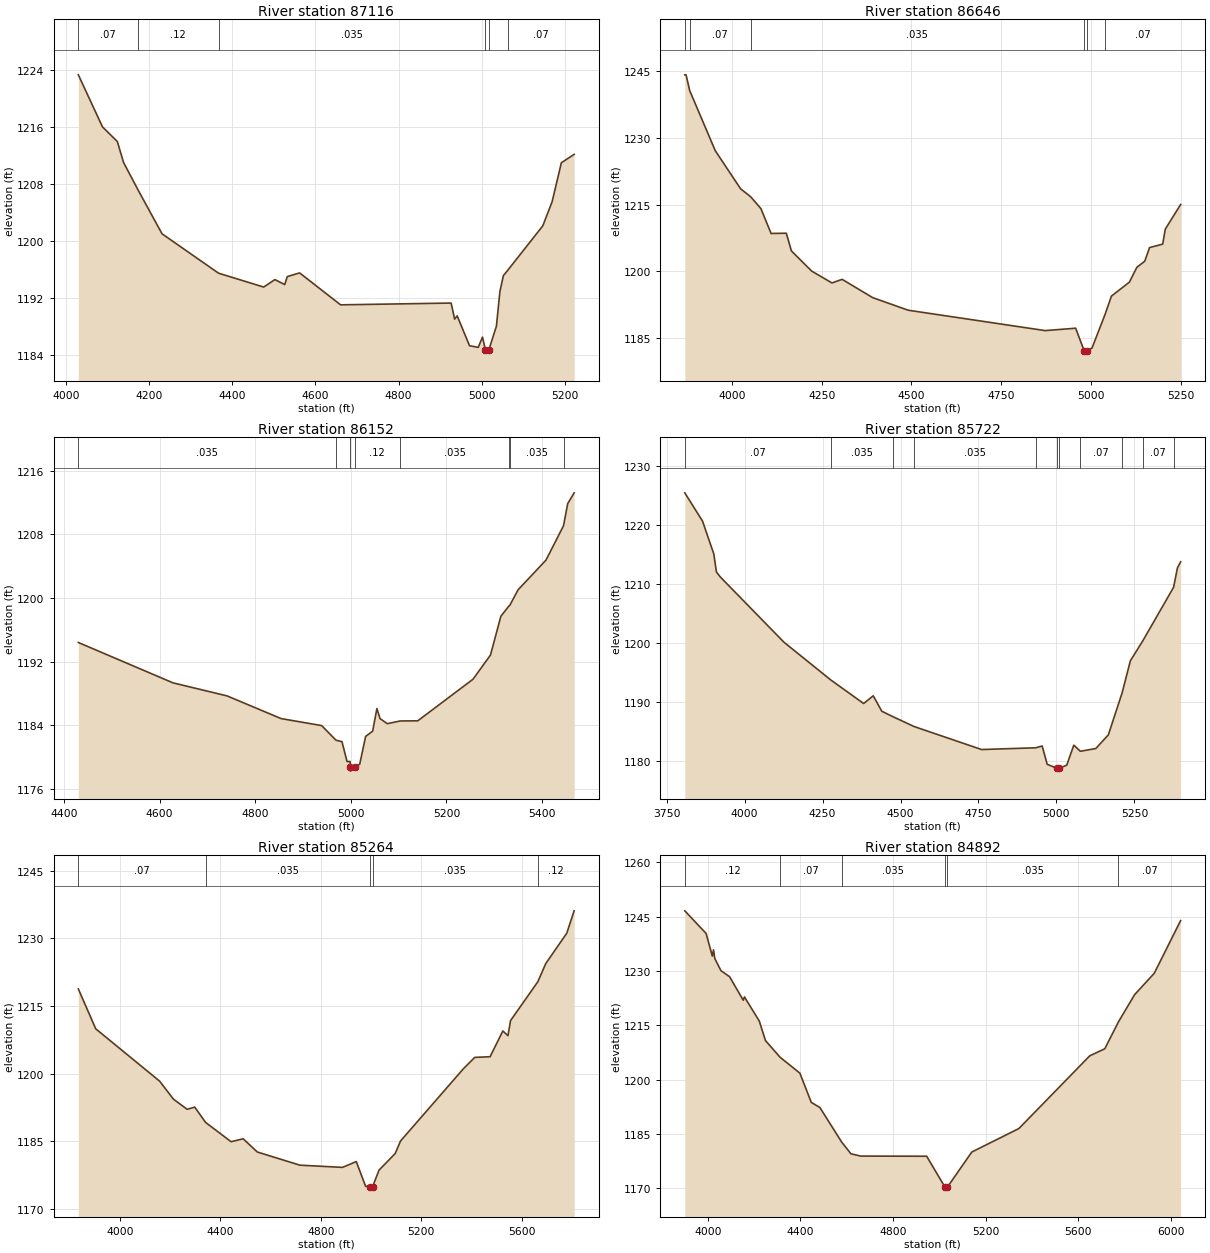
Type RM Length L Ch R = 1 ,87116   ,470,470,470
BEGIN DESCRIPTION:
West Fork 150.0
END DESCRIPTION:
XS GIS Cut Line= 3
      2182274.97     13834074.98        2181475.       13833525.
        2181275.       13833425.
#Sta/Elev= 30
  4028.7 1223.38  4086.9 1216.06  4122.7    1214  4137.6 1211.06  4172.7 1207.18
  4230.3 1201.03  4366.5 1195.49  4475.2 1193.54  4502.2 1194.59  4525.9 1193.89
    4532 1195.01  4561.8 1195.53  4660.5 1191.04  4926.7 1191.29  4935.2 1189.03
  4941.3 1189.49  4971.1 1185.29    4992 1185.06  5002.3  1186.5  5009.1 1184.75
  5009.6 1184.25  5017.8 1184.75  5035.8 1188.03  5044.2 1192.89  5052.6 1195.15
  5063.4 1195.92  5147.6 1202.15    5170 1205.53  5192.3 1211.02  5223.1  1212.2
#Mann= 6 ,-1 , 0
  4028.7     .07       0  4172.7     .12       0  4366.5    .035       0
  5009.1    .035       0  5017.8    .035       0  5063.4     .07       0
Bank Sta=5009.1,5017.8
XS Rating Curve= 0 ,0
Exp/Cntr=0.3,0.1

Type RM Length L Ch R = 1 ,86646   ,494,494,494
BEGIN DESCRIPTION:
West Fork 149.0
END DESCRIPTION:
XS GIS Cut Line= 3
      2182475.01     13833925.01        2181675.       13833125.
      2181474.99     13832974.99
#Sta/Elev= 30
  3868.6 1244.22  3872.1 1244.22  3882.3 1240.66  3953.5 1227.14  4024.2 1218.55
  4051.8  1216.8  4080.7  1214.1    4109 1208.51  4151.5 1208.56  4165.6 1204.58
  4222.2 1200.03  4278.7 1197.37    4307 1198.18  4391.9 1194.07  4490.9 1191.23
  4872.7 1186.64  4957.6 1187.18  4981.4 1182.07  4981.9 1181.57  4990.3 1182.07
  5003.1 1182.71  5039.4 1190.26  5057.3 1194.41  5107.3 1197.55  5128.1 1200.89
    5150 1202.26  5163.5 1205.33    5200 1206.11  5207.3 1209.48    5250 1215.03
#Mann= 6 ,-1 , 0
  3868.6     .12       0  3882.3     .07       0  4051.8    .035       0
  4981.4    .035       0  4990.3    .035       0  5039.4     .07       0
Bank Sta=4981.4,4990.3
XS Rating Curve= 0 ,0
Exp/Cntr=0.3,0.1

Type RM Length L Ch R = 1 ,86152   ,430,430,430
BEGIN DESCRIPTION:
West Fork 148.0
END DESCRIPTION:
XS GIS Cut Line= 3
      2182425.02     13833175.02        2182025.       13832775.
      2181625.01     13832525.01
#Sta/Elev= 30
  4429.9  1194.4  4627.9 1189.33  4741.1 1187.69  4854.2 1184.84    4939 1183.96
  4969.1 1182.12  4981.5 1181.94  4992.1 1179.45  4998.6 1179.45  4998.8 1178.74
  4999.3 1178.24  5007.8 1178.74  5018.6  1179.1    5031  1182.6  5045.7 1183.26
  5054.6  1186.1  5061.1 1184.84  5076.4  1184.2    5103 1184.54  5140.1 1184.56
  5255.6 1189.78  5292.2 1192.82    5314  1197.7    5331 1198.99  5332.7 1199.07
    5350 1201.02  5408.4 1204.75    5445 1209.06  5453.8 1211.84  5467.3  1213.2
#Mann= 8 ,-1 , 0
  4429.9    .035       0  4969.1     .12       0  4998.8     .05       0
  5007.8     .12       0    5103    .035       0    5331     .07       0
  5332.7    .035       0    5445     .07       0
Bank Sta=4998.8,5007.8
XS Rating Curve= 0 ,0
Exp/Cntr=0.3,0.1

Type RM Length L Ch R = 1 ,85722   ,458,458,458
BEGIN DESCRIPTION:
West Fork 147.0
END DESCRIPTION:
XS GIS Cut Line= 3
      2183186.08     13832621.75        2182025.       13832375.
      2181625.02       13832425.
#Sta/Elev= 30
  3808.2 1225.44  3865.1 1220.64  3901.3 1215.06  3909.6 1212.02  3921.8 1211.18
  4126.2  1200.1  4276.5 1193.69  4381.8  1189.7  4412.5 1191.01    4440 1188.39
  4476.7 1187.44  4543.8 1185.79  4760.1 1181.89  4933.7 1182.19  4954.3 1182.49
  4970.4 1179.39  5000.7 1178.73  5001.2 1178.23  5009.8 1178.73    5033 1179.23
  5055.7 1182.63  5076.8  1181.6  5126.2 1182.06  5166.5 1184.38  5210.8 1191.53
  5237.1 1196.94  5276.1 1200.25  5375.8 1209.42  5388.2 1212.73  5398.3 1213.73
#Mann= 11 ,-1 , 0
  3808.2     .07       0  4276.5    .035       0  4476.7     .07       0
  4543.8    .035       0  4933.7     .12       0  5000.7     .05       0
  5009.8     .12       0  5076.8     .07       0  5210.8    .035       0
  5276.1     .07       0  5375.8    .035       0
Bank Sta=5000.7,5009.8
XS Rating Curve= 0 ,0
Exp/Cntr=0.3,0.1

Type RM Length L Ch R = 1 ,85264   ,372,372,372
BEGIN DESCRIPTION:
H21674
END DESCRIPTION:
XS GIS Cut Line= 3
      2183112.83     13832365.45      2181909.83     13831905.18
      2181236.03     13831779.82
#Sta/Elev= 30
  3835.4 1218.76  3904.6 1209.92  4159.1 1198.31  4213.8 1194.33  4268.6 1192.07
  4298.6 1192.56  4341.9 1189.17  4443.5 1184.89  4491.6 1185.54  4547.7 1182.61
  4717.3 1179.69  4886.9  1179.2  4941.6 1180.49  4978.7 1175.02  4997.2 1174.88
  4997.7 1174.38  5006.3 1174.88  5032.3  1178.6  5096.5 1182.27  5117.9 1185.06
  5368.9 1201.12  5413.2 1203.58  5474.2 1203.73    5525 1209.44  5545.4 1208.39
  5555.6 1211.73  5664.3 1220.36  5695.7 1224.37  5779.3  1231.1  5808.8 1236.07
#Mann= 5 ,-1 , 0
  3835.4     .07       0  4341.9    .035       0  4997.2    .035       0
  5006.3    .035       0  5664.3     .12       0
Bank Sta=4997.2,5006.3
XS Rating Curve= 0 ,0
Exp/Cntr=0.3,0.1

Type RM Length L Ch R = 1 ,84892   ,643,643,643
BEGIN DESCRIPTION:
H21673
END DESCRIPTION:
XS GIS Cut Line= 5
      2183238.33     13831967.94      2182343.96     13831680.27
      2182019.67     13831648.89      2181271.73     13831497.21
      2181158.36      13831486.9
#Sta/Elev= 30
  3900.5 1246.63  3992.5 1240.39  4019.4 1234.13  4024.6 1235.85  4030.1 1233.46
  4056.7 1230.09    4094 1228.43    4153 1221.93  4158.2 1222.84  4222.4 1216.17
  4249.2 1210.77  4312.4 1206.16  4397.7 1201.78    4447  1193.7  4484.3 1192.27
  4578.3 1182.74  4618.3  1179.5  4660.3 1178.86  4945.5 1178.82  5025.2 1170.23
  5025.7 1169.73  5034.5 1170.23  5140.4 1179.97    5344 1186.47  5650.1 1206.56
  5715.1 1208.51  5774.2 1215.95    5844 1223.46    5929 1229.38  6042.8 1243.93
#Mann= 6 ,-1 , 0
  3900.5     .12       0  4312.4     .07       0  4578.3    .035       0
  5025.2    .035       0  5034.5    .035       0  5774.2     .07       0
Bank Sta=5025.2,5034.5
XS Rating Curve= 0 ,0
Exp/Cntr=0.3,0.1