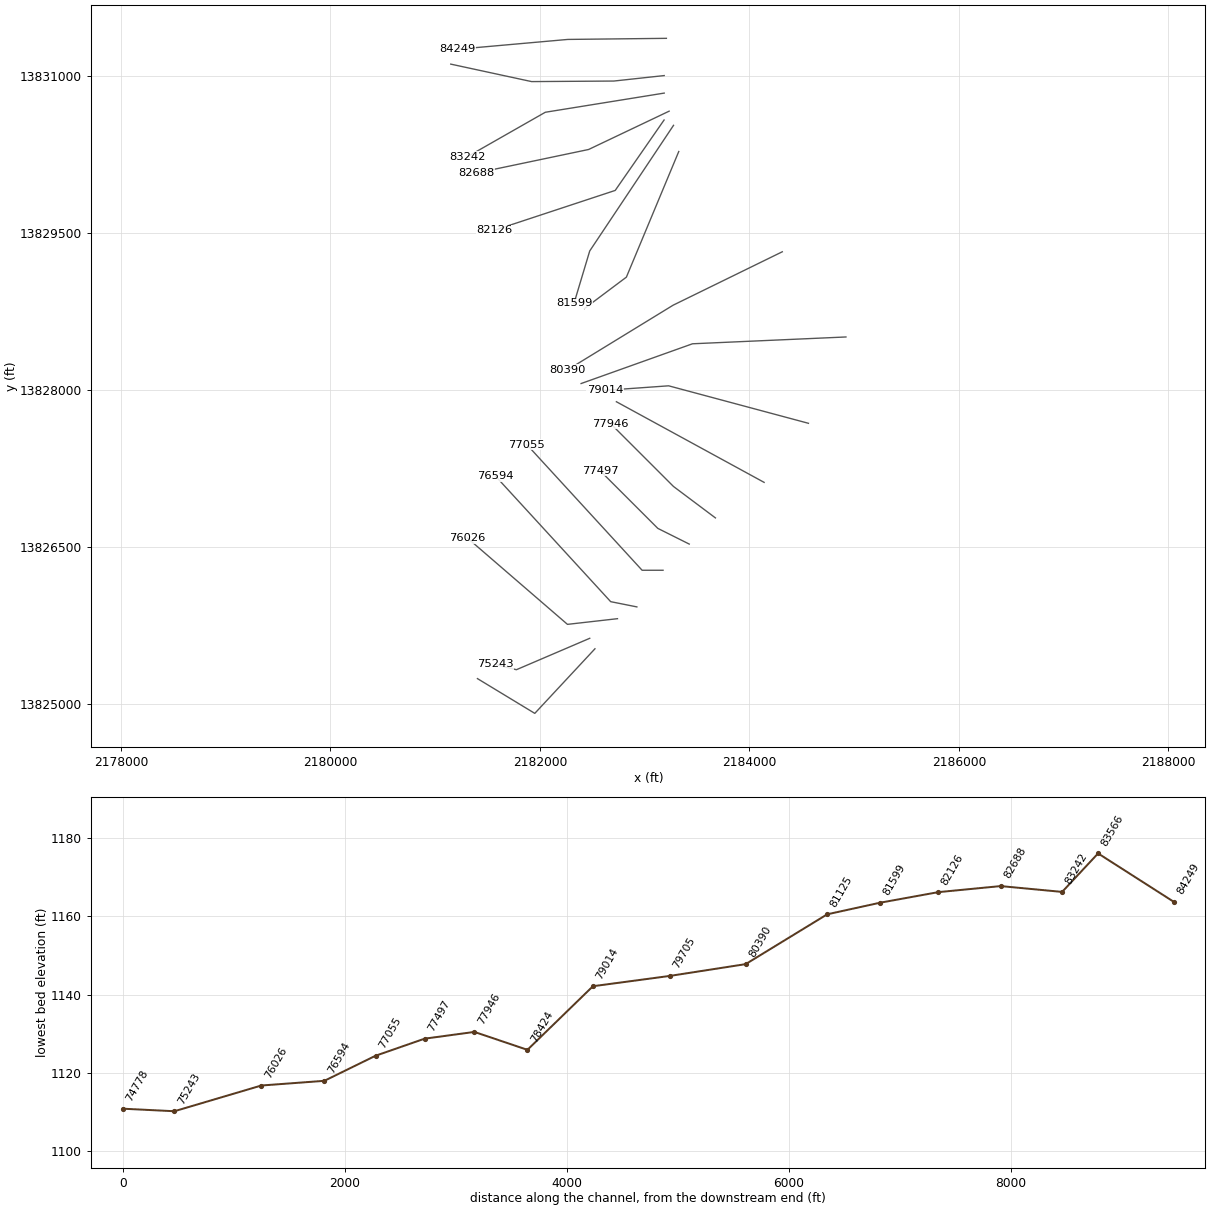
HEC-RAS study West Fork Dry Comal Creek.prj: West Fork Dry Comal Creek

--- West Fork Dry Comal Creek.g01 (geometry) --- (continued)

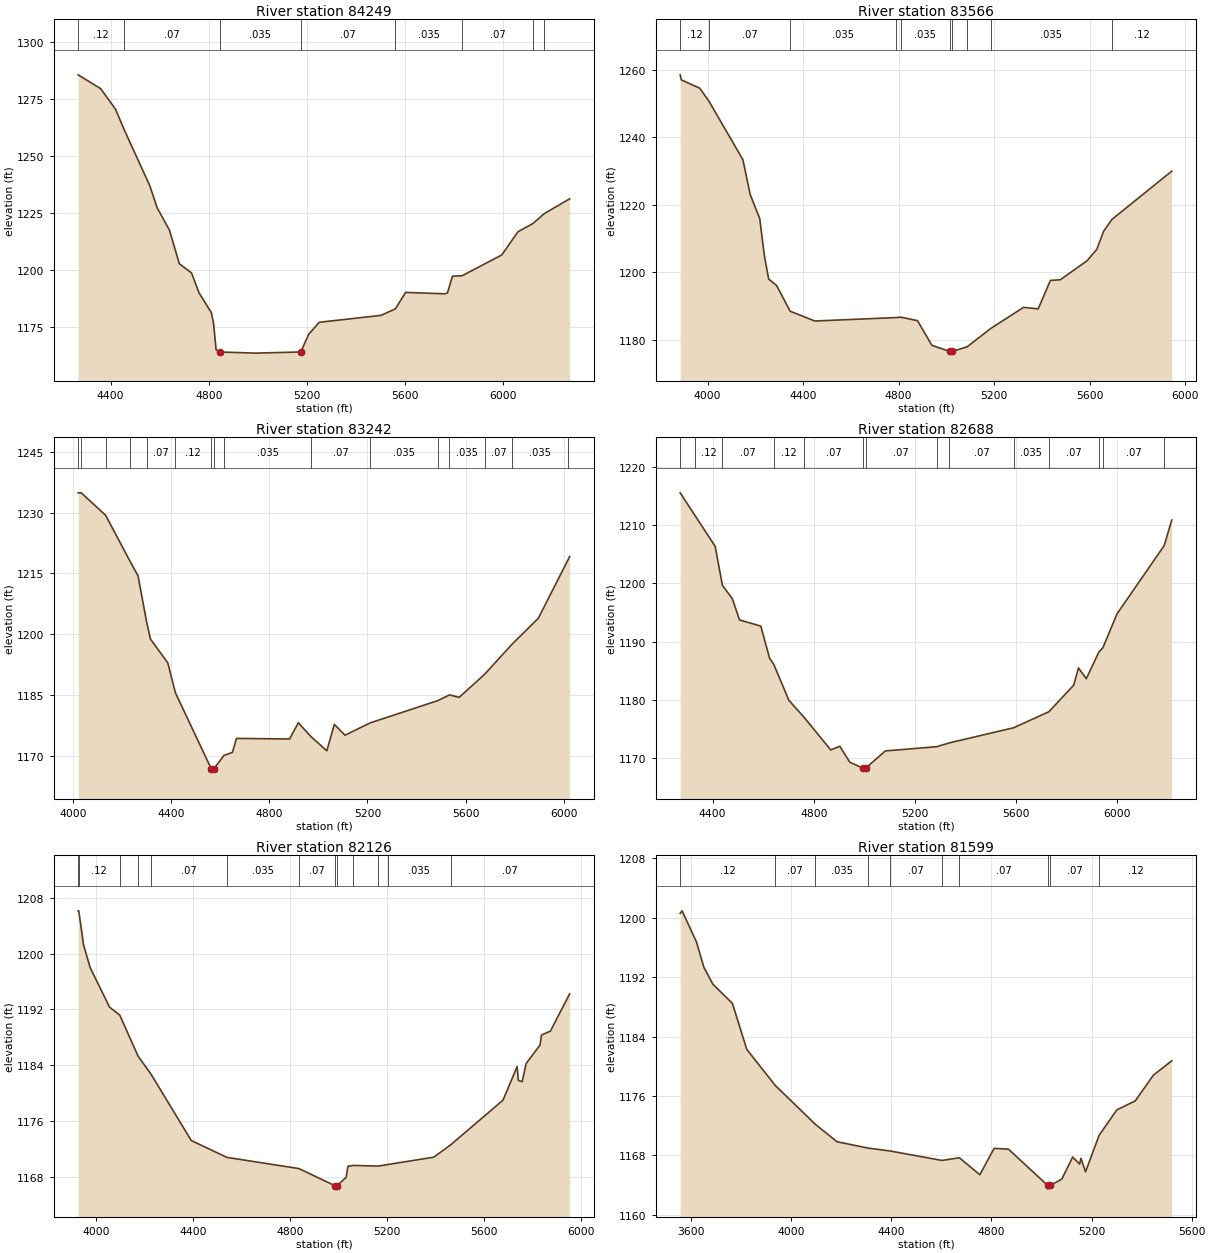
Type RM Length L Ch R = 1 ,84249   ,683,683,683
BEGIN DESCRIPTION:
H21672
END DESCRIPTION:
XS GIS Cut Line= 3
      2183206.93     13831355.99       2182265.5     13831345.53
      2181209.47     13831251.43
#Sta/Elev= 30
  4267.7 1285.54  4359.6 1279.48  4419.6 1270.57  4455.6 1261.46  4559.6 1237.01
  4589.6 1227.34  4639.6 1217.55  4679.7 1202.89  4729.7 1198.78  4759.7 1190.17
  4810.7 1181.34  4819.7 1176.35  4829.7 1165.16  4844.1  1164.2    4989  1163.7
  5174.4  1164.2  5206.9 1172.01  5249.8  1177.2  5501.3 1180.23    5560 1183.11
  5601.2 1190.28  5761.9 1189.67  5771.9  1190.1    5792 1197.39  5831.6 1197.59
  5992.8 1206.66  6059.1 1216.85  6119.9 1220.45  6165.5 1224.73  6269.4 1231.26
#Mann= 8 ,-1 , 0
  4267.7     .12       0  4455.6     .07       0  4844.1    .035       0
  5174.4     .07       0    5560    .035       0  5831.6     .07       0
  6119.9    .035       0  6165.5     .07       0
Bank Sta=4844.1,5174.4
XS Rating Curve= 0 ,0
Exp/Cntr=0.3,0.1

Type RM Length L Ch R = 1 ,83566   ,324,324,324
BEGIN DESCRIPTION:
H21671
END DESCRIPTION:
XS GIS Cut Line= 4
      2183186.04     13831000.32      2182704.85     13830948.02
      2181920.29     13830942.79      2181148.43     13831109.68
#Sta/Elev= 30
  3885.6 1258.51  3890.1 1257.02  3967.1 1254.57  4004.7 1250.86  4148.2 1233.38
  4178.4 1223.13  4218.6 1215.95  4238.7 1204.67  4256.3 1198.02    4289 1196.16
  4346.2  1188.5  4449.5 1185.61  4787.5 1186.62  4809.4 1186.75  4879.5 1185.71
  4939.5 1178.41  5014.7  1176.6  5015.2  1176.1  5024.2  1176.6  5086.8 1177.96
  5186.2 1183.41  5323.3 1189.65  5384.7 1189.21  5435.9 1197.63  5477.1 1197.82
  5589.3 1203.45  5630.2 1206.83  5658.7 1212.19  5693.5  1215.7  5943.9 1229.98
#Mann= 10 ,-1 , 0
  3885.6     .12       0  4004.7     .07       0  4346.2    .035       0
  4787.5     .07       0  4809.4    .035       0  5014.7    .035       0
  5024.2    .035       0  5086.8     .07       0  5186.2    .035       0
  5693.5     .12       0
Bank Sta=5014.7,5024.2
XS Rating Curve= 0 ,0
Exp/Cntr=0.3,0.1

Type RM Length L Ch R = 1 ,83242   ,554,554,554
BEGIN DESCRIPTION:
H21670
END DESCRIPTION:
XS GIS Cut Line= 3
      2183186.08     13830832.96      2182051.05     13830649.89
      2181309.16     13830226.69
#Sta/Elev= 30
  4020.7 1234.84  4033.6 1234.86  4132.9 1229.33  4232.2    1218  4264.9 1214.41
  4300.2 1202.97  4315.5 1198.82  4386.4 1192.94    4417 1185.62    4564 1166.75
  4564.5 1166.25  4573.5 1166.75  4615.1 1170.12  4649.8 1170.86  4666.1 1174.31
  4882.8 1174.18  4918.4 1178.18  4971.6 1174.67  5034.7 1171.26  5065.1 1177.78
  5108.8 1175.11  5210.9 1178.13  5486.5 1183.62  5534.6 1185.04  5574.2 1184.44
    5678 1190.13  5789.5 1197.53  5896.8 1203.93  6017.2 1218.27  6024.5 1219.14
#Mann= 16 ,-1 , 0
  4020.7     .12       0  4033.6     .07       0  4132.9    .035       0
  4232.2     .12       0  4300.2     .07       0    4417     .12       0
    4564     .05       0  4573.5     .12       0  4615.1    .035       0
  4971.6     .07       0  5210.9    .035       0  5486.5     .07       0
  5534.6    .035       0    5678     .07       0  5789.5    .035       0
  6017.2     .07       0
Bank Sta=4564,4573.5
XS Rating Curve= 0 ,0
Exp/Cntr=0.3,0.1

Type RM Length L Ch R = 1 ,82688   ,562,562,562
BEGIN DESCRIPTION:
H21669
END DESCRIPTION:
XS GIS Cut Line= 3
      2183233.12     13830660.35      2182464.25     13830294.22
      2181393.64     13830069.65
#Sta/Elev= 30
  4271.5 1215.56  4331.1  1211.6  4409.9 1206.37  4438.7 1199.65    4478 1197.36
  4506.2 1193.72  4590.6 1192.66  4625.3 1187.14  4642.2 1186.06  4701.4 1179.93
  4761.4 1177.01  4867.5 1171.38  4903.3 1172.01  4943.2 1169.26  4995.7 1168.24
  4996.2 1167.74  5005.2 1168.24  5083.5 1171.21  5286.9 1171.94  5336.7 1172.59
  5591.8  1175.2  5730.6 1177.94    5829 1182.51  5847.8 1185.46  5878.9 1183.62
  5928.3 1188.18  5944.7 1188.97    6001  1194.8  6187.1 1206.49    6217 1210.87
#Mann= 14 ,-1 , 0
  4271.5    .035       0  4331.1     .12       0  4438.7     .07       0
  4642.2     .12       0  4761.4     .07       0  4995.7     .05       0
  5005.2     .07       0  5286.9    .035       0  5336.7     .07       0
  5591.8    .035       0  5730.6     .07       0  5928.3    .035       0
  5944.7     .07       0  6187.1    .035       0
Bank Sta=4995.7,5005.2
XS Rating Curve= 0 ,0
Exp/Cntr=0.3,0.1

Type RM Length L Ch R = 1 ,82126   ,527,527,527
BEGIN DESCRIPTION:
H21664
END DESCRIPTION:
XS GIS Cut Line= 3
      2183184.79     13830575.86      2182718.24     13829903.15
      2181569.03      13829523.7
#Sta/Elev= 30
  3925.2 1206.16  3927.9 1206.16  3947.8 1201.25  3974.9    1198  4055.2 1192.32
  4097.1 1191.18  4172.6  1185.3  4226.5 1182.68  4392.3 1173.17  4539.5 1170.75
  4836.9 1169.14  4984.6 1166.69  4985.1 1166.19  4994.3 1166.69  5031.6 1167.89
  5038.9 1169.48  5061.8 1169.59  5164.6  1169.5    5203 1169.72  5393.4 1170.78
    5463 1172.55  5679.1 1178.97  5737.2 1183.79  5742.5 1181.81  5758.3 1181.62
  5774.3 1184.22    5832 1186.89  5837.8 1188.32  5874.8 1188.89  5954.1 1194.24
#Mann= 13 ,-1 , 0
  3925.2    .035       0  3927.9     .12       0  4097.1     .07       0
  4172.6     .12       0  4226.5     .07       0  4539.5    .035       0
  4836.9     .07       0  4984.6     .05       0  4994.3     .07       0
  5061.8    .035       0  5164.6     .07       0    5203    .035       0
    5463     .07       0
Bank Sta=4984.6,4994.3
XS Rating Curve= 0 ,0
Exp/Cntr=0.3,0.1

Type RM Length L Ch R = 1 ,81599   ,474,474,474
BEGIN DESCRIPTION:
West Fork 139.0
END DESCRIPTION:
XS GIS Cut Line= 3
      2183275.01     13830525.01        2182475.       13829325.
      2182325.01     13828825.04
#Sta/Elev= 30
  3556.2 1200.58  3563.7 1200.91  3620.8 1196.76  3650.9 1193.31  3686.9 1191.04
    3765 1188.45  3822.1 1182.28  3935.5 1177.44  4096.6 1172.18  4182.7 1169.85
  4306.6 1168.99  4395.1  1168.6  4602.5 1167.33  4671.8 1167.69  4753.6 1165.41
  4810.6 1168.95  4867.7 1168.85  5024.9 1163.97  5025.4 1163.47  5034.7 1163.97
  5081.1 1164.82  5124.6 1167.78  5152.4 1166.85  5157.6 1167.62  5175.9  1165.8
  5230.4 1170.72  5301.2 1174.14  5374.3 1175.33  5447.4 1178.81  5520.4 1180.73
#Mann= 10 ,-1 , 0
  3556.2     .12       0  3935.5     .07       0  4096.6    .035       0
  4306.6     .12       0  4395.1     .07       0  4602.5    .035       0
  4671.8     .07       0  5024.9     .05       0  5034.7     .07       0
  5230.4     .12       0
Bank Sta=5024.9,5034.7
XS Rating Curve= 0 ,0
Exp/Cntr=0.3,0.1

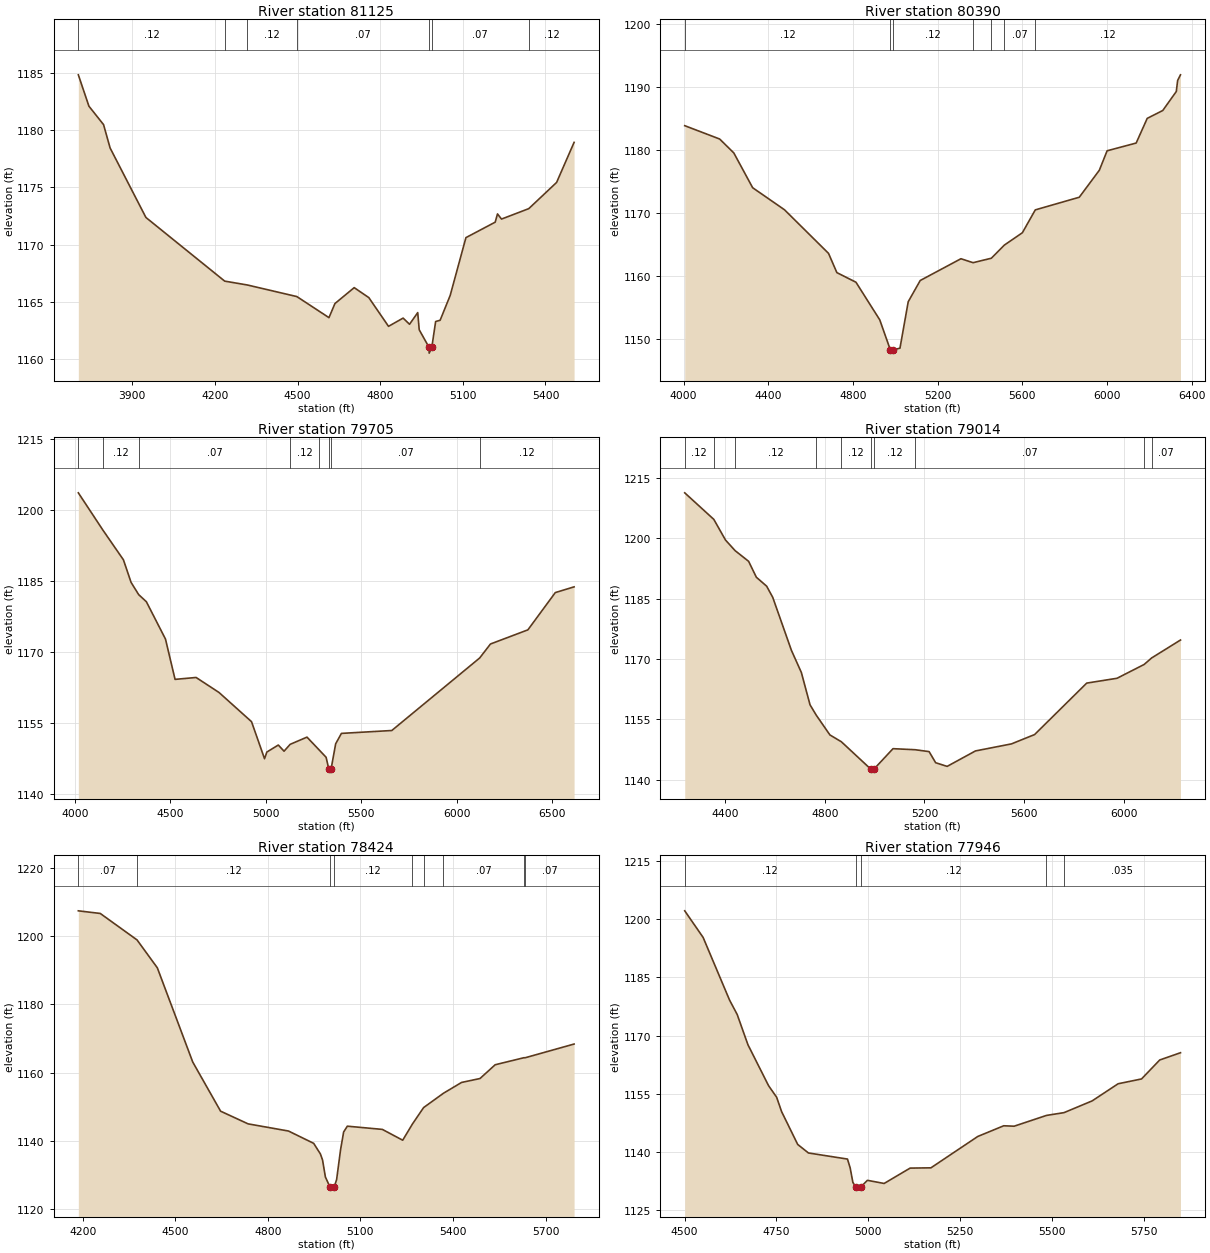
Type RM Length L Ch R = 1 ,81125   ,735,735,735
BEGIN DESCRIPTION:
West Fork 138.0
END DESCRIPTION:
XS GIS Cut Line= 3
      2183325.01     13830275.02        2182825.       13829075.
      2182425.02     13828775.02
#Sta/Elev= 30
  3703.9 1184.83  3742.4 1182.09  3795.5 1180.48  3819.3 1178.44  3949.3 1172.37
  4235.3 1166.81    4318 1166.47  4497.3 1165.46  4613.9 1163.62  4635.6 1164.85
  4705.5 1166.24  4758.6 1165.37  4830.1 1162.86  4883.1 1163.58  4906.4 1163.04
  4936.2 1164.06  4941.6 1162.56  4977.3 1161.02  4977.8 1160.52  4987.3 1161.02
  5001.2 1163.28  5017.5 1163.39  5053.9 1165.55  5111.2 1170.61  5217.5 1171.96
  5225.8 1172.68  5240.4 1172.23  5339.3 1173.14  5440.4 1175.43  5503.9 1178.93
#Mann= 7 ,-1 , 0
  3703.9     .12       0  4235.3     .07       0    4318     .12       0
  4497.3     .07       0  4977.3     .05       0  4987.3     .07       0
  5339.3     .12       0
Bank Sta=4977.3,4987.3
XS Rating Curve= 0 ,0
Exp/Cntr=0.3,0.1

Type RM Length L Ch R = 1 ,80390   ,685,685,685
BEGIN DESCRIPTION:
H21668
END DESCRIPTION:
XS GIS Cut Line= 3
       2184313.3     13829317.22      2183271.62     13828807.23
      2182263.52     13828189.37
#Sta/Elev= 30
  4005.2 1183.91  4170.3 1181.79  4237.1 1179.58  4326.2 1174.05  4476.5 1170.55
  4684.6 1163.62    4724 1160.56  4814.1 1159.04  4926.6 1153.06  4976.8 1148.27
  4977.3 1147.77  4989.4 1148.27  5022.1 1148.56  5061.1 1155.94  5117.8 1159.31
  5310.2 1162.77  5367.4 1162.14  5453.9 1162.85    5515 1164.93  5600.4  1166.9
  5661.4 1170.53  5869.2 1172.54    5964 1176.83  6000.7 1179.92    6138 1181.15
  6190.2 1185.07  6263.6 1186.32  6327.6 1189.34  6333.9 1191.09  6347.4 1191.99
#Mann= 7 ,-1 , 0
  4005.2     .12       0  4976.8     .05       0  4989.4     .12       0
  5367.4     .07       0  5453.9     .12       0    5515     .07       0
  5661.4     .12       0
Bank Sta=4976.8,4989.4
XS Rating Curve= 0 ,0
Exp/Cntr=0.3,0.1

Type RM Length L Ch R = 1 ,79705   ,691,691,691
BEGIN DESCRIPTION:
H21667
END DESCRIPTION:
XS GIS Cut Line= 3
       2184920.9     13828503.41      2183456.08     13828438.31
      2182392.73     13828058.54
#Sta/Elev= 30
  4018.9 1203.53  4147.7 1195.65    4255 1189.38  4295.1 1184.61  4334.8 1182.03
  4375.1 1180.53  4475.2 1172.64  4525.3 1164.13  4635.4 1164.53  4755.5 1161.36
  4925.7 1155.19  4993.7 1147.37  5005.8 1148.78  5065.8 1150.26  5095.9 1148.96
    5128 1150.41    5216 1151.93  5277.7 1149.31  5316.1 1147.67  5329.7 1145.25
  5330.2 1144.75  5342.4 1145.25  5366.1 1150.52  5396.2 1152.72    5660 1153.33
  6120.1 1168.65  6176.5  1171.6  6372.5 1174.59  6515.9 1182.46  6614.3 1183.67
#Mann= 8 ,-1 , 0
  4018.9     .07       0  4147.7     .12       0  4334.8     .07       0
    5128     .12       0  5277.7     .07       0  5329.7     .05       0
  5342.4     .07       0  6120.1     .12       0
Bank Sta=5329.7,5342.4
XS Rating Curve= 0 ,0
Exp/Cntr=0.3,0.1

Type RM Length L Ch R = 1 ,79014   ,590,590,590
BEGIN DESCRIPTION:
H21666
END DESCRIPTION:
XS GIS Cut Line= 3
      2184562.86     13827678.76      2183228.22     13828036.83
       2182620.6     13827993.43
#Sta/Elev= 30
  4237.5  1211.3  4354.3  1204.7  4401.4 1199.55    4440 1196.92  4494.1 1194.27
  4525.2 1190.31  4566.6 1188.09    4591 1185.31  4665.9 1172.16  4705.9 1166.64
  4740.7 1158.61  4765.6 1156.04  4820.7 1151.11  4866.4 1149.43  4984.7 1142.62
  4985.2 1142.12  4997.5 1142.62  5073.9  1147.7  5162.9 1147.44  5218.9 1146.97
  5245.2 1144.21  5291.4  1143.3  5405.2 1147.14  5549.7 1148.89  5642.6 1151.21
  5851.9    1164  5973.5  1165.2  6082.4 1168.63  6112.8 1170.26  6228.5 1174.71
#Mann= 10 ,-1 , 0
  4237.5     .12       0  4354.3     .07       0    4440     .12       0
  4765.6     .07       0  4866.4     .12       0  4984.7     .05       0
  4997.5     .12       0  5162.9     .07       0  6082.4     .12       0
  6112.8     .07       0
Bank Sta=4984.7,4997.5
XS Rating Curve= 0 ,0
Exp/Cntr=0.3,0.1

Type RM Length L Ch R = 1 ,78424   ,478,478,478
BEGIN DESCRIPTION:
H21665
END DESCRIPTION:
XS GIS Cut Line= 2
      2184139.72      13827114.5      2182729.53     13827884.68
#Sta/Elev= 30
  4185.7 1207.43  4256.8 1206.66    4376  1198.9  4441.8 1190.72  4556.6 1163.09
  4646.8  1148.7    4736 1144.98  4866.9 1142.88  4948.5 1139.27  4970.3 1136.16
  4977.3 1134.37  4986.5  1129.4  5001.8 1126.35  5002.3 1125.85  5014.7 1126.35
  5022.9 1128.68  5035.8 1137.51  5045.6  1142.6  5057.6  1144.3    5171 1143.36
    5237 1140.19  5268.6 1144.94  5304.7 1149.75  5369.2 1153.96  5427.7 1157.12
  5487.5 1158.27  5536.8 1162.31  5630.4 1164.38  5633.1 1164.34  5792.5 1168.38
#Mann= 9 ,-1 , 0
  4185.7     .07       0    4376     .12       0  5001.8     .05       0
  5014.7     .12       0  5268.6     .07       0  5304.7     .12       0
  5369.2     .07       0  5630.4    .035       0  5633.1     .07       0
Bank Sta=5001.8,5014.7
XS Rating Curve= 0 ,0
Exp/Cntr=0.3,0.1

Type RM Length L Ch R = 1 ,77946   ,449,449,449
BEGIN DESCRIPTION:
West Fork 132.0
END DESCRIPTION:
XS GIS Cut Line= 3
        2183675.       13826775.        2183275.       13827075.
      2182675.02     13827674.98
#Sta/Elev= 30
  4500.4 1202.17  4550.4 1195.32  4622.3 1179.17  4643.1 1175.45  4672.3 1167.66
  4728.5 1157.09  4750.4 1154.12  4763.9 1150.41  4807.7 1141.95  4836.9 1139.75
  4943.1 1138.18  4950.4 1135.91  4957.7 1132.19  4965.8 1130.93  4966.3 1130.43
  4978.7 1130.93  4997.3  1132.7  5042.8 1131.89  5113.5 1135.85  5170.1 1135.92
  5297.4    1144  5368.1 1146.76  5396.4 1146.65  5484.4 1149.43  5532.2 1150.15
  5608.5 1153.17  5679.2 1157.59  5742.9 1158.83  5792.4 1163.72  5848.9 1165.59
#Mann= 5 ,-1 , 0
  4500.4     .12       0  4965.8     .05       0  4978.7     .12       0
  5484.4     .07       0  5532.2    .035       0
Bank Sta=4965.8,4978.7
XS Rating Curve= 0 ,0
Exp/Cntr=0.3,0.1

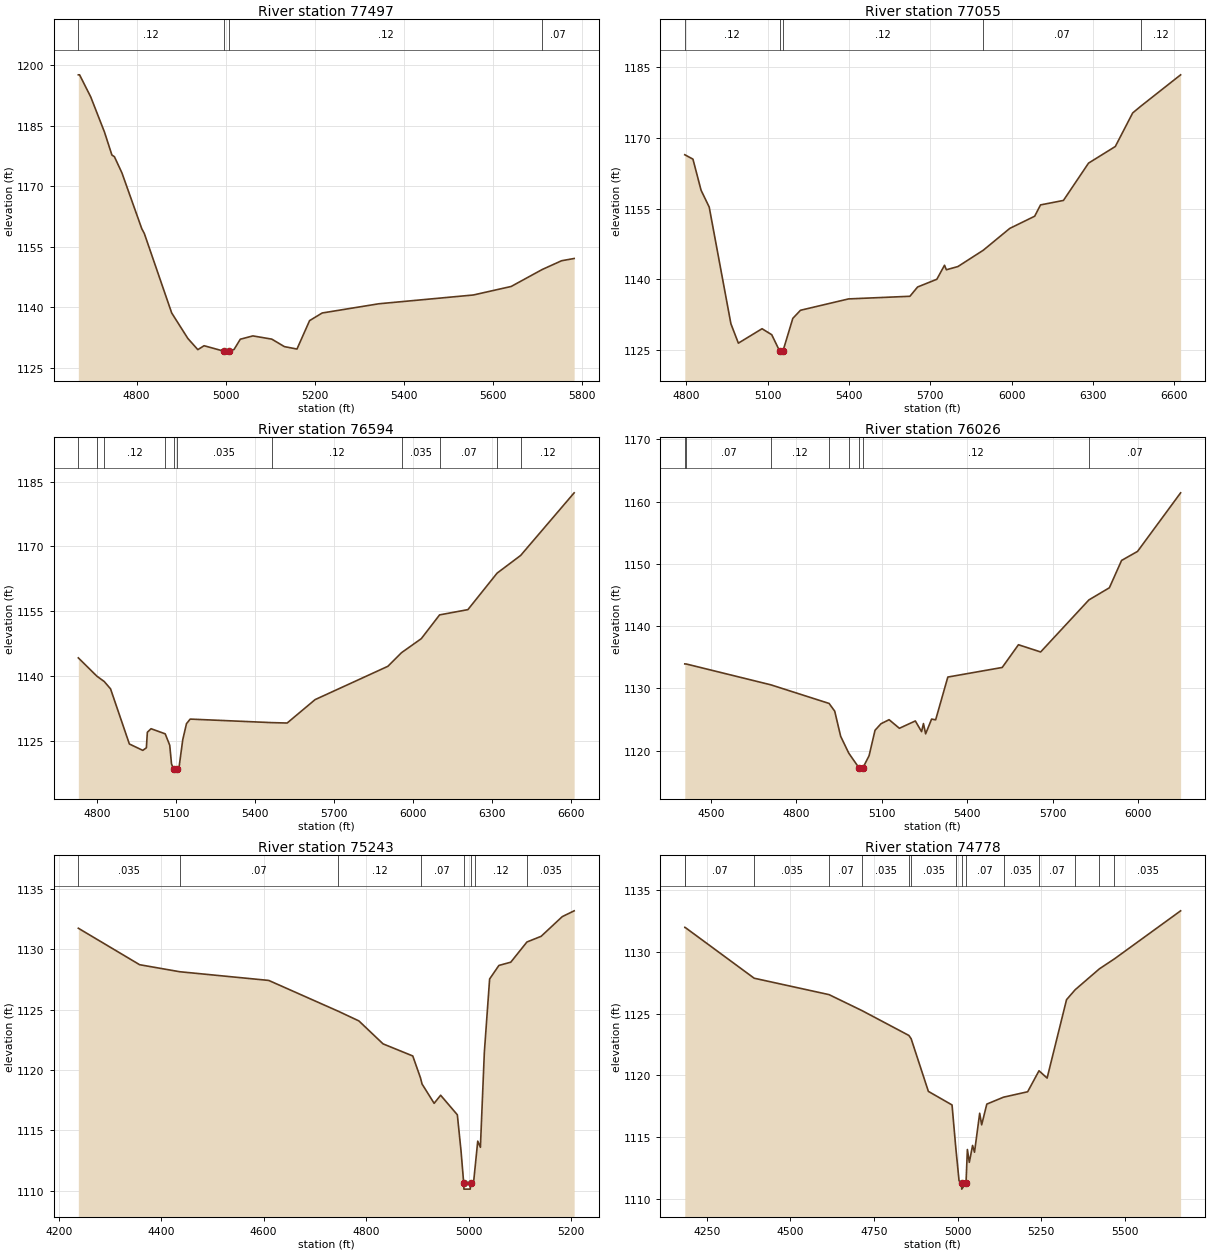
Type RM Length L Ch R = 1 ,77497   ,442,442,442
BEGIN DESCRIPTION:
West Fork 131.0
END DESCRIPTION:
XS GIS Cut Line= 3
      2183424.96     13826525.02        2183125.       13826675.
      2182574.99     13827225.01
#Sta/Elev= 30
  4669.2 1197.54    4672 1197.54  4697.1 1192.06  4727.9 1183.38  4744.6  1177.7
  4750.2 1177.29    4767 1173.31  4811.7 1159.46  4817.3 1158.31  4878.8 1138.64
  4915.1 1132.33  4937.5 1129.56  4951.5 1130.53  4995.3  1129.2  4995.8  1128.7
  5008.2  1129.2  5018.7 1129.59  5032.9 1132.14  5061.1 1132.96  5103.6 1132.16
  5131.8 1130.31  5160.1 1129.71  5188.4 1136.74  5216.7 1138.63    5344 1140.91
  5556.1 1143.08    5641 1145.19  5710.8 1149.39  5754.1 1151.55  5782.4 1152.11
#Mann= 4 ,-1 , 0
  4669.2     .12       0  4995.3     .05       0  5008.2     .12       0
  5710.8     .07       0
Bank Sta=4995.3,5008.2
XS Rating Curve= 0 ,0
Exp/Cntr=0.3,0.1

Type RM Length L Ch R = 1 ,77055   ,461,461,461
BEGIN DESCRIPTION:
West Fork 130.0
END DESCRIPTION:
XS GIS Cut Line= 3
      2183174.97       13826275.        2182975.       13826275.
      2181874.97     13827475.03
#Sta/Elev= 30
  4794.9 1166.45  4824.9 1165.52  4854.9 1158.92  4884.9 1155.34  4964.9 1130.56
  4992.4 1126.45  5079.7 1129.51  5115.4 1128.24  5144.1 1124.83  5144.6 1124.33
  5157.1 1124.83  5193.1 1131.71  5221.5 1133.43  5398.5 1135.84  5624.8  1136.4
  5653.1 1138.37    5724 1140.01  5752.4 1142.99  5759.2 1142.03  5801.7 1142.71
  5895.1 1146.17  5992.9 1150.81  6084.8  1153.4  6106.3  1155.8  6190.8 1156.75
  6283.3 1164.67    6382  1168.2  6446.1 1175.33  6476.5 1176.78  6622.8 1183.42
#Mann= 5 ,-1 , 0
  4794.9     .12       0  5144.1     .05       0  5157.1     .12       0
  5895.1     .07       0  6476.5     .12       0
Bank Sta=5144.1,5157.1
XS Rating Curve= 0 ,0
Exp/Cntr=0.3,0.1

Type RM Length L Ch R = 1 ,76594   ,568,568,568
BEGIN DESCRIPTION:
West Fork 129.0
END DESCRIPTION:
XS GIS Cut Line= 3
      2182925.01       13825925.        2182675.       13825975.
      2181575.03     13827174.97
#Sta/Elev= 30
  4729.7 1144.17  4800.3 1139.92  4827.9  1138.7  4852.1 1136.98  4923.5 1124.21
  4974.5 1122.73  4988.1 1123.33  4991.8 1126.93  5005.9 1127.75  5059.6 1126.56
  5076.8 1123.92  5083.6 1119.57  5091.3 1118.42  5091.8 1117.92  5104.3 1118.42
    5112 1118.72  5126.2  1125.2  5140.4 1128.92  5154.5 1129.98  5464.5 1129.16
  5522.7 1129.07  5628.7 1134.49    5905 1142.21  5957.1 1145.38    6032 1148.62
  6101.5 1154.13    6209 1155.35  6319.9 1163.81  6409.4 1167.91  6612.5 1182.42
#Mann= 11 ,-1 , 0
  4729.7     .12       0  4800.3     .07       0  4827.9     .12       0
  5059.6    .035       0  5091.3     .05       0  5104.3    .035       0
  5464.5     .12       0  5957.1    .035       0  6101.5     .07       0
  6319.9    .035       0  6409.4     .12       0
Bank Sta=5091.3,5104.3
XS Rating Curve= 0 ,0
Exp/Cntr=0.3,0.1

Type RM Length L Ch R = 1 ,76026   ,783,783,783
BEGIN DESCRIPTION:
H21663
END DESCRIPTION:
XS GIS Cut Line= 3
      2182739.91     13825812.44      2182262.51     13825758.19
      2181308.82     13826581.83
#Sta/Elev= 30
  4407.9 1133.94  4413.7 1133.92  4710.1 1130.58  4914.5 1127.59  4934.2 1126.35
  4955.1 1122.31  4983.5 1119.61  5019.8 1117.22  5020.3 1116.72  5032.8 1117.22
  5054.8 1119.19  5075.7 1123.28  5096.6 1124.33  5125.1 1124.98  5161.2  1123.6
  5217.2 1124.78  5239.1 1123.06  5245.7 1124.36  5253.4 1122.71  5274.3 1125.08
  5288.5 1124.96  5331.3 1131.83  5522.2 1133.37  5579.2 1137.02  5657.1 1135.86
  5826.5 1144.22  5898.4 1146.17  5941.2 1150.56  5997.2 1152.01  6148.5 1161.42
#Mann= 8 ,-1 , 0
  4407.9     .12       0  4413.7     .07       0  4710.1     .12       0
  4914.5     .07       0  4983.5     .12       0  5019.8     .05       0
  5032.8     .12       0  5826.5     .07       0
Bank Sta=5019.8,5032.8
XS Rating Curve= 0 ,0
Exp/Cntr=0.3,0.1

Type RM Length L Ch R = 1 ,75243   ,465,465,465
BEGIN DESCRIPTION:
West Fork 128.0
END DESCRIPTION:
XS GIS Cut Line= 3
      2182475.02     13825625.01        2181775.       13825325.
      2181574.96     13825375.01
#Sta/Elev= 30
  4238.3 1131.73    4358 1128.71  4436.2 1128.13    4610 1127.41  4745.7 1124.86
  4785.9 1124.06  4833.1 1122.16  4891.1 1121.16  4906.2 1119.34  4909.2 1118.84
  4932.8 1117.24  4945.5 1117.91  4978.1 1116.29  4985.4 1113.25  4990.5 1110.64
    4991 1110.14  5003.3 1110.14  5003.8 1110.64  5010.2 1110.87  5011.6 1111.46
  5017.9 1114.11  5023.1  1113.6  5030.8 1121.46  5041.1 1127.53  5059.2 1128.65
  5082.4 1128.92  5113.9 1130.59  5141.6 1131.06  5182.9 1132.69  5206.1 1133.17
#Mann= 8 ,-1 , 0
  4238.3    .035       0  4436.2     .07       0  4745.7     .12       0
  4906.2     .07       0  4990.5     .05       0  5003.8     .07       0
  5011.6     .12       0  5113.9    .035       0
Bank Sta=4990.5,5003.8
XS Rating Curve= 0 ,0
Exp/Cntr=0.3,0.1

Type RM Length L Ch R = 1 ,74778   ,491,491,491
BEGIN DESCRIPTION:
West Fork 127.0
END DESCRIPTION:
XS GIS Cut Line= 3
      2182524.97     13825524.97      2181950.59      13824907.9
      2181403.19     13825240.04
#Sta/Elev= 30
    4184    1132  4184.8    1132  4391.5 1127.88  4615.5 1126.55  4714.5 1125.25
  4854.5 1123.24  4861.2 1122.97  4912.7 1118.71  4983.5 1117.61  4994.6 1114.17
  5004.5 1111.46    5012 1111.29  5012.5 1110.79  5025.3 1111.29  5029.4    1114
  5035.2 1112.96  5044.9 1114.33  5050.7 1113.78  5066.2 1116.94  5072.1    1116
  5087.5 1117.68  5137.5 1118.24  5209.7 1118.68  5243.6 1120.38  5267.9 1119.79
    5326 1126.14    5352 1126.95  5424.3 1128.64  5469.4 1129.45  5667.3 1133.34
#Mann= 15 ,-1 , 0
    4184    .035       0  4184.8     .07       0  4391.5    .035       0
  4615.5     .07       0  4714.5    .035       0  4854.5     .07       0
  4861.2    .035       0  4994.6     .07       0    5012     .05       0
  5025.3     .07       0  5137.5    .035       0  5243.6     .07       0
    5352     .12       0  5424.3     .07       0  5469.4    .035       0
Bank Sta=5012,5025.3
XS Rating Curve= 0 ,0
Exp/Cntr=0.3,0.1