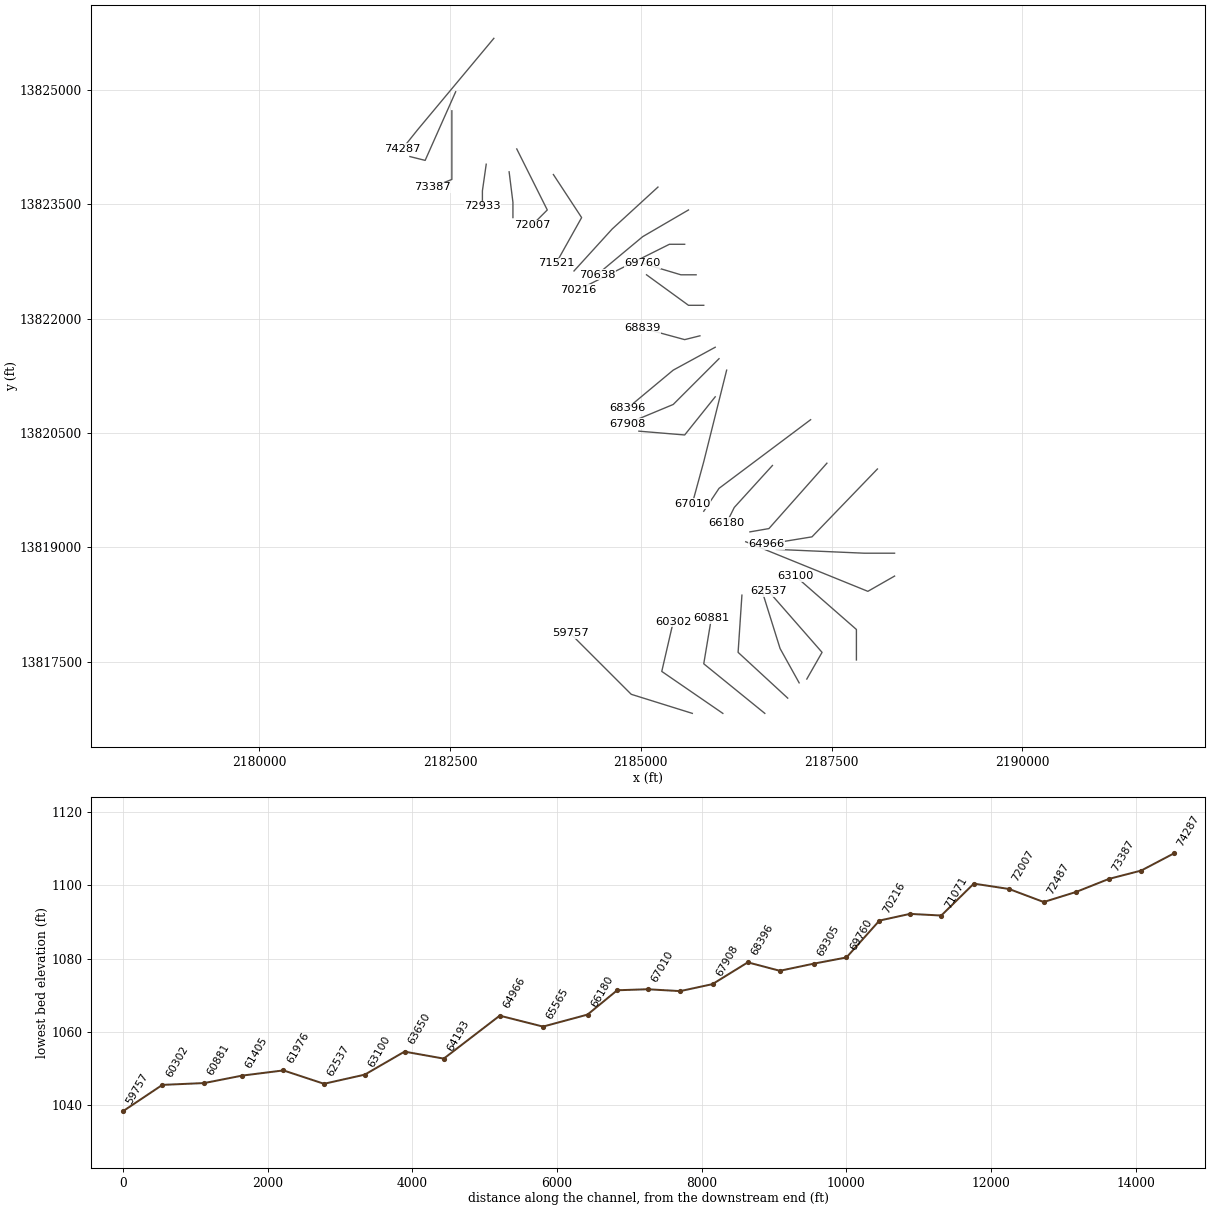
HEC-RAS study West Fork Dry Comal Creek.prj: West Fork Dry Comal Creek

--- West Fork Dry Comal Creek.g01 (geometry) --- (continued)

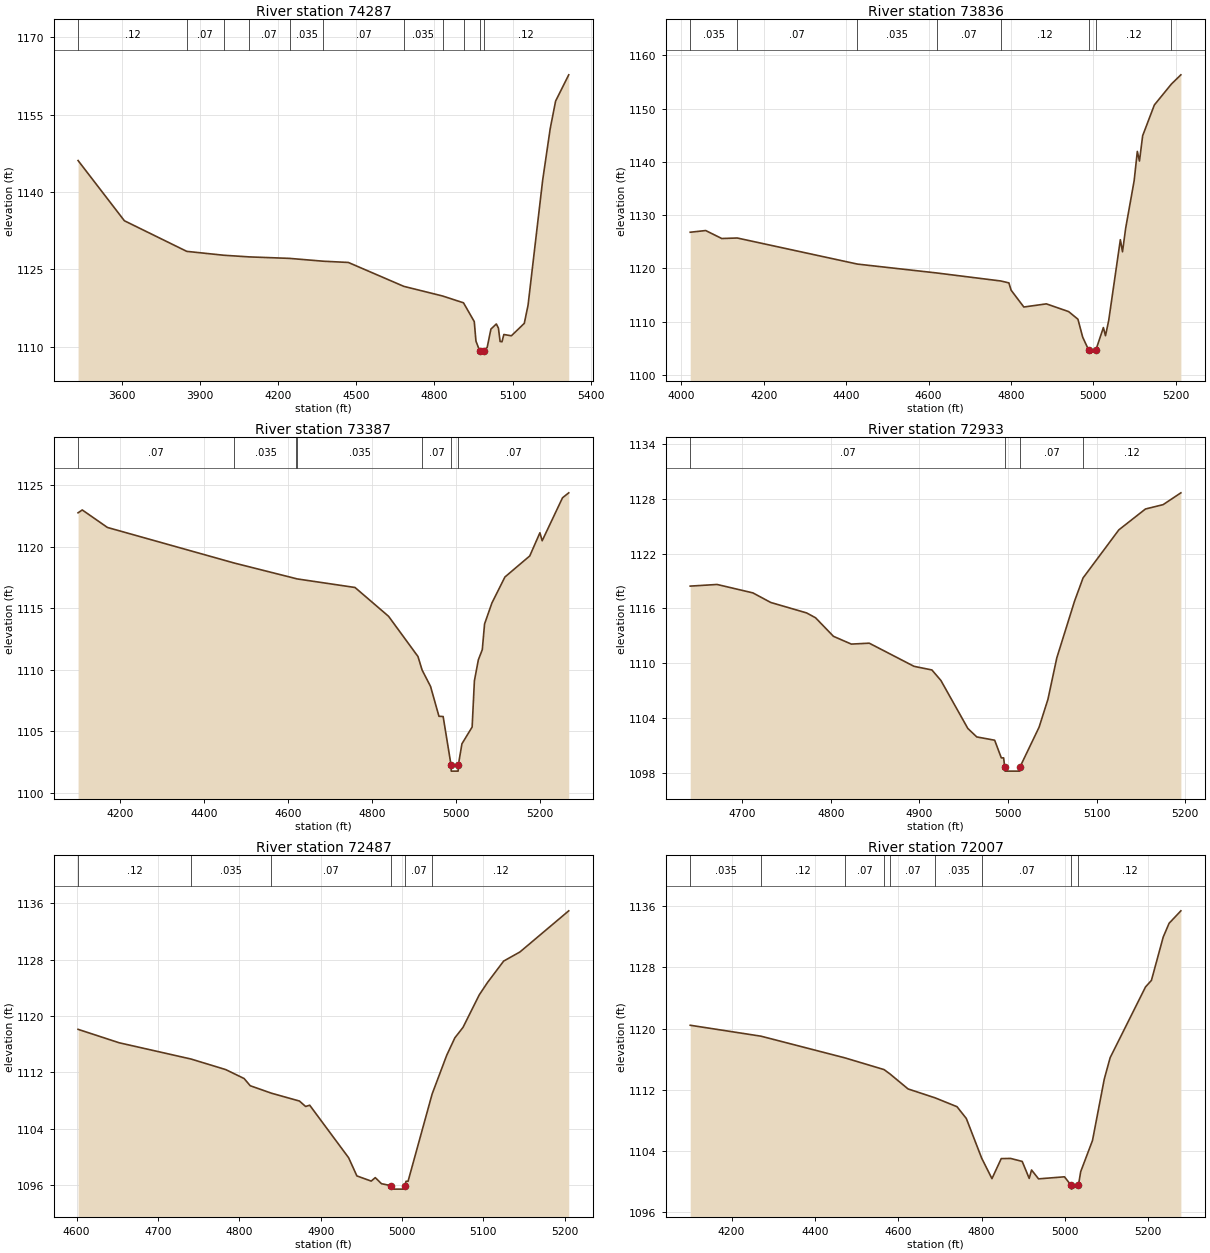
Type RM Length L Ch R = 1 ,74287   ,451,451,451
BEGIN DESCRIPTION:
West Fork 126.0
END DESCRIPTION:
XS GIS Cut Line= 3
      2183075.01     13825675.01        2182075.       13824475.
      2181875.01     13824225.01
#Sta/Elev= 30
  3432.9 1146.09  3610.6 1134.42  3849.8 1128.49  3991.5 1127.74  4088.9 1127.42
    4244 1127.13  4373.8 1126.58  4469.7 1126.34  4682.4 1121.71  4831.3 1119.84
  4911.4 1118.52  4952.7 1114.88  4959.2  1111.1    4973 1109.27  4973.5 1108.77
  4989.6 1109.27  5002.2 1109.87  5016.6 1113.43  5037.4 1114.42  5045.4 1113.61
  5051.8 1111.03    5059 1110.97  5066.2 1112.38    5095 1112.13  5144.6 1114.54
    5159 1118.05  5215.1 1142.29  5243.9 1152.24  5264.7 1157.61  5315.1  1162.7
#Mann= 11 ,-1 , 0
  3432.9     .12       0  3849.8     .07       0  3991.5     .12       0
  4088.9     .07       0    4244    .035       0  4373.8     .07       0
  4682.4    .035       0  4831.3     .07       0  4911.4     .12       0
    4973     .05       0  4989.6     .12       0
Bank Sta=4973,4989.6
XS Rating Curve= 0 ,0
Exp/Cntr=0.3,0.1

Type RM Length L Ch R = 1 ,73836   ,449,449,449
BEGIN DESCRIPTION:
West Fork 125.0
END DESCRIPTION:
XS GIS Cut Line= 3
      2182574.98     13824974.96        2182175.       13824075.
        2181975.       13824125.
#Sta/Elev= 30
  4021.5 1126.78  4059.1  1127.1  4098.1  1125.6  4135.5  1125.7  4427.4  1120.8
  4620.2 1119.13  4775.2 1117.63    4795 1117.27  4800.5 1115.89  4831.3 1112.74
    4886 1113.33    4940 1111.88  4962.6 1110.45  4974.2 1107.07  4989.2 1104.58
  4989.7 1104.08  5005.8 1104.58  5024.4 1108.88  5029.5 1107.35  5037.3 1110.21
  5065.6 1125.38  5070.8 1123.11  5078.5 1127.55  5099.1 1136.47  5106.8 1141.96
    5112 1140.15  5119.7  1144.9  5148.1 1150.68  5189.5 1154.61  5212.5 1156.34
#Mann= 8 ,-1 , 0
  4021.5    .035       0  4135.5     .07       0  4427.4    .035       0
  4620.2     .07       0  4775.2     .12       0  4989.2     .05       0
  5005.8     .12       0  5189.5     .07       0
Bank Sta=4989.2,5005.8
XS Rating Curve= 0 ,0
Exp/Cntr=0.3,0.1

Type RM Length L Ch R = 1 ,73387   ,454,454,454
BEGIN DESCRIPTION:
West Fork 124.0
END DESCRIPTION:
XS GIS Cut Line= 3
        2182525.     13824725.03        2182525.       13823825.
      2182274.99       13823725.
#Sta/Elev= 30
    4100 1122.74    4110 1122.97    4170 1121.55  4472.6 1118.66  4620.5 1117.39
  4621.2 1117.38    4760 1116.68    4840 1114.34    4910 1111.08  4919.9 1109.98
    4940 1108.65    4960 1106.23    4970 1106.21  4988.8 1102.28  4989.3 1101.78
  5005.7 1101.78  5006.2 1102.28  5014.8    1104  5039.1 1105.36  5044.5 1109.11
  5053.9 1110.81  5063.3 1111.64  5068.7 1113.72  5086.2 1115.42  5117.2 1117.53
  5176.4 1119.24  5200.6 1121.12    5206 1120.47  5254.5 1123.96  5269.3 1124.36
#Mann= 7 ,-1 , 0
    4100     .07       0  4472.6    .035       0  4620.5     .07       0
  4621.2    .035       0  4919.9     .07       0  4988.8     .05       0
  5006.2     .07       0
Bank Sta=4988.8,5006.2
XS Rating Curve= 0 ,0
Exp/Cntr=0.3,0.1

Type RM Length L Ch R = 1 ,72933   ,446,446,446
BEGIN DESCRIPTION:
West Fork 123.0
END DESCRIPTION:
XS GIS Cut Line= 3
        2182975.     13824025.01        2182925.       13823675.
        2182925.     13823474.96
#Sta/Elev= 30
  4641.4 1118.44  4671.7 1118.62  4712.1  1117.7  4732.3 1116.65  4772.7 1115.51
  4782.8 1114.98    4803 1112.95  4823.2  1112.1  4843.4  1112.2  4893.9 1109.67
  4914.1 1109.27  4924.2 1108.13  4954.6 1102.88  4964.7 1101.95  4984.9 1101.59
  4992.4 1099.66    4995 1099.66  4996.2 1098.71  4996.7 1098.21  5013.2 1098.21
  5013.7 1098.71    5035 1103.01    5045 1106.06    5055 1110.59    5075 1116.79
  5084.6 1119.33    5125 1124.59    5155 1126.87    5175 1127.35    5195 1128.64
#Mann= 4 ,-1 , 0
  4641.4     .07       0  4996.2     .05       0  5013.7     .07       0
  5084.6     .12       0
Bank Sta=4996.2,5013.7
XS Rating Curve= 0 ,0
Exp/Cntr=0.3,0.1

Type RM Length L Ch R = 1 ,72487   ,480,480,480
BEGIN DESCRIPTION:
West Fork 122.0
END DESCRIPTION:
XS GIS Cut Line= 3
        2183275.     13823925.01        2183325.       13823525.
        2183325.     13823325.02
#Sta/Elev= 30
  4601.8 1118.11  4652.2 1116.21  4740.7  1113.9  4783.2 1112.41  4805.9 1111.14
  4813.4 1110.12  4839.5 1109.06  4873.9 1107.95  4881.5 1107.18  4886.5 1107.36
  4934.4 1099.91  4944.5 1097.34  4962.1 1096.61  4967.1  1097.1  4974.7 1096.24
    4986 1095.97  4986.5 1095.47  5003.1 1095.47  5003.6 1095.97  5004.9 1096.58
  5007.4 1096.58    5037 1108.95  5054.9 1114.43  5064.9  1116.9  5074.9 1118.38
  5094.9 1122.99  5104.9 1124.72  5124.9 1127.78  5144.9 1129.07  5204.9  1134.9
#Mann= 6 ,-1 , 0
  4601.8     .12       0  4740.7    .035       0  4839.5     .07       0
    4986     .05       0  5003.6     .07       0    5037     .12       0
Bank Sta=4986,5003.6
XS Rating Curve= 0 ,0
Exp/Cntr=0.3,0.1

Type RM Length L Ch R = 1 ,72007   ,486,486,486
BEGIN DESCRIPTION:
West Fork 121.0
END DESCRIPTION:
XS GIS Cut Line= 3
      2183374.98     13824225.03        2183775.       13823425.
        2183575.       13823225.
#Sta/Elev= 30
  4100.9 1120.45  4270.9 1119.02    4472 1116.19  4565.9 1114.66  4580.4 1114.08
  4623.6 1112.13  4688.8 1110.96    4741 1109.81  4763.4 1108.27  4800.3 1103.08
  4824.9 1100.41  4847.2 1103.03  4869.6 1103.05  4897.5 1102.66  4914.3 1100.44
  4919.9 1101.54  4936.7 1100.38  4998.9 1100.65  5014.8 1099.54  5015.3 1099.04
  5032.4 1099.54  5037.8 1101.32  5066.1 1105.39  5094.4 1113.42  5108.5 1116.22
  5193.4 1125.46  5207.5 1126.31  5235.8 1131.97  5249.9 1133.77  5278.2  1135.4
#Mann= 9 ,-1 , 0
  4100.9    .035       0  4270.9     .12       0    4472     .07       0
  4565.9    .035       0  4580.4     .07       0  4688.8    .035       0
  4800.3     .07       0  5014.8     .05       0  5032.4     .12       0
Bank Sta=5014.8,5032.4
XS Rating Curve= 0 ,0
Exp/Cntr=0.3,0.1

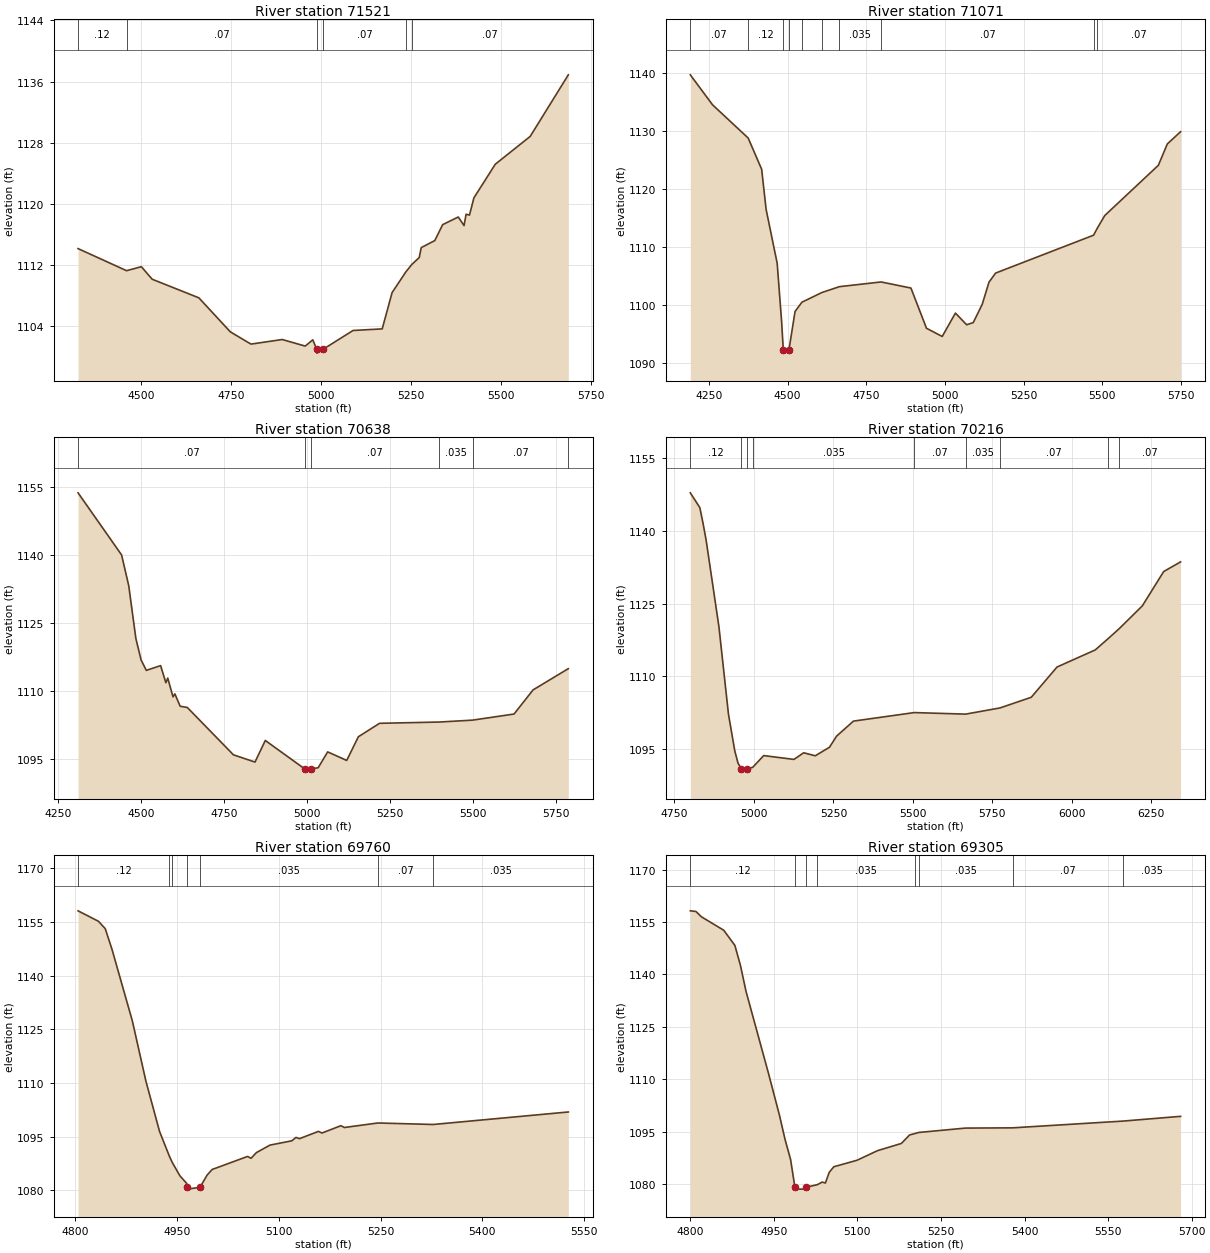
Type RM Length L Ch R = 1 ,71521   ,450,450,450
BEGIN DESCRIPTION:
West Fork 120.0
END DESCRIPTION:
XS GIS Cut Line= 3
      2183855.06     13823889.23        2184225.       13823325.
      2183889.58     13822725.33
#Sta/Elev= 30
  4325.3 1114.17    4460 1111.28  4501.1  1111.8  4531.3 1110.16  4660.9 1107.73
  4748.3 1103.28  4805.6 1101.68  4892.4 1102.28  4956.3 1101.42  4977.3 1102.24
  4988.2    1101  4988.7  1100.5  5005.8    1101  5089.1 1103.46  5170.1 1103.67
  5197.6 1108.42  5235.8 1111.12  5252.3 1112.09  5272.9    1113  5278.6  1114.3
  5316.3 1115.22    5338  1117.3  5381.4  1118.3  5397.4 1117.18  5403.1 1118.66
  5412.5 1118.55  5424.8  1120.8  5484.2  1125.2  5581.2 1128.84  5687.1 1136.89
#Mann= 6 ,-1 , 0
  4325.3     .12       0    4460     .07       0  4988.2     .05       0
  5005.8     .07       0  5235.8    .035       0  5252.3     .07       0
Bank Sta=4988.2,5005.8
XS Rating Curve= 0 ,0
Exp/Cntr=0.3,0.1

Type RM Length L Ch R = 1 ,71071   ,433,433,433
BEGIN DESCRIPTION:
West Fork 119.0
END DESCRIPTION:
XS GIS Cut Line= 3
      2185224.99     13823724.99        2184625.       13823175.
      2184125.02     13822625.02
#Sta/Elev= 30
  4191.2 1139.67  4261.8 1134.51    4375 1128.79  4417.8 1123.42    4432  1116.5
  4467.1 1107.24  4481.3 1097.13  4486.6 1092.27  4487.1 1091.77  4504.3 1092.27
  4523.9 1098.94  4545.8 1100.54  4609.1  1102.2  4664.8 1103.21  4797.3 1104.02
    4892 1102.97  4941.3 1096.05  4991.3 1094.64  5033.2 1098.66    5069 1096.65
  5089.9 1097.03  5118.3 1100.16  5139.9 1103.99  5160.9 1105.55  5472.1 1112.07
    5483 1113.19  5507.5 1115.45  5677.8  1124.1  5706.2 1127.77  5748.4 1129.88
#Mann= 10 ,-1 , 0
  4191.2     .07       0    4375     .12       0  4486.6     .05       0
  4504.3     .12       0  4545.8    .035       0  4609.1     .07       0
  4664.8    .035       0  4797.3     .07       0  5472.1    .035       0
    5483     .07       0
Bank Sta=4486.6,4504.3
XS Rating Curve= 0 ,0
Exp/Cntr=0.3,0.1

Type RM Length L Ch R = 1 ,70638   ,422,422,422
BEGIN DESCRIPTION:
West Fork 118.0
END DESCRIPTION:
XS GIS Cut Line= 3
      2185625.04     13823425.02        2185025.       13823075.
        2184425.       13822575.
#Sta/Elev= 30
  4310.6 1153.68  4441.7 1139.96  4463.2 1133.15  4484.7 1121.48  4500.4 1116.76
  4516.1 1114.47  4559.1 1115.52  4574.9 1111.74  4580.6 1112.77  4596.4 1108.62
  4602.1 1109.28  4617.9 1106.55  4639.4 1106.28  4778.3 1095.82  4843.2 1094.22
  4874.2 1098.99  4992.7 1092.72  4993.2 1092.22    5012 1092.72  5033.3 1092.96
  5061.9 1096.47  5119.2 1094.58  5154.3 1099.81  5218.1 1102.78  5397.5 1103.06
    5498 1103.48  5622.9 1104.83  5680.2 1110.16  5786.2 1114.85  5786.3 1114.85
#Mann= 6 ,-1 , 0
  4310.6     .07       0  4992.7     .05       0    5012     .07       0
  5397.5    .035       0    5498     .07       0  5786.2    .035       0
Bank Sta=4992.7,5012
XS Rating Curve= 0 ,0
Exp/Cntr=0.3,0.1

Type RM Length L Ch R = 1 ,70216   ,456,456,456
BEGIN DESCRIPTION:
West Fork 117.0
END DESCRIPTION:
XS GIS Cut Line= 3
      2185575.04       13822975.        2185375.       13822975.
      2184174.98     13822374.99
#Sta/Elev= 30
    4800 1147.86    4830  1144.8    4840 1141.59    4850 1137.99    4890  1120.2
    4920 1102.14    4940 1094.53    4950 1092.05  4960.4 1090.89  4960.9 1090.39
  4979.7 1090.89  4996.3 1091.18  5030.8  1093.6  5125.8 1092.81  5156.6 1094.18
  5192.9 1093.56  5237.6 1095.32    5260 1097.62  5313.1 1100.72  5504.4 1102.48
  5665.6 1102.16  5773.9 1103.44  5872.1 1105.64  5953.2 1111.89  6073.4 1115.42
  6113.5 1117.73  6148.7 1119.81  6221.5 1124.53  6288.6 1131.61  6341.7  1133.6
#Mann= 9 ,-1 , 0
    4800     .12       0  4960.4    .035       0  4979.7     .12       0
  4996.3    .035       0  5504.4     .07       0  5665.6    .035       0
  5773.9     .07       0  6113.5    .035       0  6148.7     .07       0
Bank Sta=4960.4,4979.7
XS Rating Curve= 0 ,0
Exp/Cntr=0.3,0.1

Type RM Length L Ch R = 1 ,69760   ,455,455,455
BEGIN DESCRIPTION:
West Fork 116.0
END DESCRIPTION:
XS GIS Cut Line= 3
      2185724.98       13822575.        2185525.       13822575.
      2185024.99       13822725.
#Sta/Elev= 30
  4804.6 1158.14  4834.6 1155.22  4844.6 1153.17  4854.6 1147.37  4884.6 1127.32
  4904.6 1110.45  4924.6 1096.45    4939 1089.55  4943.4 1087.74  4954.6 1084.02
  4964.6  1081.9  4964.9  1080.8  4965.4  1080.3  4984.2  1080.8  4994.6 1084.21
  5002.1  1085.8  5054.2 1089.44  5059.4 1088.93  5067.2 1090.51  5087.2 1092.61
  5119.4 1093.82  5125.5 1094.76  5130.7 1094.41  5158.6 1096.45  5163.8 1095.99
  5191.6 1098.04  5196.9 1097.54  5246.1  1098.8  5327.6 1098.38  5526.6 1101.88
#Mann= 7 ,-1 , 0
  4804.6     .12       0    4939     .07       0  4943.4    .035       0
  4964.9    .035       0  4984.2    .035       0  5246.1     .07       0
  5327.6    .035       0
Bank Sta=4964.9,4984.2
XS Rating Curve= 0 ,0
Exp/Cntr=0.3,0.1

Type RM Length L Ch R = 1 ,69305   ,466,466,466
BEGIN DESCRIPTION:
West Fork 115.0
END DESCRIPTION:
XS GIS Cut Line= 3
      2185824.99       13822175.        2185625.       13822175.
      2185074.97     13822575.02
#Sta/Elev= 30
  4800.1  1158.2  4810.1 1158.02  4820.1 1156.49  4860.1 1152.65  4880.1 1148.31
  4890.1 1142.59  4900.1 1135.17  4940.1  1111.9  4960.1 1099.75  4970.1 1092.84
  4980.1 1087.08  4987.9 1079.09  4988.4 1078.59  5006.7 1078.59  5007.2 1079.09
  5028.3 1079.88  5036.8  1080.6  5042.6 1080.34  5049.5  1083.4  5057.7 1084.99
  5099.4 1086.85  5136.1 1089.59    5179 1091.66  5193.7 1094.08  5204.2 1094.53
  5210.1  1094.8  5294.1 1096.05  5378.5 1096.12  5576.4 1098.05  5680.2 1099.41
#Mann= 8 ,-1 , 0
  4800.1     .12       0  4987.9     .05       0  5007.2     .12       0
  5028.3    .035       0  5204.2     .07       0  5210.1    .035       0
  5378.5     .07       0  5576.4    .035       0
Bank Sta=4987.9,5007.2
XS Rating Curve= 0 ,0
Exp/Cntr=0.3,0.1

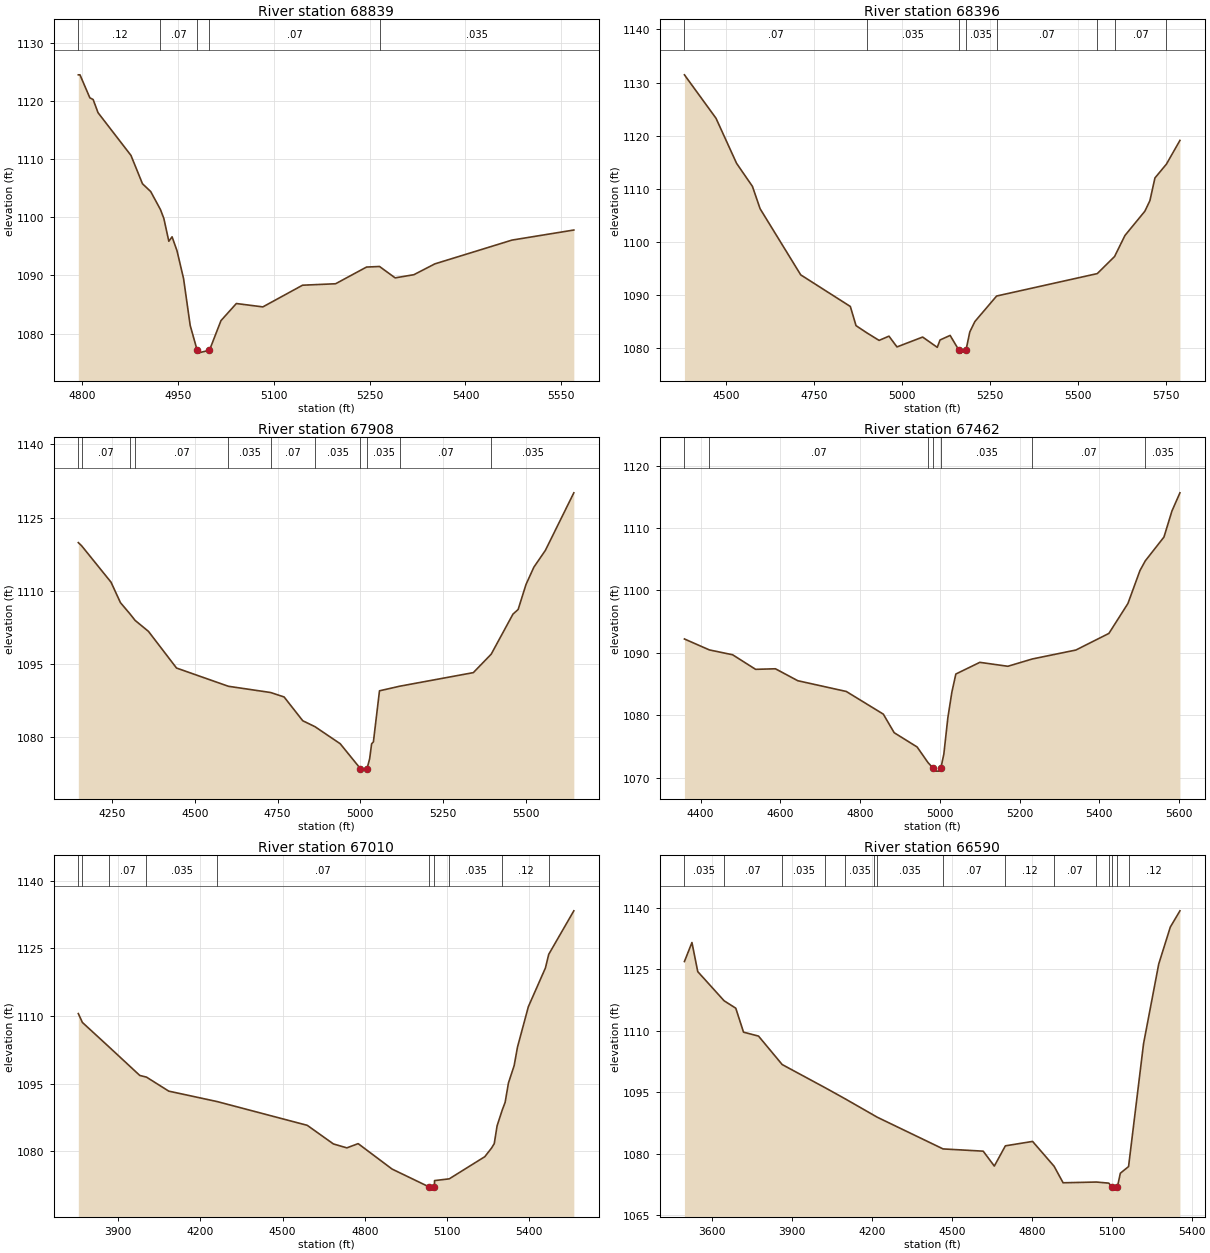
Type RM Length L Ch R = 1 ,68839   ,443,443,443
BEGIN DESCRIPTION:
West Fork 114.0
END DESCRIPTION:
XS GIS Cut Line= 3
      2185775.02     13821775.01        2185575.       13821725.
      2185024.97     13821875.01
#Sta/Elev= 30
  4793.5 1124.51  4796.1 1124.51  4811.6 1120.55  4816.7 1120.27  4824.4    1118
    4876 1110.65    4894 1105.78  4906.9 1104.44  4922.2 1101.34  4927.5 1099.81
  4935.3 1095.89  4940.4 1096.65  4948.1 1094.26  4958.4 1089.46  4968.8  1081.4
  4979.7 1077.15  4980.2 1076.65    4999 1077.15    5017 1082.24  5041.1 1085.18
  5082.6  1084.6  5144.8 1088.33  5196.6 1088.58    5245 1091.45  5265.4 1091.55
  5289.9 1089.59  5319.3 1090.14  5352.1    1092    5473 1096.09  5569.8 1097.82
#Mann= 5 ,-1 , 0
  4793.5     .12       0  4922.2     .07       0  4979.7     .05       0
    4999     .07       0  5265.4    .035       0
Bank Sta=4979.7,4999
XS Rating Curve= 0 ,0
Exp/Cntr=0.3,0.1

Type RM Length L Ch R = 1 ,68396   ,488,488,488
BEGIN DESCRIPTION:
West Fork 113.0
END DESCRIPTION:
XS GIS Cut Line= 3
      2185975.04     13821625.02        2185425.       13821325.
      2184824.97     13820824.98
#Sta/Elev= 30
  4381.6 1131.45  4471.3 1123.26  4529.7 1114.76  4574.8 1110.41  4596.6 1106.19
    4712 1093.72  4852.9 1087.76  4869.1 1084.14  4900.2 1082.77  4934.6 1081.36
  4962.6 1082.16  4985.4 1080.13  5058.3 1081.99  5099.9 1080.05  5107.7 1081.44
  5136.4  1082.3  5161.8 1079.46  5162.3 1078.96  5181.2 1079.46  5192.3 1082.96
  5206.6 1084.91  5268.4 1089.73  5554.4 1093.96  5603.6 1097.19    5633 1101.15
  5689.6 1105.73  5703.9 1107.72  5718.2    1112  5750.6 1114.59  5789.2 1119.08
#Mann= 8 ,-1 , 0
  4381.6     .07       0  4900.2    .035       0  5161.8    .035       0
  5181.2    .035       0  5268.4     .07       0  5554.4    .035       0
  5603.6     .07       0  5750.6    .035       0
Bank Sta=5161.8,5181.2
XS Rating Curve= 0 ,0
Exp/Cntr=0.3,0.1

Type RM Length L Ch R = 1 ,67908   ,446,446,446
BEGIN DESCRIPTION:
West Fork 112.0
END DESCRIPTION:
XS GIS Cut Line= 3
        2186025.       13821475.        2185425.       13820875.
      2184825.02     13820625.01
#Sta/Elev= 30
  4147.3 1119.86  4157.1 1119.23  4246.3 1111.74  4274.6 1107.56  4303.2 1105.27
  4319.1 1103.91  4359.4 1101.66  4444.3 1094.14  4601.1  1090.4    4729 1089.12
  4769.6 1088.21  4826.1 1083.33  4862.9 1082.12  4939.3 1078.62  5000.6  1073.5
  5001.1    1073  5020.3  1073.5  5028.3 1075.51  5034.3  1078.6  5039.7    1079
  5058.1 1089.47  5119.8 1090.42  5341.9  1093.2    5396 1096.99  5461.7 1105.19
  5477.4 1106.15  5501.2 1111.28    5525 1114.83  5559.7 1118.26  5645.8 1130.07
#Mann= 11 ,-1 , 0
  4147.3    .035       0  4157.1     .07       0  4303.2    .035       0
  4319.1     .07       0  4601.1    .035       0    4729     .07       0
  4862.9    .035       0  5000.6    .035       0  5020.3    .035       0
  5119.8     .07       0    5396    .035       0
Bank Sta=5000.6,5020.3
XS Rating Curve= 0 ,0
Exp/Cntr=0.3,0.1

Type RM Length L Ch R = 1 ,67462   ,452,452,452
BEGIN DESCRIPTION:
West Fork 111.0
END DESCRIPTION:
XS GIS Cut Line= 3
      2185975.02     13820975.03        2185575.       13820475.
      2184975.03       13820525.
#Sta/Elev= 30
  4359.6 1092.24  4422.1 1090.49  4480.5 1089.71  4538.1 1087.38  4587.8 1087.47
  4643.8 1085.56  4765.4 1083.84  4858.3 1080.21  4885.5 1077.24  4943.1 1074.95
  4970.5 1072.44  4982.9 1071.59  4983.4 1071.09  5002.1 1071.09  5002.6 1071.59
    5010  1073.8    5020 1079.59  5030.1 1083.71  5040.1 1086.63  5100.3  1088.5
  5170.5 1087.87  5231.9 1089.04  5341.1 1090.47  5423.9 1093.13  5471.6 1097.92
  5501.7 1103.18    5515 1104.73  5561.9 1108.55    5582 1112.73    5602 1115.63
#Mann= 7 ,-1 , 0
  4359.6    .035       0  4422.1     .07       0  4970.5    .035       0
  4982.9    .035       0  5002.6    .035       0  5231.9     .07       0
    5515    .035       0
Bank Sta=4982.9,5002.6
XS Rating Curve= 0 ,0
Exp/Cntr=0.3,0.1

Type RM Length L Ch R = 1 ,67010   ,420,420,420
BEGIN DESCRIPTION:
West Fork 110.0
END DESCRIPTION:
XS GIS Cut Line= 3
        2186125.     13821325.02        2185825.       13820125.
      2185675.01     13819575.04
#Sta/Elev= 30
  3754.9 1110.53  3769.9 1108.56  3868.3 1103.06  3979.1 1096.81  4003.5 1096.44
  4084.8 1093.33    4261 1091.02  4589.8 1085.75  4685.2 1081.62  4734.2 1080.75
  4775.4 1081.69  4899.1 1076.05  5033.8  1072.1  5034.3  1071.6  5053.6  1072.1
    5054 1073.49  5107.6 1073.88  5237.2 1078.79  5261.3 1080.66  5271.7 1081.68
  5282.1 1085.64  5301.1 1089.19  5311.4 1090.84  5323.5 1095.15  5344.3 1098.99
  5356.4 1103.08  5396.1 1112.06  5458.3 1120.64  5470.4 1123.67  5561.9 1133.32
#Mann= 10 ,-1 , 0
  3754.9     .07       0  3769.9    .035       0  3868.3     .07       0
  4003.5    .035       0    4261     .07       0  5033.8     .05       0
  5053.6     .07       0  5107.6    .035       0  5301.1     .12       0
  5470.4     .07       0
Bank Sta=5033.8,5053.6
XS Rating Curve= 0 ,0
Exp/Cntr=0.3,0.1

Type RM Length L Ch R = 1 ,66590   ,410,410,410
BEGIN DESCRIPTION:
West Fork 109.0
END DESCRIPTION:
XS GIS Cut Line= 3
      2187225.04     13820675.03        2186025.       13819775.
        2185825.       13819475.
#Sta/Elev= 30
  3495.5  1126.9  3523.7 1131.54  3545.5 1124.44  3644.4 1117.32  3688.3  1115.5
  3717.4 1109.65  3773.7 1108.69  3862.6 1101.74  4024.2 1096.07  4098.5 1093.39
  4207.6 1089.33  4218.9  1088.9  4466.6 1081.14  4617.4 1080.59  4659.1 1076.95
  4700.6 1081.89  4802.8 1082.97  4883.5 1076.91  4917.4 1072.87  5042.5 1073.05
    5089 1072.78  5101.3 1071.82  5101.8 1071.32  5121.1 1071.82  5132.3  1075.2
  5163.2 1076.83  5219.4 1106.81  5276.5  1126.3    5320 1135.32  5356.1 1139.28
#Mann= 15 ,-1 , 0
  3495.5    .035       0  3644.4     .07       0  3862.6    .035       0
  4024.2     .07       0  4098.5    .035       0  4207.6     .07       0
  4218.9    .035       0  4466.6     .07       0  4700.6     .12       0
  4883.5     .07       0  5042.5    .035       0    5089     .07       0
  5101.3     .05       0  5121.1     .07       0  5163.2     .12       0
Bank Sta=5101.3,5121.1
XS Rating Curve= 0 ,0
Exp/Cntr=0.3,0.1

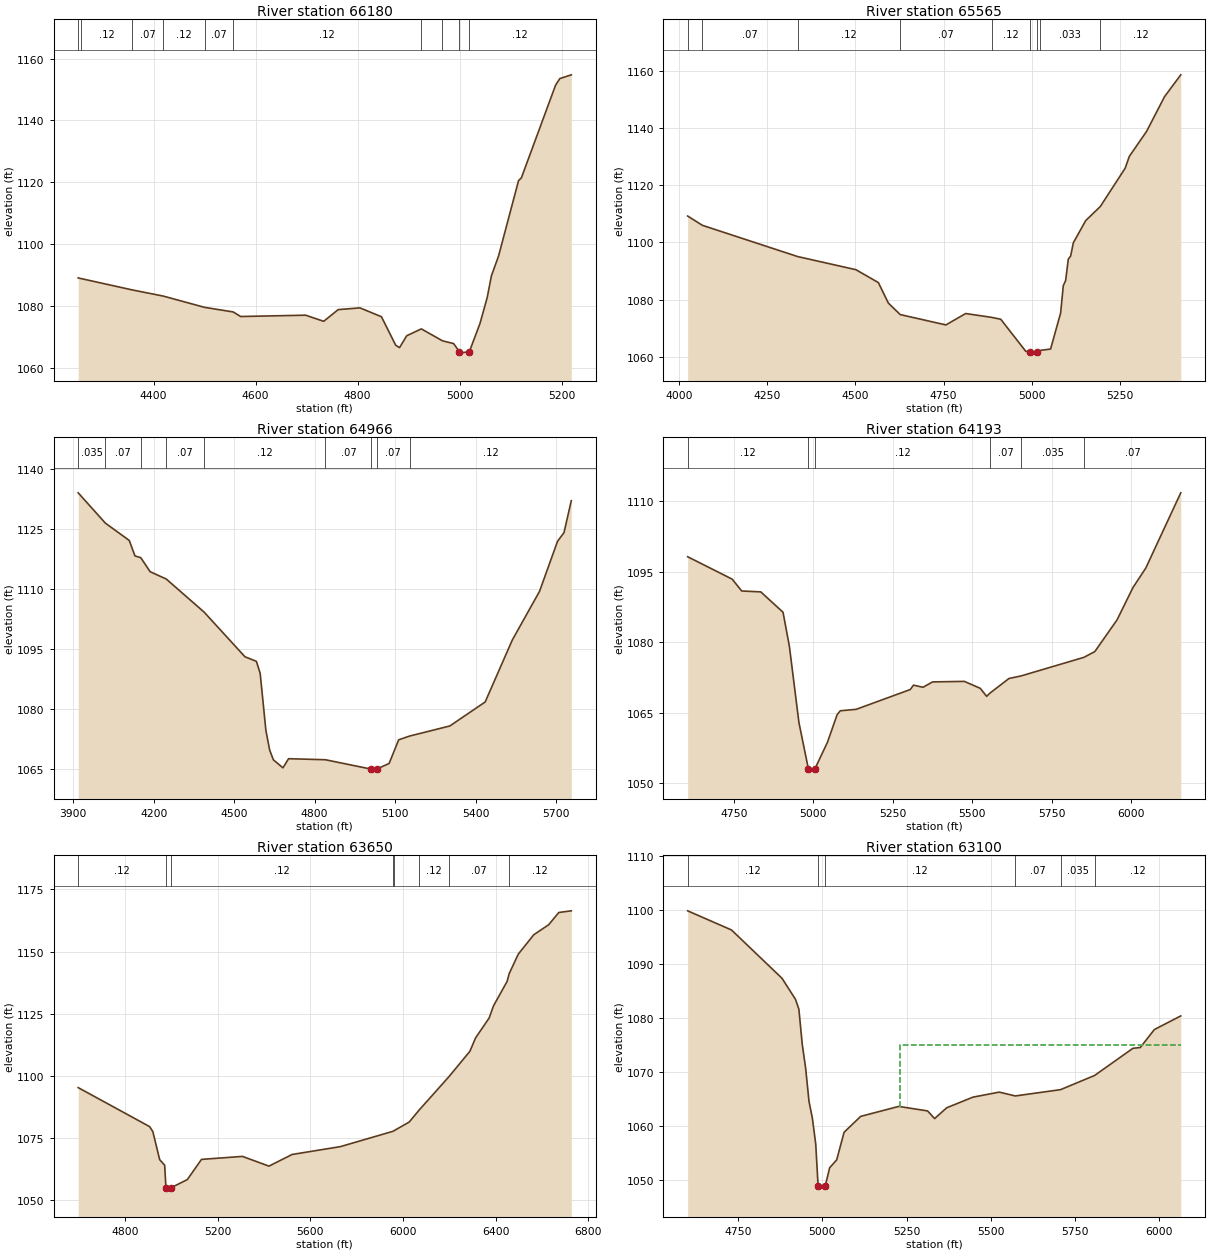
Type RM Length L Ch R = 1 ,66180   ,615,615,615
BEGIN DESCRIPTION:
West Fork 108.0
END DESCRIPTION:
XS GIS Cut Line= 3
      2186724.97     13820074.97        2186225.       13819525.
      2186124.99     13819324.97
#Sta/Elev= 30
  4252.2 1089.01  4257.8 1088.79  4358.2 1085.12  4419.4 1083.11  4499.9 1079.48
  4556.1 1077.99  4570.8 1076.51  4698.1 1076.94  4733.6 1074.96    4762 1078.74
  4804.6 1079.31  4846.8 1076.45  4874.8 1067.22  4882.3 1066.44  4896.5 1070.29
  4925.1 1072.51  4966.4 1068.65  4988.4 1067.75  4999.5 1065.16    5000 1064.66
  5019.3 1065.16  5040.2 1074.33  5054.2 1082.65  5062.5 1089.69  5076.5 1096.09
  5115.7 1120.51  5121.2 1121.37  5188.3  1151.4  5196.7 1153.53  5219.1 1154.74
#Mann= 10 ,-1 , 0
  4252.2     .07       0  4257.8     .12       0  4358.2     .07       0
  4419.4     .12       0  4499.9     .07       0  4556.1     .12       0
  4925.1     .07       0  4966.4     .12       0  4999.5     .05       0
  5019.3     .12       0
Bank Sta=4999.5,5019.3
XS Rating Curve= 0 ,0
Exp/Cntr=0.3,0.1

Type RM Length L Ch R = 1 ,65565   ,599,599,599
BEGIN DESCRIPTION:
H21662
END DESCRIPTION:
XS GIS Cut Line= 3
      2187438.31       13820105.      2186678.74     13819247.77
      2186429.61     13819204.44
#Sta/Elev= 30
  4024.5 1109.23  4066.2 1105.99  4336.4 1095.08  4501.6  1090.5  4565.2 1086.01
  4593.6 1078.84  4627.2 1074.84  4756.7 1071.22  4812.8  1075.2  4886.1 1073.87
  4912.3  1073.2  4983.4 1061.99  4994.4 1061.88  4994.9 1061.38  5014.2 1061.88
  5024.3 1062.33  5053.6 1062.81  5082.1 1075.42  5089.6 1084.89  5096.3 1086.76
  5103.8 1094.16  5110.5 1095.28  5118.1 1099.88  5153.2 1107.64  5194.6 1112.55
    5265 1125.91  5276.9 1130.05  5325.9 1138.79  5376.6 1150.87  5422.7 1158.51
#Mann= 9 ,-1 , 0
  4024.5    .035       0  4066.2     .07       0  4336.4     .12       0
  4627.2     .07       0  4886.1     .12       0  4994.4     .05       0
  5014.2     .12       0  5024.3    .033       0  5194.6     .12       0
Bank Sta=4994.4,5014.2
XS Rating Curve= 0 ,0
Exp/Cntr=0.3,0.1

Type RM Length L Ch R = 1 ,64966   ,773,773,773
BEGIN DESCRIPTION:
H21661
END DESCRIPTION:
XS GIS Cut Line= 3
      2188100.21     13820029.05      2187242.98     13819139.26
      2186648.14     13819041.93
#Sta/Elev= 30
  3918.4    1134  4019.7 1126.42  4108.8 1122.09  4130.1 1118.21  4151.6 1117.78
  4186.7 1114.26  4246.9 1112.43  4387.6 1104.17  4540.2 1092.98  4582.7 1091.84
  4596.8 1088.85  4618.2 1074.54  4632.2 1069.64  4646.2 1067.19  4681.7  1065.2
  4702.8 1067.48  4839.9 1067.22  5011.1 1064.87  5011.6 1064.37  5030.9 1064.87
  5077.6 1066.29  5113.1  1072.2  5153.6 1073.14  5303.9 1075.67  5435.6 1081.67
    5537  1097.2  5638.3 1109.35  5705.4 1121.87  5729.5 1124.04  5756.7 1132.03
#Mann= 9 ,-1 , 0
  3918.4    .035       0  4019.7     .07       0  4151.6    .035       0
  4246.9     .07       0  4387.6     .12       0  4839.9     .07       0
  5011.1     .05       0  5030.9     .07       0  5153.6     .12       0
Bank Sta=5011.1,5030.9
XS Rating Curve= 0 ,0
Exp/Cntr=0.3,0.1

Type RM Length L Ch R = 1 ,64193   ,543,543,543
BEGIN DESCRIPTION:
West Fork 105.0
END DESCRIPTION:
XS GIS Cut Line= 3
        2188325.       13818925.        2187925.       13818925.
      2186774.99       13818975.
#Sta/Elev= 30
  4605.1  1098.2  4745.1 1093.44  4775.1 1090.92  4835.1 1090.73  4905.1  1086.4
  4925.1 1079.15  4955.1 1062.96  4984.8 1053.12  4985.3 1052.62  5005.5 1053.12
  5045.1 1058.79  5075.2 1064.62  5085.2 1065.45  5135.2 1065.76  5305.4 1069.97
  5315.4  1070.9  5345.4 1070.45  5375.5 1071.59  5475.5  1071.7  5525.6 1070.22
  5545.6 1068.52  5555.7 1069.19  5615.7 1072.31  5654.4 1072.87  5851.9 1076.82
  5885.9 1078.04    5956  1084.8    6006 1091.67  6046.1 1095.78  6156.2 1111.79
#Mann= 6 ,-1 , 0
  4605.1     .12       0  4984.8     .05       0  5005.5     .12       0
  5555.7     .07       0  5654.4    .035       0  5851.9     .07       0
Bank Sta=4984.8,5005.5
XS Rating Curve= 0 ,0
Exp/Cntr=0.3,0.1

Type RM Length L Ch R = 1 ,63650   ,550,550,550
BEGIN DESCRIPTION:
West Fork 104.0
END DESCRIPTION:
XS GIS Cut Line= 3
      2188325.01       13818625.        2187975.       13818425.
      2186375.01     13819074.99
#Sta/Elev= 30
  4596.9 1095.32  4905.7 1079.64  4919.4 1077.64  4948.9 1066.37  4970.5 1064.14
    4976 1055.03  4976.5 1054.53  4996.7 1055.03  5068.3 1058.36  5129.5 1066.48
  5306.6 1067.68    5421 1063.77  5520.8 1068.45  5729.6 1071.61  5955.9 1077.74
  5961.4 1078.02  6026.9 1081.49  6069.1 1086.23  6199.3  1099.8  6289.2 1109.95
  6313.3 1115.26  6372.3 1123.32    6391 1128.18  6449.9 1138.03  6458.6  1141.1
  6498.1 1148.97  6565.1 1156.76  6629.2 1160.76    6673 1165.69    6727 1166.36
#Mann= 8 ,-1 , 0
  4596.9     .12       0    4976     .05       0  4996.7     .12       0
  5955.9     .07       0  5961.4    .035       0  6069.1     .12       0
  6199.3     .07       0  6458.6     .12       0
Bank Sta=4976,4996.7
XS Rating Curve= 0 ,0
Exp/Cntr=0.3,0.1

Type RM Length L Ch R = 1 ,63100   ,563,563,563
BEGIN DESCRIPTION:
West Fork 103.0
END DESCRIPTION:
XS GIS Cut Line= 3
        2187825.     13817525.01        2187825.       13817925.
      2187025.01     13818624.99
#Sta/Elev= 30
  4600.3 1099.87  4730.3 1096.32  4880.3 1087.35  4920.3 1083.44  4930.3 1081.61
  4940.3 1075.09  4950.3 1070.69  4960.3 1064.52  4970.3 1061.39  4980.3  1056.6
  4987.4 1048.73  4987.9 1048.23  5008.2 1048.73  5021.6  1052.2  5042.5 1053.66
  5064.4 1058.78  5113.7 1061.73  5226.7 1063.58  5312.1 1062.74    5333 1061.32
    5369 1063.33  5446.9  1065.3  5524.7 1066.23  5572.3 1065.52  5706.8 1066.69
  5807.7 1069.32  5921.4 1074.36  5943.2 1074.51    5985 1077.84  6063.3 1080.37
#Mann= 6 ,-1 , 0
  4600.3     .12       0  4987.4     .05       0  5008.2     .12       0
  5572.3     .07       0  5706.8    .035       0  5807.7     .12       0
#XS Ineff= 2 , 0
       0                    5230       0    1075
Permanent Ineff=
       F       F
Bank Sta=4987.4,5008.2
XS Rating Curve= 0 ,0
Exp/Cntr=0.3,0.1

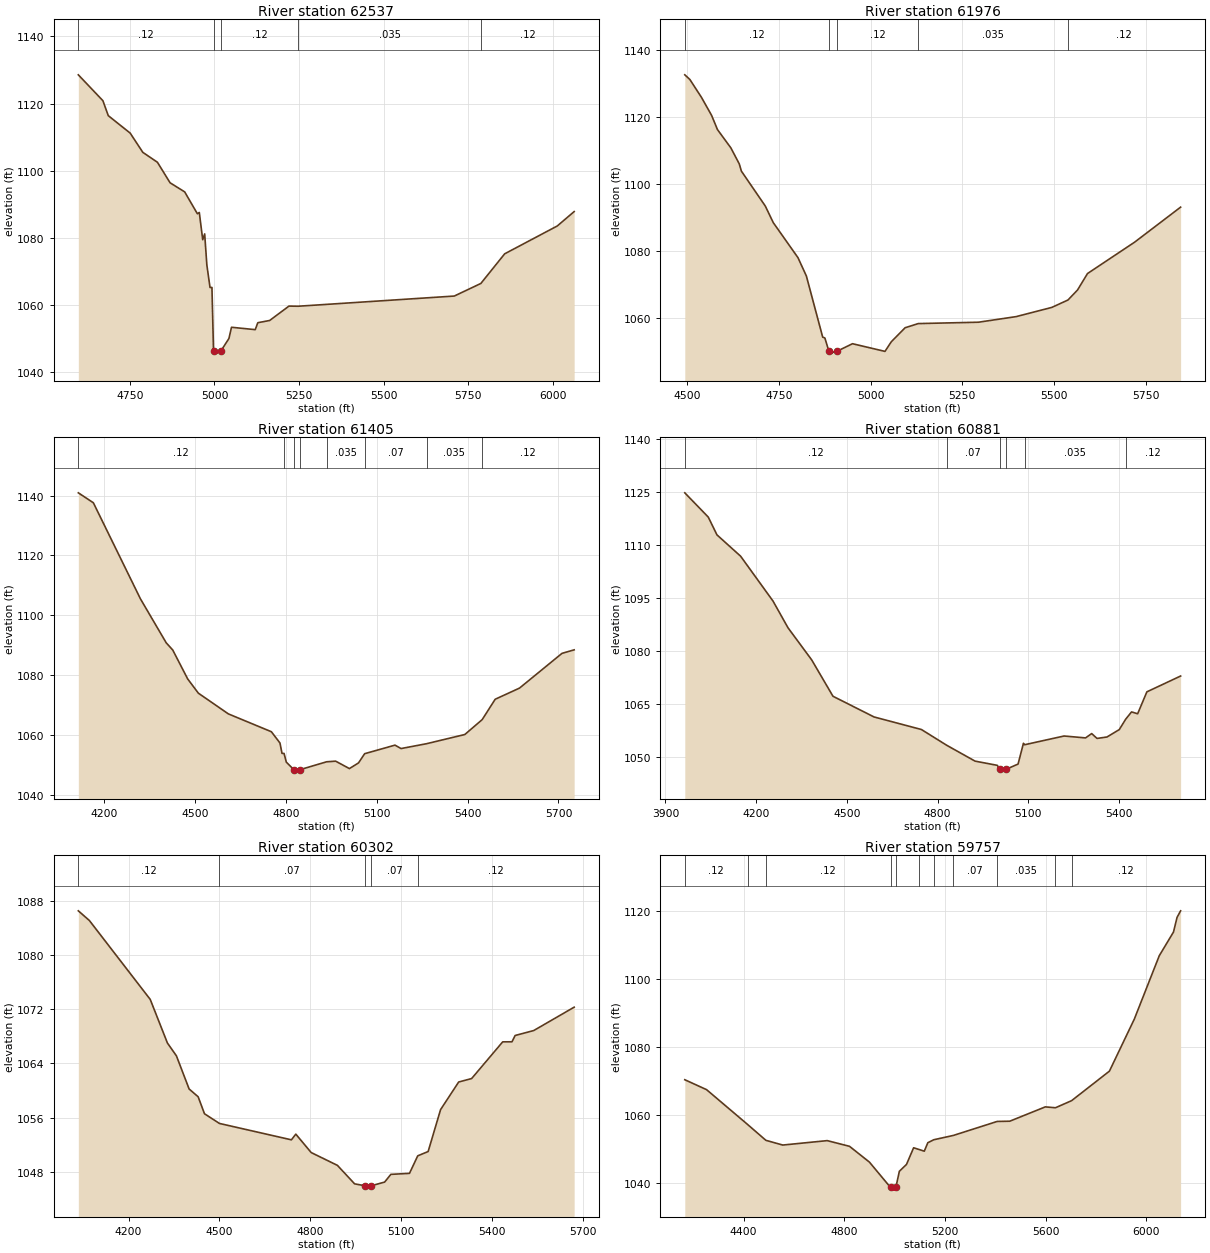
Type RM Length L Ch R = 1 ,62537   ,561,561,561
BEGIN DESCRIPTION:
West Fork 102.0
END DESCRIPTION:
XS GIS Cut Line= 3
      2187175.02     13817275.04        2187375.       13817625.
      2186674.99     13818425.01
#Sta/Elev= 30
  4597.4 1128.58  4670.1 1120.87  4685.9 1116.43  4750.7 1111.23  4788.1  1105.5
  4831.3 1102.55  4868.7 1096.44  4911.9 1093.73  4949.4 1087.22  4955.1  1087.6
  4965.2 1079.49    4971 1081.23  4977.4 1071.99  4986.8 1065.27  4992.5 1065.28
  4997.2 1046.23  4997.7 1045.73    5018 1046.23  5042.7 1050.08  5050.3 1053.43
  5120.5 1052.72  5128.1 1054.78  5163.2 1055.45  5220.2 1059.73  5247.5 1059.69
    5709 1062.72  5787.6 1066.47    5858 1075.29  6013.7 1083.59  6063.5 1087.87
#Mann= 5 ,-1 , 0
  4597.4     .12       0  4997.2     .05       0    5018     .12       0
  5247.5    .035       0  5787.6     .12       0
Bank Sta=4997.2,5018
XS Rating Curve= 0 ,0
Exp/Cntr=0.3,0.1

Type RM Length L Ch R = 1 ,61976   ,571,571,571
BEGIN DESCRIPTION:
West Fork 101.0
END DESCRIPTION:
XS GIS Cut Line= 3
      2187074.99     13817225.02        2186825.       13817675.
        2186575.     13818474.99
#Sta/Elev= 30
  4492.8 1132.49  4506.5 1131.12  4538.5 1125.72    4566 1120.37    4582 1116.13
  4618.6 1110.66  4641.5 1105.88  4647.2 1103.74  4712.4 1093.32  4734.2 1088.36
  4801.6  1077.9  4824.5 1072.43  4869.1 1054.16  4874.9 1053.93  4886.2 1049.89
  4886.7 1049.39    4907 1049.89  4950.4  1052.2    5039 1049.91  5056.3 1052.79
    5094 1056.97  5129.7 1058.21  5294.1 1058.62  5396.8 1060.29  5494.2 1063.04
  5538.3 1065.25  5564.4 1068.24  5591.6 1073.15    5720 1082.51  5845.7 1092.98
#Mann= 5 ,-1 , 0
  4492.8     .12       0  4886.2     .05       0    4907     .12       0
  5129.7    .035       0  5538.3     .12       0
Bank Sta=4886.2,4907
XS Rating Curve= 0 ,0
Exp/Cntr=0.3,0.1

Type RM Length L Ch R = 1 ,61405   ,524,524,524
BEGIN DESCRIPTION:
West Fork 100.0
END DESCRIPTION:
XS GIS Cut Line= 3
        2186925.       13817025.        2186275.       13817625.
        2186325.     13818375.04
#Sta/Elev= 30
  4115.4 1140.93    4165 1137.61  4320.4 1105.51  4405.4 1090.84    4427 1088.42
  4476.3 1078.76  4511.5 1074.01  4610.7 1067.08  4752.5 1061.13  4780.8 1057.37
  4787.6 1053.89  4794.3 1053.88  4801.8 1050.97  4826.5 1048.47    4827 1047.97
  4847.4 1048.47  4934.8 1051.09  4964.6  1051.3    5010 1048.82  5040.1 1050.72
  5060.3 1053.79  5160.4 1056.65  5180.4 1055.51  5264.7 1057.13  5390.9  1060.2
  5448.2 1065.18  5491.1 1071.98  5571.3  1075.7  5711.6 1087.31  5751.7 1088.48
#Mann= 8 ,-1 , 0
  4115.4     .12       0  4794.3     .07       0  4826.5    .035       0
  4847.4     .07       0  4934.8    .035       0  5060.3     .07       0
  5264.7    .035       0  5448.2     .12       0
Bank Sta=4826.5,4847.4
XS Rating Curve= 0 ,0
Exp/Cntr=0.3,0.1

Type RM Length L Ch R = 1 ,60881   ,579,579,579
BEGIN DESCRIPTION:
West Fork 99.0
END DESCRIPTION:
XS GIS Cut Line= 3
        2186625.       13816825.        2185825.       13817475.
      2185925.01     13818075.04
#Sta/Elev= 30
  3964.2 1124.85  4041.8 1117.97  4070.5 1112.93  4148.8 1106.87  4255.8 1094.16
  4305.4 1086.58  4383.7 1077.47  4454.1 1067.16  4589.9 1061.29  4746.5 1057.73
  4829.5 1053.29  4923.9 1048.76  4997.5 1047.57  5004.8 1046.43  5005.3 1045.93
  5025.7 1046.43  5065.9 1047.93  5083.7 1053.82  5087.4 1053.41    5218 1055.89
    5289 1055.35  5309.3 1056.58    5327  1055.2  5359.9 1055.61  5400.5 1057.71
  5421.4 1060.62    5441 1062.72  5461.3  1062.2  5491.7 1068.41  5603.3  1072.9
#Mann= 6 ,-1 , 0
  3964.2     .12       0  4829.5     .07       0  5004.8     .05       0
  5025.7     .07       0  5087.4    .035       0  5421.4     .12       0
Bank Sta=5004.8,5025.7
XS Rating Curve= 0 ,0
Exp/Cntr=0.3,0.1

Type RM Length L Ch R = 1 ,60302   ,545,545,545
BEGIN DESCRIPTION:
West Fork 98.0
END DESCRIPTION:
XS GIS Cut Line= 3
      2186075.04     13816824.97        2185275.       13817375.
      2185425.01     13818025.04
#Sta/Elev= 30
  4034.2 1086.53  4070.7  1085.1  4271.7 1073.45  4328.5 1067.01  4358.3 1065.11
  4400.2 1060.22    4430 1059.07    4451 1056.56  4500.4 1055.13  4738.1 1052.71
  4752.7 1053.55  4803.5 1050.83  4890.1 1048.94  4946.9 1046.21  4981.1 1045.93
  4981.6 1045.43  5002.1 1045.93  5046.1 1046.47  5066.6 1047.61  5128.2 1047.76
  5155.5 1050.35  5189.8 1050.98  5230.9 1057.17  5290.7 1061.25  5333.5 1061.76
  5436.1 1067.18  5466.9 1067.19  5477.2 1068.12  5538.7 1068.85  5672.2  1072.3
#Mann= 5 ,-1 , 0
  4034.2     .12       0  4500.4     .07       0  4981.1     .05       0
  5002.1     .07       0  5155.5     .12       0
Bank Sta=4981.1,5002.1
XS Rating Curve= 0 ,0
Exp/Cntr=0.3,0.1

Type RM Length L Ch R = 1 ,59757   ,553,553,553
BEGIN DESCRIPTION:
West Fork 97.0
END DESCRIPTION:
XS GIS Cut Line= 3
      2185674.99       13816825.        2184875.       13817075.
      2184075.01     13817874.99
#Sta/Elev= 30
  4166.5 1070.34  4252.9 1067.43  4415.7 1057.22  4488.6 1052.55  4555.7 1051.16
  4732.2 1052.46  4820.8 1050.79  4899.9 1046.15  4983.6 1038.72  4984.1 1038.22
  5004.8 1038.72  5018.8 1043.46  5047.1 1045.47  5075.4 1050.36  5098.5 1049.82
  5117.8 1049.36  5131.9 1051.85  5155.1 1052.71  5233.6 1053.99  5407.2 1058.09
  5457.2 1058.16  5598.6 1062.37  5638.9 1062.11  5703.1  1064.2  5853.2 1072.86
  5952.2 1088.16  6051.2 1106.75  6107.7 1113.71  6121.9 1118.02    6136 1119.93
#Mann= 11 ,-1 , 0
  4166.5     .12       0  4415.7     .07       0  4488.6     .12       0
  4983.6     .05       0  5004.8     .12       0  5098.5     .07       0
  5155.1    .035       0  5233.6     .07       0  5407.2    .035       0
  5638.9     .07       0  5703.1     .12       0
Bank Sta=4983.6,5004.8
XS Rating Curve= 0 ,0
Exp/Cntr=0.3,0.1