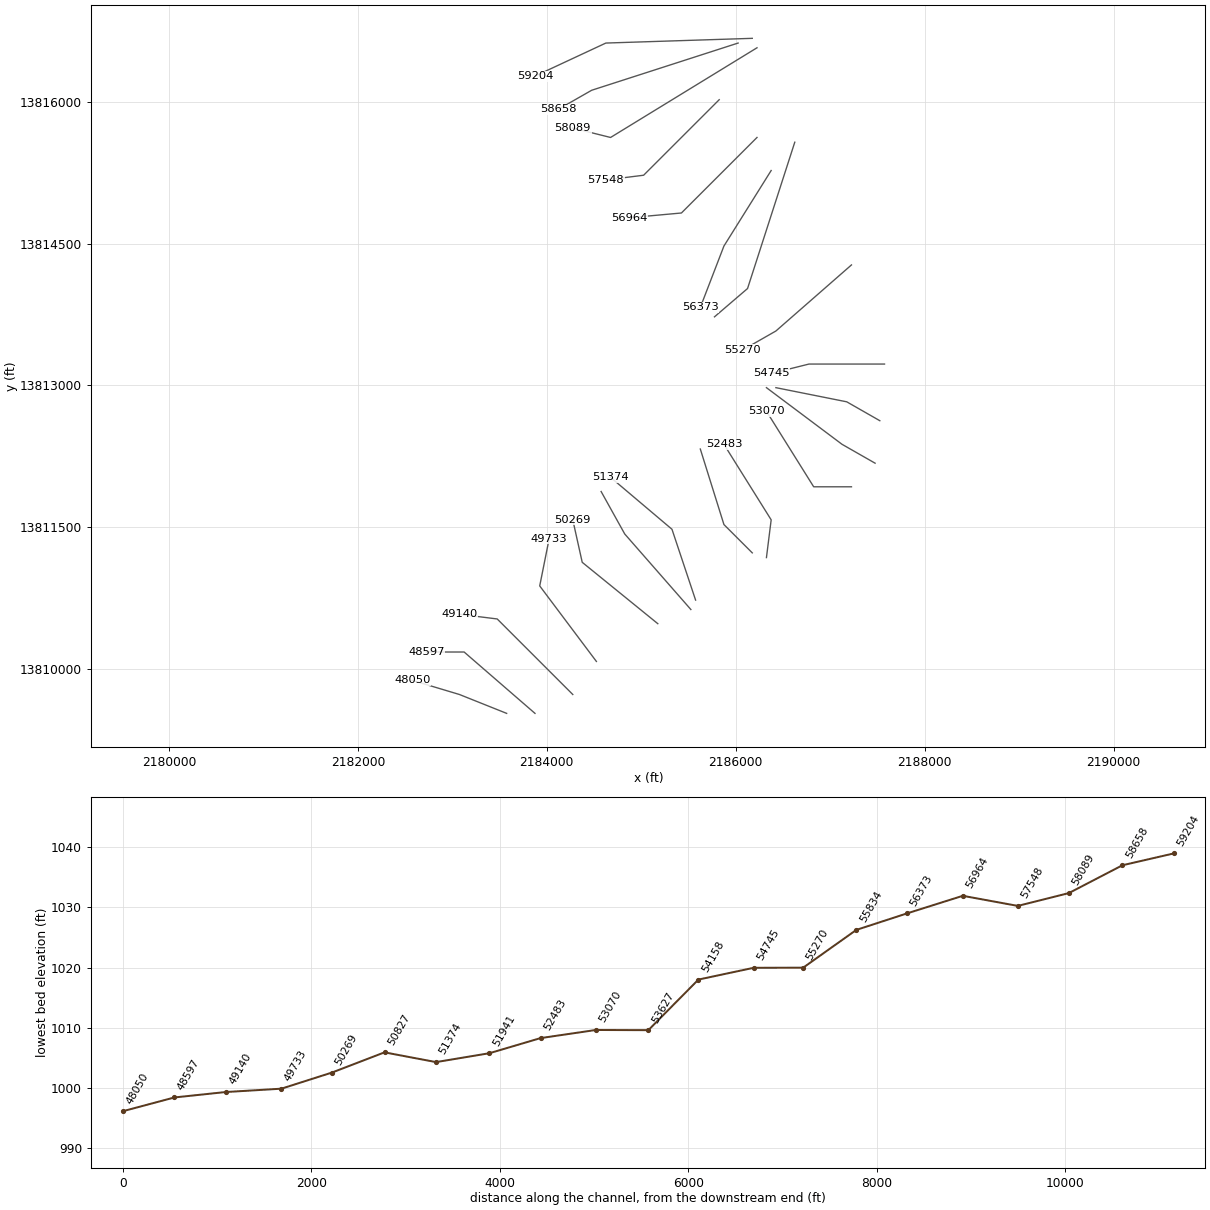
HEC-RAS study West Fork Dry Comal Creek.prj: West Fork Dry Comal Creek

--- West Fork Dry Comal Creek.g01 (geometry) --- (continued)

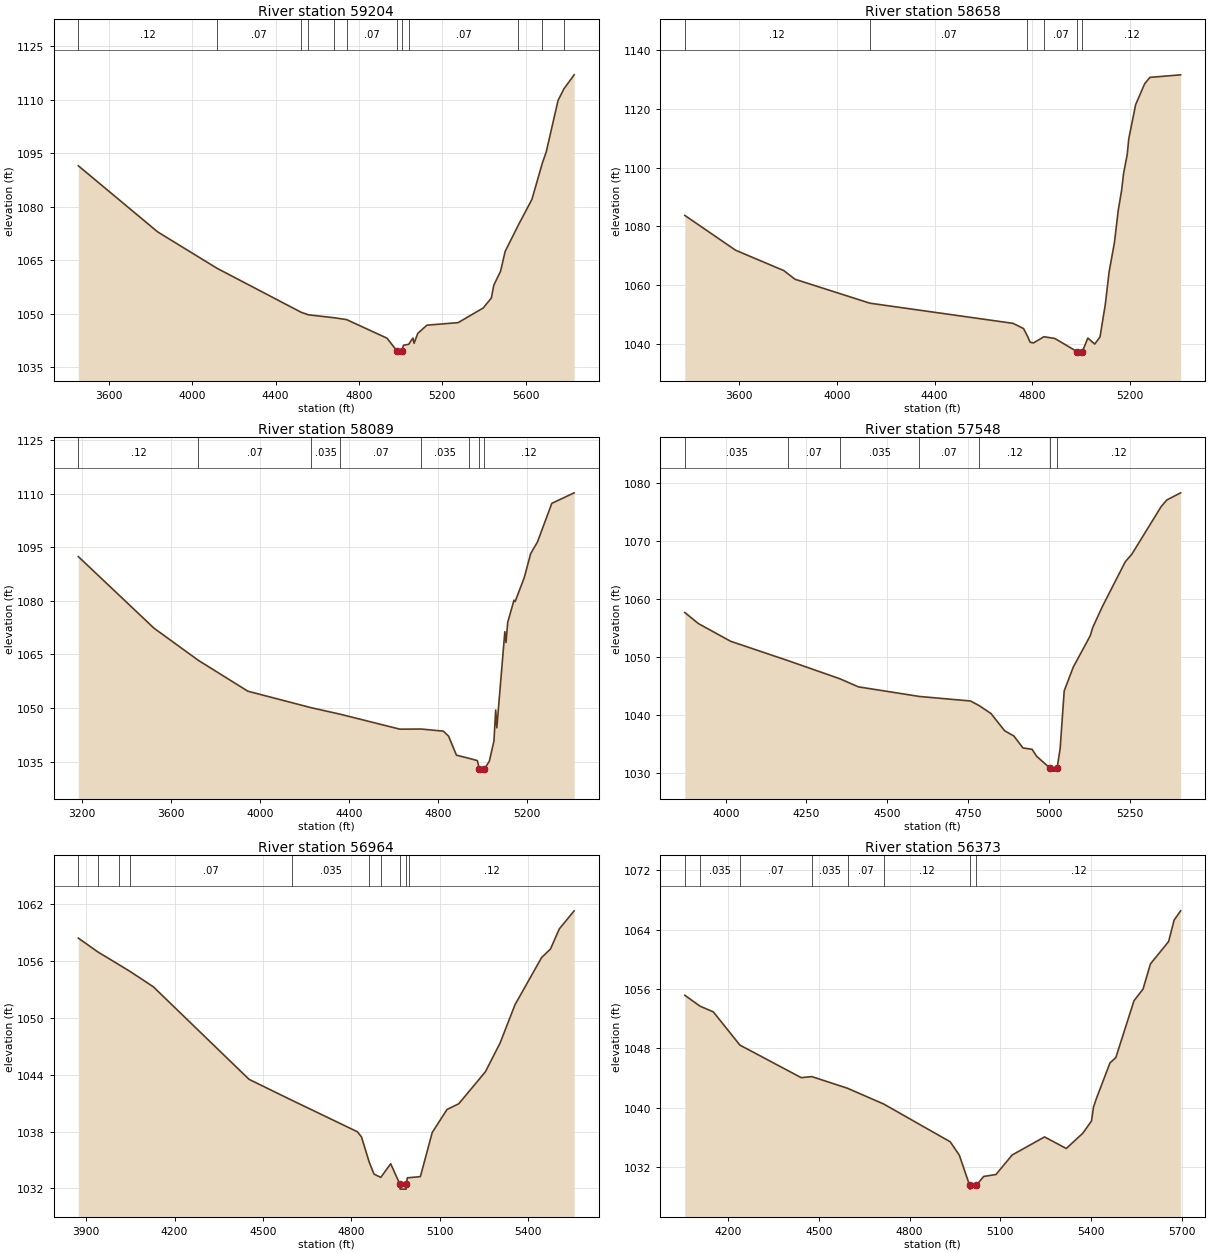
Type RM Length L Ch R = 1 ,59204   ,546,546,546
BEGIN DESCRIPTION:
West Fork 96.0
END DESCRIPTION:
XS GIS Cut Line= 3
      2186175.04       13816675.        2184625.       13816625.
      2183874.99       13816275.
#Sta/Elev= 30
  3454.1 1091.52  3834.3    1073  4119.6 1062.77  4523.6 1050.42  4557.5 1049.73
  4681.5  1048.9    4741 1048.38  4934.9 1043.17  4984.2 1039.48  4984.7 1038.98
  5005.6 1039.48  5013.6  1041.2  5038.6 1041.44  5059.3  1043.2  5064.8 1041.74
  5082.2  1044.5  5126.3 1046.82  5276.1 1047.53  5395.9 1051.63  5435.3 1054.42
  5447.1 1058.04  5479.5 1061.93  5501.5  1067.5  5565.5 1074.96    5630  1082.1
  5679.9 1092.26  5698.6 1095.39  5755.3 1109.83  5783.5  1113.1  5832.6 1117.03
#Mann= 12 ,-1 , 0
  3454.1     .12       0  4119.6     .07       0  4523.6     .12       0
  4557.5     .07       0  4681.5     .12       0    4741     .07       0
  4984.2    .035       0  5005.6     .07       0  5038.6     .07       0
  5565.5     .12       0  5679.9     .07       0  5783.5     .12       0
Bank Sta=4984.2,5005.6
XS Rating Curve= 0 ,0
Exp/Cntr=0.3,0.1

Type RM Length L Ch R = 1 ,58658   ,569,569,569
BEGIN DESCRIPTION:
West Fork 95.0
END DESCRIPTION:
XS GIS Cut Line= 3
      2186025.01       13816625.        2184475.       13816125.
      2184124.98     13815924.99
#Sta/Elev= 30
  3376.7 1083.76    3585 1071.93  3782.6 1065.02  3828.5 1062.08  4135.2 1053.96
  4721.7 1047.12    4765 1045.34  4780.8 1042.79  4791.8 1040.71  4805.7 1040.47
  4848.5 1042.58  4893.2 1041.99  4984.2 1037.51  4984.7 1037.01  5005.6 1037.51
  5028.4 1042.13  5056.5 1040.09  5078.1 1042.48  5099.7 1053.45  5115.5 1064.61
  5137.1 1074.43  5152.9 1085.48  5166.6 1092.21  5174.5 1097.88  5189.6 1104.36
  5196.1 1109.81  5224.2 1121.36  5260.9 1128.39  5282.5  1130.6  5408.5 1131.47
#Mann= 6 ,-1 , 0
  3376.7     .12       0  4135.2     .07       0  4780.8     .12       0
  4848.5     .07       0  4984.2     .05       0  5005.6     .12       0
Bank Sta=4984.2,5005.6
XS Rating Curve= 0 ,0
Exp/Cntr=0.3,0.1

Type RM Length L Ch R = 1 ,58089   ,541,541,541
BEGIN DESCRIPTION:
West Fork 94.0
END DESCRIPTION:
XS GIS Cut Line= 3
      2186225.03     13816575.02        2184675.       13815625.
      2184275.01       13815725.
#Sta/Elev= 30
    3182 1092.36  3522.5 1072.34  3722.3 1063.34  3944.4 1054.73  4229.5 1050.11
  4359.6  1048.3  4628.7 1044.11  4724.5 1044.15  4824.1 1043.55  4847.5 1042.15
  4882.7 1036.85  4938.4 1035.97  4976.8 1035.33  4986.4 1032.88  4986.9 1032.38
  5007.8 1032.88  5030.9 1035.19  5051.5 1040.77  5059.3 1049.45  5064.4 1044.49
  5100.5 1071.37  5105.7 1068.34  5113.4 1073.98  5141.7 1080.17  5146.9 1079.79
  5188.1 1086.54  5216.5 1093.16  5247.4 1096.47  5311.8 1107.25  5412.3 1110.19
#Mann= 8 ,-1 , 0
    3182     .12       0  3722.3     .07       0  4229.5    .035       0
  4359.6     .07       0  4724.5    .035       0  4938.4     .12       0
  4986.4     .05       0  5007.8     .12       0
Bank Sta=4986.4,5007.8
XS Rating Curve= 0 ,0
Exp/Cntr=0.3,0.1

Type RM Length L Ch R = 1 ,57548   ,584,584,584
BEGIN DESCRIPTION:
West Fork 93.0
END DESCRIPTION:
XS GIS Cut Line= 3
      2185825.03     13816025.03        2185025.       13815225.
      2184625.02       13815175.
#Sta/Elev= 30
  3873.4 1057.68  3915.9 1055.75  4014.9 1052.71  4193.7 1049.34  4353.3 1046.22
  4410.8 1044.82  4599.4 1043.16  4757.3 1042.38  4783.8  1041.6    4821 1040.21
  4863.4 1037.22  4891.7 1036.33    4920 1034.26  4948.2 1034.02  4962.4 1032.81
  5004.1 1030.75  5004.6 1030.25  5025.1 1030.25  5025.6 1030.75    5035 1034.12
  5047.6 1044.12  5075.4 1048.21  5128.3 1053.67  5135.8 1055.07  5166.1 1058.75
  5236.6 1066.45  5256.8 1067.75  5347.5 1075.98  5365.1 1077.13  5407.9 1078.37
#Mann= 7 ,-1 , 0
  3873.4    .035       0  4193.7     .07       0  4353.3    .035       0
  4599.4     .07       0  4783.8     .12       0  5004.1     .05       0
  5025.6     .12       0
Bank Sta=5004.1,5025.6
XS Rating Curve= 0 ,0
Exp/Cntr=0.3,0.1

Type RM Length L Ch R = 1 ,56964   ,591,591,591
BEGIN DESCRIPTION:
West Fork 92.0
END DESCRIPTION:
XS GIS Cut Line= 3
      2186225.03     13815625.03        2185425.       13814825.
      2184874.98       13814775.
#Sta/Elev= 30
  3873.4 1058.44  3940.2 1056.97    4010 1055.66  4050.1  1054.9    4128  1053.3
  4453.3 1043.52  4598.2 1041.32    4821 1037.99  4835.1 1037.43  4861.4 1034.76
  4877.5 1033.52  4900.4 1033.17  4934.1 1034.61  4965.7 1032.43  4966.2 1031.93
  4986.8 1031.93  4987.3 1032.43  4990.7 1033.13  4996.6 1033.14  5034.9 1033.25
  5075.1 1037.91  5125.3 1040.34  5165.5 1040.95  5255.8 1044.33    5306 1047.39
  5356.3 1051.41  5446.6 1056.39  5476.7 1057.29  5506.9 1059.42  5557.1 1061.32
#Mann= 10 ,-1 , 0
  3873.4    .035       0  3940.2     .07       0    4010    .035       0
  4050.1     .07       0  4598.2    .035       0  4861.4     .12       0
  4900.4    .035       0  4965.7     .05       0  4987.3    .035       0
  4996.6     .12       0
Bank Sta=4965.7,4987.3
XS Rating Curve= 0 ,0
Exp/Cntr=0.3,0.1

Type RM Length L Ch R = 1 ,56373   ,539,539,539
BEGIN DESCRIPTION:
West Fork 91.0
END DESCRIPTION:
XS GIS Cut Line= 3
      2186374.98     13815274.96        2185875.       13814475.
      2185624.99     13813824.98
#Sta/Elev= 30
  4056.7 1055.15  4107.4 1053.67    4151 1052.91  4238.9 1048.43  4441.7 1044.04
    4477 1044.18  4595.3  1042.6  4714.2 1040.49  4934.6 1035.39  4964.7 1033.58
  4998.8 1029.51  4999.3 1029.01  5020.6 1029.51  5045.1 1030.72  5085.8 1030.98
  5139.3 1033.61  5246.5 1036.05  5318.3 1034.49  5372.9 1036.54  5401.8  1038.2
  5408.3 1040.07  5417.9 1041.22  5462.9 1046.03  5482.2 1046.74  5542.2  1054.4
  5572.2 1055.98  5596.8 1059.38  5656.8 1062.39    5675 1065.28  5696.5 1066.53
#Mann= 8 ,-1 , 0
  4056.7     .07       0  4107.4    .035       0  4238.9     .07       0
    4477    .035       0  4595.3     .07       0  4714.2     .12       0
  4998.8     .05       0  5020.6     .12       0
Bank Sta=4998.8,5020.6
XS Rating Curve= 0 ,0
Exp/Cntr=0.3,0.1

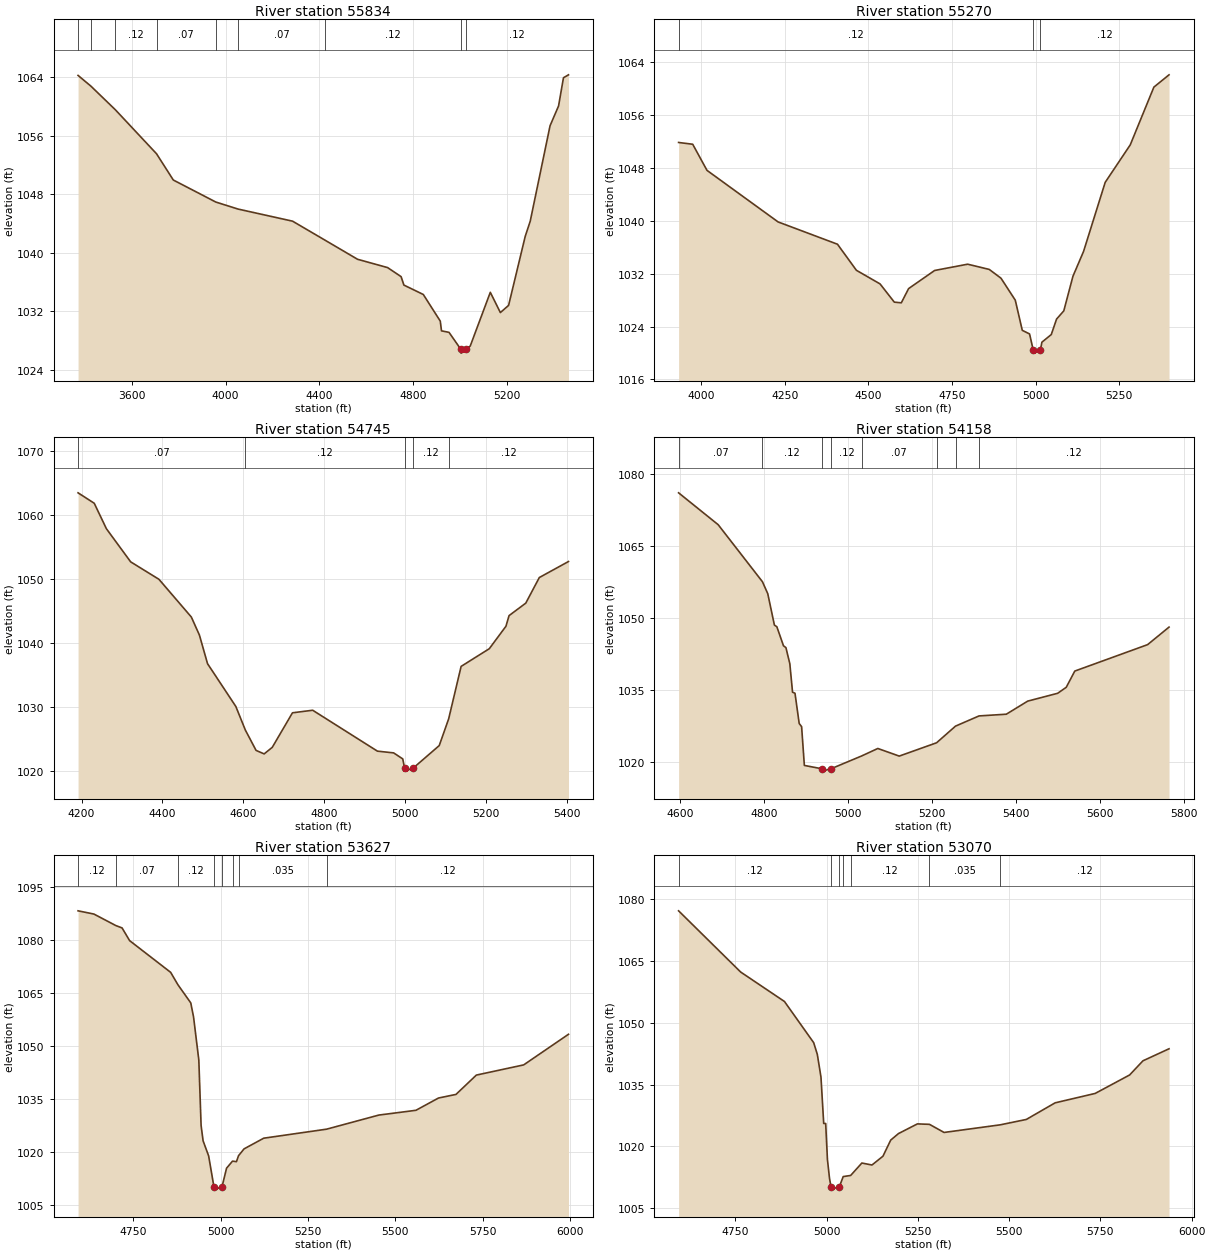
Type RM Length L Ch R = 1 ,55834   ,564,564,564
BEGIN DESCRIPTION:
West Fork 90.0
END DESCRIPTION:
XS GIS Cut Line= 3
      2186624.99     13815574.98        2186125.       13814025.
        2185775.       13813725.
#Sta/Elev= 30
  3371.4 1064.25  3426.2 1062.78  3530.6 1059.54  3705.8 1053.53  3777.2 1049.94
  3958.2 1046.93  4052.7 1045.97  4285.5 1044.31  4422.6 1041.73  4562.1  1039.1
  4690.3 1037.96  4747.8 1036.72  4759.7 1035.57  4842.4 1034.28  4914.7 1030.64
  4919.9 1029.31    4952  1029.1  5002.8 1026.76  5003.3 1026.26  5024.6 1026.76
  5042.3 1027.23  5127.9 1034.58  5170.7 1031.81  5205.8 1032.79  5276.6 1042.23
    5298 1044.31  5382.5 1057.37  5418.7 1060.07  5439.6 1063.93    5461 1064.33
#Mann= 9 ,-1 , 0
  3371.4    .035       0  3426.2     .07       0  3530.6     .12       0
  3705.8     .07       0  3958.2    .035       0  4052.7     .07       0
  4422.6     .12       0  5002.8     .05       0  5024.6     .12       0
Bank Sta=5002.8,5024.6
XS Rating Curve= 0 ,0
Exp/Cntr=0.3,0.1

Type RM Length L Ch R = 1 ,55270   ,525,525,525
BEGIN DESCRIPTION:
West Fork 89.0
END DESCRIPTION:
XS GIS Cut Line= 3
      2187224.98     13814274.98        2186425.       13813575.
        2186075.       13813375.
#Sta/Elev= 30
  3932.4 1051.84  3974.6 1051.57  4017.3 1047.62  4229.9 1039.82  4407.4 1036.45
  4463.9 1032.51  4534.6 1030.45  4577.3 1027.69  4598.2 1027.59    4620 1029.74
  4697.8 1032.48  4796.5 1033.43  4861.1 1032.64  4896.2 1031.31  4938.9 1027.99
  4959.8 1023.43  4981.6 1022.88  4992.4 1020.48  4992.9 1019.98  5014.2 1020.48
  5018.4 1021.63  5046.5 1022.79  5062.3 1025.13  5083.9 1026.37  5111.3 1031.61
    5143 1035.36  5207.7 1045.81  5282.6 1051.48  5353.2 1060.21  5398.5 1062.07
#Mann= 3 ,-1 , 0
  3932.4     .12       0  4992.4     .05       0  5014.2     .12       0
Bank Sta=4992.4,5014.2
XS Rating Curve= 0 ,0
Exp/Cntr=0.3,0.1

Type RM Length L Ch R = 1 ,54745   ,587,587,587
BEGIN DESCRIPTION:
West Fork 88.0
END DESCRIPTION:
XS GIS Cut Line= 3
        2187575.       13813225.        2186775.       13813225.
      2186375.01       13813125.
#Sta/Elev= 30
  4191.5 1063.43  4231.5  1061.8  4261.5 1057.83  4321.5 1052.65  4391.5 1049.92
  4471.5 1044.03  4491.5 1041.21  4511.5 1036.75  4581.5 1030.06    4605 1026.38
  4631.5  1023.2  4651.5 1022.65  4671.5 1023.67  4721.5 1029.07  4771.5 1029.47
  4931.5 1023.08  4971.5 1022.81  4994.1 1021.87  4998.6 1020.46  4999.1 1019.96
  5020.4 1020.46  5084.3 1023.95  5107.6 1028.13  5138.4 1036.32    5208 1039.08
  5249.2 1042.59  5256.9 1044.25  5298.2  1046.2  5331.7  1050.2  5403.8  1052.7
#Mann= 5 ,-1 , 0
  4191.5     .07       0    4605     .12       0  4998.6     .05       0
  5020.4     .12       0  5107.6     .12       0
Bank Sta=4998.6,5020.4
XS Rating Curve= 0 ,0
Exp/Cntr=0.3,0.1

Type RM Length L Ch R = 1 ,54158   ,531,531,531
BEGIN DESCRIPTION:
West Fork 87.0
END DESCRIPTION:
XS GIS Cut Line= 3
      2187525.01     13812624.99        2187175.       13812825.
      2186424.98       13812975.
#Sta/Elev= 30
  4596.9 1076.13  4691.2 1069.47  4796.6 1057.56  4809.3 1055.05  4825.1  1048.5
  4830.9 1048.16  4846.7 1044.18  4852.5  1043.8  4861.8 1040.44  4868.3 1034.48
  4874.1 1034.27  4884.1 1027.96  4889.9 1027.28  4896.4 1019.19  4937.7  1018.5
  4938.2    1018  4960.1  1018.5  5033.4 1021.19  5071.4 1022.73  5122.4 1021.14
  5211.3 1023.92  5256.4  1027.4  5312.4 1029.53  5377.4 1029.89  5428.3 1032.62
  5499.7 1034.26  5520.1 1035.51  5540.5  1038.9  5713.9 1044.42  5764.9 1048.08
#Mann= 8 ,-1 , 0
  4596.9     .07       0  4796.6     .12       0  4937.7     .05       0
  4960.1     .12       0  5033.4     .07       0  5211.3     .12       0
  5256.4     .07       0  5312.4     .12       0
Bank Sta=4937.7,4960.1
XS Rating Curve= 0 ,0
Exp/Cntr=0.3,0.1

Type RM Length L Ch R = 1 ,53627   ,557,557,557
BEGIN DESCRIPTION:
West Fork 86.0
END DESCRIPTION:
XS GIS Cut Line= 3
      2187474.97     13812175.02        2187125.       13812375.
      2186324.98     13812975.02
#Sta/Elev= 30
  4592.2 1088.22  4637.5 1087.31  4700.2 1084.06  4718.1 1083.39  4739.7  1079.8
  4857.1 1070.84  4877.8 1067.35  4914.7  1062.2  4922.6 1058.25  4937.7 1046.06
  4944.2 1027.58  4949.9 1023.25  4965.8 1018.97  4981.2 1010.09  4981.7 1009.59
  5003.6 1010.09  5017.1 1015.52  5034.1  1017.5  5045.3 1017.35  5051.3 1019.03
  5067.1 1020.96  5123.4 1023.98  5303.3 1026.53  5452.6 1030.51  5558.8 1031.86
  5623.4 1035.33  5673.4 1036.35  5731.7 1041.81  5867.1 1044.69  5995.3 1053.34
#Mann= 8 ,-1 , 0
  4592.2     .12       0  4700.2     .07       0  4877.8     .12       0
  4981.2     .05       0  5003.6     .12       0  5034.1     .07       0
  5051.3    .035       0  5303.3     .12       0
Bank Sta=4981.2,5003.6
XS Rating Curve= 0 ,0
Exp/Cntr=0.3,0.1

Type RM Length L Ch R = 1 ,53070   ,587,587,587
BEGIN DESCRIPTION:
West Fork 85.0
END DESCRIPTION:
XS GIS Cut Line= 3
      2187224.99       13811925.        2186825.       13811925.
      2186324.99     13812725.01
#Sta/Elev= 30
  4594.6 1077.24  4764.6 1062.37  4884.6 1055.21  4964.6 1045.21  4974.6 1042.36
  4984.6 1036.84  4992.1 1025.57  4997.5 1025.57  5002.3 1016.83  5008.1 1012.15
  5012.3 1010.12  5012.8 1009.62  5034.7 1010.12  5045.5 1012.67  5065.9 1012.94
  5096.6 1015.96  5124.3 1015.48  5154.4 1017.62  5175.6 1021.53  5196.8 1023.11
  5248.7 1025.47  5281.8 1025.36  5321.8 1023.39  5475.5 1025.24  5547.1 1026.55
  5626.1 1030.59  5735.7 1032.87  5830.1 1037.36  5866.6  1040.8    5938 1043.72
#Mann= 7 ,-1 , 0
  4594.6     .12       0  5012.3     .05       0  5034.7     .12       0
  5045.5     .07       0  5065.9     .12       0  5281.8    .035       0
  5475.5     .12       0
Bank Sta=5012.3,5034.7
XS Rating Curve= 0 ,0
Exp/Cntr=0.3,0.1

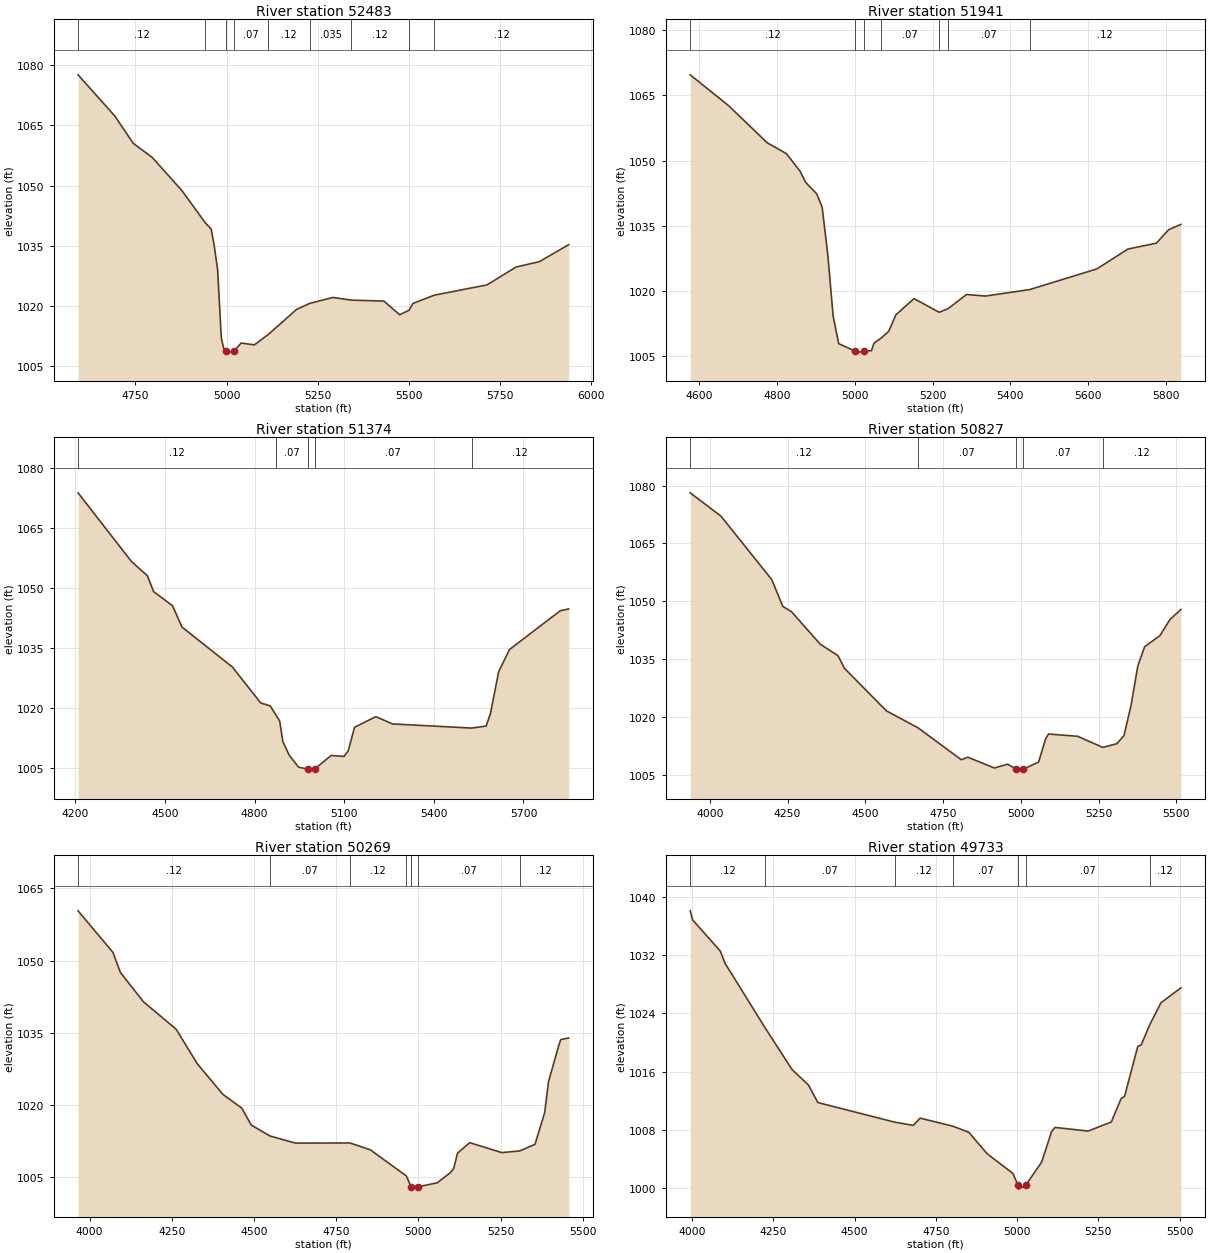
Type RM Length L Ch R = 1 ,52483   ,542,542,542
BEGIN DESCRIPTION:
West Fork 84.0
END DESCRIPTION:
XS GIS Cut Line= 3
      2186324.99     13811174.96        2186375.       13811575.
      2185874.98     13812375.04
#Sta/Elev= 30
  4592.6 1077.59  4693.4 1067.34  4743.8 1060.55  4796.7 1056.96  4877.3 1048.79
  4941.5 1040.76    4958 1039.15  4965.5 1035.46  4975.6 1029.07  4985.7 1012.03
  4993.2 1009.07  4998.1 1008.77  4998.6 1008.27  5020.6 1008.77    5040 1010.77
  5076.5 1010.33  5114.7 1012.92  5192.1 1019.15  5228.6 1020.67  5292.3 1022.14
  5342.5 1021.47  5432.1 1021.23  5475.1 1017.84  5500.7 1018.93  5511.7 1020.65
  5570.3 1022.71  5715.1 1025.27  5794.7 1029.72  5858.4 1031.05  5939.2 1035.29
#Mann= 9 ,-1 , 0
  4592.6     .12       0  4941.5     .07       0  4998.1     .05       0
  5020.6     .07       0  5114.7     .12       0  5228.6    .035       0
  5342.5     .12       0  5500.7     .07       0  5570.3     .12       0
Bank Sta=4998.1,5020.6
XS Rating Curve= 0 ,0
Exp/Cntr=0.3,0.1

Type RM Length L Ch R = 1 ,51941   ,567,567,567
BEGIN DESCRIPTION:
West Fork 83.0
END DESCRIPTION:
XS GIS Cut Line= 3
      2186175.02     13811224.98        2185875.       13811525.
      2185625.01     13812324.96
#Sta/Elev= 30
  4576.2 1069.75  4675.2 1062.64  4774.2 1054.13  4823.7 1051.63  4859.1 1047.56
  4873.2 1045.02  4901.5 1042.41  4915.6 1039.35  4929.8 1028.69  4943.9 1014.33
  4958.1 1007.95  4999.7 1006.26  5000.2 1005.76  5022.2 1006.26  5042.4 1006.31
  5049.2 1008.07  5067.4 1009.21  5086.9 1010.77  5105.3 1014.56  5151.9  1018.3
    5217 1015.14  5240.4 1016.03    5287 1019.24  5335.7 1018.88  5449.8 1020.38
  5622.3 1025.12  5702.4 1029.69  5775.8 1031.05  5807.2 1034.15  5838.6 1035.36
#Mann= 7 ,-1 , 0
  4576.2     .12       0  4999.7     .05       0  5022.2     .12       0
  5067.4     .07       0    5217     .12       0  5240.4     .07       0
  5449.8     .12       0
Bank Sta=4999.7,5022.2
XS Rating Curve= 0 ,0
Exp/Cntr=0.3,0.1

Type RM Length L Ch R = 1 ,51374   ,547,547,547
BEGIN DESCRIPTION:
West Fork 82.0
END DESCRIPTION:
XS GIS Cut Line= 3
      2185575.01     13810724.97        2185325.       13811475.
      2184674.98     13812025.02
#Sta/Elev= 30
  4209.4  1073.7  4388.6 1056.52  4441.3 1053.03  4462.4 1049.05  4525.7 1045.52
  4557.3  1040.2  4725.9 1030.25  4820.8 1021.28  4852.4 1020.56  4870.4 1018.43
  4884.1 1016.78  4894.6 1011.69  4915.7 1008.29  4947.3 1005.27  4978.2 1004.78
  4978.7 1004.28  5000.8 1004.78  5056.6 1008.18  5099.4 1007.95  5113.7 1009.37
  5134.6 1015.22    5206 1017.87    5262 1016.05  5526.5 1015.02  5575.2 1015.53
  5589.5 1018.63  5616.9 1029.05  5653.2 1034.61  5823.5  1044.3  5851.5 1044.73
#Mann= 5 ,-1 , 0
  4209.4     .12       0  4870.4     .07       0  4978.2     .05       0
  5000.8     .07       0  5526.5     .12       0
Bank Sta=4978.2,5000.8
XS Rating Curve= 0 ,0
Exp/Cntr=0.3,0.1

Type RM Length L Ch R = 1 ,50827   ,558,558,558
BEGIN DESCRIPTION:
West Fork 81.0
END DESCRIPTION:
XS GIS Cut Line= 3
      2185524.97     13810625.04        2184825.       13811425.
      2184575.02     13811874.96
#Sta/Elev= 30
  3936.9 1078.13    4036 1072.06  4199.3 1055.59  4234.4 1048.67  4262.9 1047.26
  4354.9 1038.85  4411.9 1035.88  4432.8 1032.59  4567.5 1021.56  4670.1  1017.1
  4808.6 1008.85  4829.5 1009.51  4914.9 1006.72  4957.6 1007.71  4985.2  1006.4
  4985.7  1005.9  5007.8  1006.4  5057.1 1008.26  5079.9 1014.33  5089.1 1015.53
  5182.9 1014.94  5263.4 1012.06  5308.7 1013.02  5331.6 1015.12  5354.5 1023.01
  5376.2 1033.22    5398 1038.18  5447.2 1041.08  5479.2 1045.22  5514.6 1047.85
#Mann= 5 ,-1 , 0
  3936.9     .12       0  4670.1     .07       0  4985.2     .05       0
  5007.8     .07       0  5263.4     .12       0
Bank Sta=4985.2,5007.8
XS Rating Curve= 0 ,0
Exp/Cntr=0.3,0.1

Type RM Length L Ch R = 1 ,50269   ,536,536,536
BEGIN DESCRIPTION:
West Fork 80.0
END DESCRIPTION:
XS GIS Cut Line= 3
        2185175.       13810475.        2184375.       13811125.
      2184274.99     13811575.05
#Sta/Elev= 30
  3965.2 1060.36  4071.5  1051.7  4093.8 1047.56  4164.2 1041.45  4263.3 1035.77
  4327.2 1028.64  4405.5 1022.23    4463 1019.37  4491.7 1015.86  4548.4 1013.59
    4626  1012.1  4791.9 1012.13  4854.2 1010.69  4963.3 1005.28  4977.5 1003.04
    4978 1002.54  5000.1 1003.04  5057.4 1003.86  5098.4 1006.03  5107.4 1006.87
  5118.9 1010.01    5156 1012.19  5253.4 1010.13  5307.9 1010.47  5354.5 1011.86
    5384 1018.47  5395.5 1024.85  5426.2 1032.27  5432.6  1033.6    5457 1033.95
#Mann= 7 ,-1 , 0
  3965.2     .12       0  4548.4     .07       0  4791.9     .12       0
  4963.3     .07       0  4977.5     .05       0  5000.1     .07       0
  5307.9     .12       0
Bank Sta=4977.5,5000.1
XS Rating Curve= 0 ,0
Exp/Cntr=0.3,0.1

Type RM Length L Ch R = 1 ,49733   ,593,593,593
BEGIN DESCRIPTION:
West Fork 79.0
END DESCRIPTION:
XS GIS Cut Line= 3
      2184525.01     13810074.99        2183925.       13810875.
        2184025.     13811374.99
#Sta/Elev= 30
  3994.3 1038.11  4001.6 1036.87    4087 1032.57  4101.6 1030.89  4224.2 1022.07
  4307.9 1016.28  4357.9 1014.18    4387 1011.76  4623.3 1009.07  4680.8 1008.62
  4701.6 1009.62  4802.5 1008.51  4851.6 1007.67  4907.9 1004.73    4987 1002.03
  5003.4 1000.36  5003.9  999.86  5026.1 1000.36  5075.9 1003.59  5106.5  1007.8
  5116.7 1008.34  5218.7 1007.84  5290.1 1009.09  5320.6 1012.33  5330.8 1012.59
  5371.6 1019.49  5381.8 1019.66  5408.5 1022.46    5443 1025.48  5504.2 1027.52
#Mann= 7 ,-1 , 0
  3994.3     .12       0  4224.2     .07       0  4623.3     .12       0
  4802.5     .07       0  5003.4     .05       0  5026.1     .07       0
  5408.5     .12       0
Bank Sta=5003.4,5026.1
XS Rating Curve= 0 ,0
Exp/Cntr=0.3,0.1

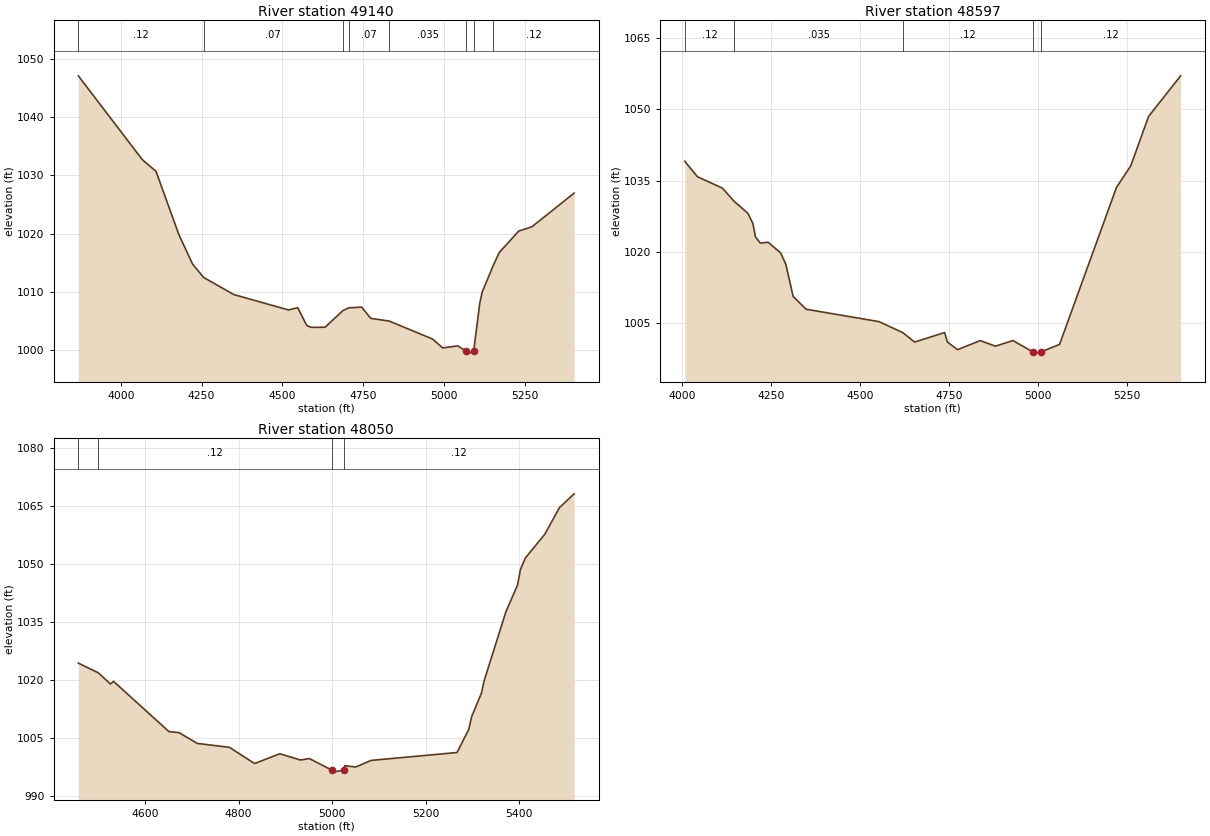
Type RM Length L Ch R = 1 ,49140   ,543,543,543
BEGIN DESCRIPTION:
West Fork 78.0
END DESCRIPTION:
XS GIS Cut Line= 3
      2184275.02     13809724.98        2183475.       13810525.
      2183075.01       13810575.
#Sta/Elev= 30
  3868.8 1047.07  4066.8 1032.68  4109.2 1030.68    4180 1019.81  4222.4 1014.75
  4256.5 1012.47  4349.7 1009.53  4519.4 1006.88  4547.6 1007.28  4575.9 1004.21
  4590.1 1003.89  4632.5 1003.92  4687.5 1006.77  4706.2 1007.25  4745.6 1007.37
  4773.9 1005.44  4831.1 1004.97  4964.8  1001.9  4996.7 1000.37    5043 1000.72
  5069.3   999.8  5069.8   999.3  5092.3   999.8  5111.1    1008  5118.6 1009.94
  5152.9 1014.51  5171.5 1016.74    5232 1020.43  5272.3 1021.15  5403.3 1026.94
#Mann= 8 ,-1 , 0
  3868.8     .12       0  4256.5     .07       0  4687.5    .035       0
  4706.2     .07       0  4831.1    .035       0  5069.3    .035       0
  5092.3    .035       0  5152.9     .12       0
Bank Sta=5069.3,5092.3
XS Rating Curve= 0 ,0
Exp/Cntr=0.3,0.1

Type RM Length L Ch R = 1 ,48597   ,547,547,547
BEGIN DESCRIPTION:
West Fork 77.0
END DESCRIPTION:
XS GIS Cut Line= 3
      2183874.98     13809525.01        2183125.       13810175.
      2182724.95       13810175.
#Sta/Elev= 30
  4007.5 1039.05  4043.1  1035.8  4113.3  1033.4  4145.8 1030.64  4184.6 1028.11
  4198.8 1025.93    4206 1023.11  4219.7 1021.81  4241.6 1021.99  4276.7 1019.74
    4291 1017.39  4311.8 1010.57    4348 1007.87  4553.1 1005.25  4620.1 1002.92
  4652.8 1000.94  4737.3 1002.95    4745 1000.95  4773.5  999.34  4837.1 1001.25
  4879.8 1000.08  4929.2 1001.26  4984.4   998.9  4984.9   998.4  5008.9   998.9
    5060 1000.45    5220 1033.57    5260  1038.1    5310 1048.52    5400 1057.08
#Mann= 5 ,-1 , 0
  4007.5     .12       0  4145.8    .035       0  4620.1     .12       0
  4984.4     .05       0  5008.9     .12       0
Bank Sta=4984.4,5008.9
XS Rating Curve= 0 ,0
Exp/Cntr=0.3,0.1

Type RM Length L Ch R = 1 ,48050   ,561,561,561
BEGIN DESCRIPTION:
West Fork 76.0
END DESCRIPTION:
XS GIS Cut Line= 3
      2183575.04     13809524.98        2183075.       13809725.
      2182574.98     13809875.01
#Sta/Elev= 30
  4457.3 1024.36  4500.1 1021.85    4526 1018.96  4532.7 1019.63  4651.2 1006.61
  4672.8 1006.35  4711.8 1003.55  4780.5 1002.54  4834.3  998.34  4888.2 1000.87
  4932.6  999.25  4951.4  999.63  5000.1  996.61  5000.6  996.11  5024.6  996.61
  5027.2  997.78  5050.7  997.44  5083.7  999.15  5267.3 1001.19  5292.5  1007.2
  5298.6 1010.49  5319.5 1016.57  5325.6  1019.9  5371.7  1037.6  5396.9 1044.65
    5403 1048.64  5413.5 1051.62  5455.2 1057.79  5486.6  1064.7  5517.9 1068.25
#Mann= 4 ,-1 , 0
  4457.3    .035       0  4500.1     .12       0  5000.1     .05       0
  5024.6     .12       0
Bank Sta=5000.1,5024.6
XS Rating Curve= 0 ,0
Exp/Cntr=0.3,0.1