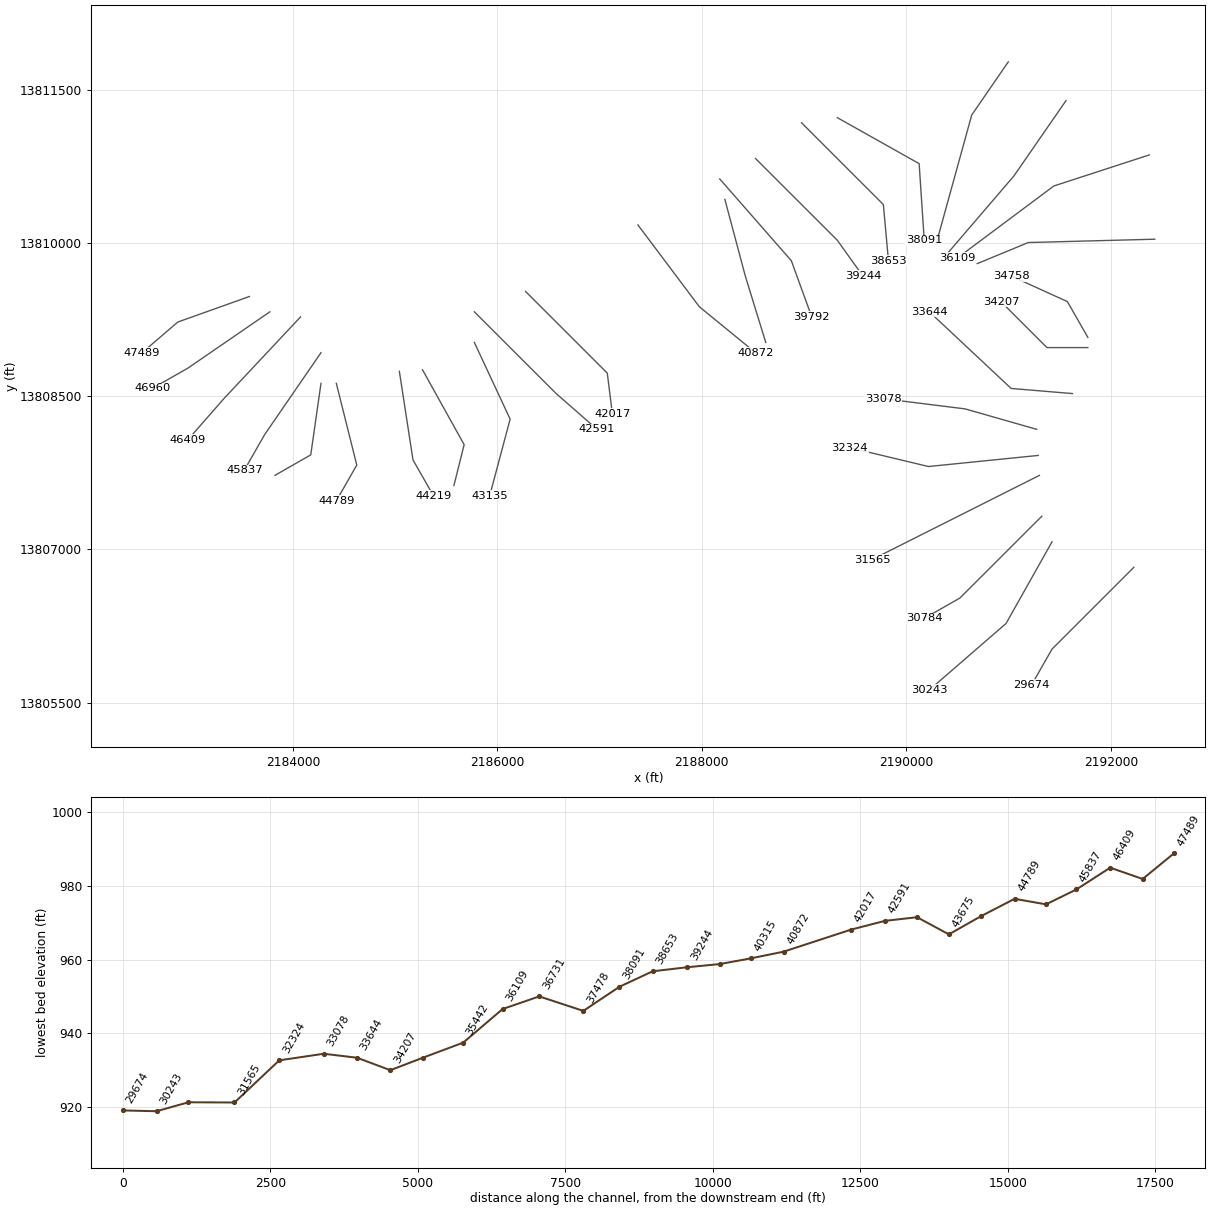
HEC-RAS study West Fork Dry Comal Creek.prj: West Fork Dry Comal Creek

--- West Fork Dry Comal Creek.g01 (geometry) --- (continued)

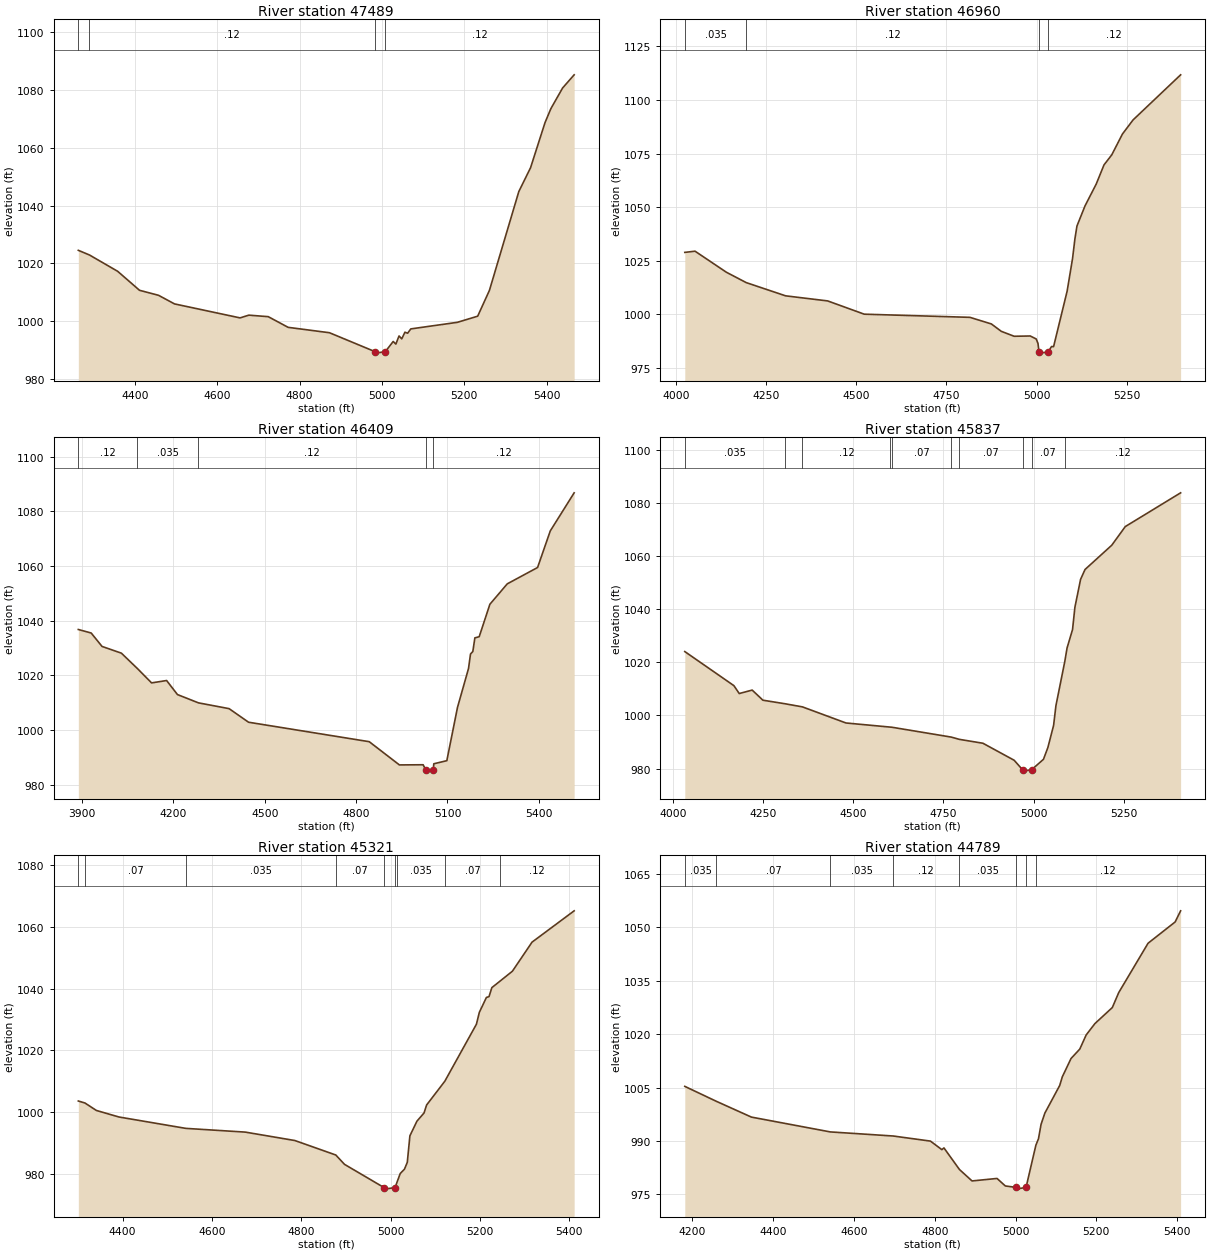
Type RM Length L Ch R = 1 ,47489   ,529,529,529
BEGIN DESCRIPTION:
West Fork 75.0
END DESCRIPTION:
XS GIS Cut Line= 3
      2183574.96     13809474.99        2182875.       13809225.
      2182525.03     13808925.02
#Sta/Elev= 30
  4262.7 1024.46  4289.8 1022.84  4358.2 1017.19  4411.3  1010.6  4457.5 1008.86
  4496.3 1005.88  4655.5 1001.03  4676.8 1001.98    4724 1001.45  4772.3  997.75
  4872.7  995.88  4983.5  989.31    4984  988.81  5008.2  989.31  5027.4  992.85
  5033.9  991.94  5041.6  994.77  5048.2  993.76  5055.9  996.06  5062.5  995.72
  5070.2  997.21  5183.2  999.49  5232.6 1001.62  5261.1 1010.56  5332.5 1044.84
    5361  1053.1  5396.1 1068.74  5410.4  1073.6  5438.9 1080.77  5466.9 1085.32
#Mann= 4 ,-1 , 0
  4262.7    .035       0  4289.8     .12       0  4983.5     .05       0
  5008.2     .12       0
Bank Sta=4983.5,5008.2
XS Rating Curve= 0 ,0
Exp/Cntr=0.3,0.1

Type RM Length L Ch R = 1 ,46960   ,551,551,551
BEGIN DESCRIPTION:
West Fork 74.0
END DESCRIPTION:
XS GIS Cut Line= 3
        2183775.       13809325.        2182975.       13808775.
      2182625.03     13808575.02
#Sta/Elev= 30
  4025.2 1028.89  4053.6 1029.45  4140.2 1019.65  4195.3 1014.79  4304.6 1008.61
    4421 1006.24  4522.5 1000.05  4815.4  998.57  4874.7  995.49    4902  992.06
  4937.8  989.74  4982.5  989.87  4998.9  988.48  5003.9  986.39  5006.7  982.37
  5007.2  981.87  5031.4  982.37  5041.4  984.94  5047.1   984.9  5084.6 1010.78
  5099.7 1026.08  5106.2 1035.24  5111.9 1041.23  5134.2  1050.6  5165.2 1060.78
  5186.8 1069.73  5208.4 1074.45  5237.9 1084.14  5267.4 1090.73  5399.1 1111.77
#Mann= 4 ,-1 , 0
  4025.2    .035       0  4195.3     .12       0  5006.7     .05       0
  5031.4     .12       0
Bank Sta=5006.7,5031.4
XS Rating Curve= 0 ,0
Exp/Cntr=0.3,0.1

Type RM Length L Ch R = 1 ,46409   ,572,572,572
BEGIN DESCRIPTION:
West Fork 73.0
END DESCRIPTION:
XS GIS Cut Line= 3
      2184074.99     13809274.99        2183325.       13808475.
      2182974.99     13808074.98
#Sta/Elev= 30
    3888 1036.76  3930.2 1035.47  3965.9 1030.56  4029.4  1028.1  4082.2 1022.45
  4128.5 1017.22  4177.9 1018.09  4213.5 1012.95  4282.4 1009.92    4383  1007.8
    4447 1002.83  4843.2  995.71  4942.3  987.21  5020.2  987.27  5028.7  985.44
  5029.2  984.94  5053.4  985.44  5055.3  987.63    5098  988.76  5133.1 1008.29
  5169.2 1022.47  5175.8 1027.79  5183.4 1028.71  5190.1 1033.69  5204.3 1034.12
  5239.4 1045.99  5296.4 1053.45    5396 1059.44  5437.8 1072.84  5516.1 1086.76
#Mann= 5 ,-1 , 0
    3888     .12       0  4082.2    .035       0  4282.4     .12       0
  5028.7     .05       0  5053.4     .12       0
Bank Sta=5028.7,5053.4
XS Rating Curve= 0 ,0
Exp/Cntr=0.3,0.1

Type RM Length L Ch R = 1 ,45837   ,516,516,516
BEGIN DESCRIPTION:
West Fork 72.0
END DESCRIPTION:
XS GIS Cut Line= 3
      2184275.02     13808925.03        2183725.       13808125.
      2183524.99     13807774.98
#Sta/Elev= 30
  4033.2  1024.1  4169.2 1011.26  4184.1 1008.28    4220 1009.58  4249.7 1005.76
  4309.5 1004.46  4359.2 1003.25  4479.8  997.18  4603.1  995.62  4608.3  995.55
  4771.8  991.85  4793.9  991.01  4859.3  989.54  4945.9  983.13  4969.3  979.53
  4969.8  979.03  4994.1  979.53  5027.1  983.48  5039.3   987.9  5055.2  996.27
  5061.6 1003.67  5086.2 1020.36  5092.6 1025.49  5107.7  1032.4  5114.2 1040.77
    5130 1051.33  5142.3 1055.04  5216.4 1064.19  5253.8 1071.21  5407.2 1083.94
#Mann= 10 ,-1 , 0
  4033.2    .035       0  4309.5     .07       0  4359.2     .12       0
  4603.1    .035       0  4608.3     .07       0  4771.8    .035       0
  4793.9     .07       0  4969.3     .05       0  4994.1     .07       0
  5086.2     .12       0
Bank Sta=4969.3,4994.1
XS Rating Curve= 0 ,0
Exp/Cntr=0.3,0.1

Type RM Length L Ch R = 1 ,45321   ,532,532,532
BEGIN DESCRIPTION:
West Fork 71.0
END DESCRIPTION:
XS GIS Cut Line= 3
        2184275.     13808625.02        2184175.       13807925.
      2183825.03     13807725.02
#Sta/Elev= 30
  4300.9 1003.55  4315.8  1002.9  4341.3 1000.49  4391.8  998.37  4541.6  994.68
  4674.7  993.47  4785.8  990.74  4877.4  986.05  4896.9  983.02  4985.5  975.49
    4986  974.99  5010.3  975.49  5014.3  977.17  5021.7  980.05  5031.1  981.45
  5037.5  983.68  5043.3  992.27  5059.1  997.02    5075  999.68  5080.7 1002.25
  5121.5 1009.96  5192.3 1028.45  5198.8 1032.29  5214.6 1037.11  5220.4 1037.37
  5226.9 1040.31  5245.6 1042.46  5272.9 1045.63  5316.8 1055.04  5411.1 1065.19
#Mann= 9 ,-1 , 0
  4300.9    .035       0  4315.8     .07       0  4541.6    .035       0
  4877.4     .07       0  4985.5     .05       0  5010.3     .07       0
  5014.3    .035       0  5121.5     .07       0  5245.6     .12       0
Bank Sta=4985.5,5010.3
XS Rating Curve= 0 ,0
Exp/Cntr=0.3,0.1

Type RM Length L Ch R = 1 ,44789   ,570,570,570
BEGIN DESCRIPTION:
West Fork 70.0
END DESCRIPTION:
XS GIS Cut Line= 3
        2184425.     13808625.01        2184625.       13807825.
      2184425.02     13807475.04
#Sta/Elev= 30
    4181 1005.35  4259.4 1001.14  4345.9  996.72  4541.2  992.56  4696.9  991.41
  4789.2  989.98  4817.5  987.58  4822.7  988.06  4861.1     982  4892.2  978.79
  4954.1  979.49  4974.7  977.38  5001.2  976.99  5001.7  976.49    5026  976.99
  5050.3  988.83  5056.7  990.62  5063.2  994.71  5072.6  997.85  5109.3  1005.6
  5115.8 1008.04  5137.4 1013.18    5159 1015.82  5174.8 1019.78  5196.4 1022.97
  5239.6 1027.49  5255.4 1031.68  5328.1 1045.55  5395.1 1051.52  5408.7 1054.65
#Mann= 8 ,-1 , 0
    4181    .035       0  4259.4     .07       0  4541.2    .035       0
  4696.9     .12       0  4861.1    .035       0  5001.2    .035       0
    5026    .035       0  5050.3     .12       0
Bank Sta=5001.2,5026
XS Rating Curve= 0 ,0
Exp/Cntr=0.3,0.1

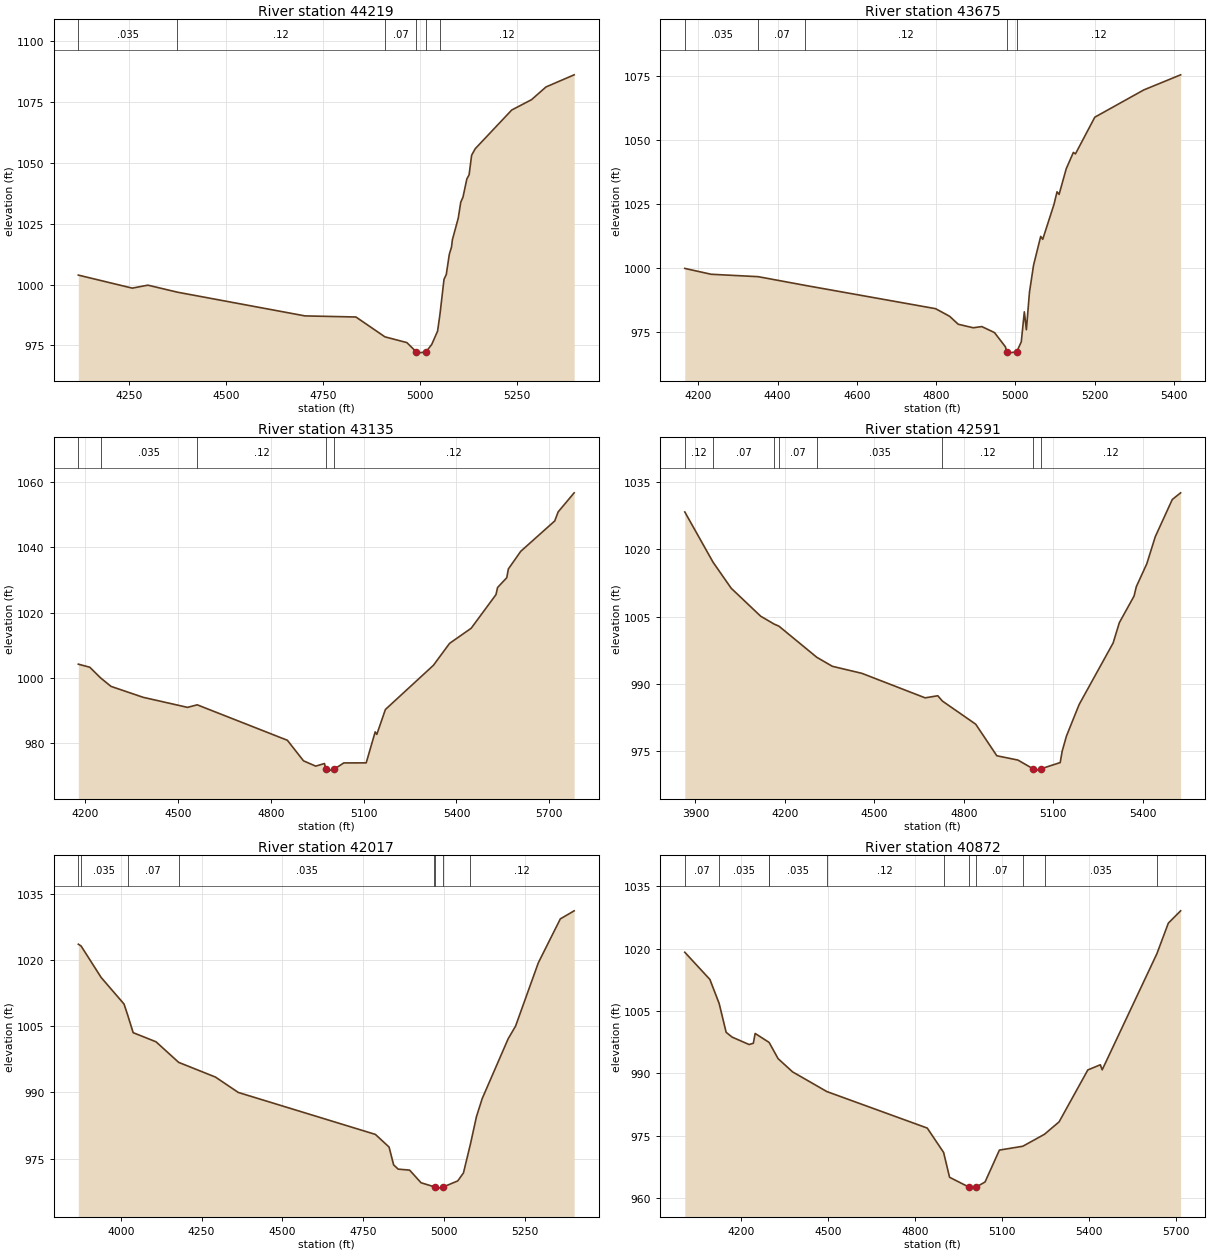
Type RM Length L Ch R = 1 ,44219   ,544,544,544
BEGIN DESCRIPTION:
West Fork 69.0
END DESCRIPTION:
XS GIS Cut Line= 4
      2185041.52     13808742.65        2185075.       13808525.
        2185175.       13807875.      2185375.01     13807524.97
#Sta/Elev= 30
  4117.9 1003.87  4257.2  998.51  4297.6  999.73    4374  996.84  4703.6  987.09
  4835.1  986.64    4910  978.48  4966.7  976.11  4991.2  972.28  4991.7  971.78
  5016.1  972.28    5031  975.37  5046.1  980.86  5052.3   987.9  5062.7 1002.15
  5068.5  1004.1  5076.4 1012.45  5082.1 1015.44  5084.3 1018.42  5099.4 1027.26
  5105.9 1033.82  5111.7 1035.95  5121.7 1043.44  5127.5 1045.13    5134 1053.16
  5143.3 1055.84  5237.6 1071.76  5288.7    1076  5326.2 1081.25  5398.9 1086.23
#Mann= 6 ,-1 , 0
  4117.9    .035       0    4374     .12       0    4910     .07       0
  4991.2     .05       0  5016.1     .07       0  5052.3     .12       0
Bank Sta=4991.2,5016.1
XS Rating Curve= 0 ,0
Exp/Cntr=0.3,0.1

Type RM Length L Ch R = 1 ,43675   ,540,540,540
BEGIN DESCRIPTION:
West Fork 68.0
END DESCRIPTION:
XS GIS Cut Line= 4
      2185267.74     13808758.06        2185425.       13808475.
        2185675.       13808025.        2185575.     13807625.01
#Sta/Elev= 30
    4166  999.95  4232.4  997.66  4351.1  996.72    4470  993.31  4798.7  984.22
  4834.1  981.24  4855.9  978.13  4893.6  976.76  4915.4  977.22  4947.4  974.87
  4974.9  969.31  4978.4  967.35  4978.9  966.85  5003.3  967.35  5014.9  971.27
  5022.6  982.98  5027.8  975.99  5035.5  990.57  5045.8 1001.15  5063.9 1012.46
    5069 1011.32  5097.4 1024.96  5105.1 1029.88  5110.3 1028.87  5128.3 1038.88
  5146.3 1045.27  5151.5 1044.69  5200.4 1059.03  5324.1 1069.69  5416.9 1075.58
#Mann= 5 ,-1 , 0
    4166    .035       0  4351.1     .07       0    4470     .12       0
  4978.4     .05       0  5003.3     .12       0
Bank Sta=4978.4,5003.3
XS Rating Curve= 0 ,0
Exp/Cntr=0.3,0.1

Type RM Length L Ch R = 1 ,43135   ,544,544,544
BEGIN DESCRIPTION:
West Fork 67.0
END DESCRIPTION:
XS GIS Cut Line= 3
      2185774.98     13809025.03        2186125.       13808275.
        2185925.     13807524.99
#Sta/Elev= 30
  4176.9 1004.23    4214 1003.29  4248.9 1000.03  4282.6  997.43  4386.6  994.09
  4530.1  991.01  4561.5  991.79  4853.2  980.94  4905.3  974.65  4944.7  973.03
  4973.1  973.83  4977.8     972  4978.3   971.5  5002.9     972  5035.6  974.01
  5108.1  974.03  5137.2  983.51  5142.4  982.74  5170.2  990.36  5325.4 1003.87
  5377.8 1010.59  5447.7 1015.22  5527.9 1025.51  5533.1 1027.69  5562.8 1030.69
    5568 1033.37  5608.1 1038.77    5718 1048.06    5729 1050.82  5780.8 1056.66
#Mann= 5 ,-1 , 0
  4176.9     .07       0  4248.9    .035       0  4561.5     .12       0
  4977.8     .05       0  5002.9     .12       0
Bank Sta=4977.8,5002.9
XS Rating Curve= 0 ,0
Exp/Cntr=0.3,0.1

Type RM Length L Ch R = 1 ,42591   ,574,574,574
BEGIN DESCRIPTION:
West Fork 66.0
END DESCRIPTION:
XS GIS Cut Line= 3
        2185775.       13809325.        2186575.       13808525.
      2186975.02     13808174.98
#Sta/Elev= 30
  3864.2 1028.37  3958.9 1017.16  4019.8 1011.34  4118.8 1005.09  4164.6 1003.31
  4179.8 1002.88  4306.8  995.93  4359.2  993.91  4458.2  992.34  4670.3  986.87
  4712.7  987.34    4728  986.16    4840  980.98  4910.7  973.94  4981.4  972.98
  5032.8  971.01  5033.3  970.51  5057.9  971.01  5123.2  972.42  5129.9  974.97
  5144.1  978.32  5186.8  985.39  5300.7  999.11  5321.6 1003.66  5370.9 1009.59
  5378.5 1011.69  5413.7 1016.81  5442.1 1022.85  5499.1 1031.15  5527.1 1032.64
#Mann= 8 ,-1 , 0
  3864.2     .12       0  3958.9     .07       0  4164.6    .035       0
  4179.8     .07       0  4306.8    .035       0    4728     .12       0
  5032.8     .05       0  5057.9     .12       0
Bank Sta=5032.8,5057.9
XS Rating Curve= 0 ,0
Exp/Cntr=0.3,0.1

Type RM Length L Ch R = 1 ,42017   ,1145,1145,1145
BEGIN DESCRIPTION:
West Fork 65.0
END DESCRIPTION:
XS GIS Cut Line= 3
      2186274.99     13809525.01        2187075.       13808725.
        2187125.       13808325.
#Sta/Elev= 30
  3868.6 1023.54  3877.2 1023.13  3939.3 1016.01    4010 1010.01  4020.8 1007.64
  4038.3 1003.53    4109 1001.47  4179.2  996.81  4292.9  993.49  4363.6  990.01
  4787.9  980.52  4830.3  977.66  4844.4  973.63  4858.6  972.66  4893.9  972.44
  4929.3  969.58  4970.4  968.66  4973.2  968.64  4973.7  968.14  4998.4  968.64
  5042.8     970  5060.5   971.8  5082.1  978.34  5100.8  984.56  5118.4   988.6
    5199 1002.17  5221.7    1005  5292.2 1019.33  5360.3 1029.27  5403.1 1031.09
#Mann= 8 ,-1 , 0
  3868.6     .12       0  3877.2    .035       0  4020.8     .07       0
  4179.2    .035       0  4970.4     .07       0  4973.2     .05       0
  4998.4     .07       0  5082.1     .12       0
Bank Sta=4973.2,4998.4
XS Rating Curve= 0 ,0
Exp/Cntr=0.3,0.1

Type RM Length L Ch R = 1 ,40872   ,557,557,557
BEGIN DESCRIPTION:
West Fork 63.0
END DESCRIPTION:
XS GIS Cut Line= 3
        2187375.     13810175.01        2187975.       13809375.
      2188524.97     13808925.03
#Sta/Elev= 30
  4004.5 1019.14    4091 1012.61  4123.1 1006.81  4147.2  999.87    4168  998.72
  4226.4  996.94    4241  997.25  4247.2   999.6  4294.1  997.51  4295.9  997.39
  4326.4  993.54  4376.4  990.36  4494.7  985.62    4841  976.84  4897.4  970.98
    4918     965  4984.5  962.65    4985  962.15  5009.9  962.65  5040.4  963.87
  5089.9  971.54  5170.8  972.47  5245.6  975.36  5295.9  978.34    5395  990.83
  5438.1  992.07  5444.5  990.85  5633.2 1018.79  5672.8 1026.16  5715.1 1029.11
#Mann= 11 ,-1 , 0
  4004.5     .07       0  4123.1    .035       0  4294.1     .07       0
  4295.9    .035       0  4494.7     .12       0  4897.4     .07       0
  4984.5     .05       0  5009.9     .07       0  5170.8     .12       0
  5245.6    .035       0  5633.2     .12       0
Bank Sta=4984.5,5009.9
XS Rating Curve= 0 ,0
Exp/Cntr=0.3,0.1

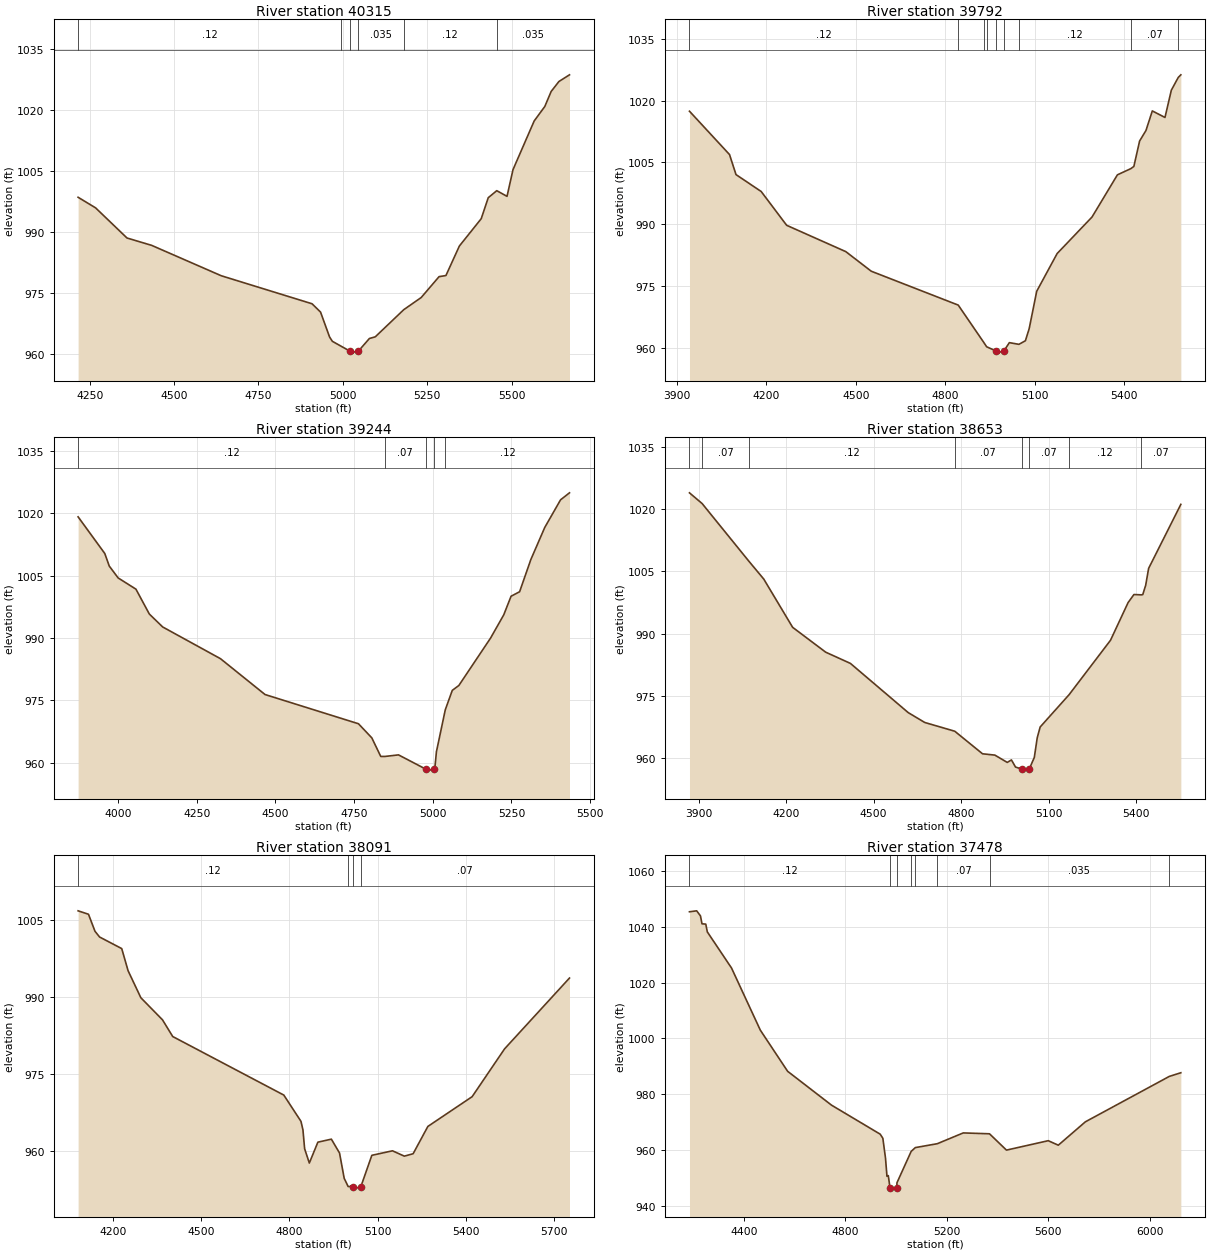
Type RM Length L Ch R = 1 ,40315   ,523,523,523
BEGIN DESCRIPTION:
West Fork 62.0
END DESCRIPTION:
XS GIS Cut Line= 3
        2188225.     13810425.01        2188425.       13809675.
        2188625.     13809024.99
#Sta/Elev= 30
  4215.4  998.64  4267.2  996.04  4360.3  988.63  4433.4  986.82  4639.7  979.35
  4908.8  972.46    4934  970.41  4960.6  964.31    4969  963.23  4993.6  962.09
  5020.7  960.83  5021.2  960.33  5046.2  960.83  5078.6  963.92  5096.2  964.34
  5180.7  971.02  5232.3     974  5285.2  979.13  5305.5   979.4  5345.4  986.66
  5410.1  993.37    5431  998.54  5456.2 1000.26  5486.6  998.87  5504.3 1005.43
  5567.1  1017.4  5598.5 1020.95  5617.4 1024.65  5640.3 1027.09  5671.7 1028.74
#Mann= 6 ,-1 , 0
  4215.4     .12       0  4993.6    .035       0  5020.7    .035       0
  5046.2    .035       0  5180.7     .12       0  5456.2    .035       0
Bank Sta=5020.7,5046.2
XS Rating Curve= 0 ,0
Exp/Cntr=0.3,0.1

Type RM Length L Ch R = 1 ,39792   ,548,548,548
BEGIN DESCRIPTION:
West Fork 61.0
END DESCRIPTION:
XS GIS Cut Line= 3
      2188175.02     13810624.98        2188875.       13809825.
      2189074.99     13809275.02
#Sta/Elev= 30
  3941.7 1017.42    4076 1006.92  4097.8 1002.06  4182.3  997.96  4267.7  989.77
  4466.1  983.39  4551.5  978.64  4843.2  970.43    4929  961.37  4938.5  960.33
  4970.5  959.29    4971  958.79  4996.1  959.29  5014.7  961.33  5046.7  960.92
  5068.5  961.79  5081.2  964.72  5106.4  973.78  5174.9  982.92    5292  991.78
  5377.1    1002  5422.6 1003.52  5432.3 1004.04  5451.6  1010.2  5472.9 1012.75
  5494.2 1017.49  5536.7 1015.91    5558 1022.51  5581.1 1025.59  5589.9 1026.24
#Mann= 9 ,-1 , 0
  3941.7     .12       0  4843.2     .07       0    4929    .035       0
  4938.5     .07       0  4970.5     .05       0  4996.1     .07       0
  5046.7     .12       0  5422.6     .07       0  5581.1     .12       0
Bank Sta=4970.5,4996.1
XS Rating Curve= 0 ,0
Exp/Cntr=0.3,0.1

Type RM Length L Ch R = 1 ,39244   ,591,591,591
BEGIN DESCRIPTION:
West Fork 60.0
END DESCRIPTION:
XS GIS Cut Line= 3
        2188525.       13810825.        2189325.       13810025.
      2189575.01     13809674.98
#Sta/Elev= 30
    3873 1019.12  3957.8  1010.3    3972 1007.28  4000.3 1004.42  4056.8 1001.72
  4099.3  995.74  4141.7  992.63  4325.5  984.99    4467  976.37  4763.9  969.34
  4806.4  965.94  4834.7  961.48  4847.9  961.47  4891.2  961.85  4977.4  958.44
  4977.9  957.94    5003  958.44  5007.4  959.25  5011.7  962.61  5039.9  972.72
  5062.1  977.37    5083  978.55  5183.8  989.96  5225.6  995.54  5248.9 1000.02
    5276  1001.1  5311.6 1008.82  5355.8 1016.55  5406.2 1023.22  5434.5  1024.9
#Mann= 5 ,-1 , 0
    3873     .12       0  4847.9     .07       0  4977.4     .05       0
    5003     .07       0  5039.9     .12       0
Bank Sta=4977.4,5003
XS Rating Curve= 0 ,0
Exp/Cntr=0.3,0.1

Type RM Length L Ch R = 1 ,38653   ,562,562,562
BEGIN DESCRIPTION:
West Fork 59.0
END DESCRIPTION:
XS GIS Cut Line= 3
      2188975.02     13811174.98        2189775.       13810375.
        2189825.     13809825.01
#Sta/Elev= 30
  3868.9 1023.93  3912.2 1021.35  4072.8 1007.41  4123.4 1003.14  4222.4   991.5
  4335.6  985.51  4420.4   982.8  4618.4  970.94    4675  968.56  4777.9  966.45
    4873  961.01  4915.4  960.69  4957.8  958.93    4972  959.53  4986.1  957.81
  5007.5  957.33    5008  956.83  5033.1  957.33  5050.4  960.12  5060.5  964.89
  5070.5  967.47  5169.6  975.26  5311.5  988.38  5371.8  997.47  5391.8  999.41
  5416.6  999.33    5422  999.39    5432 1001.63  5442.1 1005.71  5552.5 1021.15
#Mann= 8 ,-1 , 0
  3868.9     .12       0  3912.2     .07       0  4072.8     .12       0
  4777.9     .07       0  5007.5     .05       0  5033.1     .07       0
  5169.6     .12       0  5416.6     .07       0
Bank Sta=5007.5,5033.1
XS Rating Curve= 0 ,0
Exp/Cntr=0.3,0.1

Type RM Length L Ch R = 1 ,38091   ,613,613,613
BEGIN DESCRIPTION:
West Fork 58.0
END DESCRIPTION:
XS GIS Cut Line= 3
      2189325.03     13811224.98        2190125.       13810775.
        2190175.     13810025.01
#Sta/Elev= 30
  4082.2 1006.88  4117.5 1006.21  4139.5  1002.9  4155.1 1001.78  4230.4  999.52
    4252  995.21  4295.4  989.94    4369  985.63  4403.7  982.38  4781.1  970.97
  4839.4  965.85  4846.1   964.2  4851.8  960.52  4867.8  957.72  4896.8  961.79
  4942.7  962.38  4970.4  959.68  4986.3  954.74  4999.7  953.15  5017.3  953.14
  5017.8  952.64    5043  953.14  5080.2  959.23  5150.4  960.11  5190.5  959.07
  5220.5  959.54  5270.6  964.86    5421  970.66  5531.2  979.98  5751.7  993.78
#Mann= 4 ,-1 , 0
  4082.2     .12       0  4999.7     .07       0  5017.3     .05       0
    5043     .07       0
Bank Sta=5017.3,5043
XS Rating Curve= 0 ,0
Exp/Cntr=0.3,0.1

Type RM Length L Ch R = 1 ,37478   ,747,747,747
BEGIN DESCRIPTION:
H21660
END DESCRIPTION:
XS GIS Cut Line= 3
      2190997.33     13811771.67      2190639.24     13811250.81
      2190292.02      13809992.1
#Sta/Elev= 30
  4185.4 1045.33  4213.8 1045.67  4228.7 1043.87  4234.8 1041.03  4249.7 1040.91
  4255.8 1038.13  4351.2 1025.21  4464.8 1002.98  4572.4  988.26  4745.6  976.14
  4937.6  965.75    4948  964.29  4958.4  957.24  4964.3  950.67  4969.5  950.93
  4976.2  946.59  4976.7  946.09  5002.7  946.59  5003.8  948.39  5059.7  959.59
  5076.1  960.95  5162.7  962.34  5265.1   966.2  5368.6  965.89  5435.5  960.05
  5600.3  963.42  5639.9  961.81  5746.7  970.17  6077.6  986.42  6123.2  987.73
#Mann= 8 ,-1 , 0
  4185.4     .12       0  4976.2     .05       0  5002.7     .12       0
  5059.7    .035       0  5076.1     .12       0  5162.7     .07       0
  5368.6    .035       0  6077.6     .07       0
Bank Sta=4976.2,5002.7
XS Rating Curve= 0 ,0
Exp/Cntr=0.3,0.1

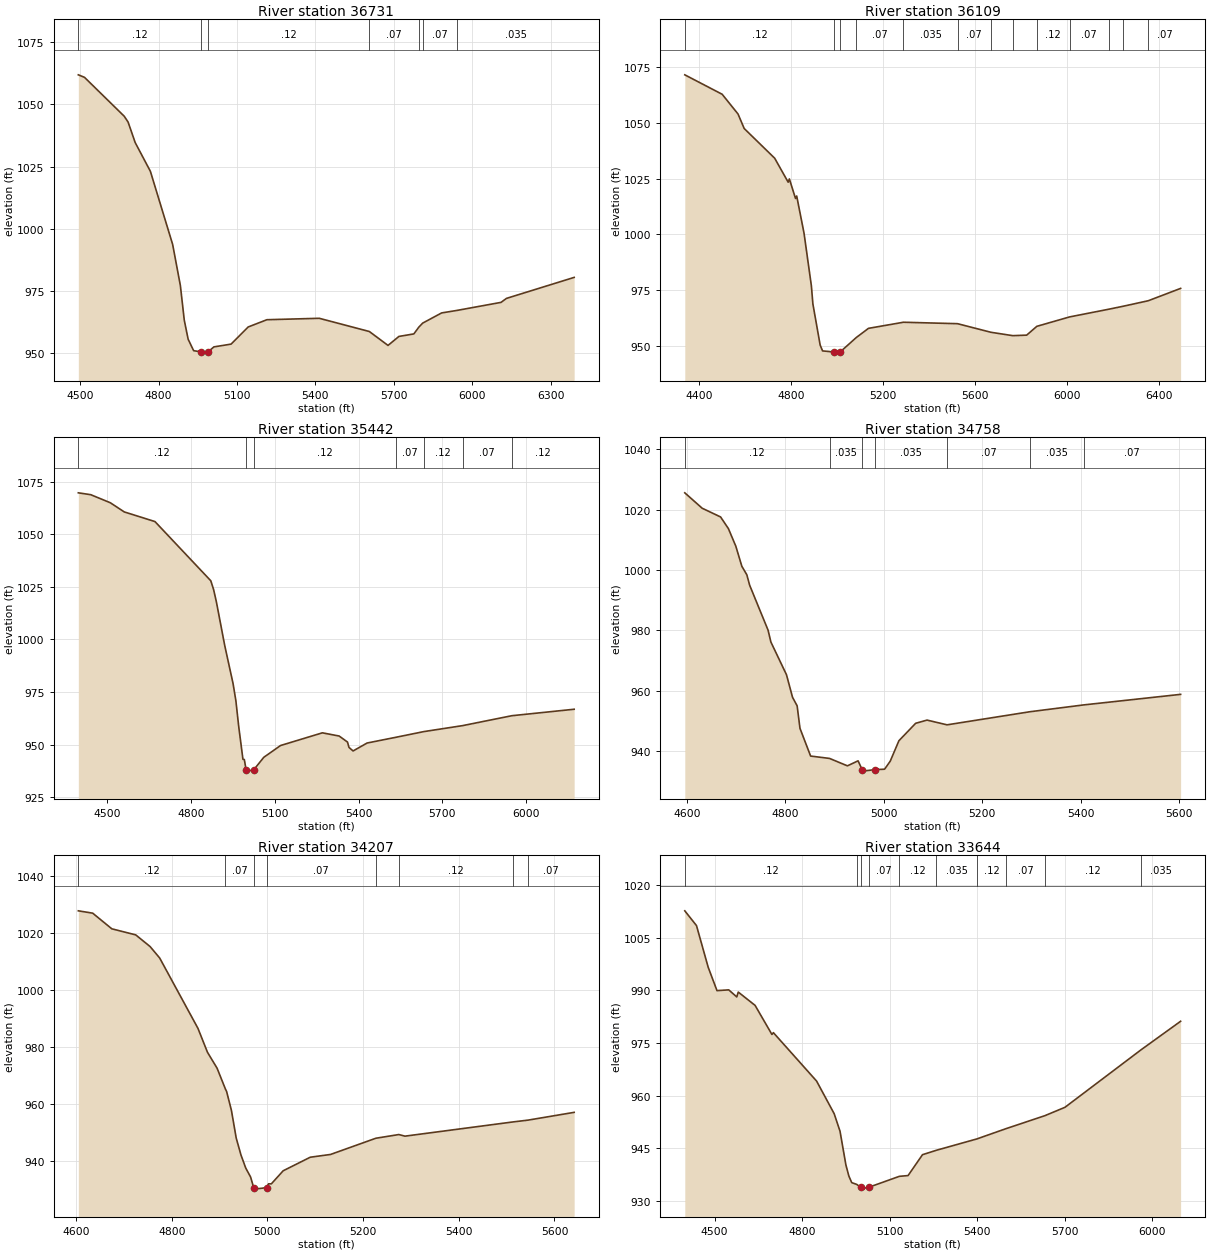
Type RM Length L Ch R = 1 ,36731   ,622,622,622
BEGIN DESCRIPTION:
H21659
END DESCRIPTION:
XS GIS Cut Line= 3
      2191561.58      13811391.9      2191051.57     13810654.02
      2190400.51     13809894.44
#Sta/Elev= 30
  4493.1 1061.88  4516.6 1060.88  4668.7 1045.24  4683.5 1042.91  4710.6 1034.67
  4768.9 1023.08    4854  993.72  4883.6  977.18  4898.5  963.29  4913.3  955.62
  4934.3  951.01  4962.9  950.52  4963.4  950.02  4989.4  950.52    5012  952.53
  5077.6  953.64  5143.1  960.53  5214.8  963.45  5415.1  964.02  5606.7  958.71
  5678.2  953.12  5719.9  956.73    5777  957.74  5796.1  960.46  5810.9  962.09
  5883.4  966.18  5942.3  967.19  6110.6  970.42  6131.5  972.02  6390.5  980.46
#Mann= 7 ,-1 , 0
  4493.1     .12       0  4962.9     .05       0  4989.4     .12       0
  5606.7     .07       0  5796.1     .12       0  5810.9     .07       0
  5942.3    .035       0
Bank Sta=4962.9,4989.4
XS Rating Curve= 0 ,0
Exp/Cntr=0.3,0.1

Type RM Length L Ch R = 1 ,36109   ,667,667,667
BEGIN DESCRIPTION:
H21658
END DESCRIPTION:
XS GIS Cut Line= 3
      2192375.32     13810860.17       2191442.2     13810556.36
      2190499.09     13809851.74
#Sta/Elev= 30
  4337.1 1071.65  4499.8 1062.91  4568.9 1054.04  4595.6 1047.54  4728.5 1034.17
  4787.1 1023.41  4792.4 1024.87  4819.1 1016.09  4824.3 1017.19  4856.2 1000.49
  4888.2  976.83  4894.8  968.66  4926.4  950.21  4936.9  947.59  4986.7  947.09
  4987.2  946.59  5013.3  947.09  5083.8  953.61  5136.7  957.72    5289  960.47
  5524.4  959.82  5669.8  955.96  5764.9  954.44  5825.4  954.67  5869.7  958.63
  6012.3  962.86  6183.8  966.34  6245.9  967.66  6355.1  970.14  6495.7  975.68
#Mann= 13 ,-1 , 0
  4337.1     .12       0  4986.7     .05       0  5013.3     .12       0
  5083.8     .07       0    5289    .035       0  5524.4     .07       0
  5669.8     .12       0  5764.9     .07       0  5869.7     .12       0
  6012.3     .07       0  6183.8     .12       0  6245.9    .035       0
  6355.1     .07       0
Bank Sta=4986.7,5013.3
XS Rating Curve= 0 ,0
Exp/Cntr=0.3,0.1

Type RM Length L Ch R = 1 ,35442   ,684,684,684
BEGIN DESCRIPTION:
H21657
END DESCRIPTION:
XS GIS Cut Line= 3
      2192429.61     13810035.53      2191192.63     13810002.98
      2190693.53     13809796.83
#Sta/Elev= 30
  4395.6 1069.65  4440.2 1068.76  4510.2 1064.94  4560.3 1060.58  4670.3    1056
  4870.4 1027.89  4880.4 1023.79  4890.4 1017.93  4920.4  997.13  4950.4  978.99
  4960.4  970.89  4970.4  958.82  4985.7   943.1  4990.7  942.98  4997.1  937.98
  4997.6  937.48  5023.7  937.98  5060.4  944.04  5120.5  949.64  5270.5  955.67
  5330.5  954.15  5360.5  951.29  5365.8  948.75  5380.5  947.06  5430.6  950.82
  5535.5  953.59    5634  956.25  5773.1  959.09  5949.8   963.8    6173  966.87
#Mann= 7 ,-1 , 0
  4395.6     .12       0  4997.1     .05       0  5023.7     .12       0
  5535.5     .07       0    5634     .12       0  5773.1     .07       0
  5949.8     .12       0
Bank Sta=4997.1,5023.7
XS Rating Curve= 0 ,0
Exp/Cntr=0.3,0.1

Type RM Length L Ch R = 1 ,34758   ,551,551,551
BEGIN DESCRIPTION:
West Fork 55.0
END DESCRIPTION:
XS GIS Cut Line= 3
      2191775.01     13809074.98        2191575.       13809425.
      2191024.99       13809675.
#Sta/Elev= 30
    4596 1025.55  4631.3 1020.45  4668.7 1017.56  4684.6  1013.7  4699.7 1007.86
  4711.9 1001.23    4722  998.42  4727.8  994.94  4765.2  980.06  4770.9  976.14
  4802.6  965.31  4814.9  957.83  4824.2  955.02    4830  947.57  4851.6  938.38
    4890   937.6  4926.4  935.14    4948   936.8  4956.3  933.89  4956.8  933.39
    4983  933.89  5001.9  934.03  5013.4   936.7    5031  943.46    5065  949.23
  5088.1  950.29  5128.8  948.72  5296.9  953.05  5406.6  955.32  5603.3  958.81
#Mann= 7 ,-1 , 0
    4596     .12       0    4890    .035       0  4956.3    .035       0
    4983    .035       0  5128.8     .07       0  5296.9    .035       0
  5406.6     .07       0
Bank Sta=4956.3,4983
XS Rating Curve= 0 ,0
Exp/Cntr=0.3,0.1

Type RM Length L Ch R = 1 ,34207   ,563,563,563
BEGIN DESCRIPTION:
West Fork 54.0
END DESCRIPTION:
XS GIS Cut Line= 3
      2191774.96       13808975.        2191375.       13808975.
      2190924.97     13809425.03
#Sta/Elev= 30
  4604.8 1027.76  4634.8 1026.94  4674.8 1021.44  4724.8 1019.31  4754.8 1015.21
  4774.8  1011.2  4854.8  986.49  4874.8  978.06  4894.8  972.49    4912  965.26
  4914.8  964.26  4924.8  957.66  4934.8  947.95  4944.8  941.98  4954.8  937.38
  4964.8  934.28  4971.4   930.5  4971.9     930  4998.2   930.5  5002.3  931.86
  5008.3  931.86    5033  936.45  5089.6  941.21    5132  942.18  5226.8  947.88
  5274.7  949.17  5287.6  948.61  5514.1  953.62  5544.9  954.24  5641.2  956.97
#Mann= 8 ,-1 , 0
  4604.8     .12       0    4912     .07       0  4971.4     .05       0
  4998.2     .07       0  5226.8    .035       0  5274.7     .12       0
  5514.1    .035       0  5544.9     .07       0
Bank Sta=4971.4,4998.2
XS Rating Curve= 0 ,0
Exp/Cntr=0.3,0.1

Type RM Length L Ch R = 1 ,33644   ,566,566,566
BEGIN DESCRIPTION:
West Fork 53.0
END DESCRIPTION:
XS GIS Cut Line= 3
      2191624.97       13808525.        2191025.       13808575.
      2190225.02     13809324.98
#Sta/Elev= 30
    4398 1012.68  4438.1 1008.47  4478.2  996.59  4508.3  989.94  4548.5  990.16
  4576.1  988.14  4581.1  989.53  4638.8  985.74  4696.5  977.45  4701.5  977.97
  4849.5  964.17  4909.7  954.88  4929.8  949.87  4949.9  940.28  4959.9  937.15
  4969.9  935.23  4987.1  934.72  5000.6  933.88  5001.1  933.38  5027.4  933.88
  5133.2  937.03  5162.9  937.24  5212.3  943.19  5259.9  944.45  5398.8  947.69
  5498.1   950.6  5631.6  954.31  5700.3  956.69  5960.6  973.05  6096.6  981.21
#Mann= 10 ,-1 , 0
    4398     .12       0  4987.1     .07       0  5000.6     .05       0
  5027.4     .07       0  5133.2     .12       0  5259.9    .035       0
  5398.8     .12       0  5498.1     .07       0  5631.6     .12       0
  5960.6    .035       0
Bank Sta=5000.6,5027.4
XS Rating Curve= 0 ,0
Exp/Cntr=0.3,0.1

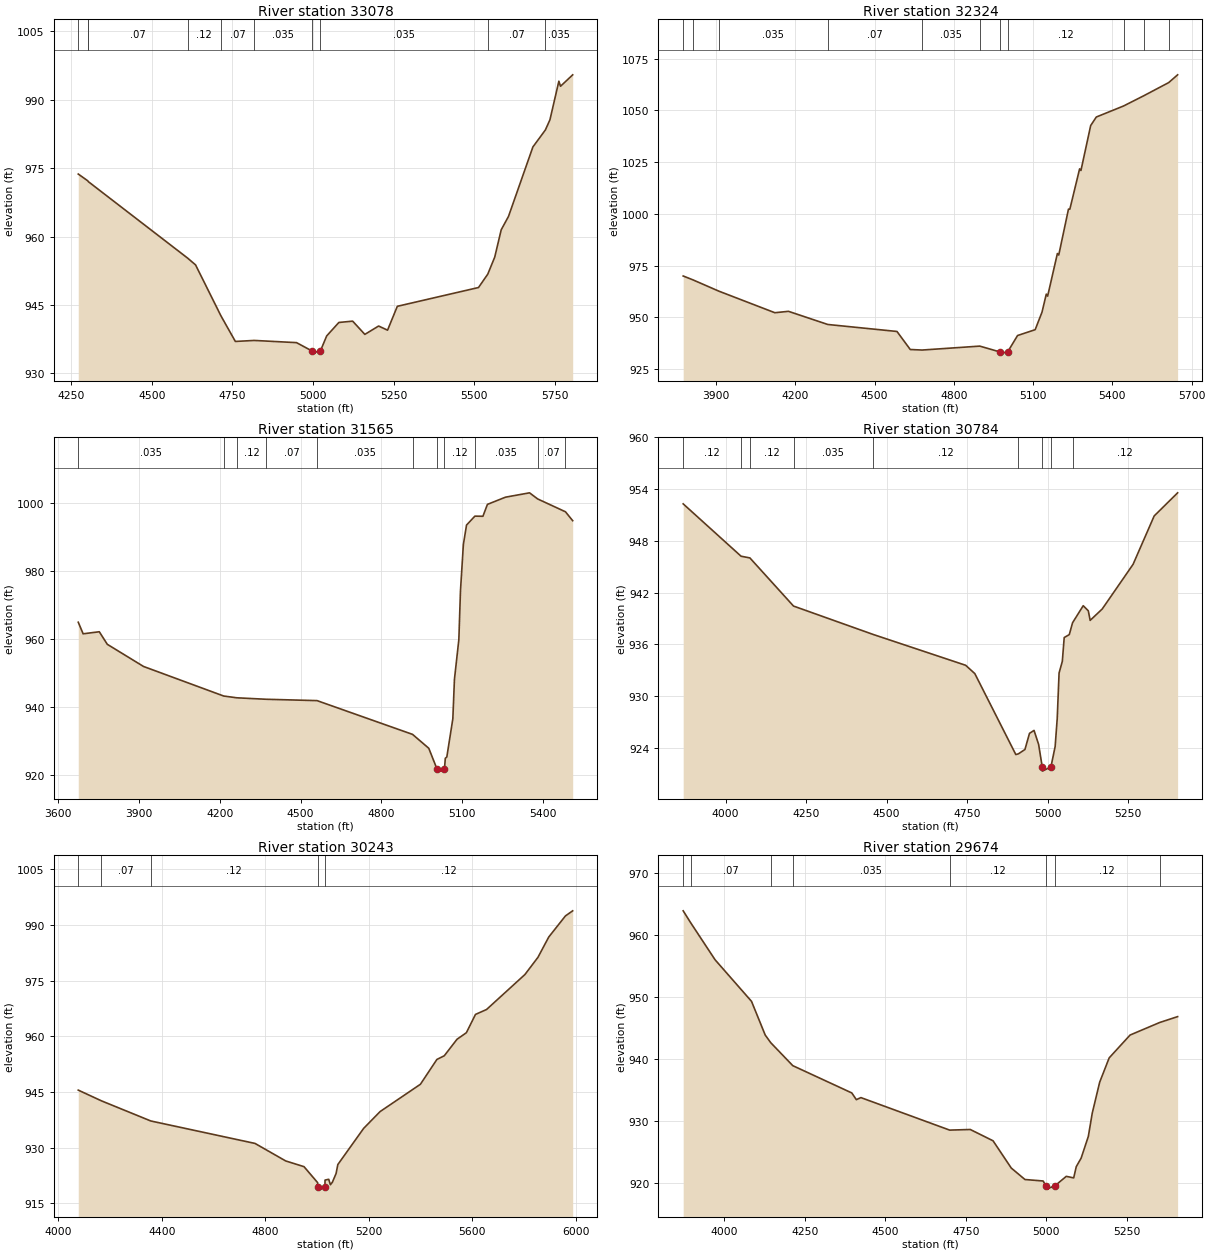
Type RM Length L Ch R = 1 ,33078   ,754,754,754
BEGIN DESCRIPTION:
West Fork 52.0
END DESCRIPTION:
XS GIS Cut Line= 3
      2191275.02     13808174.99        2190575.       13808375.
      2189774.96     13808475.01
#Sta/Elev= 30
  4271.7  973.71  4301.2  972.23  4302.9  972.05  4611.2  955.28  4635.7   953.8
  4714.5  942.63  4759.2  937.02  4817.9  937.24    4949  936.76  4996.4  934.96
  4996.9  934.46  5023.3  934.96  5042.6  938.23  5080.4  941.18  5123.2  941.47
    5161  938.57  5203.8   940.4  5231.5  939.49  5261.8  944.72  5513.7  948.84
  5542.5  951.77  5564.1  955.51  5584.2  961.49  5606.9  964.44  5682.5  979.65
  5721.2  983.37  5735.4   985.6  5763.1  994.06  5768.2  992.95    5806  995.46
#Mann= 10 ,-1 , 0
  4271.7     .07       0  4301.2     .12       0  4302.9     .07       0
  4611.2     .12       0  4714.5     .07       0  4817.9    .035       0
  4996.4    .035       0  5023.3    .035       0  5542.5     .07       0
  5721.2    .035       0
Bank Sta=4996.4,5023.3
XS Rating Curve= 0 ,0
Exp/Cntr=0.3,0.1

Type RM Length L Ch R = 1 ,32324   ,759,759,759
BEGIN DESCRIPTION:
H21656
END DESCRIPTION:
XS GIS Cut Line= 3
      2191290.33     13807919.65      2190216.07     13807811.14
      2189445.68      13807995.6
#Sta/Elev= 30
    3775  969.97  3810.8  968.16  3909.5  962.67  4122.1  952.21  4173.5  952.89
  4322.4  946.53  4584.4  943.15  4634.7  934.43  4679.4  934.17  4897.9  936.07
  4976.1  933.18  4976.6  932.68    5003  933.18  5040.9  941.19  5107.6  944.01
  5133.5  952.49  5149.7   961.2  5154.8  960.23  5191.7  980.82  5196.9  980.12
  5233.7 1002.29  5238.9 1002.26  5275.8 1021.74  5280.9 1020.98  5317.8 1042.71
  5339.1 1046.82  5442.3 1052.16  5518.7  1057.1  5613.1 1063.46  5646.9 1067.22
#Mann= 11 ,-1 , 0
    3775     .07       0  3810.8     .12       0  3909.5    .035       0
  4322.4     .07       0  4679.4    .035       0  4897.9     .12       0
  4976.1     .05       0    5003     .12       0  5442.3     .07       0
  5518.7     .12       0  5613.1     .07       0
Bank Sta=4976.1,5003
XS Rating Curve= 0 ,0
Exp/Cntr=0.3,0.1

Type RM Length L Ch R = 1 ,31565   ,781,781,781
BEGIN DESCRIPTION:
H21655
END DESCRIPTION:
XS GIS Cut Line= 2
      2191301.16     13807724.35      2189663.32       13806900.
#Sta/Elev= 30
  3675.6     965  3693.7   961.6  3753.6   962.2  3783.3  958.51  3917.6     952
    4215  943.31  4263.5  942.79  4372.1  942.36  4561.2  941.96  4915.3  932.04
  4975.5  927.96  5006.6  921.74  5007.1  921.24  5033.6  921.74  5036.8  925.02
  5042.4  925.38  5064.7  936.61  5070.7  948.22    5087  959.89  5093.1  974.31
  5103.8  987.85  5115.5  993.55  5146.5  996.18  5176.3  996.14    5193  999.63
    5260 1001.75  5349.2 1003.03  5379.3 1001.23  5482.4  997.46  5509.2  994.84
#Mann= 11 ,-1 , 0
  3675.6    .035       0    4215     .07       0  4263.5     .12       0
  4372.1     .07       0  4561.2    .035       0  4915.3     .12       0
  5006.6     .05       0  5033.6     .12       0  5146.5    .035       0
  5379.3     .07       0  5482.4    .035       0
Bank Sta=5006.6,5033.6
XS Rating Curve= 0 ,0
Exp/Cntr=0.3,0.1

Type RM Length L Ch R = 1 ,30784   ,541,541,541
BEGIN DESCRIPTION:
West Fork 49.0
END DESCRIPTION:
XS GIS Cut Line= 3
        2191325.       13807325.        2190525.       13806525.
      2190174.98     13806324.99
#Sta/Elev= 30
  3868.6  952.29  4048.2  946.22  4075.7  946.02    4211  940.44    4458  937.15
  4745.4  933.57  4773.7  932.61    4901  923.22  4909.2  923.31  4929.3  923.81
  4943.4  925.68  4957.5  926.02  4971.7   924.4  4982.9   921.8  4983.4   921.3
    5010   921.8    5023  924.15  5029.5  927.43  5035.2  932.68  5045.3  934.03
  5051.1  936.79  5066.9  937.13    5077   938.5  5110.1  940.48  5125.9  939.89
  5131.7  938.78  5169.1   940.1  5264.9  945.28  5330.4  950.89  5403.1  953.57
#Mann= 9 ,-1 , 0
  3868.6     .12       0  4048.2     .07       0  4075.7     .12       0
    4211    .035       0    4458     .12       0  4909.2    .035       0
  4982.9    .035       0    5010    .035       0    5077     .12       0
Bank Sta=4982.9,5010
XS Rating Curve= 0 ,0
Exp/Cntr=0.3,0.1

Type RM Length L Ch R = 1 ,30243   ,569,569,569
BEGIN DESCRIPTION:
West Fork 48.0
END DESCRIPTION:
XS GIS Cut Line= 3
      2191424.99     13807074.98        2190975.       13806275.
      2190225.02     13805625.02
#Sta/Elev= 30
  4077.6  945.54  4167.3  942.65  4357.9  937.23  4760.6  931.18  4879.1  926.46
  4949.9  924.92  5002.6   920.6  5003.2  919.37  5003.7  918.87  5030.4  919.37
  5031.1  921.31  5045.3  921.52  5051.9  920.06  5059.6  920.75  5073.8  923.09
  5080.4  925.48  5180.2  935.23  5243.8  939.76  5399.6  947.12  5463.2   953.8
  5491.7  954.79  5541.1  959.25  5577.2  961.01  5612.3  965.93  5655.1  967.26
  5803.2  976.67  5853.6   981.3  5895.3  986.77  5959.9  992.47  5987.9  993.84
#Mann= 5 ,-1 , 0
  4077.6     .12       0  4167.3     .07       0  4357.9     .12       0
  5003.2     .05       0  5030.4     .12       0
Bank Sta=5003.2,5030.4
XS Rating Curve= 0 ,0
Exp/Cntr=0.3,0.1

Type RM Length L Ch R = 1 ,29674   ,564,564,564
BEGIN DESCRIPTION:
West Fork 47.0
END DESCRIPTION:
XS GIS Cut Line= 3
      2192225.01     13806825.01        2191425.       13806025.
        2191225.       13805675.
#Sta/Elev= 30
    3873  963.94  3896.1  962.03    3972  956.05  4085.1  949.35  4127.6  943.92
  4144.9  942.68  4213.1  938.99  4396.3  934.59  4410.4  933.51  4424.6  933.84
  4700.1   928.6    4764   928.7  4834.7  926.88  4891.2  922.49  4933.7  920.64
  4990.2   920.4  4998.7  919.59  4999.2  919.09  5025.9  919.59    5062  921.15
    5085   920.9  5092.9  922.71    5108  924.08  5130.4  927.58  5142.6  931.35
  5165.6  936.32  5195.1  940.24  5259.9  943.92  5351.7  945.94  5407.5  946.89
#Mann= 8 ,-1 , 0
    3873    .035       0  3896.1     .07       0  4144.9     .12       0
  4213.1    .035       0  4700.1     .12       0  4998.7     .05       0
  5025.9     .12       0  5351.7     .07       0
Bank Sta=4998.7,5025.9
XS Rating Curve= 0 ,0
Exp/Cntr=0.3,0.1