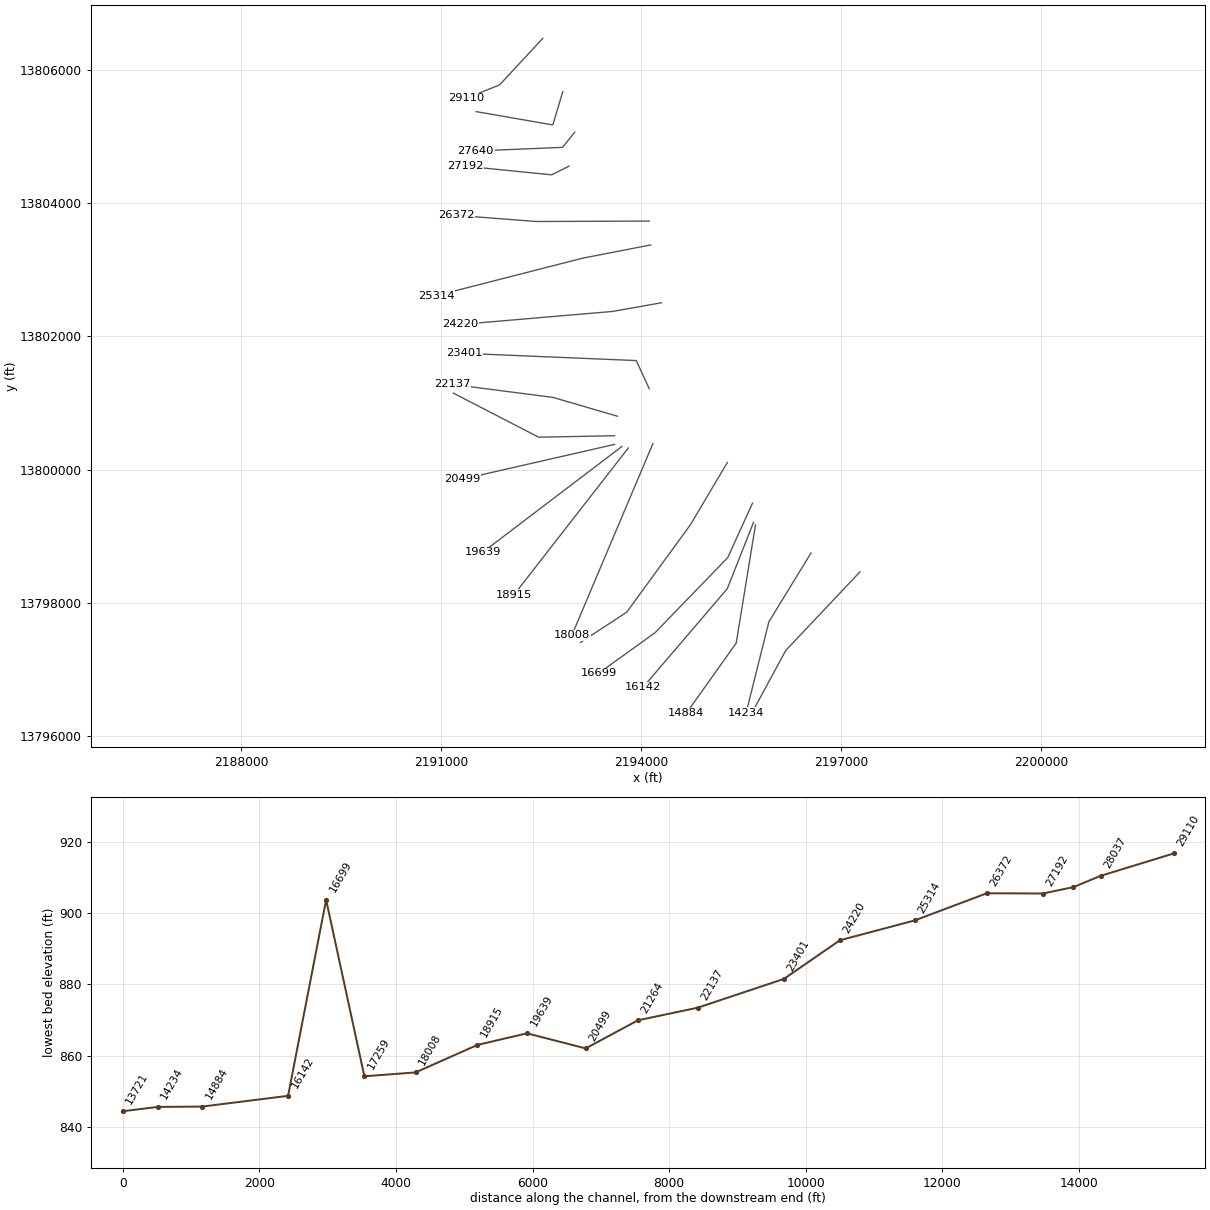
HEC-RAS study West Fork Dry Comal Creek.prj: West Fork Dry Comal Creek

--- West Fork Dry Comal Creek.g01 (geometry) --- (continued)

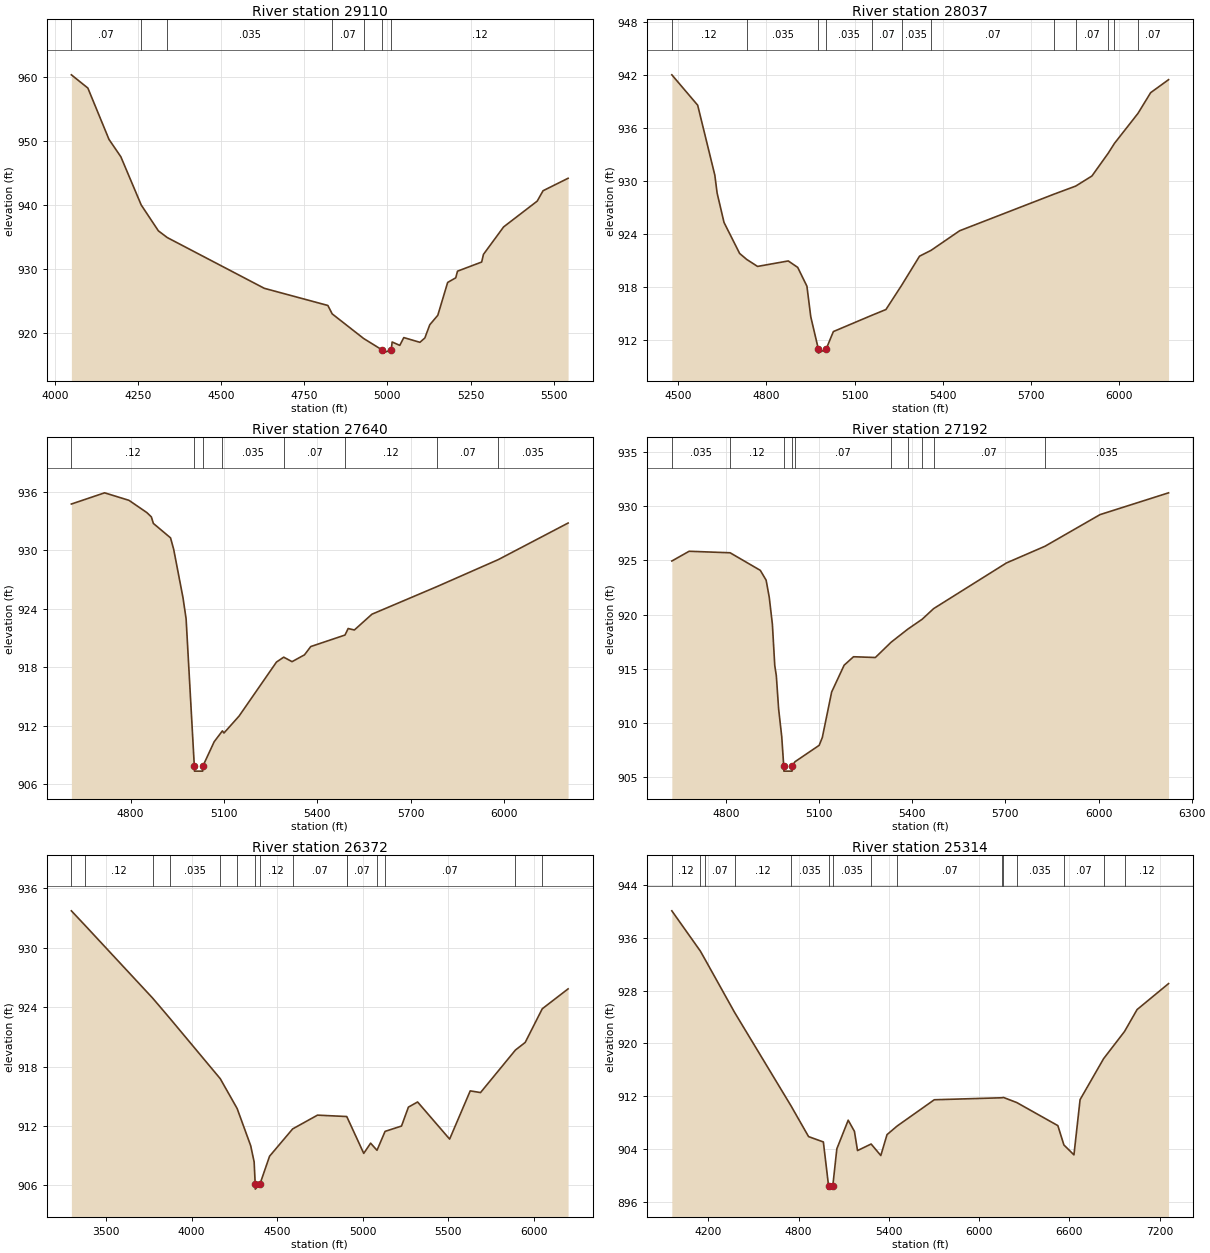
Type RM Length L Ch R = 1 ,29110   ,1073,1073,1073
BEGIN DESCRIPTION:
West Fork 46.0
END DESCRIPTION:
XS GIS Cut Line= 3
      2192525.01     13806475.01        2191875.       13805775.
      2191374.98     13805574.99
#Sta/Elev= 30
  4049.7  960.33  4099.3  958.26  4162.8  950.24  4198.5  947.52  4259.7  939.99
  4311.4  935.94  4338.2  934.89  4629.9  926.96    4821  924.28  4834.1  922.96
  4928.8  919.11  4984.2  917.33  4984.7  916.83  5011.5  917.33  5014.4  918.57
  5037.3  918.04  5049.4  919.26  5097.9  918.52  5112.7   919.2  5127.5  921.26
  5151.7  922.75  5181.3  927.88  5205.6   928.6  5210.9  929.64  5283.6  931.07
    5289  932.27  5349.6  936.56  5450.6  940.59  5468.1  942.21  5543.5  944.16
#Mann= 7 ,-1 , 0
  4049.7     .07       0  4259.7     .12       0  4338.2    .035       0
  4834.1     .07       0  4928.8     .12       0  4984.2     .05       0
  5011.5     .12       0
Bank Sta=4984.2,5011.5
XS Rating Curve= 0 ,0
Exp/Cntr=0.3,0.1

Type RM Length L Ch R = 1 ,28037   ,397,397,397
BEGIN DESCRIPTION:
West Fork 45.0
END DESCRIPTION:
XS GIS Cut Line= 3
      2192825.01     13805675.04        2192675.       13805175.
      2191525.02       13805375.
#Sta/Elev= 30
  4478.2  942.04  4566.1   938.6  4624.4  930.68  4632.2  928.65  4655.7  925.32
  4708.8  921.81  4732.9  921.13  4769.7  920.34  4874.1  920.96  4906.3  920.23
  4937.6   918.1  4950.7  914.64  4976.2  911.02  4976.7  910.52  5003.5  911.02
  5027.5  912.96  5158.8  914.81  5206.4  915.46  5259.3  918.18  5320.6   921.5
  5359.8  922.16    5457  924.38  5778.3  928.53  5851.8  929.44  5906.8  930.58
    5962  933.15  5983.6  934.28  6063.4  937.67  6106.6  940.02  6167.5  941.49
#Mann= 12 ,-1 , 0
  4478.2     .12       0  4732.9    .035       0  4976.2    .035       0
  5003.5    .035       0  5158.8     .07       0  5259.3    .035       0
  5359.8     .07       0  5778.3    .035       0  5851.8     .07       0
    5962    .035       0  5983.6     .12       0  6063.4     .07       0
Bank Sta=4976.2,5003.5
XS Rating Curve= 0 ,0
Exp/Cntr=0.3,0.1

Type RM Length L Ch R = 1 ,27640   ,448,448,448
BEGIN DESCRIPTION:
H21654
END DESCRIPTION:
XS GIS Cut Line= 3
      2193004.72     13805065.94      2192820.23     13804838.05
      2191519.07     13804783.83
#Sta/Elev= 30
  4609.8  934.76  4716.5  935.91  4794.8  935.14  4852.4  933.88  4866.7  933.44
  4873.2  932.77  4928.3  931.29  4938.3  930.13  4968.3  925.16  4978.3  922.99
  5004.7  907.86  5005.2  907.36  5031.5  907.36    5032  907.86  5068.4  910.37
  5094.9  911.49  5099.9  911.27  5148.5  913.01  5268.6  918.55  5291.8  919.05
  5318.6  918.59  5358.6  919.29  5378.7  920.14  5488.7  921.32  5498.8  921.99
  5518.8  921.84  5575.3  923.46  5784.1  926.29  5981.1  929.06  6205.3  932.81
#Mann= 8 ,-1 , 0
  4609.8     .12       0  5004.7     .05       0    5032     .12       0
  5094.9    .035       0  5291.8     .07       0  5488.7     .12       0
  5784.1     .07       0  5981.1    .035       0
Bank Sta=5004.7,5032
XS Rating Curve= 0 ,0
Exp/Cntr=0.3,0.1

Type RM Length L Ch R = 1 ,27192   ,820,820,820
BEGIN DESCRIPTION:
West Fork 44.0
END DESCRIPTION:
XS GIS Cut Line= 3
      2192917.87     13804555.92      2192657.47     13804425.72
       2191355.4     13804555.93
#Sta/Elev= 30
  4625.9  924.94  4681.6  925.84  4813.6   925.7  4910.8  924.08  4929.6  923.17
  4939.6   921.6  4949.7  919.12  4957.4   915.3  4962.4  914.36  4969.8   911.3
  4979.8  908.75  4986.2  906.06  4986.7  905.56  5013.1  905.56  5013.6  906.06
  5022.7  906.43  5100.4  907.94  5110.5  908.66  5140.6  912.86  5180.8  915.33
    5211  916.11  5281.3  916.04  5332.1  917.45    5386  918.66  5432.1  919.57
    5469  920.55  5703.4  924.76  5827.5   926.3  6004.9  929.22  6225.6  931.23
#Mann= 10 ,-1 , 0
  4625.9    .035       0  4813.6     .12       0  4986.2     .05       0
  5013.6     .12       0  5022.7     .07       0  5332.1     .12       0
    5386     .07       0  5432.1     .12       0    5469     .07       0
  5827.5    .035       0
Bank Sta=4986.2,5013.6
XS Rating Curve= 0 ,0
Exp/Cntr=0.3,0.1

Type RM Length L Ch R = 1 ,26372   ,1058,1058,1058
BEGIN DESCRIPTION:
West Fork 43.0
END DESCRIPTION:
XS GIS Cut Line= 3
      2194122.33     13803731.28        2192425.       13803725.
      2191225.15     13803818.09
#Sta/Elev= 30
  3298.1  933.73  3379.7  932.23  3773.6   924.9  3872.1   922.9  4167.6  916.78
  4266.1  913.77  4345.4  910.01  4365.4  908.38  4371.7  906.13  4372.2  905.63
  4399.1  906.13  4455.4  908.95  4590.3  911.71  4735.4   913.1    4906  912.96
  4906.6  912.95  5005.5  909.24  5045.6  910.27  5082.9  909.55    5130  911.46
  5226.1     912  5266.3  913.91    5320  914.43    5507  910.68  5627.3  915.55
  5687.5  915.38  5891.1  919.67  5948.3  920.44    6048  923.84  6198.9  925.85
#Mann= 15 ,-1 , 0
  3298.1    .035       0  3379.7     .12       0  3773.6     .07       0
  3872.1    .035       0  4167.6     .07       0  4266.1     .12       0
  4371.7     .05       0  4399.1     .12       0  4590.3     .07       0
    4906    .035       0  4906.6     .07       0  5082.9     .12       0
    5130     .07       0  5891.1    .035       0    6048     .07       0
Bank Sta=4371.7,4399.1
XS Rating Curve= 0 ,0
Exp/Cntr=0.3,0.1

Type RM Length L Ch R = 1 ,25314   ,1094,1094,1094
BEGIN DESCRIPTION:
West Fork 42.0
END DESCRIPTION:
XS GIS Cut Line= 3
      2194143.98      13803373.2        2193125.       13803175.
      2190932.18     13802613.65
#Sta/Elev= 30
  3957.7  940.05  4147.1  933.97  4175.7  932.82  4374.7   924.7  4749.6  910.58
  4866.6  905.92  4964.9  905.11  4999.4  898.48  4999.9  897.98  5027.7  898.48
  5054.4  904.07    5130   908.4  5171.3  906.72  5191.9  903.81  5282.4   904.8
  5346.7  903.06    5388  906.22  5454.7  907.51  5702.1  911.49  6151.2  911.79
  6161.8  911.84  6250.1  911.07  6523.5  907.58  6563.6  904.66  6630.4  903.16
  6671.2  911.51  6827.5   917.7  6966.6  921.81  7049.9  925.12  7259.3  929.05
#Mann= 15 ,-1 , 0
  3957.7     .12       0  4147.1    .035       0  4175.7     .07       0
  4374.7     .12       0  4749.6    .035       0  4999.4    .035       0
  5027.7    .035       0  5282.4    .035       0  5454.7     .07       0
  6151.2    .035       0  6161.8     .07       0  6250.1    .035       0
  6563.6     .07       0  6827.5    .035       0  6966.6     .12       0
Bank Sta=4999.4,5027.7
XS Rating Curve= 0 ,0
Exp/Cntr=0.3,0.1

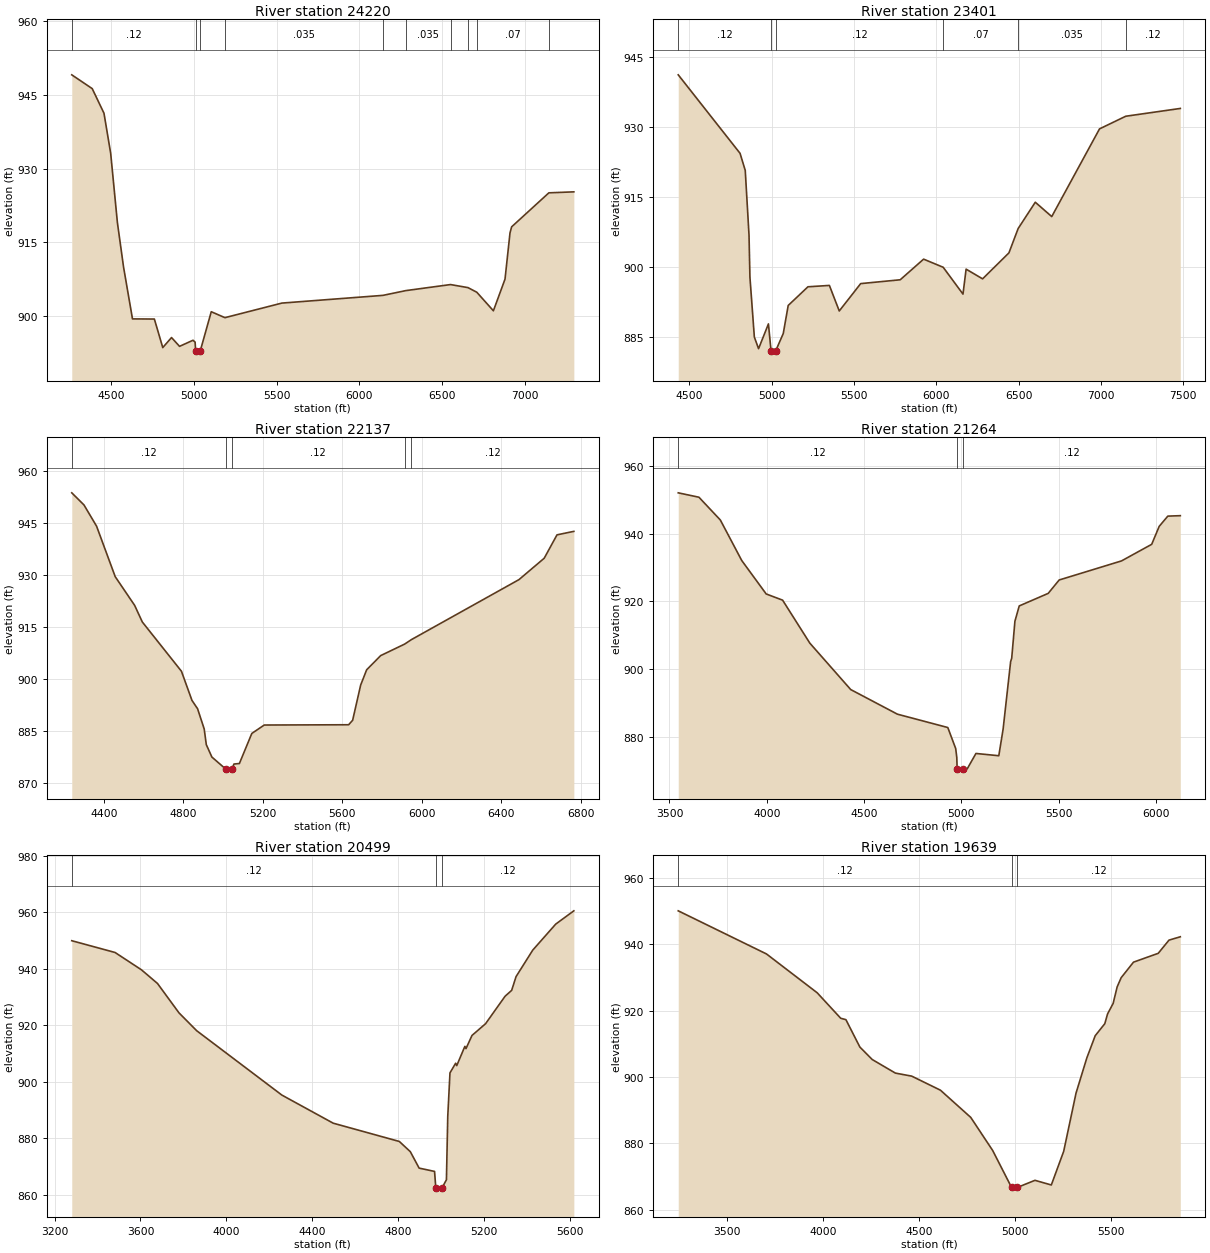
Type RM Length L Ch R = 1 ,24220   ,819,819,819
BEGIN DESCRIPTION:
West Fork 41.0
END DESCRIPTION:
XS GIS Cut Line= 3
      2194306.77     13802505.15        2193575.       13802375.
      2191290.29     13802179.63
#Sta/Elev= 30
  4261.5  949.08  4385.2  946.27  4456.3  941.26  4496.9  933.08  4537.5  918.98
  4574.8  909.91  4628.7  899.38    4761  899.35  4811.8  893.54  4864.8  895.58
  4913.3  893.79  4994.6  895.03  5007.3  894.66  5010.6  892.91  5011.1  892.41
    5039  892.91  5105.1  900.84  5187.8  899.63  5532.3   902.6  6143.1  904.17
  6281.7  905.14    6552  906.37  6657.5  905.75  6710.9  904.81  6811.3  901.03
  6881.6  907.48  6911.7  916.88  6921.7  918.13  7146.7  925.05  7297.8  925.25
#Mann= 10 ,-1 , 0
  4261.5     .12       0  5010.6     .05       0    5039     .12       0
  5187.8    .035       0  6143.1     .07       0  6281.7    .035       0
    6552     .07       0  6657.5    .035       0  6710.9     .07       0
  7146.7     .12       0
Bank Sta=5010.6,5039
XS Rating Curve= 0 ,0
Exp/Cntr=0.3,0.1

Type RM Length L Ch R = 1 ,23401   ,1264,1264,1264
BEGIN DESCRIPTION:
West Fork 40.0
END DESCRIPTION:
XS GIS Cut Line= 3
      2194122.31     13801213.94      2193927.01     13801637.09
      2191344.54      13801745.6
#Sta/Elev= 30
  4432.3  941.16  4807.9  924.35  4839.5  920.69  4862.4  906.84  4867.9  897.86
  4894.8     885  4920.4   882.5  4980.4  887.81  4996.2  882.05  4996.7  881.55
  5024.7  882.05  5070.5  885.75  5100.5  891.76  5220.6  895.76  5350.8  896.05
  5410.8  890.58  5540.9  896.44  5781.1  897.26  5923.3  901.68  6042.3  899.94
  6162.6  894.19  6181.5  899.54  6281.6  897.46  6441.7  903.02  6497.8  908.24
  6601.9  913.87  6701.9   910.8  6992.2  929.58  7151.6  932.29  7483.1  933.96
#Mann= 6 ,-1 , 0
  4432.3     .12       0  4996.2     .05       0  5024.7     .12       0
  6042.3     .07       0  6497.8    .035       0  7151.6     .12       0
Bank Sta=4996.2,5024.7
XS Rating Curve= 0 ,0
Exp/Cntr=0.3,0.1

Type RM Length L Ch R = 1 ,22137   ,873,873,873
BEGIN DESCRIPTION:
H21653
END DESCRIPTION:
XS GIS Cut Line= 3
      2193644.88     13800801.59      2192679.18     13801083.71
      2191170.94     13801279.02
#Sta/Elev= 30
  4238.9  953.69  4300.3   950.2  4363.8  944.07  4457.6  929.51  4555.4  921.24
    4594  916.45  4790.9  902.25  4843.8  893.85  4872.1  891.44  4905.5  885.59
    4916  881.09  4944.2   877.5  5015.8  873.95  5016.3  873.45  5045.2  873.95
    5055  875.49  5082.6  875.65  5145.1  884.32  5207.6  886.74  5632.4  886.82
  5652.5  888.11  5692.9  898.27  5723.1  902.67  5793.7  906.76  5914.4  910.08
  5948.4  911.37  6489.5  928.66  6616.6  934.83    6681  941.57  6765.8  942.58
#Mann= 5 ,-1 , 0
  4238.9     .12       0  5015.8     .05       0  5045.2     .12       0
  5914.4    .035       0  5948.4     .12       0
Bank Sta=5015.8,5045.2
XS Rating Curve= 0 ,0
Exp/Cntr=0.3,0.1

Type RM Length L Ch R = 1 ,21264   ,765,765,765
BEGIN DESCRIPTION:
H21652
END DESCRIPTION:
XS GIS Cut Line= 3
      2193601.44     13800508.62      2192462.16     13800486.92
      2191181.81      13801148.8
#Sta/Elev= 30
  3545.1  952.01  3651.6  950.71  3761.6  943.99  3871.6  932.04  3997.2  922.18
  4081.6  920.35  4221.7  907.66  4431.7  893.98  4671.7  886.72  4930.8  882.78
  4971.4  876.57    4977  873.94  4978.8  870.42  4979.3  869.92  5008.3  870.42
  5030.4  870.58  5075.4  875.13  5192.9  874.46    5215  882.29  5253.7   902.2
  5259.3  903.25  5275.8  914.15    5298  918.65  5446.9  922.35  5503.2   926.3
  5823.8  931.93  5978.8  936.82  6017.5  942.13  6061.8  945.14  6125.9  945.27
#Mann= 3 ,-1 , 0
  3545.1     .12       0  4978.8     .05       0  5008.3     .12       0
Bank Sta=4978.8,5008.3
XS Rating Curve= 0 ,0
Exp/Cntr=0.3,0.1

Type RM Length L Ch R = 1 ,20499   ,860,860,860
BEGIN DESCRIPTION:
H21651
END DESCRIPTION:
XS GIS Cut Line= 2
      2193601.53     13800378.42       2191322.8     13799857.57
#Sta/Elev= 30
  3280.2  949.98  3481.8  945.81  3604.9  939.66  3679.4  934.83  3779.3  924.44
  3861.5  918.13  4258.4  895.32  4497.3  885.37  4805.1   878.9  4856.4  875.28
  4897.4  869.46  4969.2  868.29    4975  862.52  4975.5  862.02  5004.5  862.52
  5024.5  865.34  5030.7  887.77    5041  903.18  5067.4   906.6  5072.6  905.76
  5110.4  912.57  5115.5  911.77  5143.6  916.44  5206.6  920.58  5297.6  930.32
  5328.2   932.4  5348.7  937.27  5426.5  946.66  5533.4  955.86  5617.7  960.56
#Mann= 3 ,-1 , 0
  3280.2     .12       0    4975     .05       0  5004.5     .12       0
Bank Sta=4975,5004.5
XS Rating Curve= 0 ,0
Exp/Cntr=0.3,0.1

Type RM Length L Ch R = 1 ,19639   ,724,724,724
BEGIN DESCRIPTION:
H21650
END DESCRIPTION:
XS GIS Cut Line= 2
        2193710.     13800345.87      2191626.63     13798761.64
#Sta/Elev= 30
  3246.3  950.03  3706.6  937.04  3970.7  925.36  4093.3  917.69  4120.4  917.27
  4193.1  909.03  4257.6  905.27  4378.2  901.19  4463.5  900.27  4613.2  896.04
  4771.2  887.85  4885.5  877.89    4984  866.76  4984.5  866.26  5013.7  866.76
    5106  868.91  5191.2  867.51  5255.7  877.64  5320.1  895.18  5376.3  905.75
    5420  912.44  5469.9  916.05  5484.4     919  5513.5  922.16  5534.3  927.12
  5555.1  929.89  5619.6  934.58  5748.5  937.24  5804.7  941.21  5863.6  942.22
#Mann= 3 ,-1 , 0
  3246.3     .12       0    4984     .05       0  5013.7     .12       0
Bank Sta=4984,5013.7
XS Rating Curve= 0 ,0
Exp/Cntr=0.3,0.1

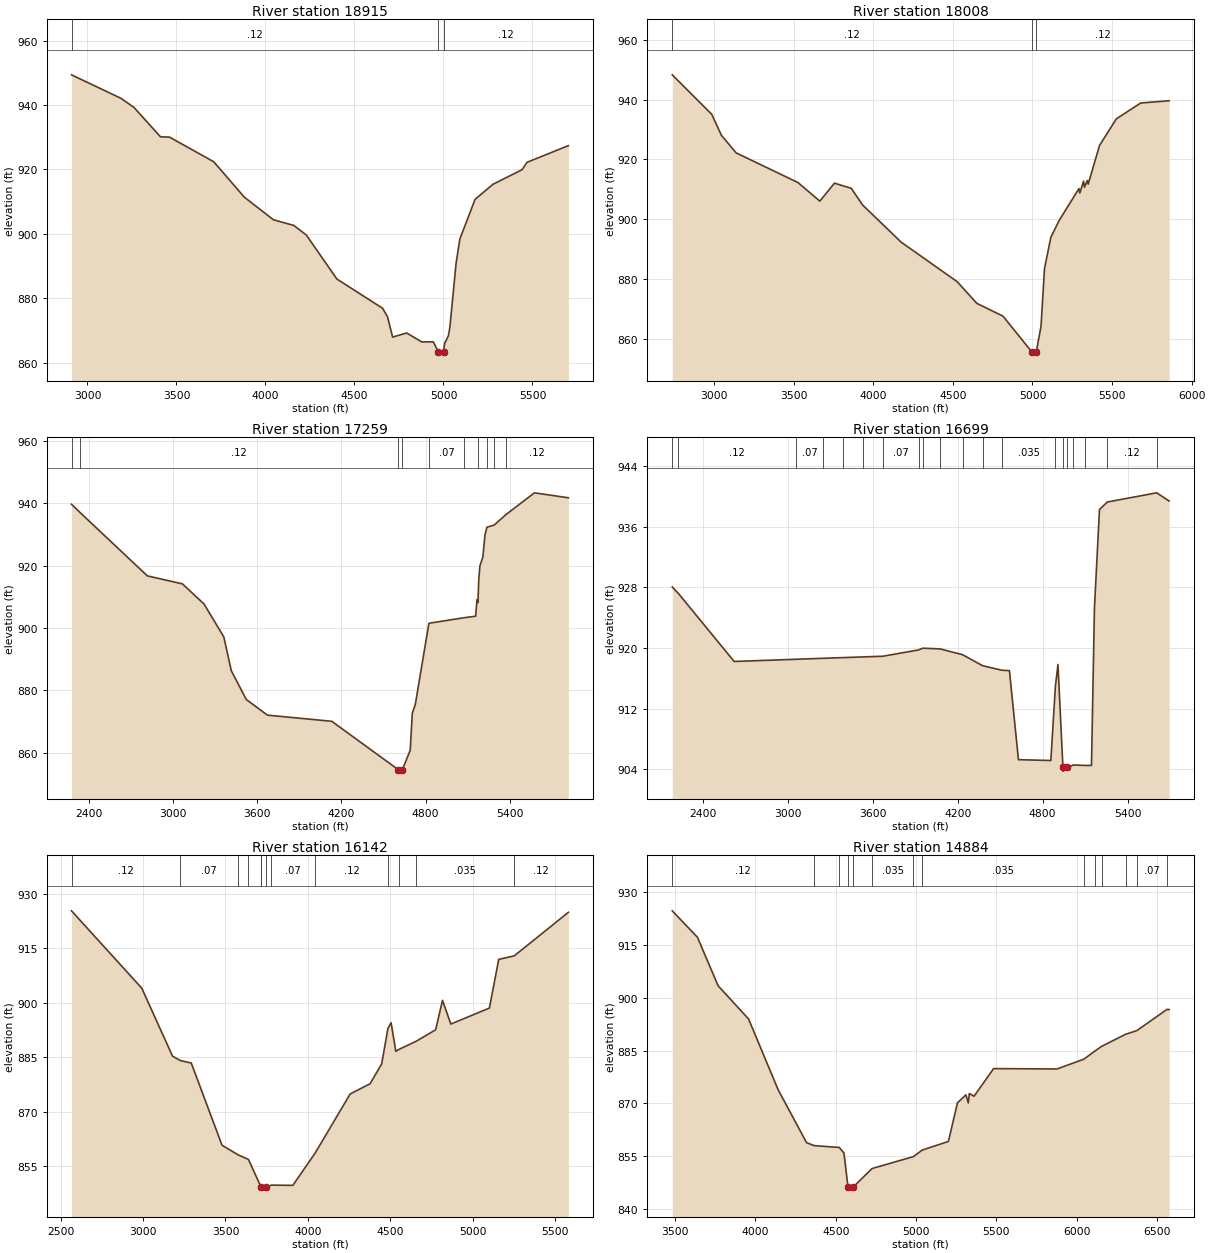
Type RM Length L Ch R = 1 ,18915   ,907,907,907
BEGIN DESCRIPTION:
H21649
END DESCRIPTION:
XS GIS Cut Line= 2
      2193807.66     13800324.17      2192093.21     13798121.44
#Sta/Elev= 30
  2910.6  949.38  3189.1  942.07  3261.5  939.26  3410.8  930.13  3460.6  930.06
  3709.4  922.41  3881.3  911.42  4045.1  904.39  4159.1  902.64  4229.7  899.67
  4401.6  885.99  4658.3  876.92  4685.7  874.29  4714.6  867.98  4793.4  869.25
  4878.4  866.48  4942.7  866.51  4971.2   863.5  4971.7     863  5000.9   863.5
  5006.9  866.06  5027.7  868.35  5035.9   870.9  5071.1  890.89    5092  898.38
  5177.8  910.73  5278.3  915.41  5442.1  919.94  5469.3  922.22  5701.9   927.4
#Mann= 3 ,-1 , 0
  2910.6     .12       0  4971.2     .05       0  5000.9     .12       0
Bank Sta=4971.2,5000.9
XS Rating Curve= 0 ,0
Exp/Cntr=0.3,0.1

Type RM Length L Ch R = 1 ,18008   ,749,749,749
BEGIN DESCRIPTION:
H21648
END DESCRIPTION:
XS GIS Cut Line= 2
      2194176.56     13800389.23      2192961.28      13797513.8
#Sta/Elev= 30
  2736.7   948.3  2985.1  935.08  3045.3  928.11  3138.2   922.2  3526.3   912.3
  3664.1  906.08  3755.9  912.09  3861.5  910.35  3932.6   904.8  4174.3  892.39
  4526.6  879.16  4650.5   871.9  4814.9  867.62  4994.5  855.77    4995  855.27
  5024.3  855.77  5053.7  864.35  5075.4  883.52  5115.1  893.95  5167.9  899.65
  5291.9  910.27  5297.3  908.78    5321  912.76  5326.4  910.72  5344.7  912.99
  5350.1  911.76  5421.2   924.7  5526.9  933.59  5679.9  938.88  5858.4  939.63
#Mann= 3 ,-1 , 0
  2736.7     .12       0  4994.5     .05       0  5024.3     .12       0
Bank Sta=4994.5,5024.3
XS Rating Curve= 0 ,0
Exp/Cntr=0.3,0.1

Type RM Length L Ch R = 1 ,17259   ,560,560,560
BEGIN DESCRIPTION:
H21647
END DESCRIPTION:
XS GIS Cut Line= 4
      2195294.19     13800107.14      2194740.81     13799173.99
      2193785.95     13797861.05      2193091.47      13797405.3
#Sta/Elev= 30
  2278.6  939.62  2338.3  937.02  2818.9  916.68  3068.4  914.13  3222.4  907.69
  3363.5  897.13  3416.9   886.3  3523.5  877.11  3674.2   872.1  4132.5  870.13
    4605  854.68  4605.5  854.18  4635.3  854.68  4691.2  860.87  4705.9  872.71
  4726.8  875.39  4824.3  901.52  5072.9  903.27  5157.2  903.78  5166.3  909.05
  5173.3  908.13  5179.4  915.45  5187.4  919.86  5208.5  922.73  5223.6  929.84
  5237.7  932.28  5288.9  932.94  5372.6   936.3  5576.1  943.27  5817.6  941.68
#Mann= 10 ,-1 , 0
  2278.6    .063       0  2338.3     .12       0    4605     .05       0
  4635.3     .12       0  4824.3     .07       0  5072.9    .035       0
  5173.3     .07       0  5237.7    .035       0  5288.9     .07       0
  5372.6     .12       0
Bank Sta=4605,4635.3
XS Rating Curve= 0 ,0
Exp/Cntr=0.3,0.1

Type RM Length L Ch R = 1 ,16699   ,557,557,557
BEGIN DESCRIPTION:
H21646
END DESCRIPTION:
XS GIS Cut Line= 4
      2195671.73      13799496.6      2195300.39     13798679.65
       2194208.6     13797550.73      2193361.88     13796941.68
#Sta/Elev= 30
  2183.1  928.05    2227  927.19  2620.5  918.23  3057.4  918.52  3250.8  918.65
    3389  918.74    3530  918.83    3671  918.92  3923.3  919.75  3953.1  919.98
  4075.2  919.89  4235.1  919.12  4376.2  917.67  4511.2  917.08  4565.6  917.02
  4629.4  905.28  4858.2  905.17  4890.4  914.94  4908.5  917.83  4943.7  904.27
  4944.2  903.77  4974.1  904.27  5016.8  904.58  5101.6  904.52  5145.4  904.52
  5166.3  925.26  5201.9  938.26  5257.1  939.26  5606.4  940.47    5694  939.39
#Mann= 20 ,-1 , 0
  2183.1    .035       0    2227     .12       0  3057.4     .07       0
  3250.8    .035       0    3389    .035       0    3530     .07       0
    3671     .07       0  3923.3    .035       0  3953.1     .07       0
  4075.2    .035       0  4235.1    .035       0  4376.2    .035       0
  4511.2    .035       0  4890.4     .07       0  4943.7     .05       0
  4974.1     .07       0  5016.8    .035       0  5101.6     .07       0
  5257.1     .12       0  5606.4     .07       0
Bank Sta=4943.7,4974.1
XS Rating Curve= 0 ,0
Exp/Cntr=0.3,0.1

Type RM Length L Ch R = 1 ,16142   ,1258,1258,1258
BEGIN DESCRIPTION:
H21645
END DESCRIPTION:
XS GIS Cut Line= 3
      2195686.59     13799206.96      2195292.96     13798211.74
      2194030.36     13796733.75
#Sta/Elev= 30
  2566.2  925.24  2992.5  903.96  3179.1  885.27  3226.6  884.06  3292.6  883.38
  3479.2  860.77    3576  858.14  3639.5  856.85    3713  849.57  3716.9  849.19
  3717.4  848.69  3747.3  849.19    3777  849.79  3908.8  849.73  4043.5  858.56
  4256.8  874.88  4377.6  877.68  4447.9  883.15  4485.4  892.85    4505  894.47
  4533.5  886.59  4552.2  887.11  4656.8  889.36    4775  892.51  4816.7  900.61
  4867.3   894.1  5101.1  898.49  5157.8  911.89    5252  912.86  5580.3  924.83
#Mann= 13 ,-1 , 0
  2566.2     .12       0  3226.6     .07       0    3576    .035       0
  3639.5     .07       0    3713    .035       0  3716.9    .035       0
  3747.3    .035       0    3777     .07       0  4043.5     .12       0
  4485.4    .035       0  4552.2     .07       0  4656.8    .035       0
    5252     .12       0
Bank Sta=3716.9,3747.3
XS Rating Curve= 0 ,0
Exp/Cntr=0.3,0.1

Type RM Length L Ch R = 1 ,14884   ,650,650,650
BEGIN DESCRIPTION:
H21644
END DESCRIPTION:
XS GIS Cut Line= 3
      2195716.32     13799169.89      2195426.65     13797394.76
      2194676.53     13796340.13
#Sta/Elev= 30
  3482.2  924.69  3639.1  917.18  3767.8   903.4  3957.2  893.99  4141.5  873.87
    4318  858.89  4364.2  858.03  4521.7  857.51    4551  855.92  4576.4  846.17
  4576.9  845.67  4606.8  846.17    4726  851.52  4983.5   854.9    5038  856.76
  5201.2  859.21  5257.6  870.19  5310.4  872.43  5325.1  870.15  5331.3  872.82
  5360.8  872.05  5482.5  879.89  5877.3  879.79  6044.6  882.57  6116.7     885
  6156.3  886.25  6304.8  889.65    6374  890.68  6561.6   896.7    6575  896.66
#Mann= 14 ,-1 , 0
  3482.2     .12       0  4364.2    .035       0  4521.7     .07       0
  4576.4     .05       0  4606.8     .07       0    4726    .035       0
  4983.5     .07       0    5038    .035       0  6044.6     .07       0
  6116.7    .035       0  6156.3     .07       0  6304.8    .035       0
    6374     .07       0  6561.6    .035       0
Bank Sta=4576.4,4606.8
XS Rating Curve= 0 ,0
Exp/Cntr=0.3,0.1

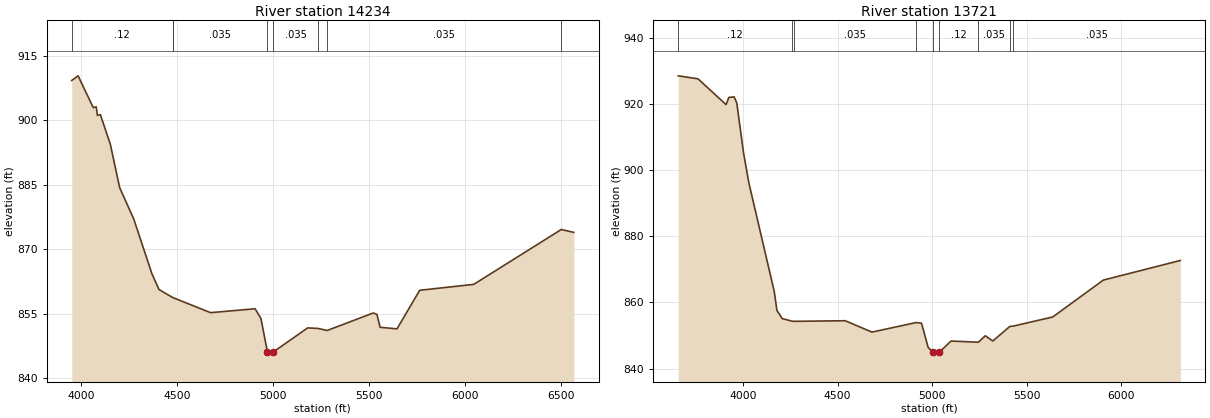
Type RM Length L Ch R = 1 ,14234   ,513,513,513
BEGIN DESCRIPTION:
H21643
END DESCRIPTION:
XS GIS Cut Line= 3
      2196548.13     13798746.47      2195916.84     13797714.12
      2195575.51     13796348.81
#Sta/Elev= 30
  3949.6  909.32  3982.5   910.4  4061.9  902.98  4077.3  903.17  4083.2   901.2
  4098.6  901.37  4150.6  894.47  4199.3  884.36  4272.8  877.04  4367.6  864.28
  4404.3  860.62  4476.5  858.74  4476.6  858.74  4673.3  855.23  4905.5  856.14
  4935.9  853.86  4969.6  846.07  4970.1  845.57  5000.1  846.07  5179.4  851.68
    5233  851.56  5281.1  851.08  5521.2  855.15  5540.2  854.84  5557.3  851.82
  5644.9  851.45  5763.4  860.44  6045.2  861.82  6501.5   874.6    6567  873.93
#Mann= 8 ,-1 , 0
  3949.6     .12       0  4476.5     .07       0  4476.6    .035       0
  4969.6     .05       0  5000.1    .035       0    5233     .07       0
  5281.1    .035       0  6501.5     .07       0
Bank Sta=4969.6,5000.1
XS Rating Curve= 0 ,0
Exp/Cntr=0.3,0.1

Type RM Length L Ch R = 1 ,13721   ,582,582,582
BEGIN DESCRIPTION:
H21642
END DESCRIPTION:
XS GIS Cut Line= 3
      2197283.41     13798464.24      2196169.37     13797283.35
      2195679.16      13796377.2
#Sta/Elev= 30
  3657.6  928.64  3762.1  927.73  3910.6  919.92  3924.8  922.08  3953.1  922.27
  3967.2   920.4  4002.4  905.45  4030.8  896.25  4165.2  863.31  4179.2   857.6
  4207.5  855.11  4260.8  854.33    4267  854.29  4540.1  854.47  4681.7  851.03
  4915.3  853.92  4943.5  853.72  4978.7  846.36  5005.9  844.86  5006.4  844.36
  5036.4  844.86  5099.2  848.32    5244  847.97  5280.6  849.92  5320.4  848.34
    5410  852.73  5428.6  852.85    5637  855.61  5904.5  866.78  6311.3  872.72
#Mann= 9 ,-1 , 0
  3657.6     .12       0  4260.8     .07       0    4267    .035       0
  4915.3     .12       0  5005.9     .05       0  5036.4     .12       0
    5244    .035       0    5410     .07       0  5428.6    .035       0
Bank Sta=5005.9,5036.4
XS Rating Curve= 0 ,0
Exp/Cntr=0.3,0.1