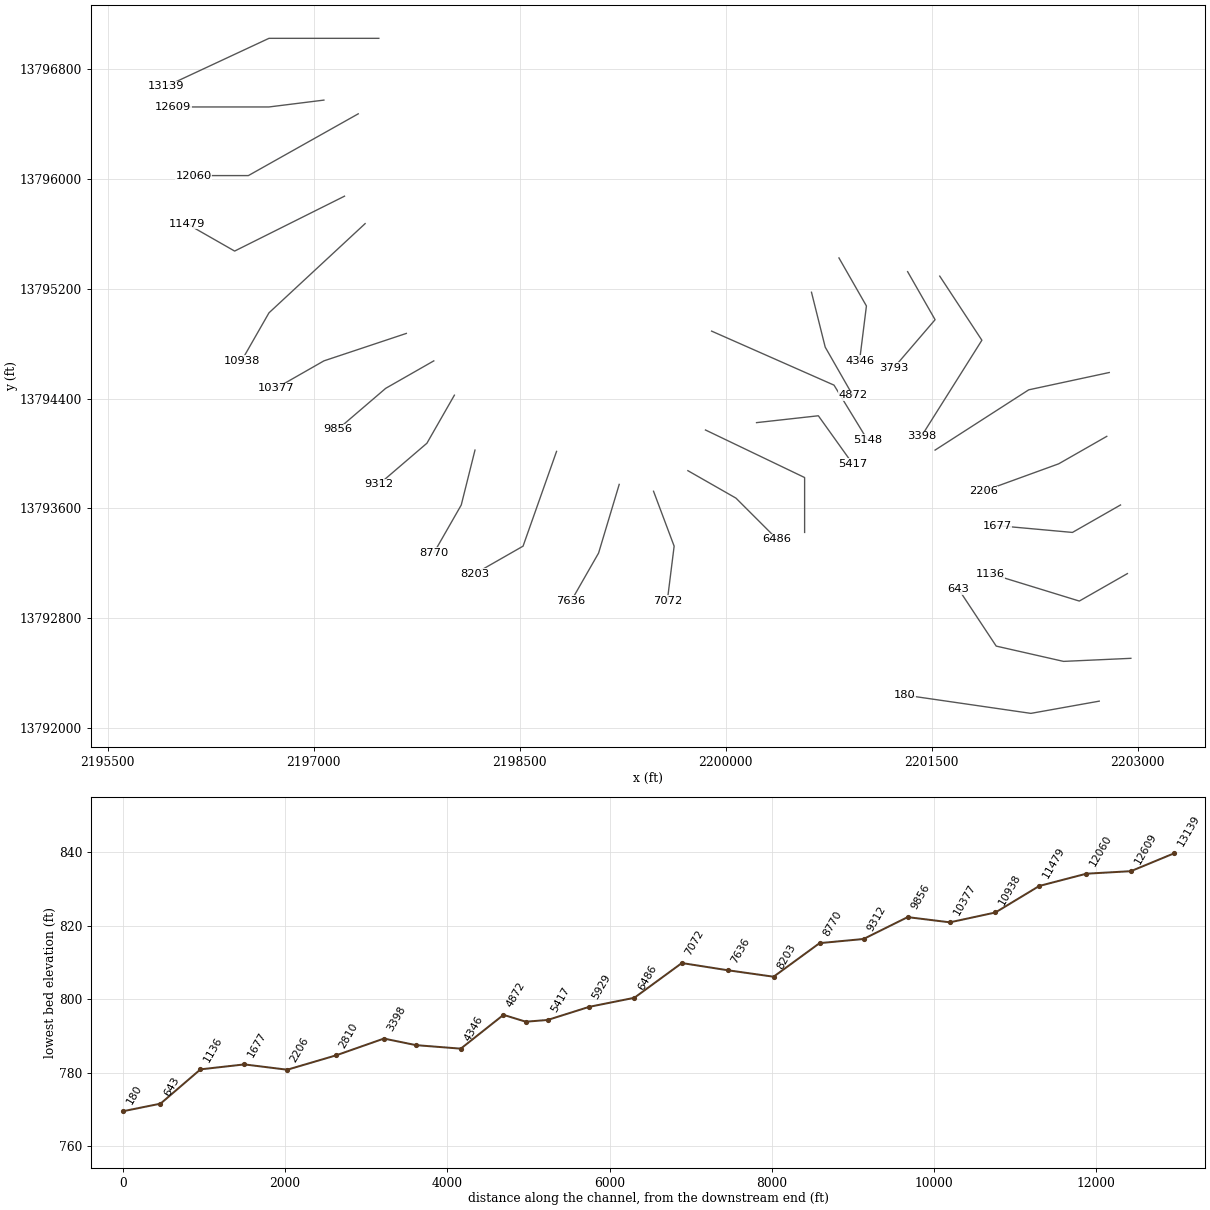
HEC-RAS study West Fork Dry Comal Creek.prj: West Fork Dry Comal Creek

--- West Fork Dry Comal Creek.g01 (geometry) --- (continued)

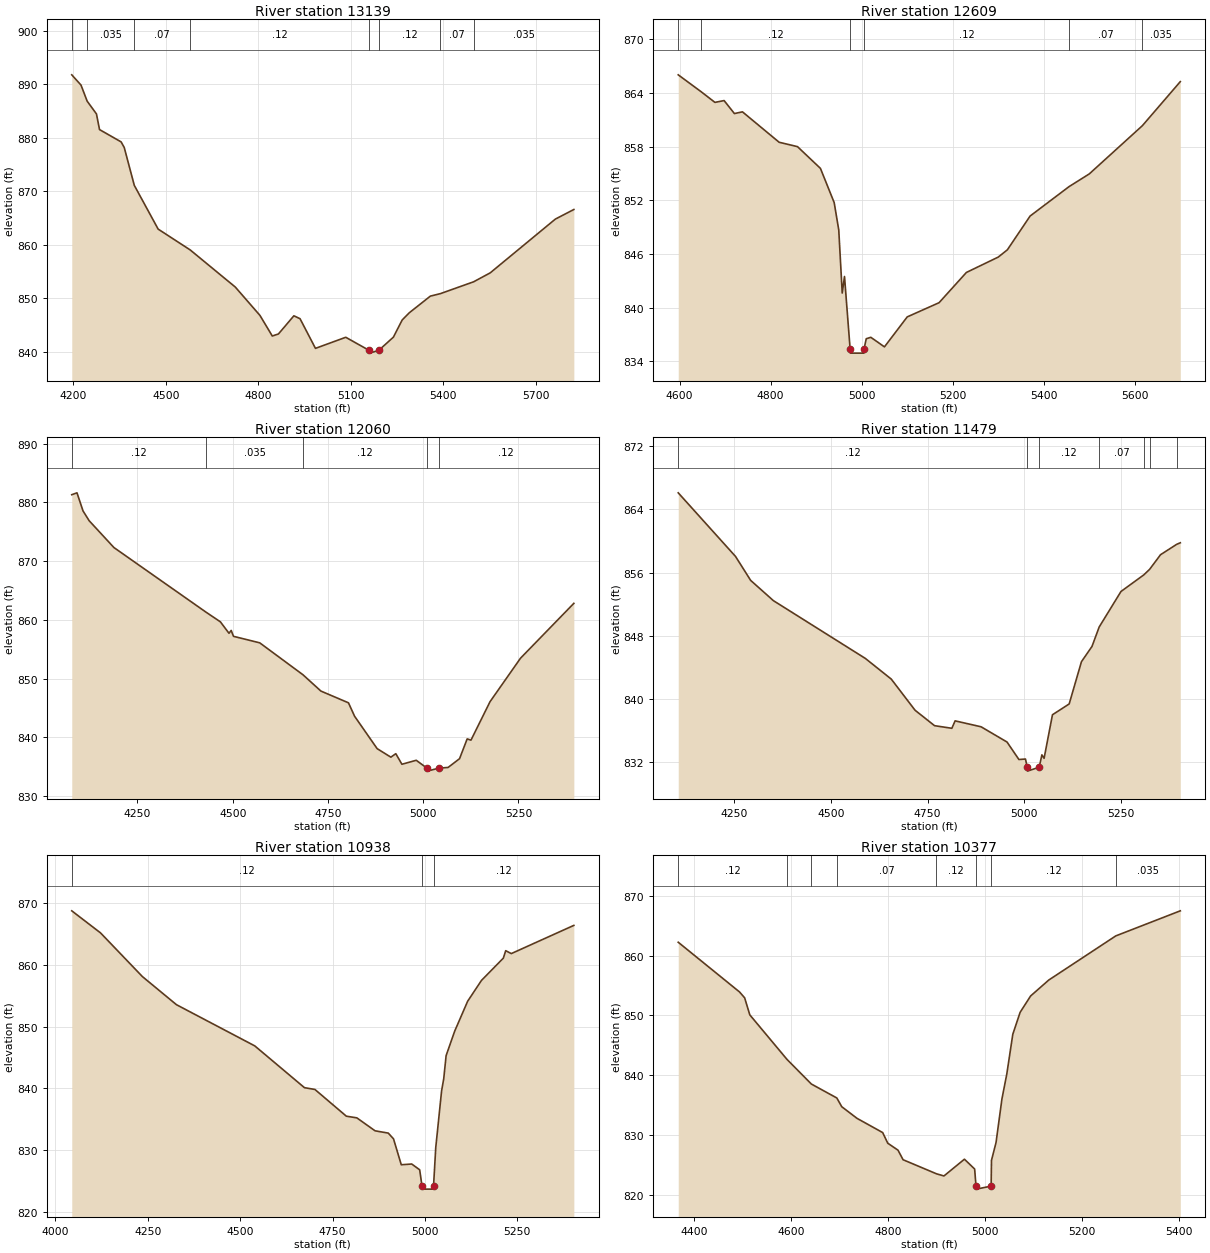
Type RM Length L Ch R = 1 ,13139   ,530,530,530
BEGIN DESCRIPTION:
West Fork 24.0
END DESCRIPTION:
XS GIS Cut Line= 3
      2197474.95       13797025.        2196675.       13797025.
        2195925.       13796675.
#Sta/Elev= 30
  4195.5  891.74  4225.5  889.82  4245.4  886.82  4275.5  884.44  4285.5  881.51
  4355.5  879.21  4365.5  878.18  4398.2  871.09  4475.5  862.92  4579.4  859.03
  4725.5   852.1  4805.5   846.8  4845.5  842.95  4865.5  843.33  4915.5  846.72
  4935.5  846.18  4985.5  840.64  5083.7  842.71  5159.9  840.25  5160.4  839.75
  5190.4  840.25  5238.2  842.74  5266.6  845.94  5289.5  847.28    5358   850.4
  5390.8  850.87    5498  853.07  5551.9  854.74  5763.2  864.79  5823.1  866.58
#Mann= 8 ,-1 , 0
  4195.5     .12       0  4245.4    .035       0  4398.2     .07       0
  4579.4     .12       0  5159.9     .05       0  5190.4     .12       0
  5390.8     .07       0    5498    .035       0
Bank Sta=5159.9,5190.4
XS Rating Curve= 0 ,0
Exp/Cntr=0.3,0.1

Type RM Length L Ch R = 1 ,12609   ,549,549,549
BEGIN DESCRIPTION:
West Fork 23.0
END DESCRIPTION:
XS GIS Cut Line= 3
      2197074.99       13796575.        2196675.       13796525.
        2195975.       13796525.
#Sta/Elev= 30
  4596.9  866.03  4647.2  864.14  4677.5  862.95  4697.7  863.15  4720.3   861.7
    4738  861.89  4818.6  858.49  4858.9     858  4909.3  855.57  4939.5  851.75
  4949.6  848.68  4957.2  841.63  4962.2  843.48  4974.5  835.41    4975  834.91
  5004.8  834.91  5005.3  835.41    5010  836.52    5020  836.68    5050  835.61
    5100  838.96    5170  840.55    5230  843.93    5300  845.65    5320  846.46
    5370  850.24  5455.6  853.53    5500  854.95  5616.6  860.34    5700  865.27
#Mann= 6 ,-1 , 0
  4596.9    .035       0  4647.2     .12       0  4974.5     .05       0
  5005.3     .12       0  5455.6     .07       0  5616.6    .035       0
Bank Sta=4974.5,5005.3
XS Rating Curve= 0 ,0
Exp/Cntr=0.3,0.1

Type RM Length L Ch R = 1 ,12060   ,581,581,581
BEGIN DESCRIPTION:
West Fork 22.0
END DESCRIPTION:
XS GIS Cut Line= 3
      2197325.01       13796475.        2196525.       13796025.
      2196124.99       13796025.
#Sta/Elev= 30
  4077.5  881.32  4091.2  881.64  4107.1  878.55  4123.1  876.89  4188.1  872.32
  4429.8  861.31  4467.6  859.66  4490.2  857.71    4496  858.19    4502  857.19
  4570.9  856.08  4684.4  850.64  4731.5  847.86  4803.8  845.86  4819.8  843.58
  4879.1  838.05  4915.1   836.6  4928.1  837.19  4944.1  835.39  4981.7  836.07
    5010  834.72  5010.5  834.22  5040.8  834.72  5065.4  834.85  5095.4  836.34
  5115.4  839.71  5125.4   839.5  5175.4  846.05  5255.4  853.46  5395.4  862.81
#Mann= 5 ,-1 , 0
  4077.5     .12       0  4429.8    .035       0  4684.4     .12       0
    5010     .05       0  5040.8     .12       0
Bank Sta=5010,5040.8
XS Rating Curve= 0 ,0
Exp/Cntr=0.3,0.1

Type RM Length L Ch R = 1 ,11479   ,541,541,541
BEGIN DESCRIPTION:
West Fork 21.0
END DESCRIPTION:
XS GIS Cut Line= 3
      2197224.98     13795874.99        2196425.       13795475.
      2196075.01     13795674.99
#Sta/Elev= 30
  4105.5  866.09  4253.6  858.04  4292.7  855.01  4351.4  852.45    4589  845.14
  4656.1  842.52  4717.6  838.58  4767.9  836.63  4812.6   836.3    4821  837.24
  4888.1  836.49  4955.2  834.56  4985.9  832.35  5002.8  832.41  5007.5  831.38
    5008  830.88  5038.4  831.38  5045.3  832.94    5051   832.5  5072.6  838.01
  5115.8  839.38  5147.5  844.72  5174.8  846.66  5193.3  849.11  5249.7  853.61
  5308.7  855.71  5323.7  856.41  5351.9  858.26  5393.5  859.57    5403  859.77
#Mann= 7 ,-1 , 0
  4105.5     .12       0  5007.5     .05       0  5038.4     .12       0
  5193.3     .07       0  5308.7    .035       0  5323.7     .07       0
  5393.5     .12       0
Bank Sta=5007.5,5038.4
XS Rating Curve= 0 ,0
Exp/Cntr=0.3,0.1

Type RM Length L Ch R = 1 ,10938   ,561,561,561
BEGIN DESCRIPTION:
West Fork 20.0
END DESCRIPTION:
XS GIS Cut Line= 3
        2197375.       13795675.        2196675.       13795025.
      2196474.98     13794674.96
#Sta/Elev= 30
  4044.5  868.75  4122.4  865.17  4235.5   858.1  4327.7  853.54  4539.7  846.86
  4674.1  840.09  4702.4   839.8  4787.4  835.47  4815.8   835.2  4865.1   833.1
  4900.8  832.73    4915   831.8    4936   827.6  4964.3  827.72  4985.8  826.78
  4992.1  824.15  4992.6  823.65  5022.8  823.65  5023.3  824.15  5029.3  830.39
  5045.1  839.58  5050.9  841.55  5057.3  845.28  5080.4  849.23  5115.6   854.1
  5153.1  857.48  5212.1  861.08  5218.6  862.29  5233.7  861.82  5402.9  866.39
#Mann= 3 ,-1 , 0
  4044.5     .12       0  4992.1     .05       0  5023.3     .12       0
Bank Sta=4992.1,5023.3
XS Rating Curve= 0 ,0
Exp/Cntr=0.3,0.1

Type RM Length L Ch R = 1 ,10377   ,521,521,521
BEGIN DESCRIPTION:
West Fork 19.0
END DESCRIPTION:
XS GIS Cut Line= 3
      2197675.01       13794875.        2197075.       13794675.
      2196724.98     13794474.99
#Sta/Elev= 30
  4367.3  862.22  4493.8  853.91  4504.3  852.93  4514.9  850.09  4591.6  842.65
  4641.9  838.53  4694.4   836.2  4704.6  834.74  4736.2  832.79    4789  830.42
  4799.5  828.64  4820.6  827.48  4831.1  825.88    4900  823.53  4915.4  823.17
  4957.6  825.97  4978.7  824.33  4981.5  821.47    4982  820.97  5012.7  821.47
  5013.4  825.77  5022.8  828.75    5035  836.05  5045.1  840.24  5057.4  846.85
  5072.5  850.51  5094.1  853.24  5131.5   855.9  5269.8  863.28  5402.9  867.47
#Mann= 8 ,-1 , 0
  4367.3     .12       0  4591.6     .07       0  4641.9     .12       0
  4694.4     .07       0    4900     .12       0  4981.5     .05       0
  5012.7     .12       0  5269.8    .035       0
Bank Sta=4981.5,5012.7
XS Rating Curve= 0 ,0
Exp/Cntr=0.3,0.1

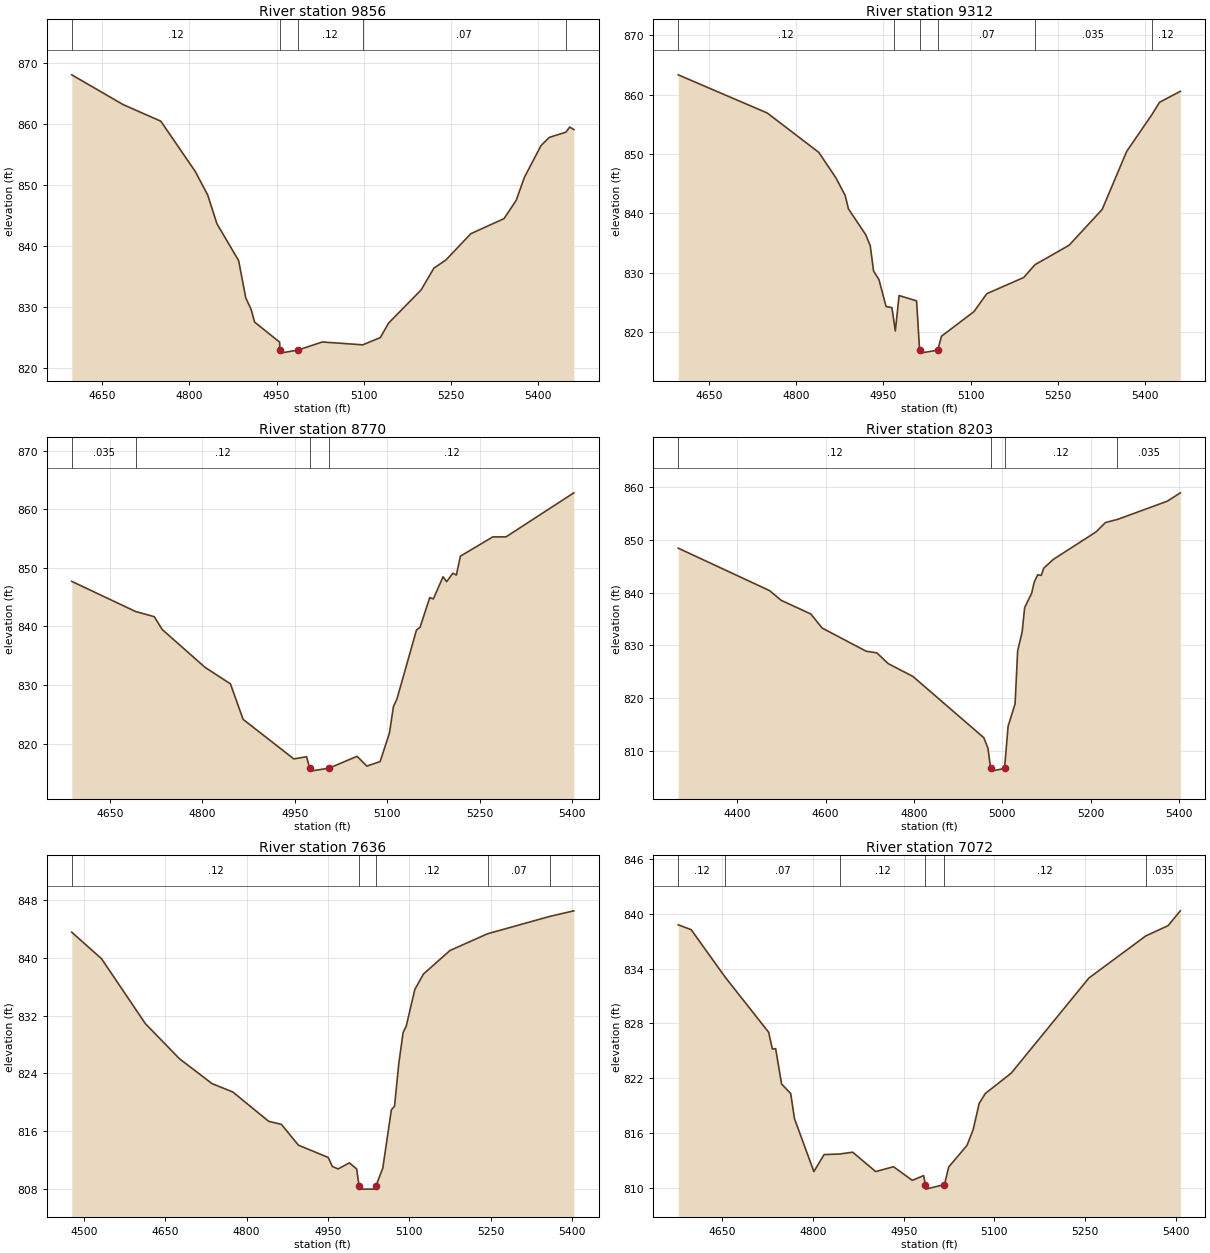
Type RM Length L Ch R = 1 ,9856    ,544,544,544
BEGIN DESCRIPTION:
West Fork 18.0
END DESCRIPTION:
XS GIS Cut Line= 3
        2197875.       13794675.        2197525.       13794475.
        2197175.       13794175.
#Sta/Elev= 30
  4597.6  868.06  4686.1  863.17  4750.9  860.45    4810  852.22  4831.6  848.33
  4847.4  843.63  4884.8  837.57  4897.1  831.45  4906.4  829.54  4912.2  827.49
  4955.4  824.19  4955.6  822.89  4956.1  822.39  4986.9  822.89  5028.7  824.22
  5098.3  823.75  5128.6  824.94  5142.9  827.32  5198.8  832.76  5220.8  836.33
  5241.6  837.68  5284.4  841.99  5341.5  844.46  5362.4  847.45  5376.6  851.24
  5405.2  856.45  5419.4  857.79    5448  858.65  5454.6  859.49  5461.7  859.08
#Mann= 5 ,-1 , 0
  4597.6     .12       0  4955.6     .05       0  4986.9     .12       0
  5098.3     .07       0    5448     .12       0
Bank Sta=4955.6,4986.9
XS Rating Curve= 0 ,0
Exp/Cntr=0.3,0.1

Type RM Length L Ch R = 1 ,9312    ,542,542,542
BEGIN DESCRIPTION:
West Fork 17.0
END DESCRIPTION:
XS GIS Cut Line= 3
      2198024.99     13794424.99        2197825.       13794075.
      2197474.98     13793774.99
#Sta/Elev= 30
  4596.9  863.35  4750.2  856.91  4838.8  850.28  4868.3  845.98  4884.1  843.04
  4889.9  840.74  4919.4  836.42  4927.3  834.58  4933.1  830.28  4942.4  828.81
  4954.6  824.29  4964.7   824.1  4967.5   822.2  4970.5  820.16    4977  826.14
  5007.1  825.24  5012.3  816.93  5012.8  816.43  5043.6  816.93  5049.9  819.28
  5105.9  823.43  5127.9  826.45  5191.5  829.18  5210.9  831.34  5269.5  834.61
  5326.5  840.65  5368.8  850.46  5411.9  856.61  5425.3  858.72    5461  860.57
#Mann= 6 ,-1 , 0
  4596.9     .12       0  4967.5     .07       0  5012.3     .05       0
  5043.6     .07       0  5210.9    .035       0  5411.9     .12       0
Bank Sta=5012.3,5043.6
XS Rating Curve= 0 ,0
Exp/Cntr=0.3,0.1

Type RM Length L Ch R = 1 ,8770    ,567,567,567
BEGIN DESCRIPTION:
West Fork 16.0
END DESCRIPTION:
XS GIS Cut Line= 3
      2198174.99     13794024.97        2198075.       13793625.
        2197875.       13793275.
#Sta/Elev= 30
  4587.7  847.67  4691.2  842.54  4721.7  841.65  4734.6  839.46  4804.1  833.01
  4845.4  830.19    4866  824.13  4948.4  817.38  4969.1  817.76    4974   815.8
  4974.5   815.3  5005.4   815.8  5051.1  817.83  5066.9  816.16  5088.5  816.93
  5103.6  821.79  5110.1  826.31  5115.9  827.64  5147.6  839.39  5153.3  839.83
  5169.1  844.91  5174.9  844.68  5190.7  848.46  5196.5  847.62  5206.6  849.07
  5212.3  848.75  5218.8  851.97  5271.4  855.26    5293  855.27  5403.1  862.78
#Mann= 4 ,-1 , 0
  4587.7    .035       0  4691.2     .12       0    4974     .05       0
  5005.4     .12       0
Bank Sta=4974,5005.4
XS Rating Curve= 0 ,0
Exp/Cntr=0.3,0.1

Type RM Length L Ch R = 1 ,8203    ,567,567,567
BEGIN DESCRIPTION:
West Fork 15.0
END DESCRIPTION:
XS GIS Cut Line= 3
      2198768.87     13794015.42        2198525.       13793325.
      2198175.03     13793125.02
#Sta/Elev= 30
    4267  848.42  4473.8  840.36  4499.6  838.54  4566.8  835.94  4592.4  833.28
  4691.7  828.89  4716.1  828.57  4741.7  826.54  4797.7   824.1  4958.1  812.48
  4967.4  810.47  4973.4  806.65  4973.9  806.15  5004.8  806.65  5012.9  814.66
  5028.7  818.91  5034.5  828.97  5044.6   832.5  5050.3  837.14  5066.2  839.89
  5071.9  841.96  5079.8  843.38  5087.8  843.25  5093.5  844.63  5115.1  846.29
  5211.6  851.49  5233.2  853.29  5259.9  853.86  5372.8  857.32  5402.3  858.91
#Mann= 4 ,-1 , 0
    4267     .12       0  4973.4     .05       0  5004.8     .12       0
  5259.9    .035       0
Bank Sta=4973.4,5004.8
XS Rating Curve= 0 ,0
Exp/Cntr=0.3,0.1

Type RM Length L Ch R = 1 ,7636    ,564,564,564
BEGIN DESCRIPTION:
West Fork 14.0
END DESCRIPTION:
XS GIS Cut Line= 3
      2199224.99     13793774.97        2199075.       13793275.
        2198875.       13792925.
#Sta/Elev= 30
    4478  843.56  4532.8  839.89  4613.7  830.87  4676.3  826.02  4736.4  822.56
  4774.7   821.4  4840.8  817.33  4864.3   816.9  4895.6  814.02  4950.4  812.32
  4958.2  811.06  4968.7  810.72  4989.5  811.56  5002.9  810.72  5007.3  808.42
  5007.8  807.92  5038.3  807.92  5038.8  808.42  5051.1  810.85  5066.9  818.93
  5072.7  819.43  5080.6  825.37  5088.5  829.65  5094.3  830.54  5110.1  835.62
    5126  837.76  5174.9  841.03  5244.2  843.35  5359.4  845.77  5403.1  846.53
#Mann= 5 ,-1 , 0
    4478     .12       0  5007.3     .05       0  5038.8     .12       0
  5244.2     .07       0  5359.4     .12       0
Bank Sta=5007.3,5038.8
XS Rating Curve= 0 ,0
Exp/Cntr=0.3,0.1

Type RM Length L Ch R = 1 ,7072    ,586,586,586
BEGIN DESCRIPTION:
West Fork 13.0
END DESCRIPTION:
XS GIS Cut Line= 3
        2199475.     13793724.99        2199625.       13793325.
        2199575.       13792925.
#Sta/Elev= 30
  4577.1  838.79  4598.5  838.26  4654.7  833.07  4726.6  827.04  4732.8   825.2
  4738.2  825.25    4748  821.38  4763.1  820.33  4769.3   817.6  4801.4   811.8
  4818.3  813.66  4843.9  813.72  4865.5  813.92  4903.7   811.8  4933.1  812.33
  4964.2  810.84  4982.9  811.36  4985.9  810.38  4986.4  809.88  5017.4  810.38
  5024.4   812.3  5054.7  814.67  5064.8  816.38  5074.8  819.26  5084.9  820.34
  5127.7  822.56  5256.2  832.97  5350.2  837.57  5387.2   838.7  5407.4  840.32
#Mann= 6 ,-1 , 0
  4577.1     .12       0  4654.7     .07       0  4843.9     .12       0
  4985.9     .05       0  5017.4     .12       0  5350.2    .035       0
Bank Sta=4985.9,5017.4
XS Rating Curve= 0 ,0
Exp/Cntr=0.3,0.1

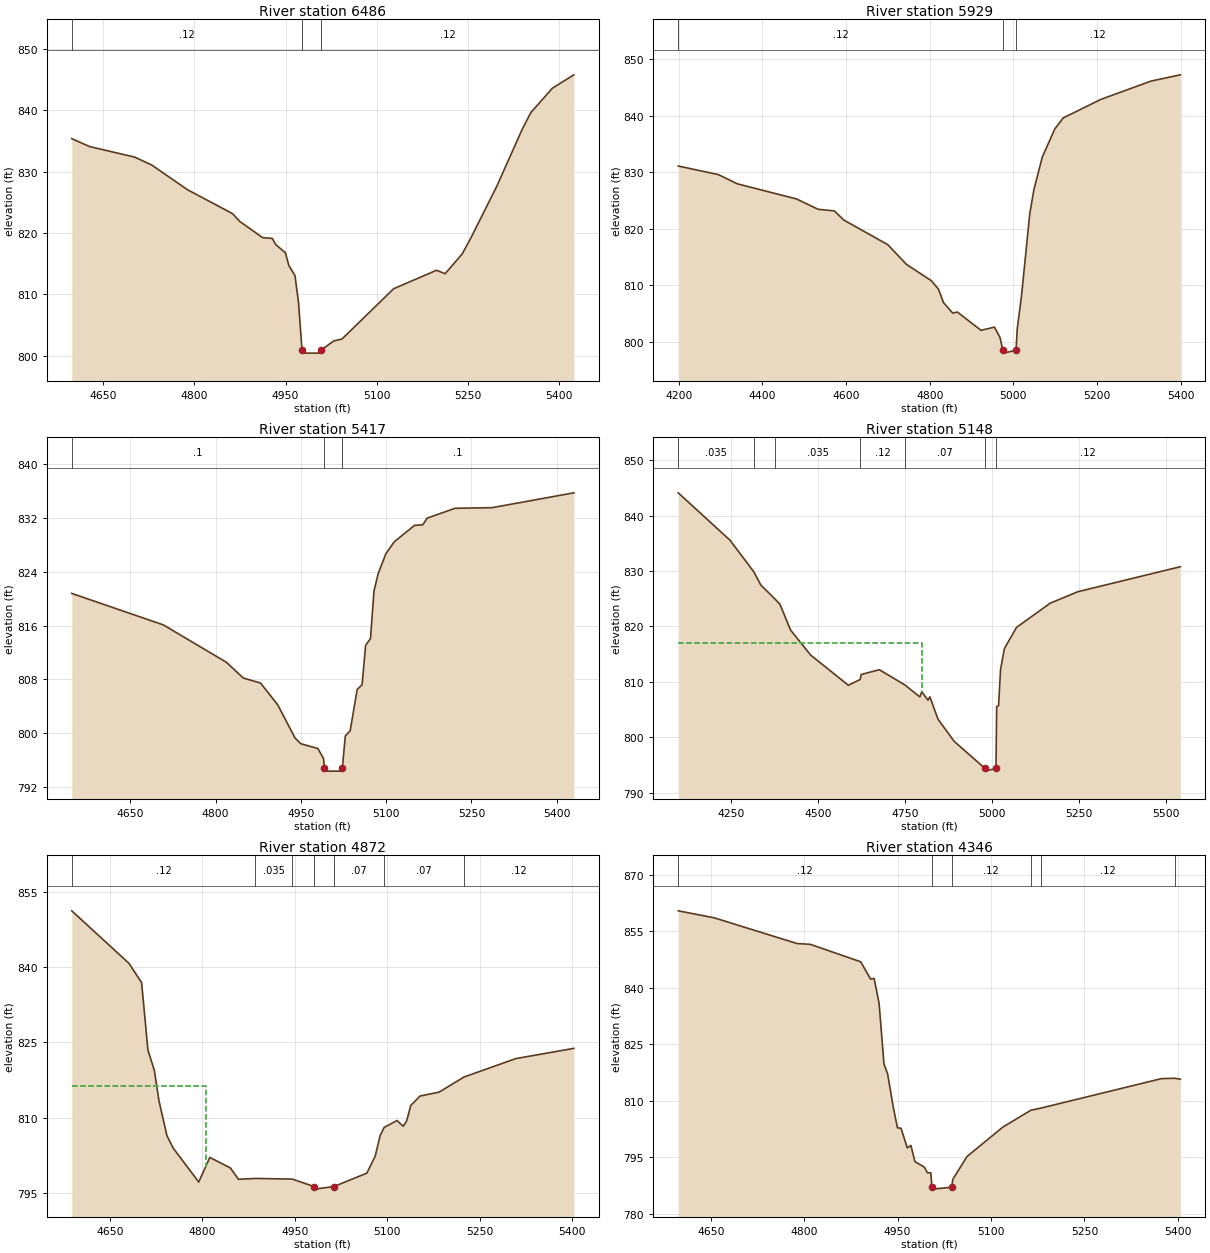
Type RM Length L Ch R = 1 ,6486    ,557,557,557
BEGIN DESCRIPTION:
West Fork 12.0
END DESCRIPTION:
XS GIS Cut Line= 3
      2199725.03     13793874.98        2200075.       13793675.
      2200374.97     13793375.03
#Sta/Elev= 30
  4597.8  835.38  4627.3  834.08  4701.4  832.37  4729.5  831.08  4788.5  827.05
  4862.7  823.15  4874.9  821.86  4912.3  819.24  4928.2  819.11  4933.9   818.1
  4949.8  816.78  4955.5   814.7  4965.6  813.05  4971.4   808.7  4977.2  800.91
  4977.7  800.41  5008.2  800.41  5008.7  800.91  5029.2  802.38  5043.3  802.73
  5128.2  810.91  5198.9  813.92    5213  813.35  5241.3  816.61  5255.4  819.18
  5297.9  827.56  5340.3  836.96  5354.4  839.65  5389.8   843.6  5425.1  845.78
#Mann= 3 ,-1 , 0
  4597.8     .12       0  4977.2     .05       0  5008.7     .12       0
Bank Sta=4977.2,5008.7
XS Rating Curve= 0 ,0
Exp/Cntr=0.3,0.1

Type RM Length L Ch R = 1 ,5929    ,512,512,512
BEGIN DESCRIPTION:
West Fork 11.0
END DESCRIPTION:
XS GIS Cut Line= 3
      2199853.21     13794171.38        2200575.       13793825.
        2200575.       13793425.
#Sta/Elev= 30
  4198.7  831.09  4294.7  829.57    4340  827.94  4481.4  825.26  4533.4  823.42
    4572  823.14  4594.6  821.52  4699.8  817.16  4744.2  813.68    4804  810.77
  4821.1  809.26  4832.9  806.91  4855.1  805.03  4866.2  805.22  4922.8  801.98
  4954.9  802.55  4968.1  800.72  4974.9  798.44  4975.4  797.94  5006.5  798.44
  5009.3   802.2  5019.3   807.9  5039.3  822.62  5049.3  826.93  5069.3  832.68
  5099.3  837.68  5119.3  839.61  5209.3   842.9  5329.3  846.14  5399.3  847.25
#Mann= 3 ,-1 , 0
  4198.7     .12       0  4974.9     .05       0  5006.5     .12       0
Bank Sta=4974.9,5006.5
XS Rating Curve= 0 ,0
Exp/Cntr=0.3,0.1

Type RM Length L Ch R = 1 ,5417    ,269,269,269
BEGIN DESCRIPTION:
West Fork 10.0
END DESCRIPTION:
XS GIS Cut Line= 3
        2200225.       13794225.        2200675.       13794275.
      2200925.01     13793924.99
#Sta/Elev= 30
  4547.1   820.8  4708.1  816.12  4818.8  810.57  4848.9  808.21  4879.1  807.47
  4909.3  804.23  4939.5  799.33  4949.6  798.45  4979.7  797.74  4989.8  796.26
  4991.4  794.87  4991.9  794.37  5022.5  794.37    5023  794.87  5028.1   799.6
  5036.7  800.37    5049  806.52  5057.6   807.2  5063.8  813.06  5072.4  814.09
  5078.5  821.14  5085.9  823.74  5099.4   826.7  5114.2  828.48  5149.8  830.92
  5164.5  831.01  5171.9  831.99  5221.1  833.46  5286.2  833.55    5430  835.76
#Mann= 3 ,-1 , 0
  4547.1      .1       0  4991.4     .05       0    5023      .1       0
Bank Sta=4991.4,5023
XS Rating Curve= 0 ,0
Exp/Cntr=0.3,0.1

Type RM Length L Ch R = 1 ,5148    ,276,276,276
BEGIN DESCRIPTION:
H21641
END DESCRIPTION:
XS GIS Cut Line= 3
      2199897.83     13794891.79      2200789.05     13794498.17
      2201033.26     13794098.56
#Sta/Elev= 30
  4099.3  844.13    4248  835.58  4316.6  829.86  4336.7  827.47  4377.2  824.97
  4391.4  824.03  4422.1  819.36  4479.6  814.85  4588.1  809.39  4622.1  810.43
    4625  811.33    4677   812.2  4750.3  809.46  4793.6  807.29    4799  808.22
  4816.9  806.69  4822.4   807.3  4845.7  803.26  4892.3  799.26  4980.6  794.39
  4981.1  793.89  5012.2  794.39  5014.3  805.54  5019.7  805.69  5025.4  812.22
  5036.4  816.01  5071.3  819.84  5168.2  824.21  5247.6  826.28  5541.9  830.79
#Mann= 7 ,-1 , 0
  4099.3    .035       0  4316.6     .12       0  4377.2    .035       0
  4622.1     .12       0  4750.3     .07       0  4980.6     .05       0
  5012.2     .12       0
#XS Ineff= 2 , 0
       0    4800     817               0
Permanent Ineff=
       F       F
Bank Sta=4980.6,5012.2
XS Rating Curve= 0 ,0
Exp/Cntr=0.3,0.1

Type RM Length L Ch R = 1 ,4872    ,526,526,526
BEGIN DESCRIPTION:
West Fork 9.0
END DESCRIPTION:
XS GIS Cut Line= 3
        2200625.       13795175.        2200725.       13794775.
      2200924.99     13794425.02
#Sta/Elev= 30
  4587.7  851.22  4680.5  840.77  4701.1  836.91  4711.4  823.46  4721.7  819.48
  4729.4  813.32  4742.3  806.39  4752.6   803.9  4793.9  797.17  4811.9  802.08
  4845.4  799.97  4858.3  797.72    4886  797.89  4945.8  797.76  4981.6  796.26
  4982.1  795.76  5013.2  796.26    5067  798.95  5080.6  802.37  5088.5  806.42
    5095  808.05  5115.9  809.43    5126  808.28  5131.7  809.38  5138.2  812.42
  5153.3  814.31  5184.3  815.09  5224.7   818.1  5308.8  821.77  5403.1  823.81
#Mann= 7 ,-1 , 0
  4587.7     .12       0    4886    .035       0  4945.8     .07       0
  4981.6    .035       0  5013.2     .07       0    5095     .07       0
  5224.7     .12       0
#XS Ineff= 2 , 0
       0    4805   816.3               0
Permanent Ineff=
       F       F
Bank Sta=4981.6,5013.2
XS Rating Curve= 0 ,0
Exp/Cntr=0.3,0.1

Type RM Length L Ch R = 1 ,4346    ,553,553,553
BEGIN DESCRIPTION:
West Fork 8.0
END DESCRIPTION:
XS GIS Cut Line= 3
        2200825.     13795424.99        2201025.       13795075.
        2200975.     13794675.02
#Sta/Elev= 30
  4597.8  860.49  4655.4  858.64  4788.6   851.8  4810.1  851.58  4890.8  846.95
  4906.6  842.37  4912.4  842.52  4920.3  835.92  4928.2  819.75    4934  817.19
  4943.3  808.13  4949.8  802.84  4955.6  802.71  4965.6   797.5  4971.4  798.15
  4977.9  793.85    4993  792.39    4998  790.89  5003.4  790.89  5005.2  787.05
  5005.7  786.55    5037  787.05  5038.7  789.14  5061.4   795.2  5119.3  803.06
    5164  807.51    5181  808.11  5373.8  815.91  5395.7  816.01    5404  815.74
#Mann= 6 ,-1 , 0
  4597.8     .12       0  5005.2     .05       0    5037     .12       0
    5164     .07       0    5181     .12       0  5395.7    .035       0
Bank Sta=5005.2,5037
XS Rating Curve= 0 ,0
Exp/Cntr=0.3,0.1

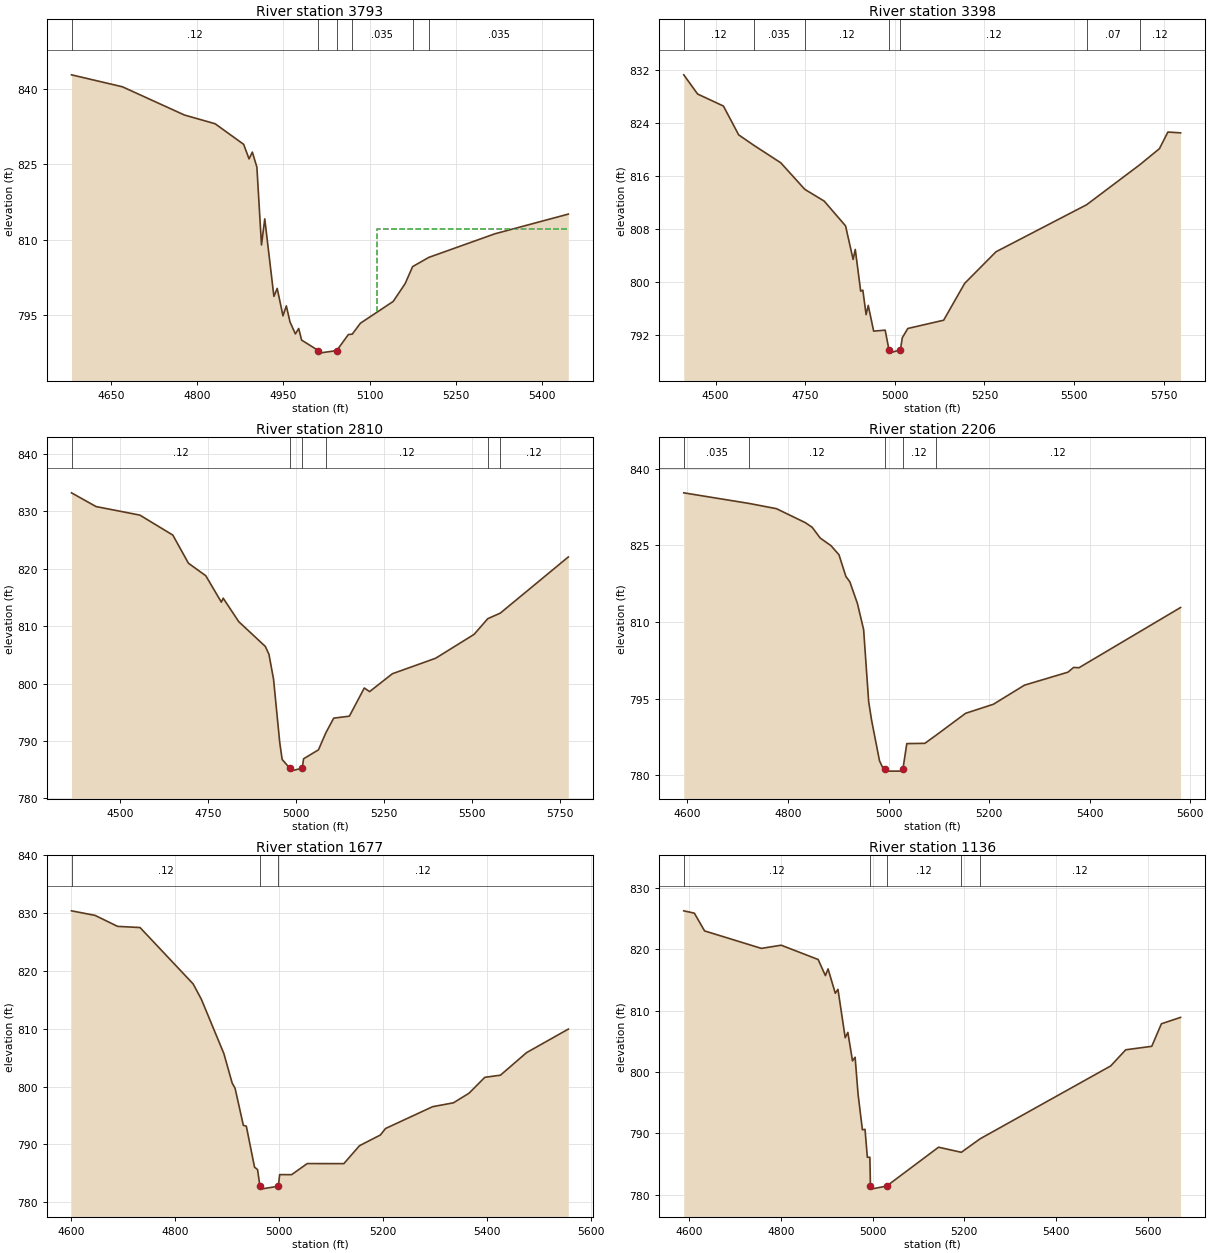
Type RM Length L Ch R = 1 ,3793    ,395,395,395
BEGIN DESCRIPTION:
West Fork 7.0
END DESCRIPTION:
XS GIS Cut Line= 3
      2201325.02     13795324.96        2201525.       13794975.
      2201225.03     13794625.03
#Sta/Elev= 30
  4581.4  842.72  4669.9  840.35  4777.9  834.74  4831.1  833.02  4880.8  828.93
  4890.2  826.04  4895.9  827.39  4903.8  824.41  4911.8  808.97  4917.5  814.14
  4933.4  798.76  4939.1  800.35  4949.2  794.91    4955  796.89  4961.4  793.69
  4970.8  791.32  4976.5   792.4  4981.6  790.09  5010.8  788.01  5011.3  787.51
  5042.6  788.01  5062.9   791.2  5069.6  791.27  5083.8  793.44  5140.9  797.77
  5161.7  801.31  5174.6  804.67  5202.7   806.5  5317.6  811.18  5445.4  815.09
#Mann= 6 ,-1 , 0
  4581.4     .12       0  5010.8     .05       0  5042.6     .12       0
  5069.6    .035       0  5174.6      .1       0  5202.7    .035       0
#XS Ineff= 2 , 0
       0                    5112       0   812.1
Permanent Ineff=
       F       F
Bank Sta=5010.8,5042.6
XS Rating Curve= 0 ,0
Exp/Cntr=0.3,0.1

Type RM Length L Ch R = 1 ,3398    ,588,588,588
BEGIN DESCRIPTION:
West Fork 6.0
END DESCRIPTION:
XS GIS Cut Line= 3
      2201558.83     13795292.46      2201865.67     13794825.38
      2201425.02     13794125.03
#Sta/Elev= 30
  4411.1  831.32  4449.8  828.42  4521.7  826.61  4564.3  822.26  4605.8  820.71
  4681.8  818.04  4748.8  814.03  4802.9  812.26  4862.6  808.51  4883.7  803.44
  4889.7  804.96  4904.8  798.65  4910.8  798.81  4919.9  795.11  4925.9   796.5
    4941  792.62  4973.1  792.77  4983.8   789.8  4984.3   789.3  5015.6   789.8
  5020.9  791.62  5036.2  793.02  5136.3  794.27  5194.9  799.83  5282.3   804.6
  5535.4  811.71    5683  817.72  5738.4  820.17    5762  822.68  5797.4  822.56
#Mann= 7 ,-1 , 0
  4411.1     .12       0  4605.8    .035       0  4748.8     .12       0
  4983.8     .05       0  5015.6     .12       0  5535.4     .07       0
    5683     .12       0
Bank Sta=4983.8,5015.6
XS Rating Curve= 0 ,0
Exp/Cntr=0.3,0.1

Type RM Length L Ch R = 1 ,2810    ,604,604,604
BEGIN DESCRIPTION:
West Fork 5.0
END DESCRIPTION:
XS GIS Cut Line= 3
      2202793.03     13794590.14      2202206.61     13794463.99
      2201524.98     13794024.99
#Sta/Elev= 30
  4363.1  833.21  4432.7  830.82  4557.2  829.33  4650.8  825.85  4695.1  820.95
  4744.4  818.77  4788.6  814.17  4793.8  814.86    4838  810.77  4913.4  806.46
  4923.7  805.09  4936.7  800.78  4954.4   789.7  4961.2  786.78  4982.9  785.24
  4983.7  784.74  5018.2  785.24    5022  786.89  5064.3  788.45  5085.3  791.42
  5107.6  793.97  5152.1  794.31  5194.4  799.22  5209.5  798.59  5274.1   801.7
    5397   804.4    5506  808.55    5545  811.29  5580.6  812.26  5773.7  822.04
#Mann= 6 ,-1 , 0
  4363.1     .12       0  4982.9     .05       0  5018.2     .12       0
  5085.3     .12       0    5545     .07       0  5580.6     .12       0
Bank Sta=4982.9,5018.2
XS Rating Curve= 0 ,0
Exp/Cntr=0.3,0.1

Type RM Length L Ch R = 1 ,2206    ,529,529,529
BEGIN DESCRIPTION:
West Fork 4.0
END DESCRIPTION:
XS GIS Cut Line= 3
        2202775.       13794125.        2202425.       13793925.
      2201875.04     13793725.01
#Sta/Elev= 30
  4592.7  835.29  4722.8  833.21    4777  832.19  4834.6  829.45  4848.2  828.54
  4864.1  826.44  4885.7  824.94  4901.5  823.16  4915.2  818.93  4923.1  817.86
  4938.2  813.62  4950.5  808.51  4960.5  794.45  4966.3   790.8  4982.1  782.83
  4987.9  781.61  4993.5  781.31  4994.2  780.81    5028  780.81  5028.8  781.31
  5036.4   786.2  5072.3  786.25  5093.7  787.77  5153.4  792.13  5208.6   793.9
  5270.5  797.64  5356.9  800.18  5368.2  801.11  5378.9  801.05    5581  812.84
#Mann= 5 ,-1 , 0
  4592.7    .035       0  4722.8     .12       0  4993.5     .05       0
  5028.8     .12       0  5093.7     .12       0
Bank Sta=4993.5,5028.8
XS Rating Curve= 0 ,0
Exp/Cntr=0.3,0.1

Type RM Length L Ch R = 1 ,1677    ,541,541,541
BEGIN DESCRIPTION:
West Fork 3.0
END DESCRIPTION:
XS GIS Cut Line= 3
      2202875.04     13793625.02        2202525.       13793425.
      2201975.02       13793475.
#Sta/Elev= 30
    4601   830.4  4646.4  829.61  4689.6  827.71  4732.8  827.51    4835  817.75
  4850.8  815.09    4894  805.71  4909.9  800.63  4915.6  799.69  4931.5  793.29
  4937.2  793.15    4953  786.06  4958.8  785.64  4963.4  782.76  4964.2  782.26
  4998.8  782.76  5001.3  784.77  5024.2  784.76  5054.4  786.68  5124.7  786.67
  5154.8  789.77  5194.9  791.62    5205  792.75  5295.4  796.52  5335.5  797.19
  5365.6  798.86  5395.8   801.6  5425.9  801.97  5476.1  805.87  5556.4  809.94
#Mann= 3 ,-1 , 0
    4601     .12       0  4963.4     .05       0  4998.8     .12       0
Bank Sta=4963.4,4998.8
XS Rating Curve= 0 ,0
Exp/Cntr=0.3,0.1

Type RM Length L Ch R = 1 ,1136    ,493,493,493
BEGIN DESCRIPTION:
West Fork 2.0
END DESCRIPTION:
XS GIS Cut Line= 3
      2202925.03     13793125.02        2202575.       13792925.
      2201925.02     13793124.99
#Sta/Elev= 30
  4588.3  826.25  4611.4  825.87  4633.7  822.98  4757.5  820.13  4800.7  820.65
  4881.3  818.32  4897.1   815.7  4902.9  816.79  4918.7  812.82  4924.5  813.46
  4940.3  805.58  4946.1  806.44  4956.2  801.81  4961.9   802.4  4968.4  796.33
  4977.8  790.58  4983.5  790.65  4988.6   786.1  4994.1   786.1  4995.3  781.41
  4996.1  780.91  5030.7  781.41  5143.8  787.74  5193.5  786.91  5234.2   789.1
  5519.2  800.98  5551.9  803.61  5608.7  804.18  5629.7  807.85  5671.5  808.89
#Mann= 5 ,-1 , 0
  4588.3     .12       0  4995.3     .05       0  5030.7     .12       0
  5193.5      .1       0  5234.2     .12       0
Bank Sta=4995.3,5030.7
XS Rating Curve= 0 ,0
Exp/Cntr=0.3,0.1

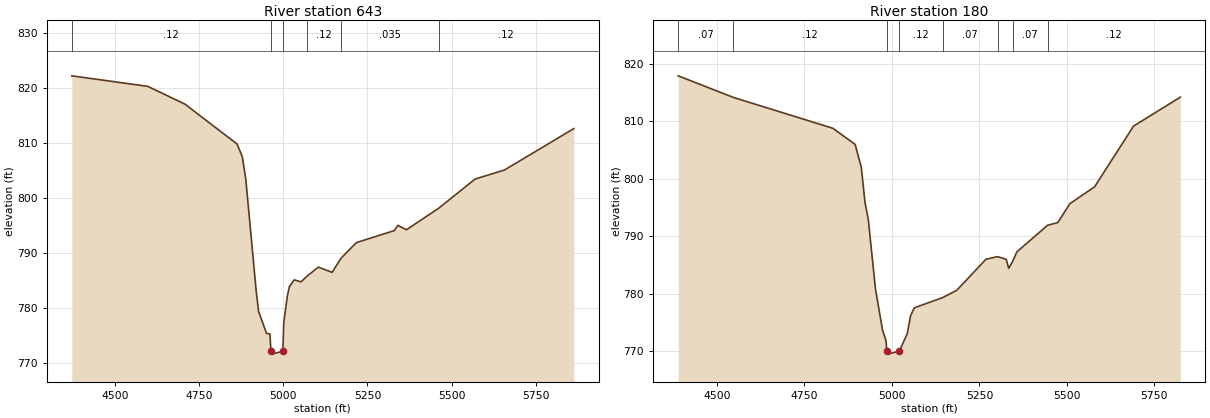
Type RM Length L Ch R = 1 ,643     ,463,463,463
BEGIN DESCRIPTION:
H21640
END DESCRIPTION:
XS GIS Cut Line= 4
       2202950.4      13792507.7      2202460.16     13792485.41
      2201969.97     13792596.82      2201696.07     13793011.37
#Sta/Elev= 30
  4372.5  822.26  4598.1  820.34  4708.2  817.11  4863.2  809.84  4878.8   807.5
  4889.1  803.41  4919.8  783.16    4927  779.34  4950.6  775.34  4960.8  775.23
  4963.6  772.06  4964.4  771.56    4999  772.06  5001.8  777.29  5012.1  782.04
  5018.3  783.82  5032.6  785.09  5053.1  784.73    5070  785.72  5104.4  787.41
  5145.4  786.46  5171.7  789.03  5217.2  791.87    5330  794.07  5340.3  795.02
  5365.9  794.22  5461.1  798.11  5569.5  803.45  5656.8   805.1  5862.8  812.65
#Mann= 6 ,-1 , 0
  4372.5     .12       0  4963.6     .05       0    4999     .12       0
    5070     .12       0  5171.7    .035       0  5461.1     .12       0
Bank Sta=4963.6,4999
XS Rating Curve= 0 ,0
Exp/Cntr=0.3,0.1

Type RM Length L Ch R = 1 ,180     ,0,0,0
BEGIN DESCRIPTION:
H21639
END DESCRIPTION:
XS GIS Cut Line= 3
      2202720.14     13792195.76      2202222.49     13792106.63
       2201302.6     13792240.16
#Sta/Elev= 30
  4389.1  817.94  4546.8  814.18  4831.2  808.81  4894.7  806.01  4912.3  802.04
  4922.8  795.96  4932.6   792.8  4952.8  780.87    4973  773.68  4982.9  771.86
  4985.5     770  4986.3   769.5    5021     770  5043.7  773.07  5053.1  776.16
  5063.9  777.56    5145  779.34  5185.2  780.61  5268.6  786.01  5301.7  786.47
  5326.6     786  5333.7  784.44  5344.9  785.63    5357   787.3  5444.9  791.93
  5474.1   792.4  5508.5  795.69  5579.3  798.63  5690.4  809.18  5824.2  814.23
#Mann= 8 ,-1 , 0
  4389.1     .07       0  4546.8     .12       0  4985.5     .05       0
    5021     .12       0    5145     .07       0  5301.7     .12       0
  5344.9     .07       0  5444.9     .12       0
Bank Sta=4985.5,5021
XS Rating Curve= 0 ,0
Exp/Cntr=0.3,0.1

Chan Stop Cuts=-1
Use User Specified Reach Order=0
Composite Channel Slope=5