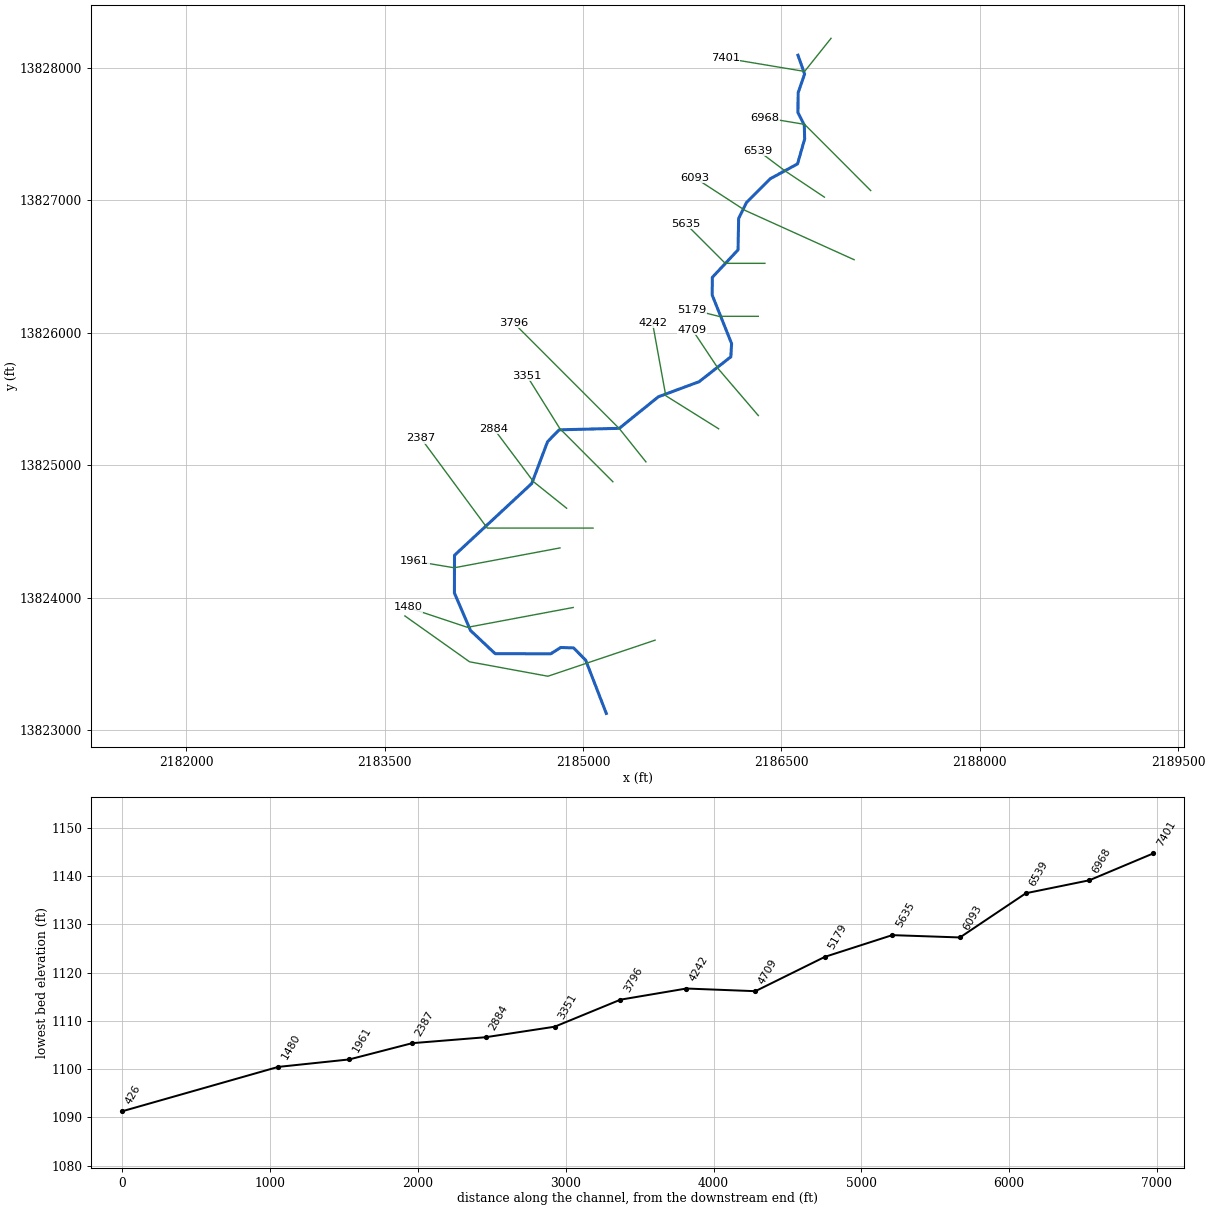
--- West Fork Tributary 10.prj (project) ---

Proj Title=West Fork Tributary 10 Base Level Engineering
Current Plan=p01
Default Exp/Contr=0.3,0.1
English Units
Geom File=g01
Flow File=f01
Plan File=p01
BEGIN DESCRIPTION:
West Fork Tributary 10
END DESCRIPTION:

--- West Fork Tributary 10.p01 (plan) ---

Plan Title=Multiple Run
Short Identifier=Multiple
Geom File=g01
Flow File=f01
Subcritical Flow
K Sum by GR= 0
Std Step Tol= 0.01
Critical Tol= 0.01
Num of Std Step Trials= 20
Max Error Tol= 0.3
Flow Tol Ratio= 0.001
Split Flow NTrial= 30
Split Flow Tol= 0.02
Split Flow Ratio= 0.02
Log Output Level= 0
Friction Slope Method= 1
Unsteady Friction Slope Method= 2
Unsteady Bridges Friction Slope Method= 1
Parabolic Critical Depth
Global Vel Dist=  1 , 1 , 1
Global Log Level= 0
CheckData=True
Encroach Param= -1, 0, 0, 0
BEGIN DESCRIPTION:
Multiple Run
END DESCRIPTION:

--- West Fork Tributary 10.f01 (steady flow) ---

Flow Title=Multiple
Number of Profiles=7
Profile Names=10-year,25-year,50-year,1pct_min,100-year,1pct_plu,500-year
River Rch & RM= West Fork Tribut,Reach-1,7401
     330     510     665     421     841    1678    1326
River Rch & RM= West Fork Tribut,Reach-1,6539
     844    1386    1884    1239    2473    4933    4215
River Rch & RM= West Fork Tribut,Reach-1,3796
    1106    1849    2545    1695    3381    6746    5906
Boundary for River Rch & Prof#=West Fork Tribut,Reach-1,1
Up Type=0
Dn Type=3
Dn Slope=0.005
Boundary for River Rch & Prof#=West Fork Tribut,Reach-1,2
Up Type=0
Dn Type=3
Dn Slope=0.005
Boundary for River Rch & Prof#=West Fork Tribut,Reach-1,3
Up Type=0
Dn Type=3
Dn Slope=0.005
Boundary for River Rch & Prof#=West Fork Tribut,Reach-1,4
Up Type=0
Dn Type=3
Dn Slope=0.005
Boundary for River Rch & Prof#=West Fork Tribut,Reach-1,5
Up Type=0
Dn Type=3
Dn Slope=0.005
Boundary for River Rch & Prof#=West Fork Tribut,Reach-1,6
Up Type=0
Dn Type=3
Dn Slope=0.005
Boundary for River Rch & Prof#=West Fork Tribut,Reach-1,7
Up Type=0
Dn Type=3
Dn Slope=0.005

--- West Fork Tributary 10.g01 (geometry) ---

Geom Title=Existing Conditions

River Reach=West Fork Tribut,Reach-1
Reach XY= 30
      2186625.00     13828097.28      2186675.12     13827954.91
      2186626.22     13827814.50      2186624.54     13827664.82
      2186672.75     13827569.06      2186675.50     13827464.83
      2186621.48     13827276.28      2186415.32     13827164.24
      2186235.76     13826984.68      2186176.20     13826864.50
      2186171.46     13826626.46      2185977.05     13826419.14
      2185976.37     13826284.67      2186122.84     13825919.02
      2186117.25     13825818.81      2185877.29     13825630.84
      2185568.95     13825516.84      2185273.54     13825278.54
      2184818.79     13825267.20      2184730.82     13825177.31
      2184611.38     13824861.78      2184027.17     13824319.56
      2184026.38     13824034.66      2184148.01     13823751.53
      2184334.59     13823576.20      2184754.97     13823575.07
      2184830.57     13823622.72      2184927.44     13823619.61
      2185019.17     13823527.31      2185175.00     13823125.00

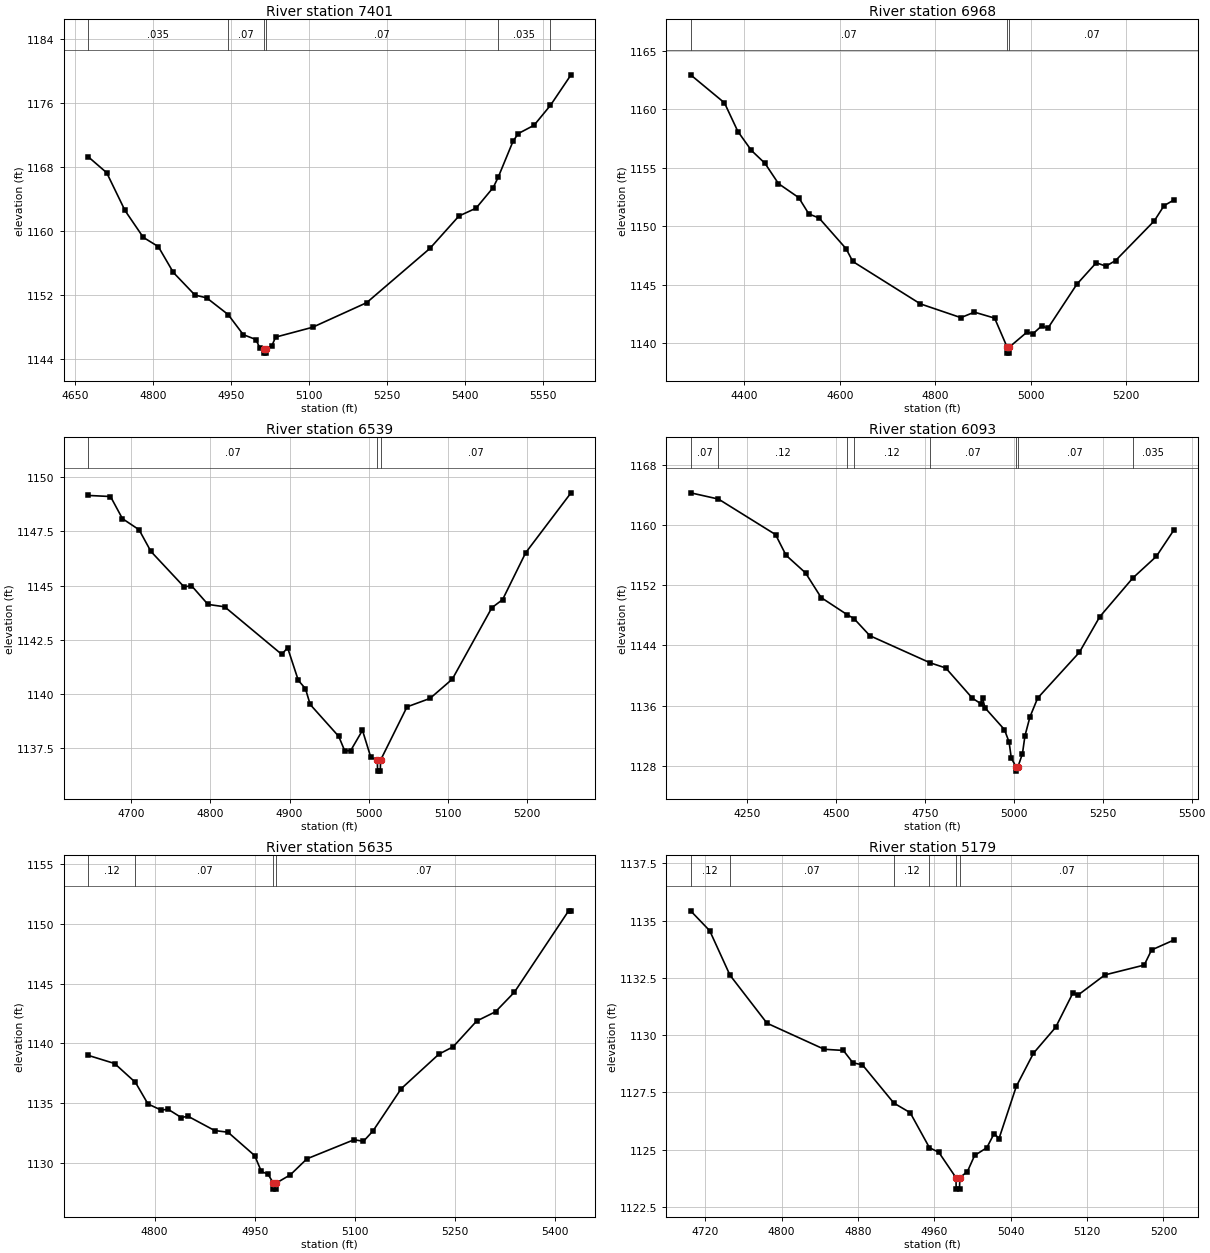
Type RM Length L Ch R = 1,7401,433,433,433
BEGIN DESCRIPTION:
West Fork Tributary 10 14.0
END DESCRIPTION:
XS GIS Cut Line= 3
      2186874.99     13828224.98      2186675.00     13827975.00
      2186075.01     13828075.00
#Sta/Elev= 30
  4675.0 1169.26  4711.0 1167.24  4746.2 1162.52  4781.4 1159.16  4810.2 1158.01
  4839.1 1154.78  4880.7 1151.95  4903.1 1151.61  4944.4 1149.52  4973.5 1147.01
  4997.7 1146.40  5005.3 1145.36  5013.4 1145.20  5013.7 1144.70  5017.2 1144.70
  5017.4 1145.20  5028.1 1145.57  5035.7 1146.70  5106.7 1147.93  5210.6 1151.00
  5332.2 1157.78  5388.0 1161.83  5420.9 1162.81  5453.9 1165.39  5463.5 1166.68
  5491.9 1171.16  5502.0 1172.13  5532.4 1173.17  5563.9 1175.66  5603.4 1179.47
#Mann=6,-1,0
  4675.0   0.035       0  4944.4    0.07       0  5013.4    0.05       0
  5017.4    0.07       0  5463.5   0.035       0  5563.9    0.12       0
Bank Sta=5013.4,5017.4
Exp/Cntr=0.3,0.1

Type RM Length L Ch R = 1,6968,429,429,429
BEGIN DESCRIPTION:
West Fork Tributary 10 13.0
END DESCRIPTION:
XS GIS Cut Line= 3
      2187175.03     13827074.97      2186675.00     13827575.00
      2186374.99     13827625.00
#Sta/Elev= 30
  4287.8 1162.97  4358.6 1160.57  4386.8 1158.11  4415.1 1156.49  4443.4 1155.39
  4471.7 1153.65  4514.1 1152.45  4535.3 1151.05  4556.5 1150.71  4613.1 1148.08
  4627.3 1146.98  4768.7 1143.35  4853.5 1142.17  4881.8 1142.64  4924.2 1142.13
  4950.5 1139.63  4950.8 1139.13  4954.3 1139.13  4954.5 1139.63  4991.4 1140.91
  5005.1 1140.81  5022.8 1141.47  5035.5 1141.25  5096.3 1145.03  5136.9 1146.87
  5157.2 1146.58  5177.4 1147.06  5258.5 1150.46  5278.8 1151.76  5299.1 1152.24
#Mann=3,-1,0
  4287.8    0.07       0  4950.5    0.05       0  4954.5    0.07       0
Bank Sta=4950.5,4954.5
Exp/Cntr=0.3,0.1

Type RM Length L Ch R = 1,6539,446,446,446
BEGIN DESCRIPTION:
West Fork Tributary 10 12.0
END DESCRIPTION:
XS GIS Cut Line= 3
      2186825.00     13827025.00      2186525.00     13827225.00
      2186324.96     13827375.03
#Sta/Elev= 30
  4645.2 1149.15  4673.7 1149.10  4688.8 1148.08  4709.8 1147.57  4724.8 1146.57
  4766.9 1144.93  4775.9 1145.00  4796.9 1144.13  4818.0 1144.02  4890.1 1141.83
  4897.6 1142.13  4911.1 1140.63  4920.1 1140.25  4926.1 1139.52  4962.2 1138.05
  4969.7 1137.39  4977.2 1137.39  4992.2 1138.33  5002.7 1137.09  5011.0 1136.95
  5011.3 1136.45  5014.8 1136.45  5015.0 1136.95  5048.5 1139.41  5077.6 1139.80
  5105.8 1140.69  5155.8 1143.98  5169.3 1144.35  5198.5 1146.51  5255.8 1149.27
#Mann=3,-1,0
  4645.2    0.07       0  5011.0    0.05       0  5015.0    0.07       0
Bank Sta=5011,5015
Exp/Cntr=0.3,0.1

Type RM Length L Ch R = 1,6093,458,458,458
BEGIN DESCRIPTION:
West Fork Tributary 10 11.0
END DESCRIPTION:
XS GIS Cut Line= 3
      2187049.55     13826552.48      2186225.00     13826925.00
      2185844.01     13827172.28
#Sta/Elev= 30
  4090.5 1164.28  4168.8 1163.45  4329.4 1158.73  4358.9 1155.98  4413.7 1153.64
  4457.6 1150.36  4530.4 1148.10  4550.1 1147.56  4594.7 1145.29  4764.1 1141.69
  4808.2 1141.00  4883.0 1136.99  4906.2 1136.27  4911.6 1137.03  4918.5 1135.71
  4973.3 1132.81  4986.5 1131.13  4992.6 1129.01  5006.8 1127.79  5007.1 1127.29
  5010.8 1127.79  5024.0 1129.62  5031.1 1132.00  5045.1 1134.50  5066.8 1137.00
  5184.1 1143.08  5241.5 1147.81  5334.5 1152.96  5400.6 1155.83  5449.5 1159.30
#Mann=8,-1,0
  4090.5    0.07       0  4168.8    0.12       0  4530.4    0.07       0
  4550.1    0.12       0  4764.1    0.07       0  5006.8    0.05       0
  5010.8    0.07       0  5334.5   0.035       0
Bank Sta=5006.8,5010.8
Exp/Cntr=0.3,0.1

Type RM Length L Ch R = 1,5635,456,456,456
BEGIN DESCRIPTION:
West Fork Tributary 10 10.0
END DESCRIPTION:
XS GIS Cut Line= 3
      2186374.99     13826525.00      2186075.00     13826525.00
      2185774.97     13826825.03
#Sta/Elev= 30
  4700.0 1138.99  4740.0 1138.30  4771.3 1136.71  4790.0 1134.91  4810.0 1134.39
  4820.0 1134.47  4840.0 1133.77  4850.0 1133.88  4890.0 1132.68  4910.0 1132.54
  4950.0 1130.58  4960.0 1129.25  4970.0 1129.02  4978.0 1128.27  4978.2 1127.77
  4981.7 1127.77  4982.0 1128.27  5003.5 1128.97  5028.3 1130.31  5099.0 1131.91
  5113.1 1131.78  5127.3 1132.64  5169.7 1136.19  5226.3 1139.09  5247.5 1139.70
  5282.8 1141.86  5311.1 1142.64  5339.4 1144.28  5420.7 1151.10  5424.3 1151.10
#Mann=4,-1,0
  4700.0    0.12       0  4771.3    0.07       0  4978.0    0.05       0
  4982.0    0.07       0
Bank Sta=4978,4982
Exp/Cntr=0.3,0.1

Type RM Length L Ch R = 1,5179,470,470,470
BEGIN DESCRIPTION:
West Fork Tributary 10 9.0
END DESCRIPTION:
XS GIS Cut Line= 3
      2186324.95     13826125.00      2186025.00     13826125.00
      2185825.01     13826175.00
#Sta/Elev= 30
  4704.7 1135.43  4724.7 1134.56  4745.9 1132.62  4784.7 1130.52  4844.7 1129.38
  4864.7 1129.33  4874.7 1128.79  4884.7 1128.70  4917.6 1127.03  4934.7 1126.61
  4954.9 1125.08  4964.7 1124.88  4982.7 1123.77  4982.9 1123.27  4986.4 1123.27
  4986.7 1123.77  4994.7 1124.04  5002.2 1124.74  5015.0 1125.08  5022.7 1125.70
  5027.8 1125.48  5045.9 1127.76  5063.9 1129.21  5087.1 1130.34  5105.2 1131.84
  5110.3 1131.74  5138.7 1132.63  5179.9 1133.06  5187.6 1133.72  5210.8 1134.15
#Mann=6,-1,0
  4704.7    0.12       0  4745.9    0.07       0  4917.6    0.12       0
  4954.9    0.07       0  4982.7    0.05       0  4986.7    0.07       0
Bank Sta=4982.7,4986.7
Exp/Cntr=0.3,0.1

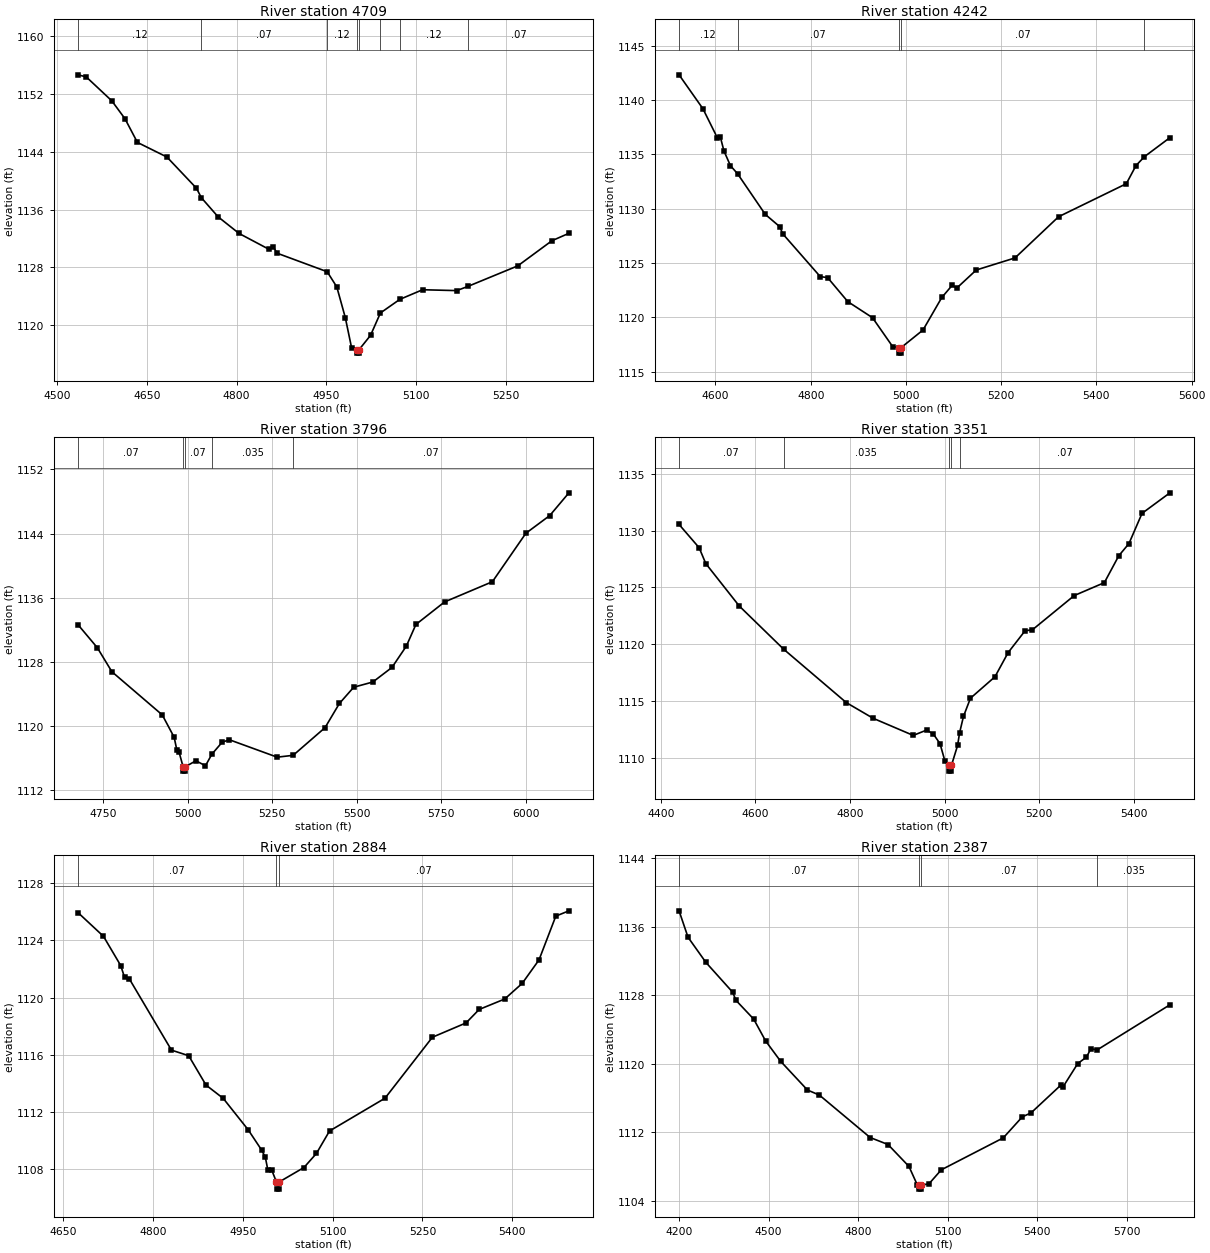
Type RM Length L Ch R = 1,4709,467,467,467
BEGIN DESCRIPTION:
West Fork Tributary 10 8.0
END DESCRIPTION:
XS GIS Cut Line= 3
      2186324.99     13825375.01      2186025.00     13825725.00
      2185825.01     13826024.99
#Sta/Elev= 30
  4534.6 1154.62  4548.3 1154.33  4591.1 1151.02  4613.1 1148.55  4633.9 1145.28
  4683.3 1143.26  4732.7 1138.95  4740.9 1137.64  4768.9 1135.00  4804.0 1132.70
  4853.4 1130.54  4861.1 1130.87  4867.7 1129.97  4951.5 1127.41  4967.6 1125.31
  4981.8 1121.08  4992.3 1116.92  5001.0 1116.66  5001.3 1116.16  5004.9 1116.16
  5005.1 1116.66  5024.1 1118.62  5040.6 1121.71  5073.1 1123.59  5111.2 1124.92
  5168.3 1124.80  5187.0 1125.38  5270.5 1128.22  5327.6 1131.69  5356.1 1132.72
#Mann=8,-1,0
  4534.6    0.12       0  4740.9    0.07       0  4951.5    0.12       0
  5001.0    0.05       0  5005.1    0.12       0  5040.6    0.07       0
  5073.1    0.12       0  5187.0    0.07       0
Bank Sta=5001,5005.1
Exp/Cntr=0.3,0.1

Type RM Length L Ch R = 1,4242,446,446,446
BEGIN DESCRIPTION:
West Fork Tributary 10 7.0
END DESCRIPTION:
XS GIS Cut Line= 3
      2186024.97     13825275.02      2185625.00     13825525.00
      2185525.00     13826075.02
#Sta/Elev= 30
  4523.6 1142.32  4573.7 1139.20  4604.3 1136.50  4610.2 1136.61  4617.9 1135.31
  4631.5 1133.96  4646.4 1133.22  4704.6 1129.48  4735.2 1128.34  4741.1 1127.70
  4820.1 1123.75  4835.5 1123.66  4877.9 1121.45  4929.8 1119.97  4972.3 1117.30
  4985.5 1117.21  4985.8 1116.71  4989.4 1116.71  4989.7 1117.21  5035.9 1118.84
  5075.3 1121.83  5096.9 1122.94  5107.1 1122.71  5147.7 1124.36  5229.0 1125.47
  5320.5 1129.26  5462.8 1132.30  5483.1 1133.97  5500.9 1134.79  5554.3 1136.54
#Mann=5,-1,0
  4523.6    0.12       0  4646.4    0.07       0  4985.5    0.05       0
  4989.7    0.07       0  5500.9    0.12       0
Bank Sta=4985.5,4989.7
Exp/Cntr=0.3,0.1

Type RM Length L Ch R = 1,3796,445,445,445
BEGIN DESCRIPTION:
West Fork Tributary 10 6.0
END DESCRIPTION:
XS GIS Cut Line= 3
      2185474.99     13825025.01      2185275.00     13825275.00
      2184475.01     13826074.99
#Sta/Elev= 30
  4675.6 1132.64  4732.4 1129.79  4775.6 1126.79  4924.5 1121.41  4959.7 1118.62
  4967.7 1117.02  4974.1 1116.79  4986.4 1114.90  4986.7 1114.40  4990.4 1114.40
  4990.7 1114.90  5024.0 1115.69  5052.3 1115.07  5071.4 1116.52  5101.8 1118.01
  5123.0 1118.31  5264.4 1116.14  5311.6 1116.37  5405.9 1119.82  5448.3 1122.83
  5490.7 1124.86  5547.3 1125.51  5603.9 1127.33  5646.3 1129.98  5674.6 1132.68
  5759.4 1135.49  5900.8 1138.01  5999.8 1144.05  6070.5 1146.26  6127.1 1149.09
#Mann=5,-1,0
  4675.6    0.07       0  4986.4    0.05       0  4990.7    0.07       0
  5071.4   0.035       0  5311.6    0.07       0
Bank Sta=4986.4,4990.7
Exp/Cntr=0.3,0.1

Type RM Length L Ch R = 1,3351,467,467,467
BEGIN DESCRIPTION:
West Fork Tributary 10 5.0
END DESCRIPTION:
XS GIS Cut Line= 3
      2185224.97     13824875.03      2184825.00     13825275.00
      2184575.02     13825674.96
#Sta/Elev= 30
  4438.6 1130.55  4481.0 1128.50  4495.1 1127.10  4565.8 1123.36  4659.4 1119.56
  4792.1 1114.84  4848.7 1113.46  4933.5 1111.95  4961.8 1112.42  4976.0 1112.07
  4990.1 1111.22  5000.7 1109.65  5009.7 1109.30  5010.0 1108.80  5013.9 1108.80
  5014.2 1109.30  5027.2 1111.06  5031.4 1112.17  5039.6 1113.62  5054.4 1115.23
  5106.2 1117.12  5134.0 1119.25  5169.9 1121.18  5185.3 1121.26  5273.7 1124.28
  5337.4 1125.42  5368.0 1127.80  5389.3 1128.86  5417.0 1131.53  5475.9 1133.34
#Mann=5,-1,0
  4438.6    0.07       0  4659.4   0.035       0  5009.7   0.035       0
  5014.2   0.035       0  5031.4    0.07       0
Bank Sta=5009.7,5014.2
Exp/Cntr=0.3,0.1

Type RM Length L Ch R = 1,2884,497,497,497
BEGIN DESCRIPTION:
West Fork Tributary 10 4.0
END DESCRIPTION:
XS GIS Cut Line= 3
      2184874.96     13824675.03      2184625.00     13824875.00
      2184325.01     13825274.99
#Sta/Elev= 30
  4674.7 1125.93  4717.1 1124.28  4745.9 1122.24  4752.3 1121.42  4760.3 1121.31
  4830.7 1116.33  4859.5 1115.94  4888.4 1113.89  4917.2 1112.96  4958.8 1110.77
  4981.2 1109.36  4987.6 1108.84  4991.6 1107.99  4997.9 1107.99  5006.1 1107.12
  5006.4 1106.62  5010.3 1106.62  5010.7 1107.12  5052.1 1108.13  5072.9 1109.11
  5094.8 1110.68  5187.5 1112.97  5266.7 1117.23  5322.9 1118.23  5344.8 1119.17
  5387.5 1119.90  5416.7 1120.99  5444.8 1122.63  5472.9 1125.69  5494.8 1126.06
#Mann=3,-1,0
  4674.7    0.07       0  5006.1    0.05       0  5010.7    0.07       0
Bank Sta=5006.1,5010.7
Exp/Cntr=0.3,0.1

Type RM Length L Ch R = 1,2387,426,426,426
BEGIN DESCRIPTION:
West Fork Tributary 10 3.0
END DESCRIPTION:
XS GIS Cut Line= 3
      2185075.01     13824525.00      2184275.00     13824525.00
      2183773.31     13825203.83
#Sta/Elev= 30
  4200.3 1137.85  4230.3 1134.77  4290.3 1131.83  4380.3 1128.34  4390.3 1127.43
  4450.3 1125.22  4490.3 1122.67  4540.3 1120.31  4630.3 1116.95  4670.3 1116.36
  4840.3 1111.41  4900.3 1110.59  4970.3 1108.04  4997.8 1105.92  5005.3 1105.89
  5005.6 1105.39  5009.6 1105.39  5009.9 1105.89  5036.9 1105.99  5078.6 1107.64
  5286.3 1111.37  5350.0 1113.82  5379.2 1114.28  5479.4 1117.53  5485.6 1117.27
  5535.8 1120.04  5565.0 1120.79  5579.6 1121.77  5600.9 1121.63  5844.4 1126.89
#Mann=4,-1,0
  4200.3    0.07       0  5005.3    0.05       0  5009.9    0.07       0
  5600.9   0.035       0
Bank Sta=5005.3,5009.9
Exp/Cntr=0.3,0.1

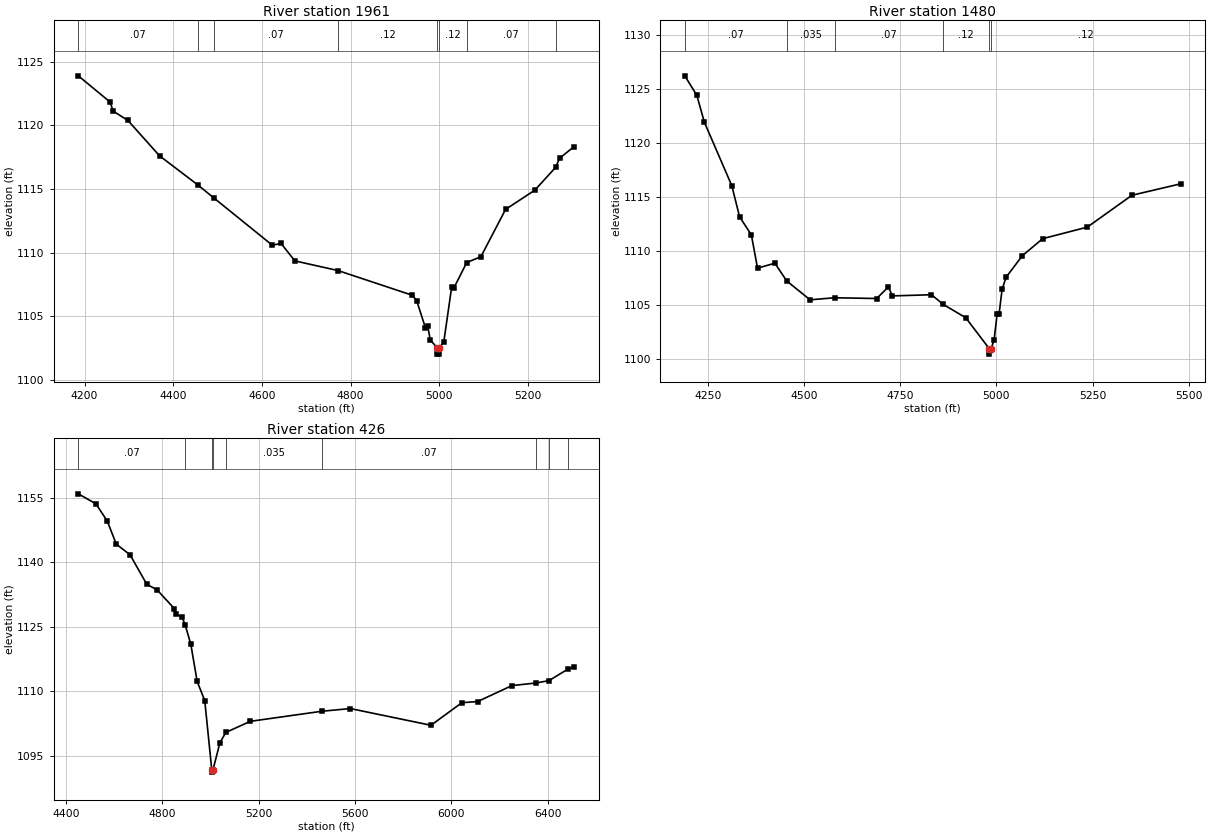
Type RM Length L Ch R = 1,1961,481,481,481
BEGIN DESCRIPTION:
West Fork Tributary 10 2.0
END DESCRIPTION:
XS GIS Cut Line= 3
      2184824.96     13824374.99      2184025.00     13824225.00
      2183725.04     13824274.99
#Sta/Elev= 30
  4186.0 1123.90  4257.2 1121.85  4264.8 1121.12  4297.9 1120.39  4369.1 1117.61
  4454.8 1115.34  4492.6 1114.27  4623.5 1110.58  4642.9 1110.73  4674.3 1109.35
  4771.5 1108.59  4938.9 1106.65  4949.0 1106.22  4968.5 1104.10  4973.6 1104.26
  4979.5 1103.14  4995.0 1102.52  4995.4 1102.02  4999.4 1102.02  4999.7 1102.52
  5010.0 1102.96  5027.8 1107.30  5032.8 1107.22  5061.7 1109.22  5093.7 1109.68
  5149.4 1113.40  5215.3 1114.91  5262.4 1116.71  5271.1 1117.42  5304.0 1118.34
#Mann=8,-1,0
  4186.0    0.07       0  4454.8   0.035       0  4492.6    0.07       0
  4771.5    0.12       0  4995.0    0.05       0  4999.7    0.12       0
  5061.7    0.07       0  5262.4    0.12       0
Bank Sta=4995,4999.7
Exp/Cntr=0.3,0.1

Type RM Length L Ch R = 1,1480,1054,1054,1054
BEGIN DESCRIPTION:
West Fork Tributary 10 1.0
END DESCRIPTION:
XS GIS Cut Line= 3
      2184924.97     13823924.99      2184125.00     13823775.00
      2183674.96     13823925.01
#Sta/Elev= 30
  4190.5 1126.24  4221.8 1124.43  4241.3 1121.95  4312.6 1116.07  4332.9 1113.18
  4363.4 1111.52  4379.5 1108.43  4424.5 1108.89  4455.5 1107.24  4516.0 1105.50
  4580.0 1105.69  4689.0 1105.62  4719.5 1106.69  4729.7 1105.86  4831.5 1105.97
  4862.2 1105.07  4920.5 1103.84  4981.7 1100.97  4982.1 1100.47  4986.4 1100.97
  4994.2 1101.79  5001.9 1104.17  5007.0 1104.17  5015.0 1106.48  5025.5 1107.60
  5067.7 1109.59  5120.4 1111.16  5236.3 1112.23  5352.3 1115.18  5478.8 1116.24
#Mann=6,-1,0
  4190.5    0.07       0  4455.5   0.035       0  4580.0    0.07       0
  4862.2    0.12       0  4981.7    0.05       0  4986.4    0.12       0
Bank Sta=4981.7,4986.4
Exp/Cntr=0.3,0.1

Type RM Length L Ch R = 1,426,0,0,0
BEGIN DESCRIPTION:
H21697
END DESCRIPTION:
XS GIS Cut Line= 4
      2185544.24     13823678.07      2184733.72     13823405.63
      2184141.13     13823514.61      2183652.10     13823861.01
#Sta/Elev= 30
  4452.0 1155.86  4525.0 1153.54  4572.0 1149.54  4609.4 1144.20  4666.6 1141.71
  4736.0 1134.87  4778.2 1133.60  4850.4 1129.23  4855.7 1127.96  4881.9 1127.33
  4896.0 1125.31  4918.7 1120.94  4944.9 1112.34  4976.5 1107.87  5005.6 1091.79
  5005.9 1091.29  5010.4 1091.79  5039.5 1098.14  5064.0 1100.50  5165.6 1103.08
  5461.9 1105.41  5580.3 1106.04  5915.0 1102.16  6042.9 1107.40  6108.2 1107.66
  6250.9 1111.37  6350.8 1111.97  6404.4 1112.52  6485.3 1115.27  6508.9 1115.65
#Mann=9,-1,0
  4452.0    0.07       0  4896.0    0.12       0  5005.6    0.05       0
  5010.4    0.12       0  5064.0   0.035       0  5461.9    0.07       0
  6350.8   0.035       0  6404.4    0.12       0  6485.3   0.035       0
Bank Sta=5005.6,5010.4
Exp/Cntr=0.3,0.1

Chan Stop Cuts=-1