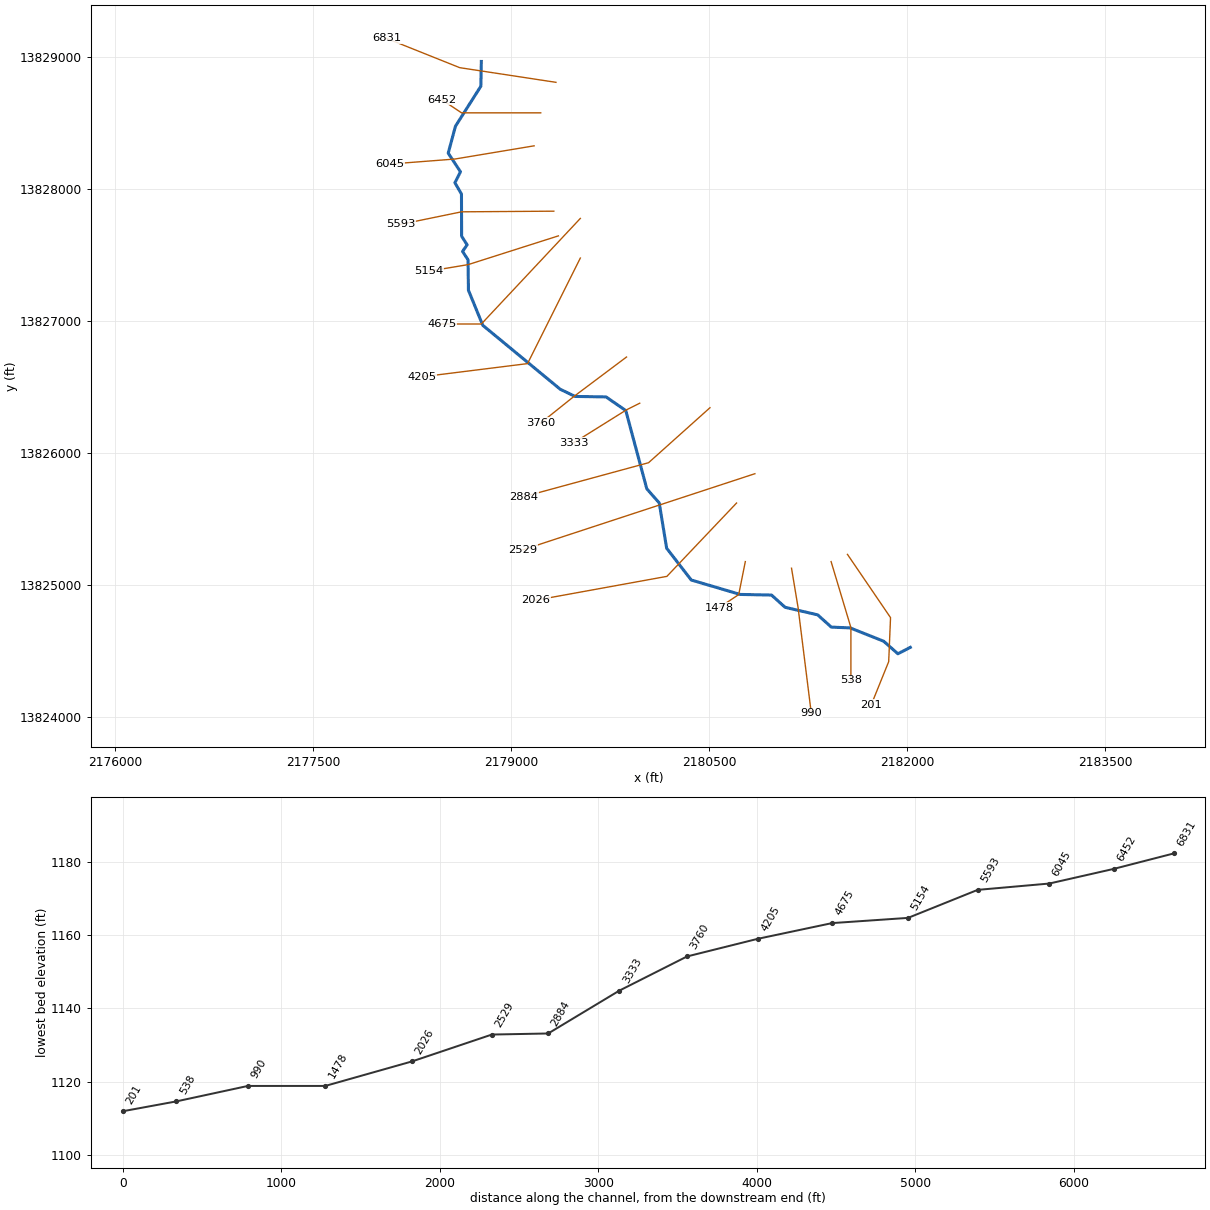
--- West Fork Tributary 12.prj (project) ---

Proj Title=West Fork Tributary 12 Base Level Engineering
Current Plan=p01
Default Exp/Contr=0.3,0.1
English Units
Geom File=g01
Flow File=f01
Plan File=p01
BEGIN DESCRIPTION:
West Fork Tributary 12
END DESCRIPTION:

--- West Fork Tributary 12.p01 (plan) ---

Plan Title=Multiple Run
Short Identifier=Multiple
Geom File=g01
Flow File=f01
Subcritical Flow
K Sum by GR= 0
Std Step Tol= 0.01
Critical Tol= 0.01
Num of Std Step Trials= 20
Max Error Tol= 0.3
Flow Tol Ratio= 0.001
Split Flow NTrial= 30
Split Flow Tol= 0.02
Split Flow Ratio= 0.02
Log Output Level= 0
Friction Slope Method= 1
Unsteady Friction Slope Method= 2
Unsteady Bridges Friction Slope Method= 1
Parabolic Critical Depth
Global Vel Dist=  1 , 1 , 1
Global Log Level= 0
CheckData=True
Encroach Param= -1, 0, 0, 0
BEGIN DESCRIPTION:
Multiple Run
END DESCRIPTION:

--- West Fork Tributary 12.f01 (steady flow) ---

Flow Title=Multiple
Number of Profiles=7
Profile Names=10-year,25-year,50-year,1pct_min,100-year,1pct_plu,500-year
River Rch & RM= West Fork Tribut,Reach-1,6831
     964    1612    2221    1483    2959    5903    5192
River Rch & RM= West Fork Tribut,Reach-1,5154
    1210    2040    2824    1892    3774    7531    6672
River Rch & RM= West Fork Tribut,Reach-1,201
    1447    2465    3435    2315    4618    9214    8265
Boundary for River Rch & Prof#=West Fork Tribut,Reach-1,1
Up Type=0
Dn Type=3
Dn Slope=0.005
Boundary for River Rch & Prof#=West Fork Tribut,Reach-1,2
Up Type=0
Dn Type=3
Dn Slope=0.005
Boundary for River Rch & Prof#=West Fork Tribut,Reach-1,3
Up Type=0
Dn Type=3
Dn Slope=0.005
Boundary for River Rch & Prof#=West Fork Tribut,Reach-1,4
Up Type=0
Dn Type=3
Dn Slope=0.005
Boundary for River Rch & Prof#=West Fork Tribut,Reach-1,5
Up Type=0
Dn Type=3
Dn Slope=0.005
Boundary for River Rch & Prof#=West Fork Tribut,Reach-1,6
Up Type=0
Dn Type=3
Dn Slope=0.005
Boundary for River Rch & Prof#=West Fork Tribut,Reach-1,7
Up Type=0
Dn Type=3
Dn Slope=0.005

--- West Fork Tributary 12.g01 (geometry) ---

Geom Title=Existing Conditions

River Reach=West Fork Tribut,Reach-1
Reach XY= 30
      2178775.00     13828964.26      2178771.27     13828776.52
      2178578.83     13828473.42      2178524.08     13828269.61
      2178616.94     13828128.34      2178574.79     13828045.21
      2178624.46     13827959.79      2178625.65     13827640.16
      2178667.21     13827574.90      2178632.79     13827525.10
      2178674.18     13827461.14      2178677.26     13827230.94
      2178785.76     13826965.32      2179372.71     13826480.84
      2179485.50     13826426.20      2179719.55     13826422.82
      2179869.41     13826319.39      2180028.62     13825726.50
      2180122.93     13825619.14      2180178.82     13825276.58
      2180365.21     13825035.52      2180735.50     13824926.22
      2180973.53     13824921.45      2181076.50     13824828.62
      2181323.50     13824771.38      2181426.47     13824678.56
      2181569.48     13824672.64      2181823.50     13824571.38
      2181930.97     13824476.55      2182025.00     13824525.00

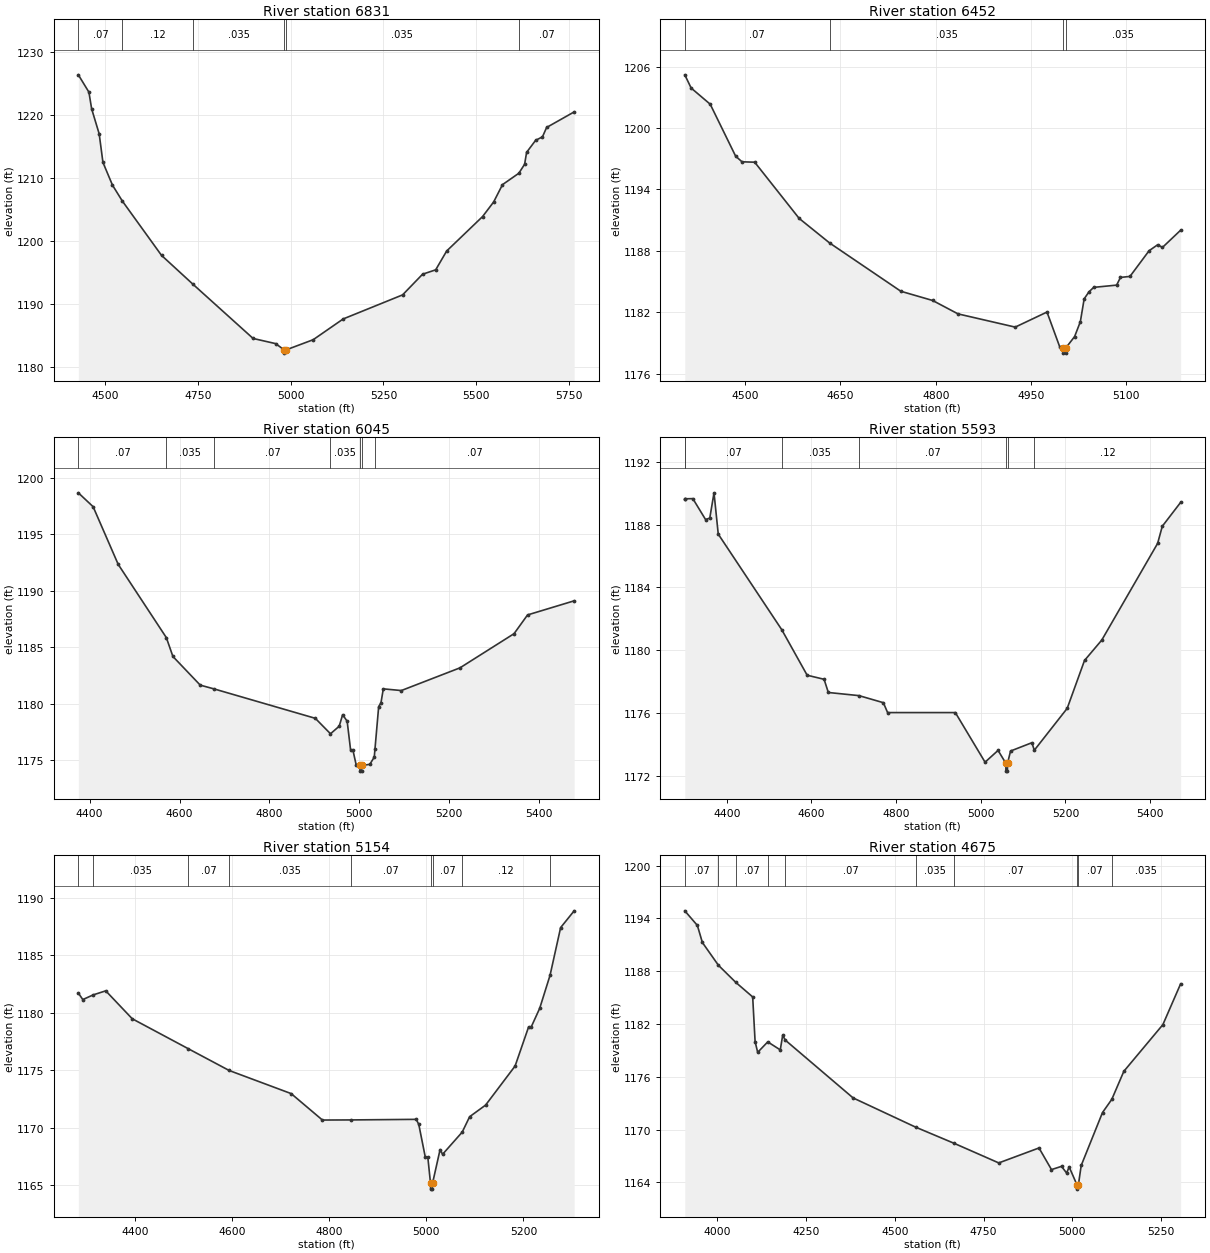
Type RM Length L Ch R = 1,6831,379,379,379
BEGIN DESCRIPTION:
H21702
END DESCRIPTION:
XS GIS Cut Line= 3
      2179340.53     13828806.07      2178611.35     13828917.19
      2178055.75     13829139.43
#Sta/Elev= 30
  4428.0 1226.44  4456.5 1223.69  4463.9 1221.03  4484.2 1217.06  4494.3 1212.53
  4520.0 1208.92  4546.5 1206.40  4652.1 1197.77  4736.7 1193.19  4898.9 1184.57
  4959.6 1183.75  4983.0 1182.74  4983.3 1182.24  4987.0 1182.74  5060.8 1184.37
  5141.7 1187.67  5301.7 1191.49  5355.5 1194.77  5390.9 1195.47  5420.5 1198.46
  5517.1 1203.92  5547.1 1206.25  5570.9 1209.00  5615.0 1210.81  5630.5 1212.24
  5635.9 1214.13  5660.2 1216.04  5678.6 1216.59  5689.8 1218.08  5764.0 1220.55
#Mann=6,-1,0
  4428.0    0.07       0  4546.5    0.12       0  4736.7   0.035       0
  4983.0   0.035       0  4987.0   0.035       0  5615.0    0.07       0
Bank Sta=4983,4987
Exp/Cntr=0.3,0.1

Type RM Length L Ch R = 1,6452,407,407,407
BEGIN DESCRIPTION:
West Fork Tributary 12 14.0
END DESCRIPTION:
XS GIS Cut Line= 3
      2179224.98     13828575.00      2178625.00     13828575.00
      2178474.96     13828675.03
#Sta/Elev= 30
  4405.0 1205.19  4415.0 1203.90  4445.0 1202.32  4485.0 1197.25  4495.0 1196.70
  4515.0 1196.66  4585.0 1191.17  4633.0 1188.77  4745.0 1184.06  4795.0 1183.16
  4835.0 1181.85  4925.0 1180.56  4975.0 1182.03  4995.0 1178.64  5000.5 1178.52
  5000.7 1178.02  5004.2 1178.02  5004.5 1178.52  5018.5 1179.64  5027.5 1181.09
  5033.5 1183.32  5041.0 1184.00  5048.5 1184.44  5084.6 1184.66  5090.6 1185.41
  5105.6 1185.51  5135.7 1188.02  5149.2 1188.60  5156.7 1188.34  5185.3 1190.02
#Mann=4,-1,0
  4405.0    0.07       0  4633.0   0.035       0  5000.5   0.035       0
  5004.5   0.035       0
Bank Sta=5000.5,5004.5
Exp/Cntr=0.3,0.1

Type RM Length L Ch R = 1,6045,452,452,452
BEGIN DESCRIPTION:
West Fork Tributary 12 13.0
END DESCRIPTION:
XS GIS Cut Line= 3
      2179175.00     13828325.00      2178575.00     13828225.00
      2178081.66     13828186.71
#Sta/Elev= 30
  4374.8 1198.68  4407.7 1197.45  4463.5 1192.34  4570.6 1185.85  4585.2 1184.18
  4646.0 1181.64  4677.2 1181.30  4902.0 1178.70  4935.8 1177.33  4955.2 1178.00
  4962.8 1179.02  4972.9 1178.44  4980.5 1175.90  4985.6 1175.90  4993.1 1174.54
  5001.1 1174.52  5001.4 1174.02  5004.9 1174.02  5005.1 1174.52  5023.2 1174.62
  5033.2 1175.26  5034.7 1175.95  5043.0 1179.74  5048.0 1180.05  5053.3 1181.31
  5093.4 1181.16  5223.8 1183.17  5344.2 1186.20  5374.2 1187.86  5477.9 1189.11
#Mann=7,-1,0
  4374.8    0.07       0  4570.6   0.035       0  4677.2    0.07       0
  4935.8   0.035       0  5001.1   0.035       0  5005.1   0.035       0
  5034.7    0.07       0
Bank Sta=5001.1,5005.1
Exp/Cntr=0.3,0.1

Type RM Length L Ch R = 1,5593,439,439,439
BEGIN DESCRIPTION:
West Fork Tributary 12 12.0
END DESCRIPTION:
XS GIS Cut Line= 3
      2179324.01     13827829.90      2178625.00     13827825.00
      2178162.61     13827729.91
#Sta/Elev= 30
  4301.0 1189.64  4301.5 1189.64  4320.0 1189.65  4350.0 1188.32  4360.0 1188.41
  4370.0 1190.02  4380.0 1187.39  4530.0 1181.30  4590.0 1178.40  4630.0 1178.14
  4640.0 1177.30  4712.4 1177.10  4770.0 1176.65  4780.0 1176.02  4940.0 1176.02
  5010.2 1172.86  5040.9 1173.61  5059.3 1172.79  5059.5 1172.29  5063.0 1172.29
  5063.3 1172.79  5070.4 1173.57  5120.8 1174.10  5126.5 1173.62  5204.2 1176.29
  5245.1 1179.34  5285.9 1180.64  5417.8 1186.80  5428.8 1187.89  5472.1 1189.41
#Mann=7,-1,0
  4301.0   0.035       0  4301.5    0.07       0  4530.0   0.035       0
  4712.4    0.07       0  5059.3    0.05       0  5063.3    0.07       0
  5126.5    0.12       0
Bank Sta=5059.3,5063.3
Exp/Cntr=0.3,0.1

Type RM Length L Ch R = 1,5154,479,479,479
BEGIN DESCRIPTION:
West Fork Tributary 12 11.0
END DESCRIPTION:
XS GIS Cut Line= 3
      2179358.82     13827642.80      2178675.00     13827425.00
      2178375.00     13827375.00
#Sta/Elev= 30
  4282.7 1181.71  4291.9 1181.14  4313.5 1181.55  4339.2 1181.90  4393.8 1179.47
  4508.6 1176.88  4593.6 1174.97  4721.3 1172.96  4785.7 1170.66  4845.4 1170.67
  4979.0 1170.72  4984.3 1170.28  4997.7 1167.44  5002.9 1167.44  5008.5 1165.15
  5008.7 1164.65  5012.3 1164.65  5012.6 1165.15  5028.2 1168.09  5033.3 1167.68
  5073.8 1169.61  5089.1 1170.95  5122.0 1171.96  5182.8 1175.36  5210.7 1178.77
  5215.8 1178.74  5233.5 1180.38  5254.8 1183.25  5276.6 1187.40  5304.5 1188.86
#Mann=9,-1,0
  4282.7    0.07       0  4313.5   0.035       0  4508.6    0.07       0
  4593.6   0.035       0  4845.4    0.07       0  5008.5    0.05       0
  5012.6    0.07       0  5073.8    0.12       0  5254.8    0.07       0
Bank Sta=5008.5,5012.6
Exp/Cntr=0.3,0.1

Type RM Length L Ch R = 1,4675,470,470,470
BEGIN DESCRIPTION:
West Fork Tributary 12 10.0
END DESCRIPTION:
XS GIS Cut Line= 3
      2179524.98     13827774.97      2178775.00     13826975.00
      2178475.05     13826975.00
#Sta/Elev= 30
  3908.3 1194.87  3943.7 1193.21  3957.8 1191.27  4003.0 1188.68  4051.8 1186.74
  4099.5 1185.08  4106.3 1180.00  4113.6 1178.78  4141.9 1179.97  4177.2 1179.06
  4184.0 1180.72  4191.3 1180.17  4382.3 1173.60  4558.3 1170.28  4667.9 1168.42
  4792.6 1166.21  4905.9 1167.91  4941.1 1165.45  4969.4 1165.82  4983.6 1165.06
  4990.9 1165.75  5012.7 1163.73  5013.0 1163.23  5016.9 1163.73  5024.8 1165.92
  5084.8 1171.94  5111.0 1173.44  5144.8 1176.62  5254.8 1181.93  5304.8 1186.57
#Mann=10,-1,0
  3908.3    0.07       0  4003.0   0.035       0  4051.8    0.07       0
  4141.9   0.035       0  4191.3    0.07       0  4558.3   0.035       0
  4667.9    0.07       0  5012.7    0.05       0  5016.9    0.07       0
  5111.0   0.035       0
Bank Sta=5012.7,5016.9
Exp/Cntr=0.3,0.1

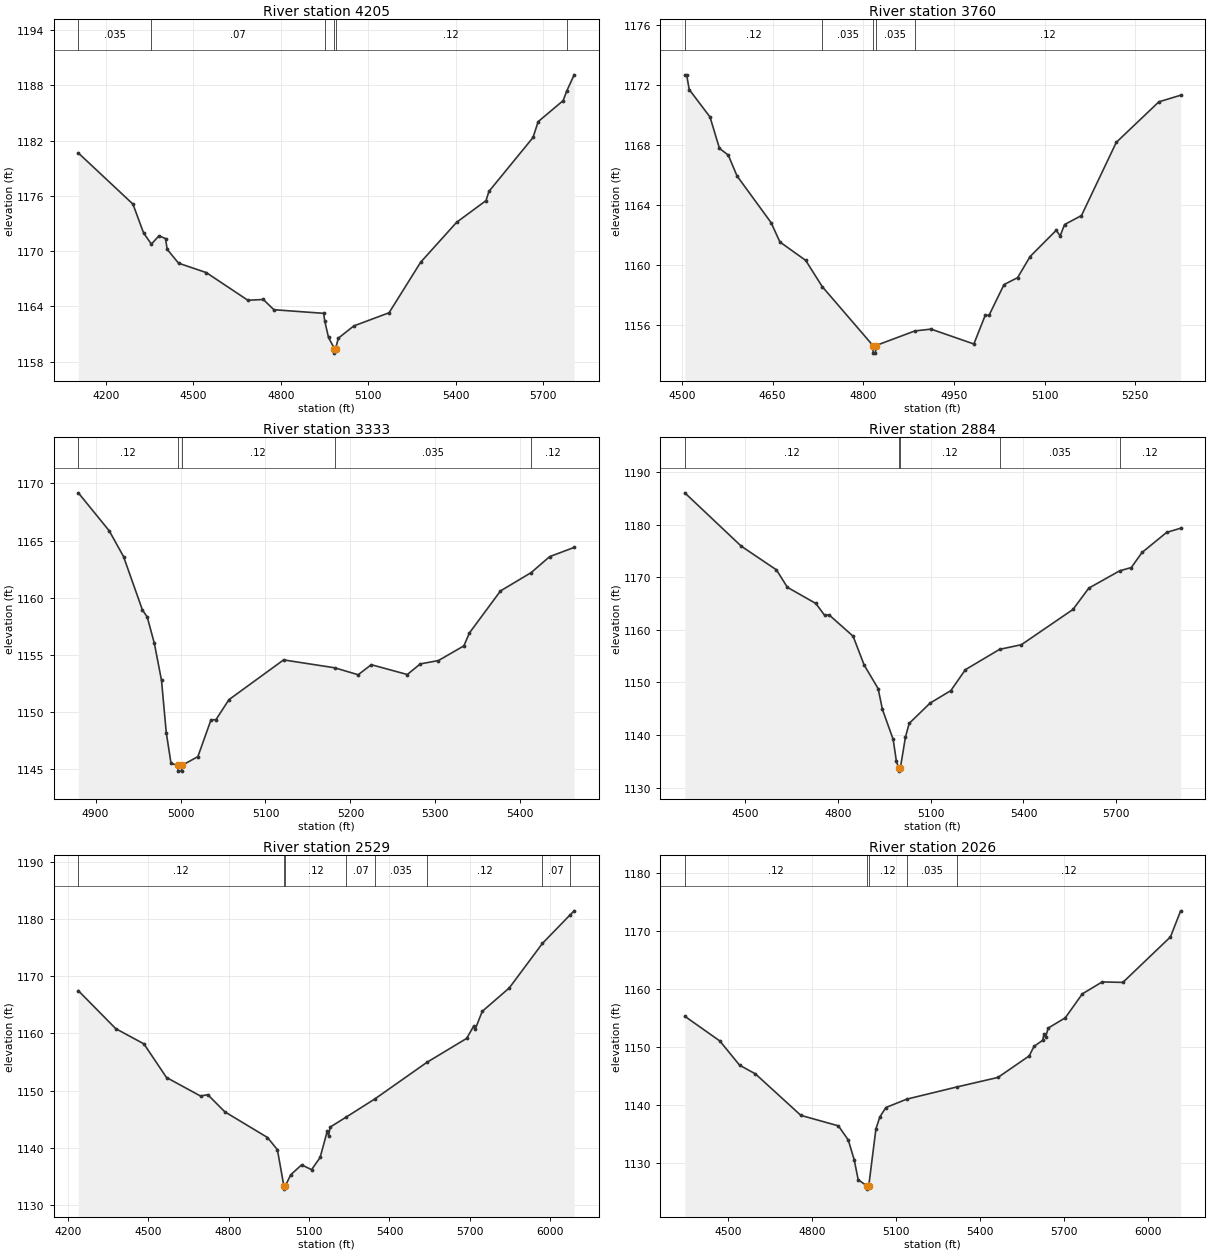
Type RM Length L Ch R = 1,4205,445,445,445
BEGIN DESCRIPTION:
West Fork Tributary 12 9.0
END DESCRIPTION:
XS GIS Cut Line= 3
      2179525.01     13827475.02      2179125.00     13826675.00
      2178324.98     13826575.00
#Sta/Elev= 30
  4105.5 1180.65  4292.8 1175.10  4329.1 1171.99  4355.9 1170.76  4382.2 1171.66
  4404.6 1171.36  4410.2 1170.20  4449.3 1168.69  4544.4 1167.67  4686.9 1164.67
  4740.0 1164.75  4776.3 1163.64  4946.8 1163.25  4950.9 1162.39  4963.6 1160.63
  4983.8 1159.43  4984.1 1158.93  4988.1 1159.43  4997.2 1160.55  5050.3 1161.88
  5171.3 1163.31  5279.6 1168.79  5403.1 1173.13  5503.8 1175.48  5513.9 1176.48
  5665.1 1182.33  5682.7 1184.05  5768.4 1186.33  5781.1 1187.40  5806.2 1189.13
#Mann=6,-1,0
  4105.5   0.035       0  4355.9    0.07       0  4950.9    0.12       0
  4983.8    0.05       0  4988.1    0.12       0  5781.1    0.07       0
Bank Sta=4983.8,4988.1
Exp/Cntr=0.3,0.1

Type RM Length L Ch R = 1,3760,427,427,427
BEGIN DESCRIPTION:
West Fork Tributary 12 8.0
END DESCRIPTION:
XS GIS Cut Line= 3
      2179874.99     13826724.99      2179475.00     13826425.00
      2179225.04     13826225.03
#Sta/Elev= 30
  4504.9 1172.68  4508.0 1172.68  4512.2 1171.70  4546.6 1169.87  4562.2 1167.78
  4576.8 1167.33  4591.3 1165.94  4647.6 1162.83  4662.2 1161.54  4704.9 1160.31
  4732.1 1158.57  4816.2 1154.63  4816.5 1154.13  4820.3 1154.13  4820.6 1154.63
  4885.5 1155.61  4912.2 1155.73  4983.0 1154.74  5001.8 1156.65  5008.1 1156.65
  5032.9 1158.70  5055.3 1159.16  5076.1 1160.57  5119.3 1162.32  5125.7 1161.94
  5133.0 1162.70  5161.0 1163.30  5218.6 1168.18  5289.0 1170.88  5325.0 1171.32
#Mann=5,-1,0
  4504.9    0.12       0  4732.1   0.035       0  4816.2    0.05       0
  4820.6   0.035       0  4885.5    0.12       0
Bank Sta=4816.2,4820.6
Exp/Cntr=0.3,0.1

Type RM Length L Ch R = 1,3333,449,449,449
BEGIN DESCRIPTION:
West Fork Tributary 12 7.0
END DESCRIPTION:
XS GIS Cut Line= 3
      2179975.04     13826375.02      2179875.00     13826325.00
      2179474.96     13826074.97
#Sta/Elev= 30
  4879.7 1169.18  4916.1 1165.85  4932.9 1163.60  4955.2 1158.91  4960.8 1158.31
  4969.2 1155.99  4977.6 1152.76  4983.2 1148.18  4988.8 1145.49  4996.9 1145.31
  4997.2 1144.81  5001.2 1144.81  5001.6 1145.31  5020.4 1146.08  5035.8 1149.29
  5041.7 1149.32  5057.0 1151.07  5121.3 1154.55  5181.4 1153.86  5209.1 1153.25
  5224.5 1154.13  5266.9 1153.27  5282.2 1154.20  5303.5 1154.49  5333.5 1155.78
  5340.0 1156.91  5376.6 1160.59  5412.8 1162.20  5434.4 1163.59  5463.3 1164.40
#Mann=5,-1,0
  4879.7    0.12       0  4996.9    0.05       0  5001.6    0.12       0
  5181.4   0.035       0  5412.8    0.12       0
Bank Sta=4996.9,5001.6
Exp/Cntr=0.3,0.1

Type RM Length L Ch R = 1,2884,355,355,355
BEGIN DESCRIPTION:
H21701
END DESCRIPTION:
XS GIS Cut Line= 3
      2180507.16     13826340.78      2180041.90     13825924.13
      2179098.73     13825667.53
#Sta/Elev= 30
  4305.8 1186.03  4488.4 1175.88  4602.0 1171.38  4637.2 1168.07  4729.1 1165.00
  4757.5 1162.75  4771.7 1162.84  4849.5 1158.78  4885.4 1153.28  4930.4 1148.82
  4944.4 1144.84  4979.0 1139.16  4989.3 1135.06  4997.3 1133.62  4997.6 1133.12
  5002.0 1133.62  5018.8 1139.62  5030.8 1142.20  5098.3 1146.05  5165.5 1148.44
  5212.4 1152.41  5322.8 1156.27  5393.5 1157.16  5560.0 1163.86  5611.1 1167.91
  5710.7 1171.20  5748.5 1171.83  5783.1 1174.69  5862.7 1178.51  5907.8 1179.30
#Mann=5,-1,0
  4305.8    0.12       0  4997.3    0.05       0  5002.0    0.12       0
  5322.8   0.035       0  5710.7    0.12       0
Bank Sta=4997.3,5002
Exp/Cntr=0.3,0.1

Type RM Length L Ch R = 1,2529,503,503,503
BEGIN DESCRIPTION:
H21700
END DESCRIPTION:
XS GIS Cut Line= 2
      2180847.42     13825840.79      2179090.55     13825264.42
#Sta/Elev= 30
  4239.8 1167.46  4379.2 1160.84  4484.4 1158.18  4568.6 1152.31  4695.8 1149.07
  4722.4 1149.32  4786.0 1146.33  4945.2 1141.84  4982.2 1139.71  5006.4 1133.33
  5006.8 1132.83  5011.2 1133.33  5031.7 1135.33  5072.5 1137.07  5109.5 1136.22
  5141.4 1138.35  5167.9 1142.91  5173.2 1142.18  5179.0 1143.66  5238.6 1145.40
  5347.1 1148.62  5539.8 1154.96  5687.7 1159.13  5714.3 1161.29  5719.5 1160.71
  5746.1 1163.86  5846.8 1167.94  5970.4 1175.71  6073.0 1180.66  6088.8 1181.40
#Mann=8,-1,0
  4239.8    0.12       0  5006.4    0.05       0  5011.2    0.12       0
  5238.6    0.07       0  5347.1   0.035       0  5539.8    0.12       0
  5970.4    0.07       0  6073.0   0.035       0
Bank Sta=5006.4,5011.2
Exp/Cntr=0.3,0.1

Type RM Length L Ch R = 1,2026,548,548,548
BEGIN DESCRIPTION:
H21699
END DESCRIPTION:
XS GIS Cut Line= 3
      2180708.58     13825618.59      2180180.79     13825063.02
      2179188.86     13824882.67
#Sta/Elev= 30
  4343.8 1155.32  4469.2 1151.06  4540.0 1146.88  4596.6 1145.38  4759.2 1138.23
  4893.5 1136.42  4928.7 1134.00  4950.1 1130.57  4964.3 1127.14  4997.1 1126.01
  4997.4 1125.51  5002.0 1126.01  5027.8 1135.89  5042.0 1137.98  5063.4 1139.58
  5138.4 1141.03  5316.8 1143.12  5464.5 1144.77  5576.3 1148.48  5593.7 1150.13
  5624.2 1151.16  5629.7 1152.27  5634.8 1151.69  5644.5 1153.29  5705.5 1155.05
  5766.5 1159.18  5837.6 1161.24  5911.7 1161.16  6082.0 1169.01  6118.3 1173.50
#Mann=5,-1,0
  4343.8    0.12       0  4997.1    0.05       0  5002.0    0.12       0
  5138.4   0.035       0  5316.8    0.12       0
Bank Sta=4997.1,5002
Exp/Cntr=0.3,0.1

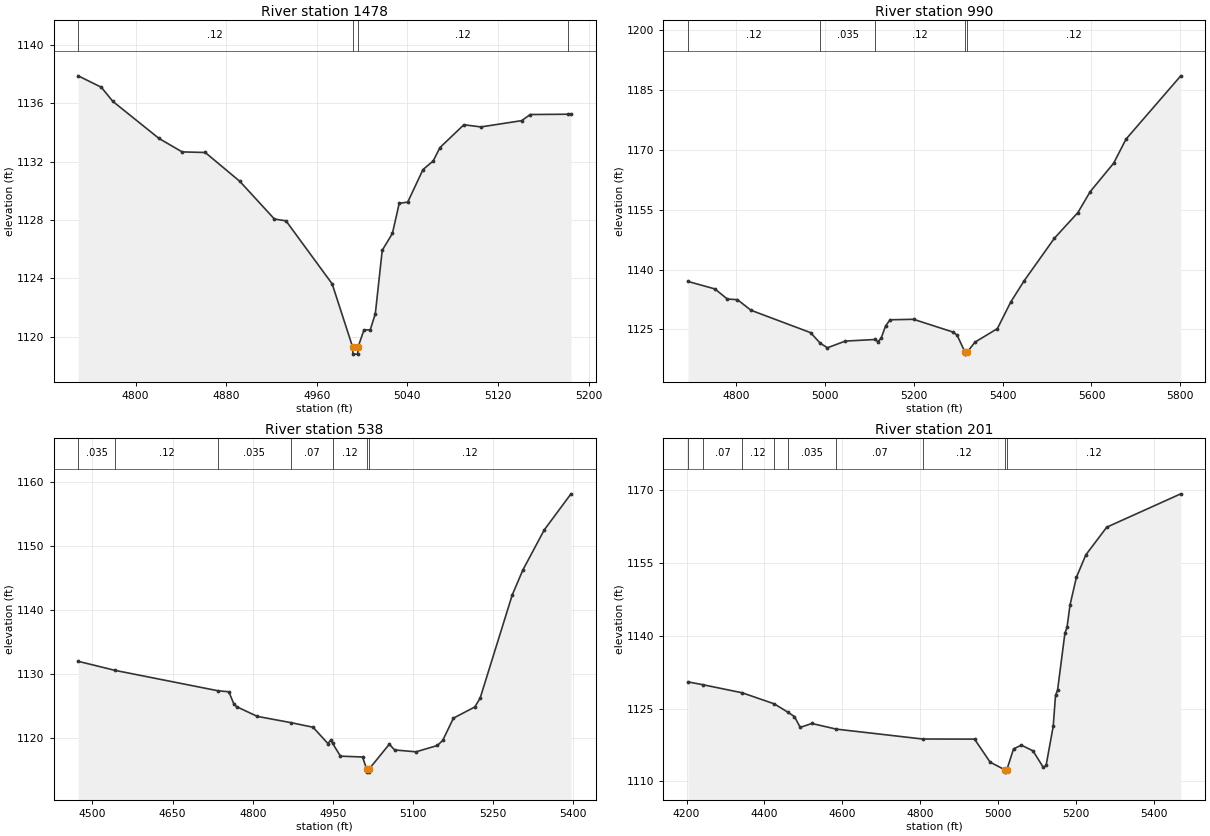
Type RM Length L Ch R = 1,1478,488,488,488
BEGIN DESCRIPTION:
West Fork Tributary 12 3.0
END DESCRIPTION:
XS GIS Cut Line= 3
      2180775.00     13825174.98      2180725.00     13824925.00
      2180575.01     13824825.01
#Sta/Elev= 30
  4749.3 1137.87  4769.7 1137.09  4779.9 1136.12  4820.7 1133.58  4841.1 1132.66
  4861.5 1132.62  4892.1 1130.64  4922.6 1128.06  4932.8 1127.94  4973.6 1123.62
  4991.6 1119.31  4991.9 1118.81  4996.1 1118.81  4996.5 1119.31  5001.7 1120.47
  5007.2 1120.47  5011.7 1121.58  5017.8 1125.92  5026.8 1127.08  5032.8 1129.14
  5040.3 1129.22  5053.8 1131.45  5062.8 1132.04  5068.8 1132.96  5089.9 1134.52
  5104.9 1134.37  5140.9 1134.80  5148.5 1135.22  5182.1 1135.24  5184.5 1135.25
#Mann=4,-1,0
  4749.3    0.12       0  4991.6    0.05       0  4996.5    0.12       0
  5182.1   0.035       0
Bank Sta=4991.6,4996.5
Exp/Cntr=0.3,0.1

Type RM Length L Ch R = 1,990,452,452,452
BEGIN DESCRIPTION:
West Fork Tributary 12 2.0
END DESCRIPTION:
XS GIS Cut Line= 3
      2181125.01     13825124.96      2181175.00     13824825.00
      2181275.00     13824025.02
#Sta/Elev= 30
  4690.9 1137.03  4751.7 1135.15  4779.6 1132.62  4802.4 1132.46  4832.8 1129.81
  4967.1 1124.20  4989.0 1121.54  5005.1 1120.40  5045.4 1122.08  5113.3 1122.48
  5118.5 1121.91  5126.0 1122.76  5136.1 1125.86  5146.2 1127.42  5199.1 1127.54
  5287.3 1124.37  5297.3 1123.57  5315.0 1119.31  5315.4 1118.81  5319.9 1119.31
  5337.6 1121.82  5388.0 1125.20  5418.3 1131.91  5448.5 1137.22  5516.5 1147.87
  5569.4 1154.29  5597.1 1159.53  5650.1 1166.69  5677.8 1172.70  5801.2 1188.57
#Mann=5,-1,0
  4690.9    0.12       0  4989.0   0.035       0  5113.3    0.12       0
  5315.0   0.035       0  5319.9    0.12       0
Bank Sta=5315,5319.9
Exp/Cntr=0.3,0.1

Type RM Length L Ch R = 1,538,337,337,337
BEGIN DESCRIPTION:
West Fork Tributary 12 1.0
END DESCRIPTION:
XS GIS Cut Line= 3
      2181424.99     13825175.04      2181575.00     13824675.00
      2181575.00     13824274.96
#Sta/Elev= 30
  4473.4 1131.94  4542.4 1130.52  4735.5 1127.32  4755.3 1127.17  4764.9 1125.22
  4770.1 1124.83  4808.4 1123.32  4870.7 1122.35  4912.8 1121.62  4940.6 1119.07
  4945.9 1119.59  4949.6 1119.08  4964.1 1117.09  5005.5 1116.96  5013.0 1115.09
  5013.4 1114.59  5017.6 1114.59  5017.9 1115.09  5055.5 1118.96  5065.5 1118.06
  5105.5 1117.77  5145.5 1118.76  5155.5 1119.56  5175.5 1123.04  5215.5 1124.79
  5225.5 1126.18  5285.5 1142.32  5305.5 1146.25  5345.5 1152.52  5395.5 1158.16
#Mann=7,-1,0
  4473.4   0.035       0  4542.4    0.12       0  4735.5   0.035       0
  4870.7    0.07       0  4949.6    0.12       0  5013.0    0.05       0
  5017.9    0.12       0
Bank Sta=5013,5017.9
Exp/Cntr=0.3,0.1

Type RM Length L Ch R = 1,201,0,0,0
BEGIN DESCRIPTION:
H21698
END DESCRIPTION:
XS GIS Cut Line= 4
      2181548.87     13825229.66      2181875.24     13824750.52
      2181861.35     13824417.19      2181729.70     13824091.54
#Sta/Elev= 30
  4203.6 1130.52  4242.2 1129.93  4342.9 1128.27  4425.3 1125.98  4459.6 1124.29
  4476.8 1123.37  4491.7 1121.14  4521.6 1121.94  4584.2 1120.78  4805.5 1118.74
  4939.0 1118.72  4979.0 1113.97  5016.2 1112.41  5016.7 1111.91  5021.9 1112.41
  5039.1 1116.70  5059.1 1117.48  5089.1 1116.29  5115.5 1112.88  5122.6 1113.28
  5140.9 1121.38  5146.8 1127.73  5152.1 1128.84  5170.9 1140.56  5176.3 1141.75
  5184.0 1146.38  5200.4 1152.09  5224.5 1156.70  5278.2 1162.42  5468.2 1169.30
#Mann=9,-1,0
  4203.6   0.035       0  4242.2    0.07       0  4342.9    0.12       0
  4425.3    0.07       0  4459.6   0.035       0  4584.2    0.07       0
  4805.5    0.12       0  5016.2    0.05       0  5021.9    0.12       0
Bank Sta=5016.2,5021.9
Exp/Cntr=0.3,0.1

Chan Stop Cuts=-1