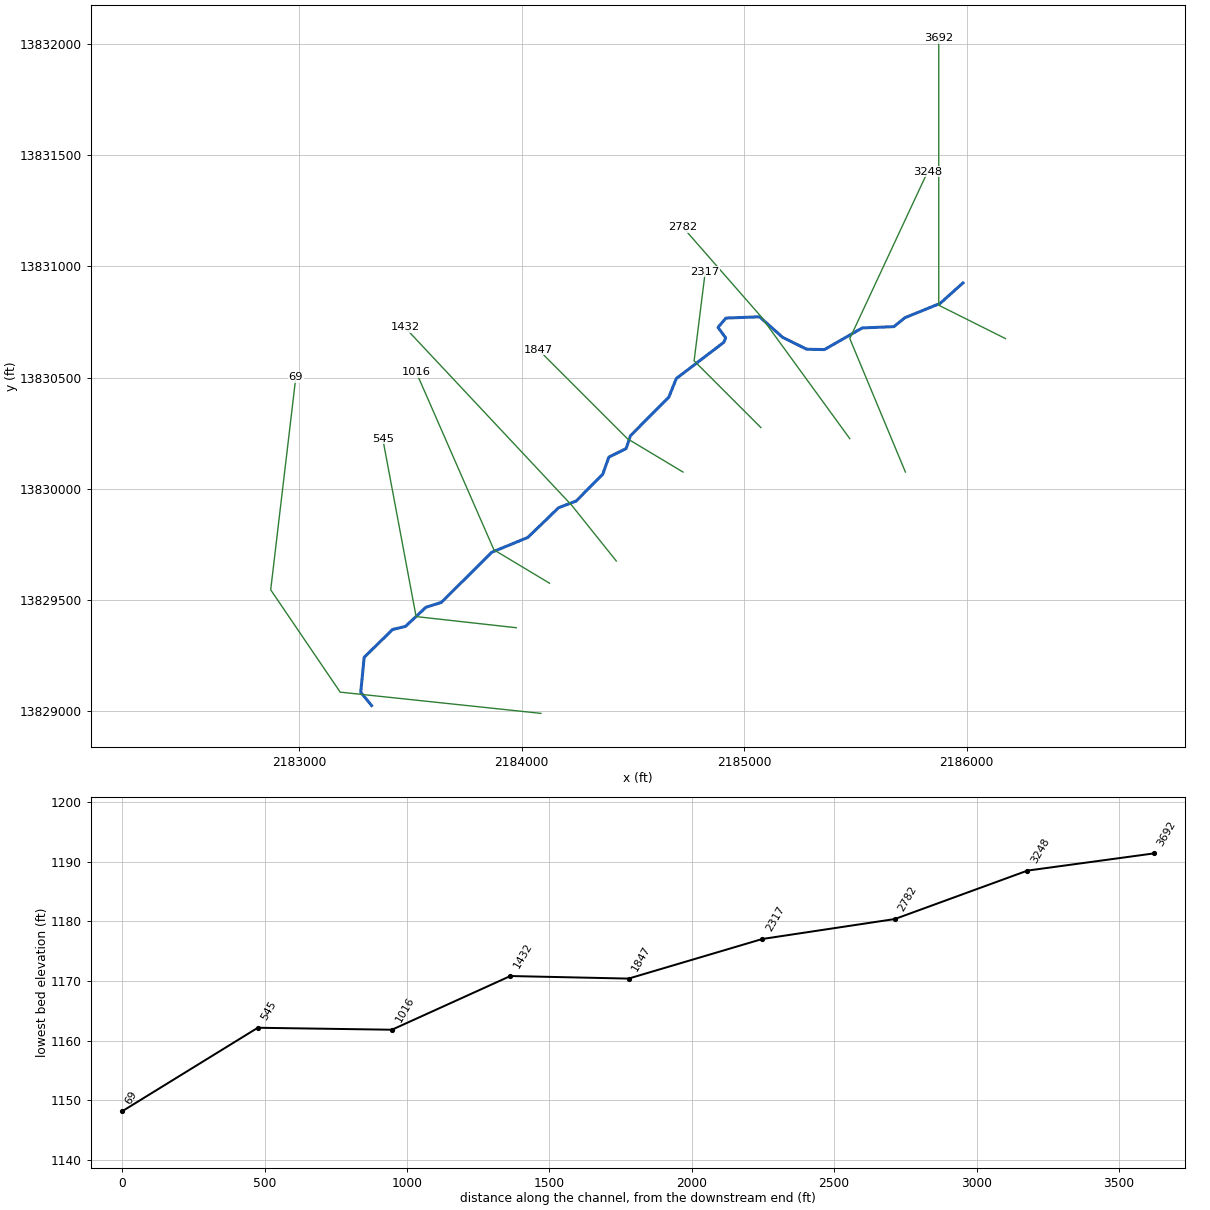
--- West Fork Tributary 14.prj (project) ---

Proj Title=West Fork Tributary 14 Base Level Engineering
Current Plan=p01
Default Exp/Contr=0.3,0.1
English Units
Geom File=g01
Flow File=f01
Plan File=p01
BEGIN DESCRIPTION:
West Fork Tributary 14
END DESCRIPTION:

--- West Fork Tributary 14.p01 (plan) ---

Plan Title=Multiple Run
Short Identifier=Multiple
Geom File=g01
Flow File=f01
Subcritical Flow
K Sum by GR= 0
Std Step Tol= 0.01
Critical Tol= 0.01
Num of Std Step Trials= 20
Max Error Tol= 0.3
Flow Tol Ratio= 0.001
Split Flow NTrial= 30
Split Flow Tol= 0.02
Split Flow Ratio= 0.02
Log Output Level= 0
Friction Slope Method= 1
Unsteady Friction Slope Method= 2
Unsteady Bridges Friction Slope Method= 1
Parabolic Critical Depth
Global Vel Dist=  1 , 1 , 1
Global Log Level= 0
CheckData=True
Encroach Param= -1, 0, 0, 0
BEGIN DESCRIPTION:
Multiple Run
END DESCRIPTION:

--- West Fork Tributary 14.f01 (steady flow) ---

Flow Title=Multiple
Number of Profiles=7
Profile Names=10-year,25-year,50-year,1pct_min,100-year,1pct_plu,500-year
River Rch & RM= West Fork Tribut,Reach-1,3692
     830    1370    1871    1237    2468    4924    4250
River Rch & RM= West Fork Tribut,Reach-1,1847
    1094    1834    2529    1687    3366    6717    5905
Boundary for River Rch & Prof#=West Fork Tribut,Reach-1,1
Up Type=0
Dn Type=3
Dn Slope=0.005
Boundary for River Rch & Prof#=West Fork Tribut,Reach-1,2
Up Type=0
Dn Type=3
Dn Slope=0.005
Boundary for River Rch & Prof#=West Fork Tribut,Reach-1,3
Up Type=0
Dn Type=3
Dn Slope=0.005
Boundary for River Rch & Prof#=West Fork Tribut,Reach-1,4
Up Type=0
Dn Type=3
Dn Slope=0.005
Boundary for River Rch & Prof#=West Fork Tribut,Reach-1,5
Up Type=0
Dn Type=3
Dn Slope=0.005
Boundary for River Rch & Prof#=West Fork Tribut,Reach-1,6
Up Type=0
Dn Type=3
Dn Slope=0.005
Boundary for River Rch & Prof#=West Fork Tribut,Reach-1,7
Up Type=0
Dn Type=3
Dn Slope=0.005

--- West Fork Tributary 14.g01 (geometry) ---

Geom Title=Existing Conditions

River Reach=West Fork Tribut,Reach-1
Reach XY= 30
      2185983.59     13830925.00      2185881.07     13830833.10
      2185722.82     13830768.88      2185673.44     13830728.76
      2185530.93     13830722.75      2185361.03     13830625.54
      2185280.97     13830627.14      2185172.71     13830680.85
      2185069.14     13830772.95      2184918.18     13830767.19
      2184882.46     13830725.25      2184916.84     13830678.34
      2184908.62     13830658.30      2184694.77     13830495.13
      2184661.37     13830411.79      2184488.72     13830237.98
      2184469.35     13830180.63      2184391.58     13830142.01
      2184364.22     13830065.34      2184245.09     13829944.79
      2184165.32     13829914.22      2184027.30     13829780.83
      2183865.32     13829714.24      2183638.21     13829488.63
      2183568.96     13829466.82      2183477.28     13829380.87
      2183418.95     13829366.84      2183291.43     13829241.77
      2183276.09     13829084.55      2183325.00     13829025.00

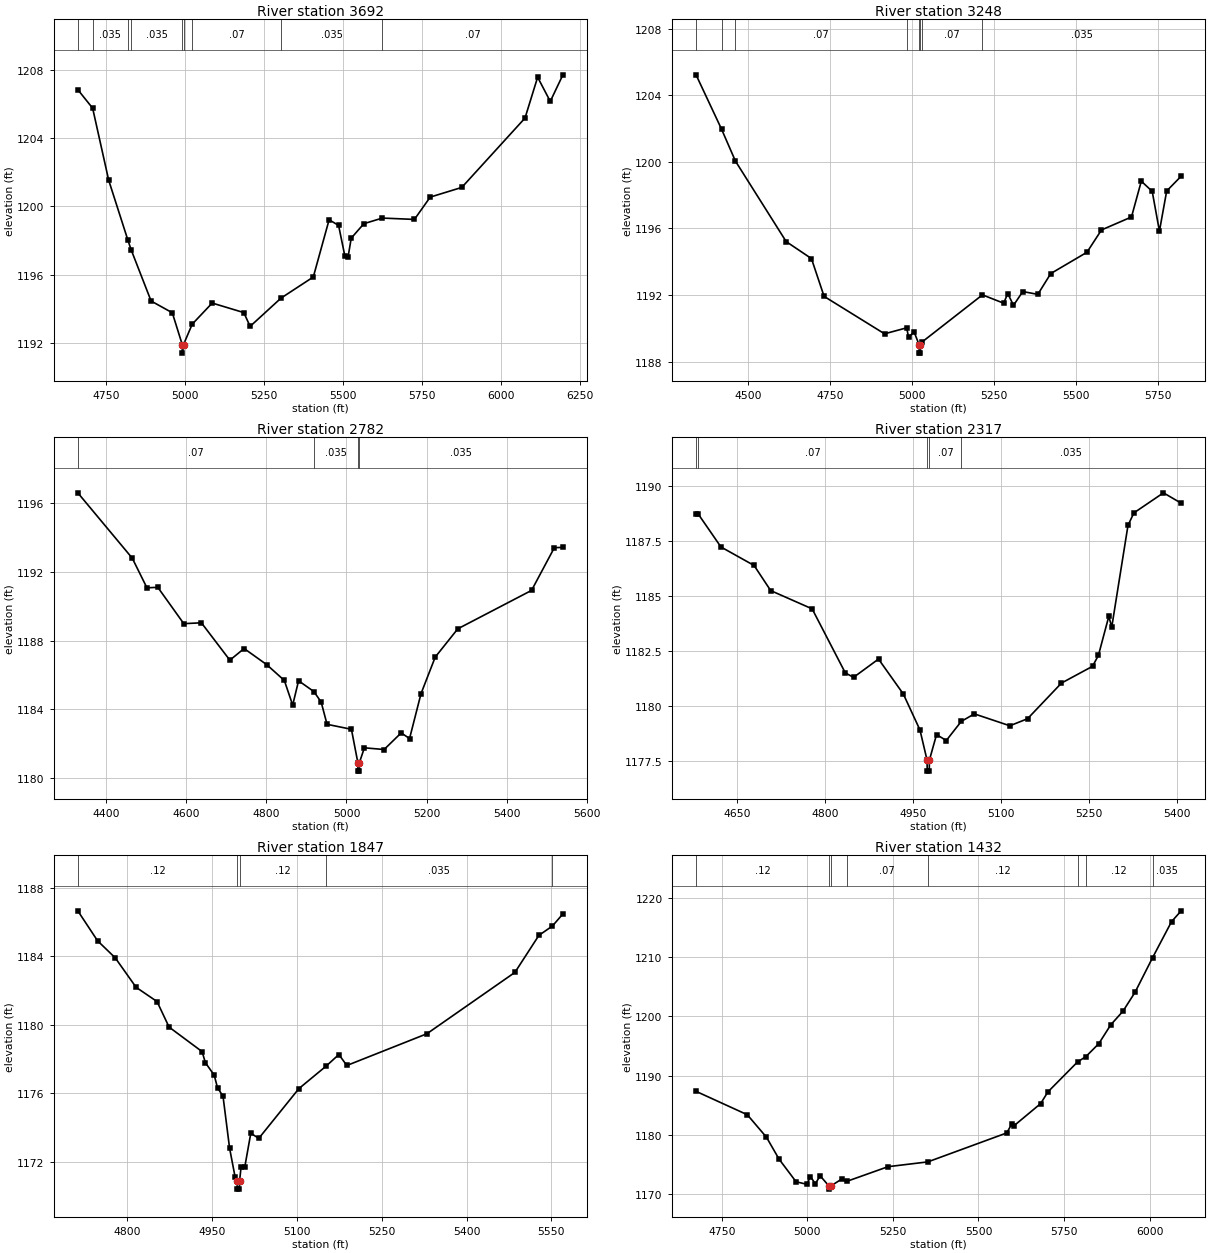
Type RM Length L Ch R = 1,3692,444,444,444
BEGIN DESCRIPTION:
West Fork Tributary 14 8.0
END DESCRIPTION:
XS GIS Cut Line= 3
      2186174.99     13830675.00      2185875.00     13830825.00
      2185875.00     13832025.00
#Sta/Elev= 30
  4659.9 1206.86  4706.9 1205.77  4757.7 1201.54  4818.7 1198.01  4828.5 1197.47
  4891.9 1194.45  4959.0 1193.76  4990.5 1191.89  4990.8 1191.39  4994.5 1191.89
  5022.0 1193.09  5085.3 1194.33  5185.3 1193.77  5205.3 1192.96  5303.1 1194.62
  5405.3 1195.86  5455.3 1199.22  5485.3 1198.89  5505.3 1197.08  5515.3 1197.03
  5525.3 1198.14  5565.3 1198.99  5623.9 1199.32  5725.3 1199.24  5775.3 1200.55
  5875.3 1201.12  6075.3 1205.19  6115.3 1207.59  6155.3 1206.17  6195.3 1207.73
#Mann=9,-1,0
  4659.9    0.07       0  4706.9   0.035       0  4818.7    0.07       0
  4828.5   0.035       0  4990.5   0.035       0  4994.5   0.035       0
  5022.0    0.07       0  5303.1   0.035       0  5623.9    0.07       0
Bank Sta=4990.5,4994.5
Exp/Cntr=0.3,0.1

Type RM Length L Ch R = 1,3248,466,466,466
BEGIN DESCRIPTION:
West Fork Tributary 14 7.0
END DESCRIPTION:
XS GIS Cut Line= 3
      2185725.00     13830075.01      2185475.00     13830675.00
      2185824.99     13831424.97
#Sta/Elev= 30
  4342.6 1205.23  4420.4 1201.96  4462.5 1200.05  4617.2 1195.21  4694.1 1194.19
  4732.6 1191.92  4916.8 1189.67  4984.1 1190.03  4989.9 1189.47  5006.8 1189.78
  5022.1 1189.01  5022.4 1188.51  5025.9 1188.51  5026.1 1189.01  5031.1 1189.18
  5214.9 1192.01  5279.5 1191.51  5292.1 1192.09  5309.5 1191.38  5337.8 1192.21
  5383.6 1192.04  5423.0 1193.29  5533.3 1194.57  5577.5 1195.91  5668.9 1196.69
  5698.8 1198.84  5732.0 1198.23  5754.0 1195.84  5776.1 1198.25  5820.2 1199.14
#Mann=8,-1,0
  4342.6    0.07       0  4420.4   0.035       0  4462.5    0.07       0
  4984.1   0.035       0  5022.1   0.035       0  5026.1   0.035       0
  5031.1    0.07       0  5214.9   0.035       0
Bank Sta=5022.1,5026.1
Exp/Cntr=0.3,0.1

Type RM Length L Ch R = 1,2782,465,465,465
BEGIN DESCRIPTION:
West Fork Tributary 14 6.0
END DESCRIPTION:
XS GIS Cut Line= 3
      2185474.99     13830225.01      2185075.00     13830775.00
      2184724.98     13831175.02
#Sta/Elev= 30
  4328.9 1196.62  4464.9 1192.81  4501.6 1191.08  4528.7 1191.11  4593.6 1188.99
  4637.6 1189.04  4708.7 1186.86  4744.3 1187.54  4800.7 1186.60  4844.7 1185.68
  4865.6 1184.24  4880.3 1185.66  4918.5 1185.03  4936.7 1184.42  4951.4 1183.12
  5012.3 1182.83  5028.3 1180.89  5028.6 1180.39  5032.1 1180.39  5032.3 1180.89
  5044.6 1181.75  5093.9 1181.65  5136.6 1182.62  5157.5 1182.29  5186.0 1184.90
  5221.6 1187.04  5278.0 1188.69  5462.2 1190.93  5519.1 1193.42  5540.5 1193.44
#Mann=4,-1,0
  4328.9    0.07       0  4918.5   0.035       0  5028.3   0.035       0
  5032.3   0.035       0
Bank Sta=5028.3,5032.3
Exp/Cntr=0.3,0.1

Type RM Length L Ch R = 1,2317,470,470,470
BEGIN DESCRIPTION:
West Fork Tributary 14 5.0
END DESCRIPTION:
XS GIS Cut Line= 3
      2185075.03     13830274.97      2184775.00     13830575.00
      2184825.00     13830974.98
#Sta/Elev= 30
  4580.5 1188.75  4583.6 1188.75  4623.0 1187.23  4679.5 1186.39  4707.8 1185.25
  4778.5 1184.42  4835.1 1181.51  4849.2 1181.31  4891.7 1182.14  4934.1 1180.55
  4962.4 1178.92  4974.5 1177.55  4974.8 1177.05  4978.3 1177.05  4978.5 1177.55
  4990.7 1178.71  5007.3 1178.44  5032.9 1179.31  5055.2 1179.65  5115.7 1179.11
  5145.9 1179.43  5203.8 1181.05  5256.7 1181.81  5266.8 1182.31  5284.5 1184.08
  5289.5 1183.59  5317.2 1188.21  5327.3 1188.78  5377.7 1189.69  5407.9 1189.22
#Mann=5,-1,0
  4580.5   0.035       0  4583.6    0.07       0  4974.5    0.05       0
  4978.5    0.07       0  5032.9   0.035       0
Bank Sta=4974.5,4978.5
Exp/Cntr=0.3,0.1

Type RM Length L Ch R = 1,1847,415,415,415
BEGIN DESCRIPTION:
West Fork Tributary 14 4.0
END DESCRIPTION:
XS GIS Cut Line= 3
      2184725.01     13830074.99      2184475.00     13830225.00
      2184075.03     13830624.97
#Sta/Elev= 30
  4713.1 1186.64  4748.1 1184.89  4779.2 1183.90  4816.1 1182.18  4853.1 1181.35
  4874.4 1179.86  4932.7 1178.43  4938.6 1177.78  4954.1 1177.06  4960.0 1176.32
  4969.7 1175.83  4981.3 1172.80  4991.1 1171.11  4994.7 1170.91  4995.0 1170.41
  4998.8 1170.41  4999.0 1170.91  5001.7 1171.71  5008.2 1171.71  5018.8 1173.67
  5032.9 1173.37  5103.7 1176.27  5152.1 1177.59  5174.4 1178.26  5188.5 1177.62
  5329.9 1179.47  5485.5 1183.05  5527.9 1185.21  5551.6 1185.75  5570.3 1186.46
#Mann=5,-1,0
  4713.1    0.12       0  4994.7    0.05       0  4999.0    0.12       0
  5152.1   0.035       0  5551.6    0.12       0
Bank Sta=4994.7,4999
Exp/Cntr=0.3,0.1

Type RM Length L Ch R = 1,1432,416,416,416
BEGIN DESCRIPTION:
West Fork Tributary 14 3.0
END DESCRIPTION:
XS GIS Cut Line= 3
      2184425.01     13829674.99      2184225.00     13829925.00
      2183474.97     13830725.03
#Sta/Elev= 30
  4675.1 1187.35  4824.8 1183.40  4880.8 1179.60  4917.6 1175.90  4967.3 1172.08
  4998.7 1171.66  5009.2 1172.97  5023.4 1171.74  5037.5 1173.09  5063.7 1171.34
  5064.0 1170.84  5068.1 1171.34  5101.5 1172.58  5114.8 1172.14  5235.8 1174.63
  5352.0 1175.44  5582.6 1180.33  5596.8 1181.81  5603.7 1181.54  5681.3 1185.27
  5702.8 1187.26  5789.2 1192.31  5813.7 1193.22  5851.3 1195.40  5886.5 1198.60
  5922.1 1200.89  5957.3 1204.09  6008.4 1209.92  6063.8 1216.00  6091.9 1217.83
#Mann=8,-1,0
  4675.1    0.12       0  5063.7    0.05       0  5068.1    0.12       0
  5114.8    0.07       0  5352.0    0.12       0  5789.2    0.07       0
  5813.7    0.12       0  6008.4   0.035       0
Bank Sta=5063.7,5068.1
Exp/Cntr=0.3,0.1

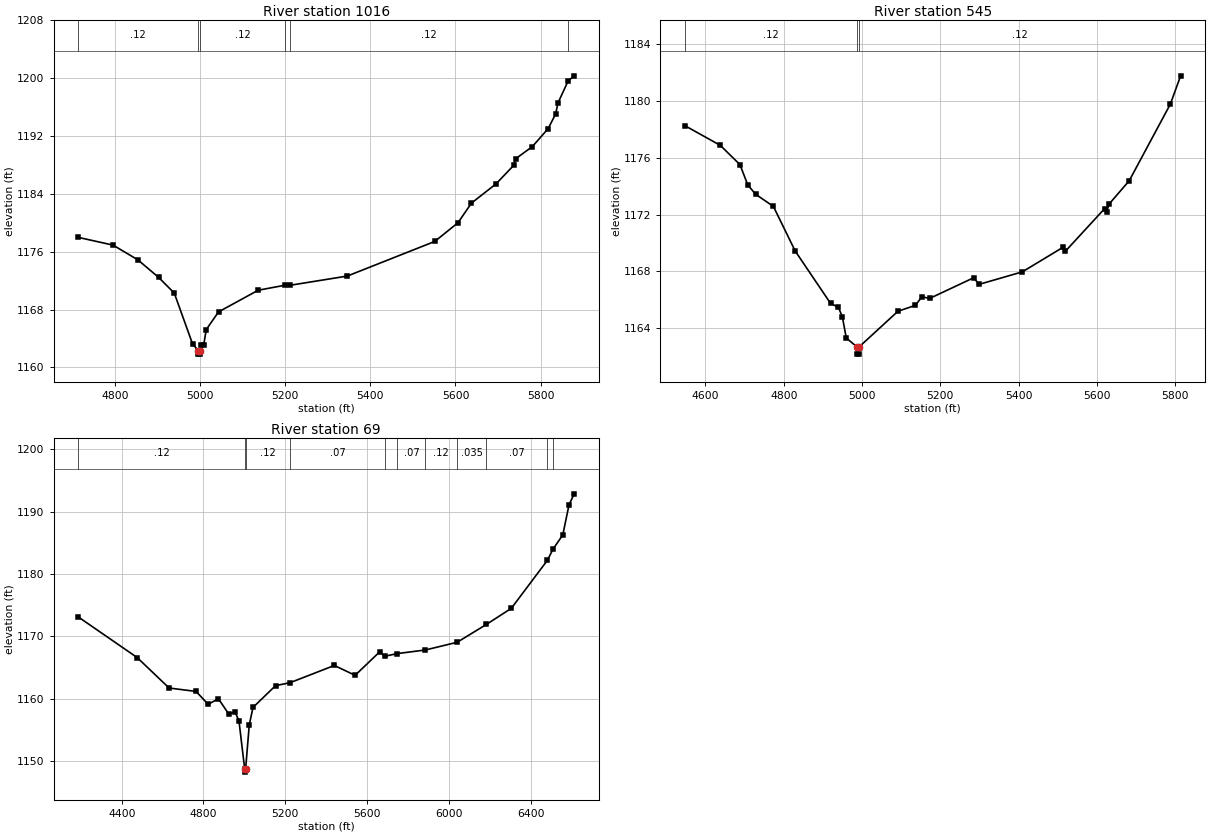
Type RM Length L Ch R = 1,1016,471,471,471
BEGIN DESCRIPTION:
West Fork Tributary 14 2.0
END DESCRIPTION:
XS GIS Cut Line= 3
      2184124.98     13829575.01      2183875.00     13829725.00
      2183525.02     13830524.96
#Sta/Elev= 30
  4714.1 1177.99  4795.7 1176.92  4854.0 1174.88  4902.6 1172.46  4939.5 1170.28
  4982.3 1163.27  4995.6 1162.34  4996.0 1161.84  4999.8 1161.84  5000.1 1162.34
  5002.7 1163.06  5008.4 1163.06  5014.6 1165.24  5043.4 1167.68  5136.6 1170.68
  5200.3 1171.38  5212.2 1171.37  5345.9 1172.64  5551.4 1177.43  5606.0 1180.02
  5637.5 1182.73  5695.2 1185.39  5736.6 1187.94  5742.0 1188.89  5780.6 1190.55
  5817.6 1193.03  5835.2 1195.05  5841.0 1196.61  5864.7 1199.64  5878.8 1200.34
#Mann=6,-1,0
  4714.1    0.12       0  4995.6    0.05       0  5000.1    0.12       0
  5200.3    0.07       0  5212.2    0.12       0  5864.7   0.035       0
Bank Sta=4995.6,5000.1
Exp/Cntr=0.3,0.1

Type RM Length L Ch R = 1,545,476,476,476
BEGIN DESCRIPTION:
West Fork Tributary 14 1.0
END DESCRIPTION:
XS GIS Cut Line= 3
      2183975.03     13829375.00      2183525.00     13829425.00
      2183375.01     13830224.96
#Sta/Elev= 30
  4547.2 1178.28  4637.8 1176.89  4688.1 1175.53  4708.2 1174.09  4728.3 1173.44
  4773.6 1172.58  4829.0 1169.45  4919.5 1165.75  4939.6 1165.47  4949.7 1164.80
  4959.8 1163.30  4987.7 1162.67  4988.0 1162.17  4991.9 1162.17  4992.2 1162.67
  5091.6 1165.19  5136.5 1165.61  5152.6 1166.21  5173.0 1166.10  5284.9 1167.55
  5299.3 1167.09  5409.5 1167.97  5514.6 1169.72  5519.7 1169.43  5619.8 1172.43
  5624.9 1172.17  5630.8 1172.74  5682.5 1174.39  5787.7 1179.80  5813.9 1181.79
#Mann=3,-1,0
  4547.2    0.12       0  4987.7    0.05       0  4992.2    0.12       0
Bank Sta=4987.7,4992.2
Exp/Cntr=0.3,0.1

Type RM Length L Ch R = 1,69,0,0,0
BEGIN DESCRIPTION:
H21703
END DESCRIPTION:
XS GIS Cut Line= 4
      2184086.50     13828989.81      2183183.71     13829085.30
      2182871.21     13829545.37      2182984.05     13830500.14
#Sta/Elev= 30
  4187.8 1173.10  4475.4 1166.59  4631.8 1161.69  4763.8 1161.14  4822.8 1159.08
  4873.1 1159.96  4923.4 1157.52  4954.4 1157.86  4973.7 1156.38  5001.5 1148.68
  5001.8 1148.18  5006.1 1148.68  5023.9 1155.75  5042.1 1158.57  5152.6 1162.07
  5223.0 1162.54  5440.1 1165.31  5541.8 1163.73  5661.5 1167.49  5687.0 1166.79
  5748.0 1167.22  5885.8 1167.80  6041.0 1169.04  6184.2 1171.91  6305.9 1174.49
  6482.5 1182.21  6509.3 1183.97  6557.7 1186.29  6587.9 1191.09  6613.2 1192.88
#Mann=11,-1,0
  4187.8    0.12       0  5001.5    0.05       0  5006.1    0.12       0
  5223.0    0.07       0  5687.0    0.12       0  5748.0    0.07       0
  5885.8    0.12       0  6041.0   0.035       0  6184.2    0.07       0
  6482.5    0.12       0  6509.3    0.07       0
Bank Sta=5001.5,5006.1
Exp/Cntr=0.3,0.1

Chan Stop Cuts=-1