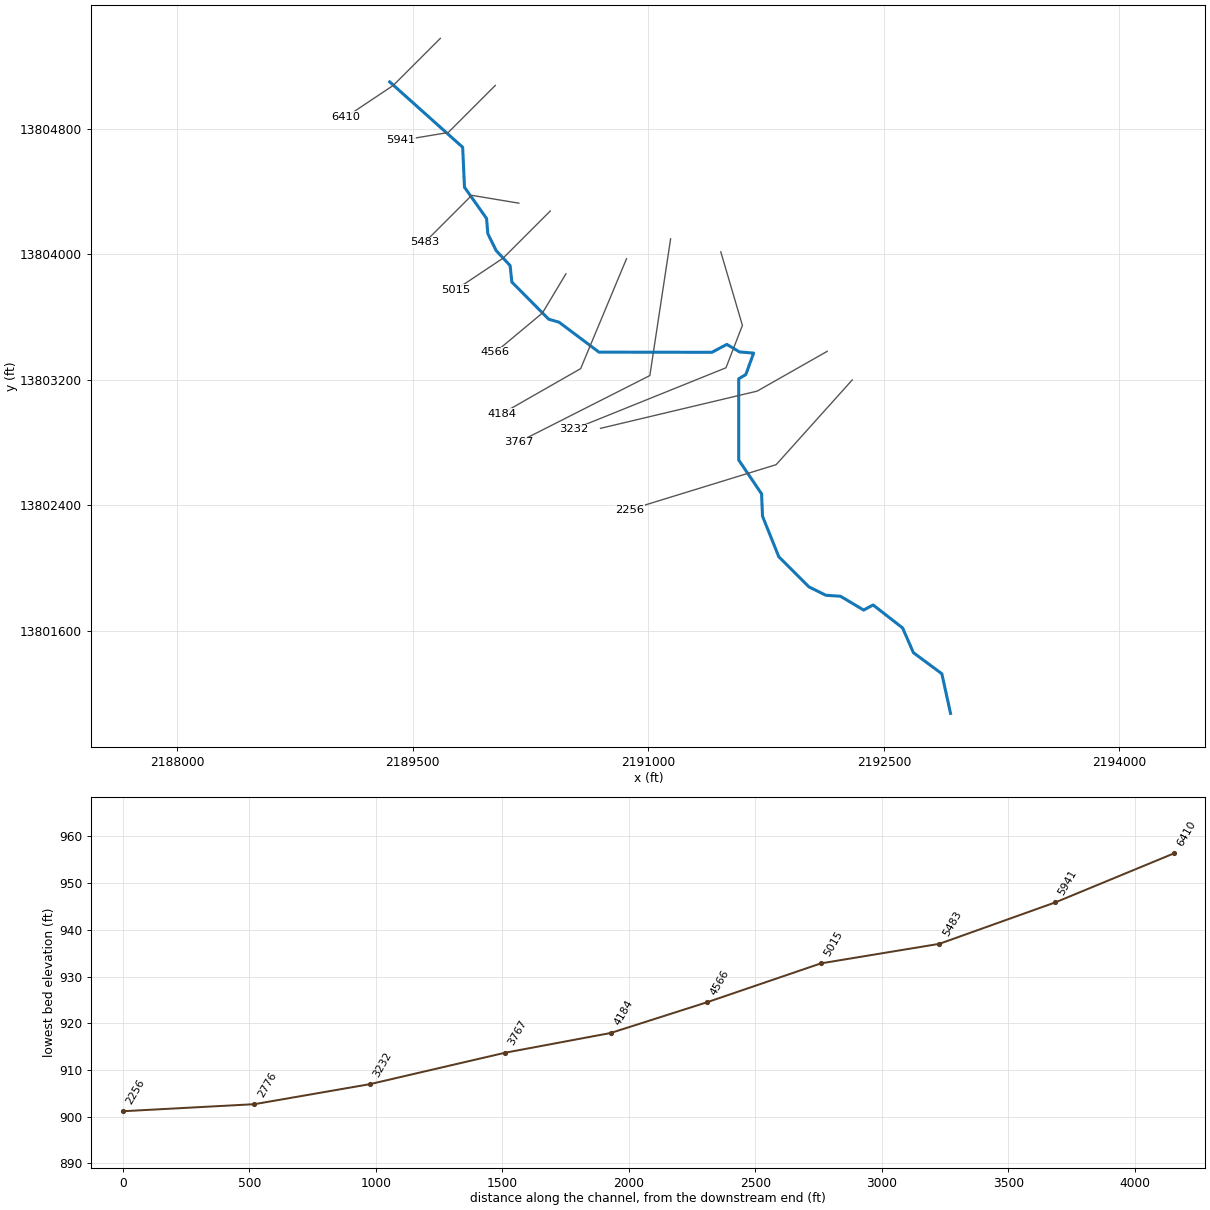
--- West Fork Tributary 2.prj (project) ---

Proj Title=West Fork Tributary 2 Base Level Engineering
Current Plan=p01
Default Exp/Contr=0.3,0.1
English Units
Geom File=g01
Flow File=f01
Plan File=p01
BEGIN DESCRIPTION:
West Fork Tributary 2
END DESCRIPTION:

--- West Fork Tributary 2.p01 (plan) ---

Plan Title=Multiple Run
Short Identifier=Multiple
Geom File=g01
Flow File=f01
Subcritical Flow
K Sum by GR= 0
Std Step Tol= 0.01
Critical Tol= 0.01
Num of Std Step Trials= 20
Max Error Tol= 0.3
Flow Tol Ratio= 0.001
Split Flow NTrial= 30
Split Flow Tol= 0.02
Split Flow Ratio= 0.02
Log Output Level= 0
Friction Slope Method= 1
Unsteady Friction Slope Method= 2
Unsteady Bridges Friction Slope Method= 1
Parabolic Critical Depth
Global Vel Dist=  1 , 1 , 1
Global Log Level= 0
CheckData=True
Encroach Param= -1, 0, 0, 0
BEGIN DESCRIPTION:
Multiple Run
END DESCRIPTION:

--- West Fork Tributary 2.f01 (steady flow) ---

Flow Title=Multiple
Number of Profiles=7
Profile Names=10-year,25-year,50-year,1pct_min,100-year,1pct_plu,500-year
River Rch & RM= West Fork Tribut,Reach-1,6410
     655    1070    1450     953    1902    3795    3235
Boundary for River Rch & Prof#=West Fork Tribut,Reach-1,1
Up Type=0
Dn Type=3
Dn Slope=0.005
Boundary for River Rch & Prof#=West Fork Tribut,Reach-1,2
Up Type=0
Dn Type=3
Dn Slope=0.005
Boundary for River Rch & Prof#=West Fork Tribut,Reach-1,3
Up Type=0
Dn Type=3
Dn Slope=0.005
Boundary for River Rch & Prof#=West Fork Tribut,Reach-1,4
Up Type=0
Dn Type=3
Dn Slope=0.005
Boundary for River Rch & Prof#=West Fork Tribut,Reach-1,5
Up Type=0
Dn Type=3
Dn Slope=0.005
Boundary for River Rch & Prof#=West Fork Tribut,Reach-1,6
Up Type=0
Dn Type=3
Dn Slope=0.005
Boundary for River Rch & Prof#=West Fork Tribut,Reach-1,7
Up Type=0
Dn Type=3
Dn Slope=0.005

--- West Fork Tributary 2.g01 (geometry) ---

Geom Title=Existing Conditions

River Reach=West Fork Tribut,Reach-1
Reach XY= 30
      2189352.35     13805097.65      2189817.19     13804681.19
      2189828.75     13804426.55      2189969.46     13804227.42
      2189977.33     13804130.97      2190030.85     13804022.71
      2190119.46     13803927.42      2190130.52     13803822.57
      2190365.32     13803585.78      2190431.04     13803566.82
      2190685.44     13803376.05      2191404.97     13803375.09
      2191500.00     13803425.40      2191580.66     13803377.53
      2191670.38     13803369.75      2191621.10     13803233.65
      2191575.47     13803206.33      2191575.54     13802688.86
      2191721.24     13802473.44      2191727.27     13802330.94
      2191830.83     13802072.70      2192022.70     13801880.83
      2192130.97     13801827.33      2192223.42     13801821.17
      2192371.77     13801733.25      2192431.67     13801765.70
      2192619.41     13801619.39      2192688.47     13801461.44
      2192869.48     13801327.44      2192925.00     13801075.00

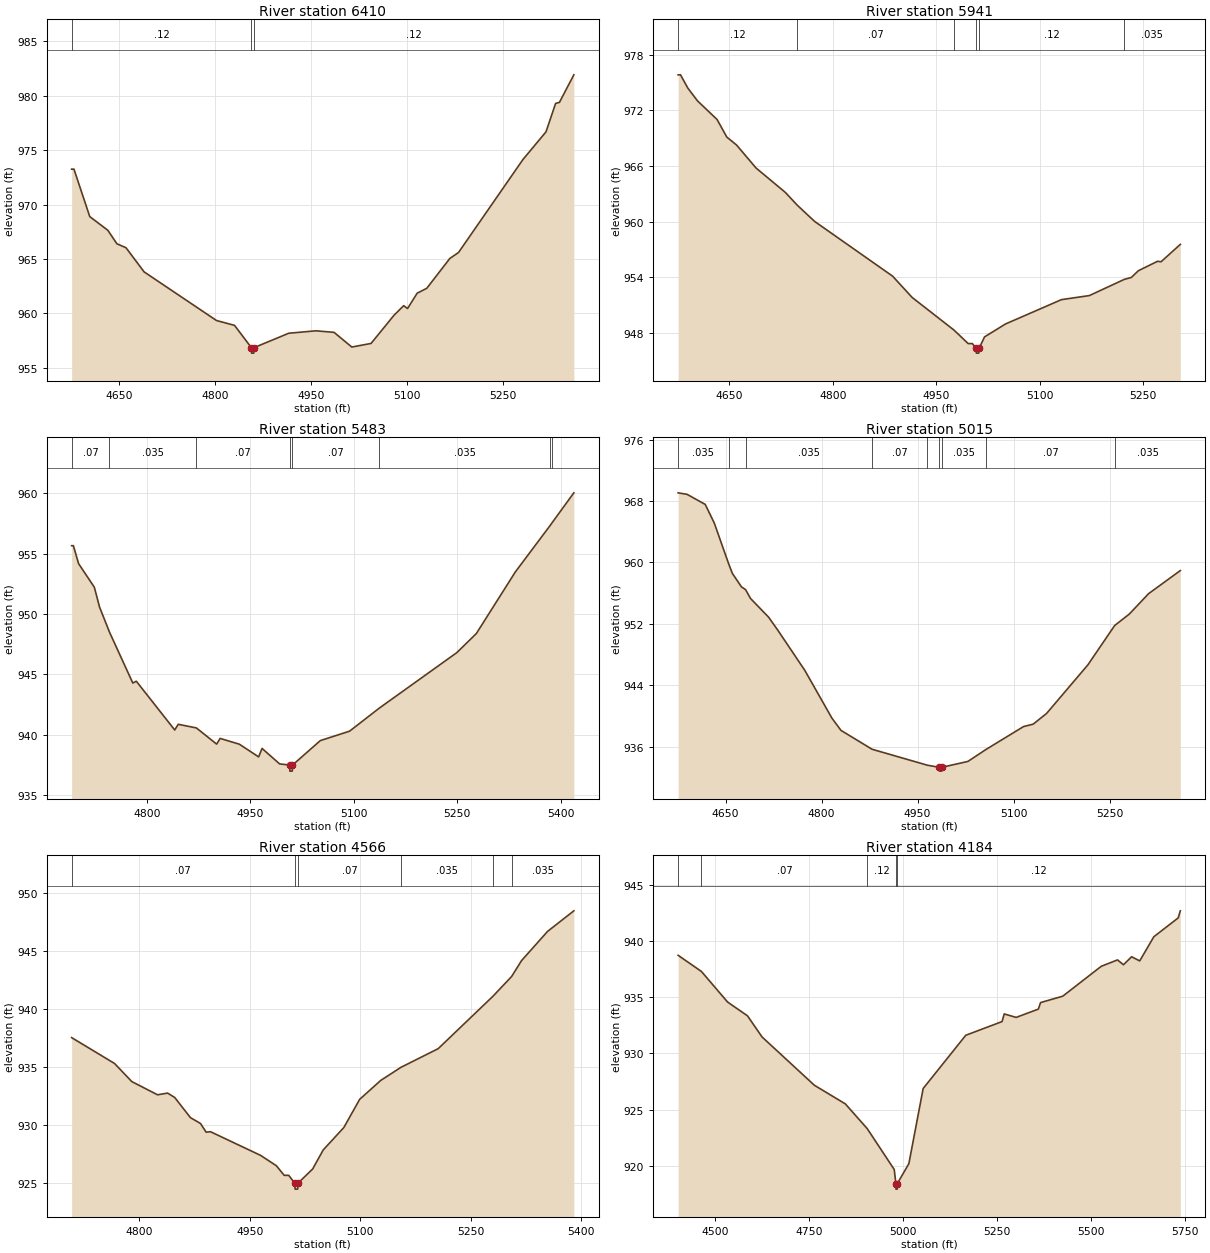
Type RM Length L Ch R = 1,6410,469,469,469
BEGIN DESCRIPTION:
West Fork Tributary 2 10.0
END DESCRIPTION:
XS GIS Cut Line= 3
      2189675.02     13805375.02      2189375.00     13805075.00
      2189075.04     13804875.02
#Sta/Elev= 30
  4575.7  973.25  4579.3  973.25  4604.0  968.89  4632.3  967.63  4646.4  966.39
  4660.6  966.03  4688.9  963.81  4802.0  959.34  4830.3  958.89  4856.6  956.84
  4856.8  956.34  4860.3  956.34  4860.6  956.84  4915.1  958.17  4957.6  958.39
  4985.8  958.25  5013.5  956.90  5043.6  957.23  5079.6  959.83  5094.6  960.70
  5100.6  960.44  5115.7  961.85  5130.7  962.30  5166.7  965.04  5180.3  965.59
  5280.9  974.13  5317.0  976.68  5332.0  979.29  5338.0  979.39  5360.5  981.92
#Mann=3,-1,0
  4575.7    0.12       0  4856.6    0.05       0  4860.6    0.12       0
Bank Sta=4856.6,4860.6
Exp/Cntr=0.3,0.1

Type RM Length L Ch R = 1,5941,458,458,458
BEGIN DESCRIPTION:
West Fork Tributary 2 9.0
END DESCRIPTION:
XS GIS Cut Line= 3
      2190024.97     13805074.97      2189725.00     13804775.00
      2189424.96     13804724.99
#Sta/Elev= 30
  4575.8  975.82  4579.3  975.82  4589.9  974.39  4604.0  973.01  4632.3  971.01
  4646.5  969.11  4660.6  968.26  4688.9  965.78  4731.3  963.16  4748.9  961.76
  4773.7  960.04  4886.9  954.14  4915.2  951.85  4975.8  948.34  4996.5  946.88
  5002.6  946.88  5008.2  946.35  5008.4  945.85  5011.9  945.85  5012.2  946.35
  5020.3  947.60  5050.7  948.99  5131.8  951.61  5172.4  952.05  5222.9  953.79
  5233.2  954.00  5243.3  954.72  5271.2  955.74  5276.3  955.69  5304.2  957.56
#Mann=6,-1,0
  4575.8    0.12       0  4748.9    0.07       0  4975.8    0.12       0
  5008.2    0.05       0  5012.2    0.12       0  5222.9   0.035       0
Bank Sta=5008.2,5012.2
Exp/Cntr=0.3,0.1

Type RM Length L Ch R = 1,5483,468,468,468
BEGIN DESCRIPTION:
West Fork Tributary 2 8.0
END DESCRIPTION:
XS GIS Cut Line= 3
      2190174.98     13804325.00      2189875.00     13804375.00
      2189574.98     13804074.98
#Sta/Elev= 30
  4690.8  955.67  4693.3  955.67  4700.9  954.18  4723.7  952.23  4731.3  950.58
  4745.6  948.52  4779.5  944.29  4784.6  944.44  4840.3  940.40  4845.4  940.87
  4871.7  940.57  4901.1  939.23  4906.2  939.70  4934.1  939.22  4962.0  938.17
  4967.0  938.87  4992.4  937.59  5007.1  937.49  5007.3  936.99  5010.8  936.99
  5011.1  937.49  5051.5  939.52  5093.9  940.30  5137.0  942.21  5249.5  946.81
  5277.8  948.39  5334.3  953.49  5385.3  957.38  5387.9  957.59  5419.2  960.05
#Mann=8,-1,0
  4690.8    0.07       0  4745.6   0.035       0  4871.7    0.07       0
  5007.1    0.05       0  5011.1    0.07       0  5137.0   0.035       0
  5385.3    0.07       0  5387.9   0.035       0
Bank Sta=5007.1,5011.1
Exp/Cntr=0.3,0.1

Type RM Length L Ch R = 1,5015,449,449,449
BEGIN DESCRIPTION:
West Fork Tributary 2 7.0
END DESCRIPTION:
XS GIS Cut Line= 3
      2190374.97     13804274.97      2190075.00     13803975.00
      2189774.98     13803774.99
#Sta/Elev= 30
  4575.8  969.07  4589.9  968.87  4618.2  967.56  4632.3  965.14  4654.8  959.82
  4660.6  958.57  4674.8  956.82  4681.3  956.45  4688.9  955.31  4717.2  952.87
  4731.3  951.21  4773.8  945.94  4816.2  939.71  4830.3  938.12  4878.9  935.66
  4965.4  933.58  4983.9  933.31  4984.1  932.81  4987.6  932.81  4987.9  933.31
  5028.6  934.07  5057.1  935.64  5115.7  938.62  5130.7  938.93  5151.8  940.34
  5216.4  946.68  5258.0  951.78  5281.0  953.28  5311.0  955.93  5360.6  958.94
#Mann=9,-1,0
  4575.8   0.035       0  4654.8    0.07       0  4681.3   0.035       0
  4878.9    0.07       0  4965.4   0.035       0  4983.9   0.035       0
  4987.9   0.035       0  5057.1    0.07       0  5258.0   0.035       0
Bank Sta=4983.9,4987.9
Exp/Cntr=0.3,0.1

Type RM Length L Ch R = 1,4566,382,382,382
BEGIN DESCRIPTION:
West Fork Tributary 2 6.0
END DESCRIPTION:
XS GIS Cut Line= 3
      2190475.02     13803875.03      2190325.00     13803625.00
      2190024.99     13803374.99
#Sta/Elev= 30
  4708.2  937.57  4766.5  935.34  4789.9  933.78  4824.9  932.64  4838.5  932.79
  4848.2  932.41  4869.6  930.67  4883.2  930.17  4890.9  929.42  4896.8  929.46
  4964.8  927.42  4986.2  926.53  4996.9  925.70  5003.0  925.70  5011.4  925.01
  5011.7  924.51  5015.2  924.51  5015.4  925.01  5035.6  926.25  5049.9  927.89
  5077.9  929.82  5099.4  932.25  5128.0  933.88  5155.5  935.01  5206.1  936.62
  5280.5  941.14  5305.8  942.84  5319.3  944.21  5354.5  946.72  5390.3  948.50
#Mann=6,-1,0
  4708.2    0.07       0  5011.4    0.05       0  5015.4    0.07       0
  5155.5   0.035       0  5280.5    0.07       0  5305.8   0.035       0
Bank Sta=5011.4,5015.4
Exp/Cntr=0.3,0.1

Type RM Length L Ch R = 1,4184,417,417,417
BEGIN DESCRIPTION:
H21708
END DESCRIPTION:
XS GIS Cut Line= 3
      2190860.77     13803970.80      2190568.69     13803270.92
      2190068.65     13802985.18
#Sta/Elev= 30
  4402.3  938.73  4464.3  937.29  4533.7  934.57  4586.7  933.34  4625.3  931.46
  4764.3  927.16  4846.6  925.50  4904.7  923.30  4976.5  919.66  4980.9  918.41
  4981.1  917.91  4984.6  917.91  4984.9  918.41  5015.4  920.18  5053.4  926.87
  5166.6  931.61  5263.1  932.83  5268.8  933.51  5300.5  933.20  5359.5  933.94
  5365.3  934.52  5424.3  935.09  5526.5  937.75  5569.7  938.32  5585.6  937.89
  5607.2  938.60  5628.8  938.23  5666.2  940.38  5731.0  942.06  5736.6  942.69
#Mann=5,-1,0
  4402.3    0.12       0  4464.3    0.07       0  4904.7    0.12       0
  4980.9    0.05       0  4984.9    0.12       0
Bank Sta=4980.9,4984.9
Exp/Cntr=0.3,0.1

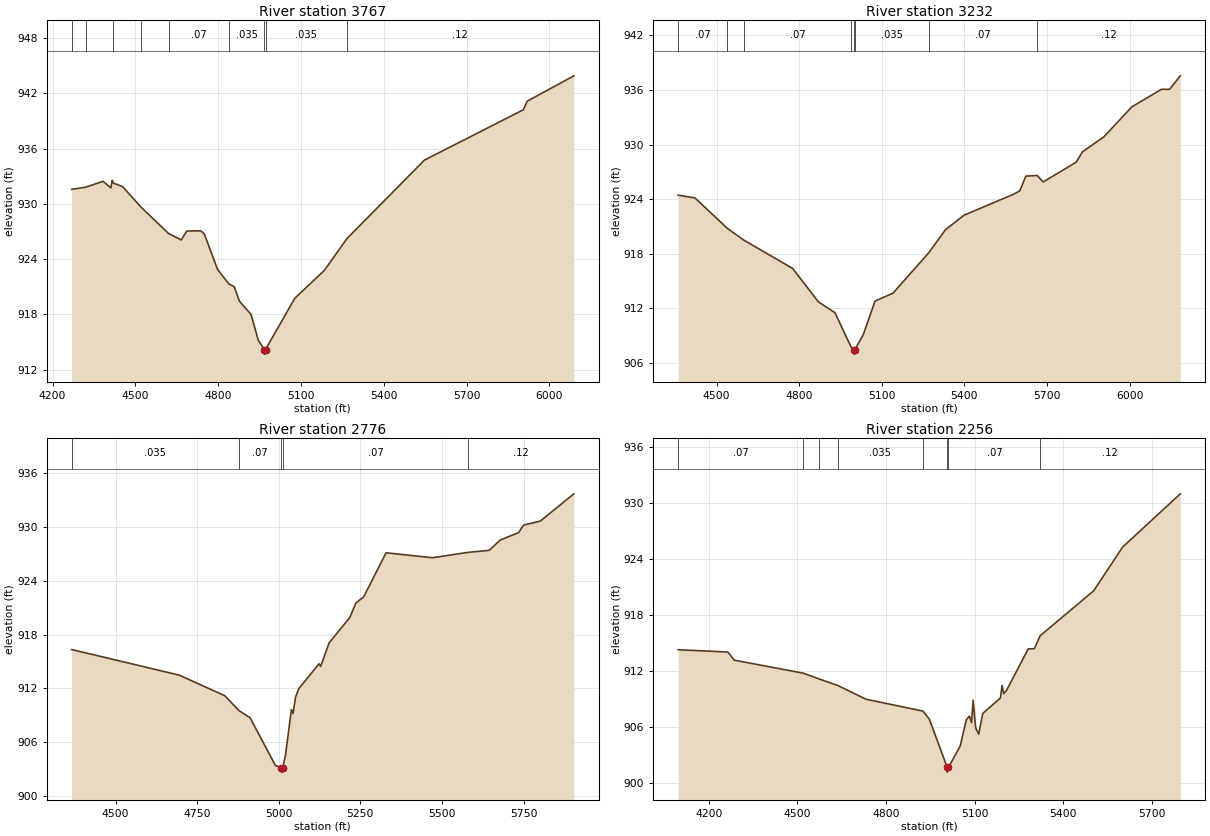
Type RM Length L Ch R = 1,3767,535,535,535
BEGIN DESCRIPTION:
H21707
END DESCRIPTION:
XS GIS Cut Line= 3
      2191141.78     13804097.50      2191009.53     13803226.84
      2190171.92     13802802.53
#Sta/Elev= 30
  4269.2  931.57  4320.4  931.81  4383.0  932.44  4411.3  931.73  4416.3  932.55
  4420.4  932.25  4453.8  931.87  4520.4  929.65  4620.4  926.78  4666.2  926.08
  4686.4  927.05  4737.0  927.07  4749.7  926.75  4797.7  922.90  4838.1  921.32
  4858.4  921.00  4877.0  919.44  4919.1  918.00  4945.7  915.18  4967.6  914.19
  4967.9  913.69  4971.4  913.69  4971.6  914.19  5078.0  919.76  5185.0  922.78
  5266.4  926.22  5547.3  934.74  5906.0  940.21  5920.1  941.14  6088.8  943.89
#Mann=9,-1,0
  4269.2    0.07       0  4320.4    0.12       0  4420.4    0.07       0
  4520.4   0.035       0  4620.4    0.07       0  4838.1   0.035       0
  4967.6   0.035       0  4971.6   0.035       0  5266.4    0.12       0
Bank Sta=4967.6,4971.6
Exp/Cntr=0.3,0.1

Type RM Length L Ch R = 1,3232,456,456,456
BEGIN DESCRIPTION:
H21706
END DESCRIPTION:
XS GIS Cut Line= 4
      2191461.39     13804014.82      2191599.15     13803546.45
      2191494.45     13803276.43      2190524.61     13802885.19
#Sta/Elev= 30
  4360.6  924.44  4422.1  924.13  4538.5  920.81  4599.4  919.49  4776.5  916.38
  4870.3  912.70  4930.1  911.52  4988.0  907.79  4998.5  907.46  4998.8  906.96
  5002.3  906.96  5002.5  907.46  5032.7  909.09  5075.6  912.79  5140.8  913.66
  5270.6  918.10  5331.9  920.65  5399.1  922.24  5578.9  924.54  5601.5  924.92
  5623.1  926.53  5664.2  926.61  5686.3  925.89  5806.4  928.07  5828.6  929.20
  5906.4  930.84  6008.4  934.15  6115.8  936.08  6145.3  936.08  6184.2  937.56
#Mann=8,-1,0
  4360.6    0.07       0  4538.5   0.035       0  4599.4    0.07       0
  4988.0   0.035       0  4998.5   0.035       0  5002.5   0.035       0
  5270.6    0.07       0  5664.2    0.12       0
Bank Sta=4998.5,5002.5
Exp/Cntr=0.3,0.1

Type RM Length L Ch R = 1,2776,520,520,520
BEGIN DESCRIPTION:
H21705
END DESCRIPTION:
XS GIS Cut Line= 3
      2192139.19     13803381.14      2191692.83     13803127.65
      2190695.41     13802890.70
#Sta/Elev= 30
  4365.5  916.34  4694.9  913.49  4834.8  911.19  4877.9  909.54  4912.2  908.74
  4989.7  903.42  5008.2  903.18  5008.5  902.68  5012.0  902.68  5012.2  903.18
  5020.5  904.54  5038.8  909.65  5043.9  909.22  5051.3  911.03  5061.6  911.99
  5123.2  914.75  5128.3  914.46  5154.1  917.07  5217.8  919.92  5236.3  921.53
  5260.0  922.20  5328.8  927.12  5471.0  926.57  5580.3  927.17  5644.9  927.39
  5678.3  928.54  5734.4  929.36  5750.2  930.20  5801.6  930.66  5904.0  933.69
#Mann=5,-1,0
  4365.5   0.035       0  4877.9    0.07       0  5008.2    0.05       0
  5012.2    0.07       0  5580.3    0.12       0
Bank Sta=5008.2,5012.2
Exp/Cntr=0.3,0.1

Type RM Length L Ch R = 1,2256,0,0,0
BEGIN DESCRIPTION:
H21704
END DESCRIPTION:
XS GIS Cut Line= 3
      2192298.95     13803199.25      2191814.06     13802659.26
      2190882.80     13802372.72
#Sta/Elev= 30
  4095.9  914.27  4264.3  914.02  4286.0  913.15  4519.5  911.76  4572.0  911.15
  4635.9  910.45  4732.2  908.97  4924.8  907.70  4946.2  906.85  5007.0  901.67
  5007.2  901.17  5011.0  901.67  5050.8  903.96  5071.8  906.78  5082.2  907.16
  5089.3  906.47  5094.5  908.87  5103.2  905.89  5113.6  905.24  5127.2  907.45
  5186.9  909.10  5192.6  910.45  5197.9  909.57  5207.8  909.92  5281.0  914.35
  5301.9  914.38  5321.7  915.77  5502.6  920.57  5600.7  925.25  5796.0  930.95
#Mann=8,-1,0
  4095.9    0.07       0  4519.5   0.035       0  4572.0    0.07       0
  4635.9   0.035       0  4924.8    0.07       0  5007.0    0.05       0
  5011.0    0.07       0  5321.7    0.12       0
Bank Sta=5007,5011
Exp/Cntr=0.3,0.1

Chan Stop Cuts=-1