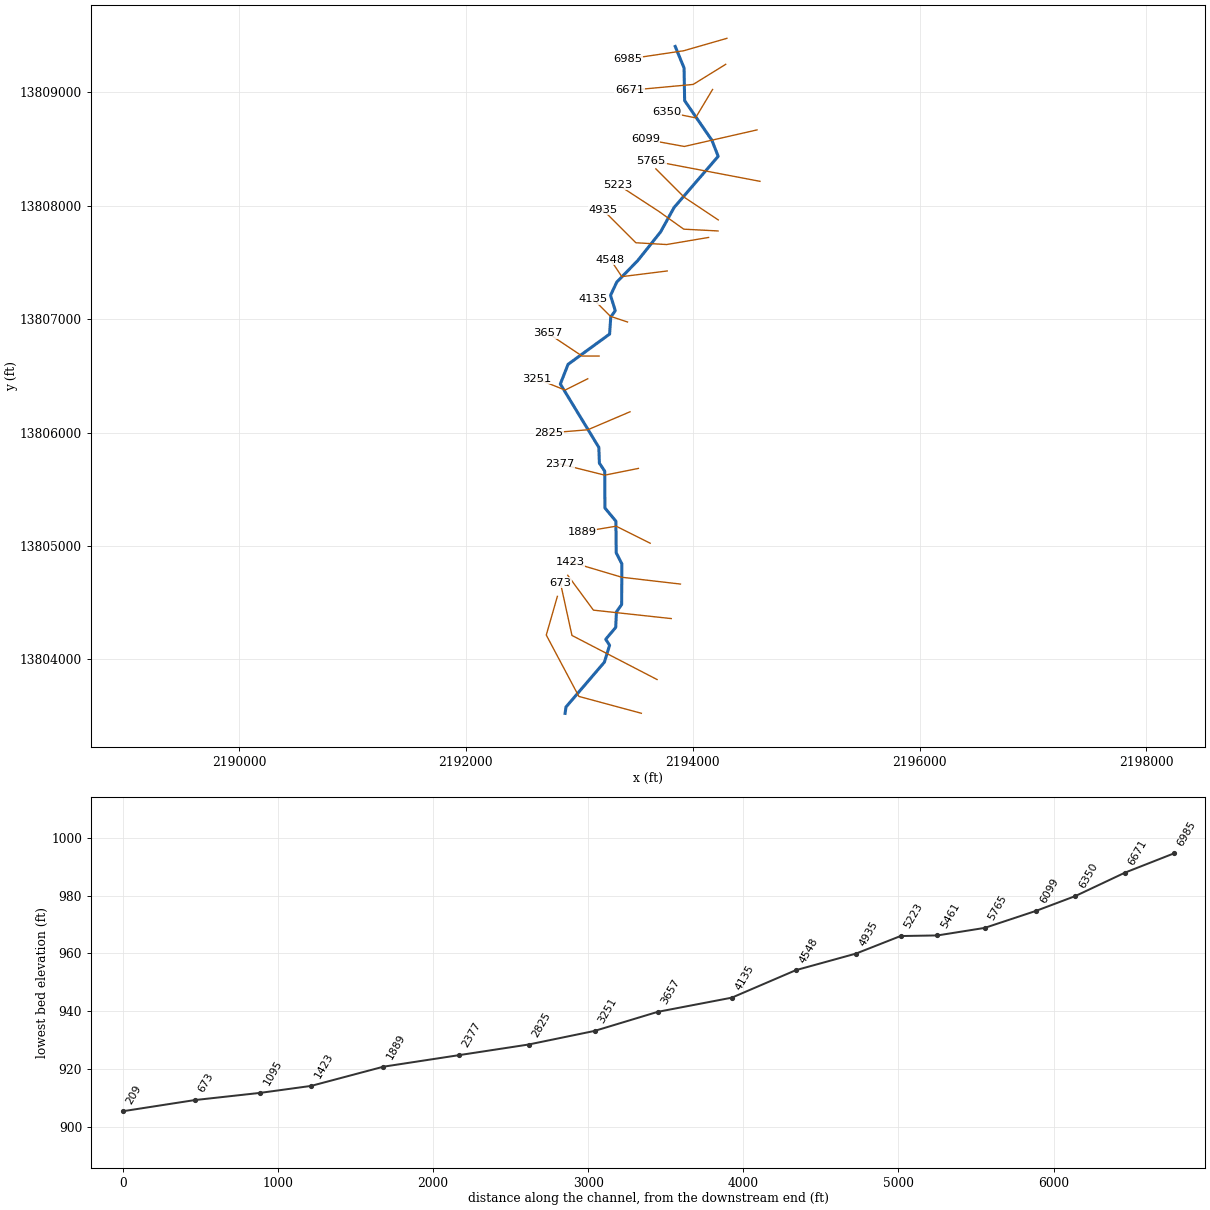
--- West Fork Tributary 3.prj (project) ---

Proj Title=West Fork Tributary 3 Base Level Engineering
Current Plan=p01
Default Exp/Contr=0.3,0.1
English Units
Geom File=g01
Flow File=f01
Plan File=p01
BEGIN DESCRIPTION:
West Fork Tributary 3
END DESCRIPTION:

--- West Fork Tributary 3.p01 (plan) ---

Plan Title=Multiple Run
Short Identifier=Multiple
Geom File=g01
Flow File=f01
Subcritical Flow
K Sum by GR= 0
Std Step Tol= 0.01
Critical Tol= 0.01
Num of Std Step Trials= 20
Max Error Tol= 0.3
Flow Tol Ratio= 0.001
Split Flow NTrial= 30
Split Flow Tol= 0.02
Split Flow Ratio= 0.02
Log Output Level= 0
Friction Slope Method= 1
Unsteady Friction Slope Method= 2
Unsteady Bridges Friction Slope Method= 1
Parabolic Critical Depth
Global Vel Dist=  1 , 1 , 1
Global Log Level= 0
CheckData=True
Encroach Param= -1, 0, 0, 0
BEGIN DESCRIPTION:
Multiple Run
END DESCRIPTION:

--- West Fork Tributary 3.f01 (steady flow) ---

Flow Title=Multiple
Number of Profiles=7
Profile Names=10-year,25-year,50-year,1pct_min,100-year,1pct_plu,500-year
River Rch & RM= West Fork Tribut,Reach-1,6985
     791    1313    1800    1196    2386    4761    4149
Boundary for River Rch & Prof#=West Fork Tribut,Reach-1,1
Up Type=0
Dn Type=3
Dn Slope=0.005
Boundary for River Rch & Prof#=West Fork Tribut,Reach-1,2
Up Type=0
Dn Type=3
Dn Slope=0.005
Boundary for River Rch & Prof#=West Fork Tribut,Reach-1,3
Up Type=0
Dn Type=3
Dn Slope=0.005
Boundary for River Rch & Prof#=West Fork Tribut,Reach-1,4
Up Type=0
Dn Type=3
Dn Slope=0.005
Boundary for River Rch & Prof#=West Fork Tribut,Reach-1,5
Up Type=0
Dn Type=3
Dn Slope=0.005
Boundary for River Rch & Prof#=West Fork Tribut,Reach-1,6
Up Type=0
Dn Type=3
Dn Slope=0.005
Boundary for River Rch & Prof#=West Fork Tribut,Reach-1,7
Up Type=0
Dn Type=3
Dn Slope=0.005

--- West Fork Tributary 3.g01 (geometry) ---

Geom Title=Existing Conditions

River Reach=West Fork Tribut,Reach-1
Reach XY= 30
      2193845.85     13809404.15      2193923.79     13809214.50
      2193928.75     13808926.55      2194169.16     13808577.29
      2194224.41     13808435.62      2193835.78     13807984.68
      2193716.84     13807768.95      2193514.22     13807515.32
      2193330.83     13807327.30      2193275.37     13807209.73
      2193317.44     13807075.00      2193277.47     13807019.14
      2193267.30     13806868.53      2192901.15     13806601.93
      2192833.05     13806428.29      2193172.64     13805869.48
      2193177.27     13805730.94      2193224.48     13805659.78
      2193226.06     13805335.44      2193322.93     13805219.14
      2193325.52     13804940.22      2193375.39     13804843.34
      2193373.62     13804484.66      2193327.39     13804419.46
      2193321.42     13804283.15      2193233.23     13804178.27
      2193267.21     13804125.10      2193221.38     13803976.50
      2192882.76     13803581.21      2192875.00     13803525.00

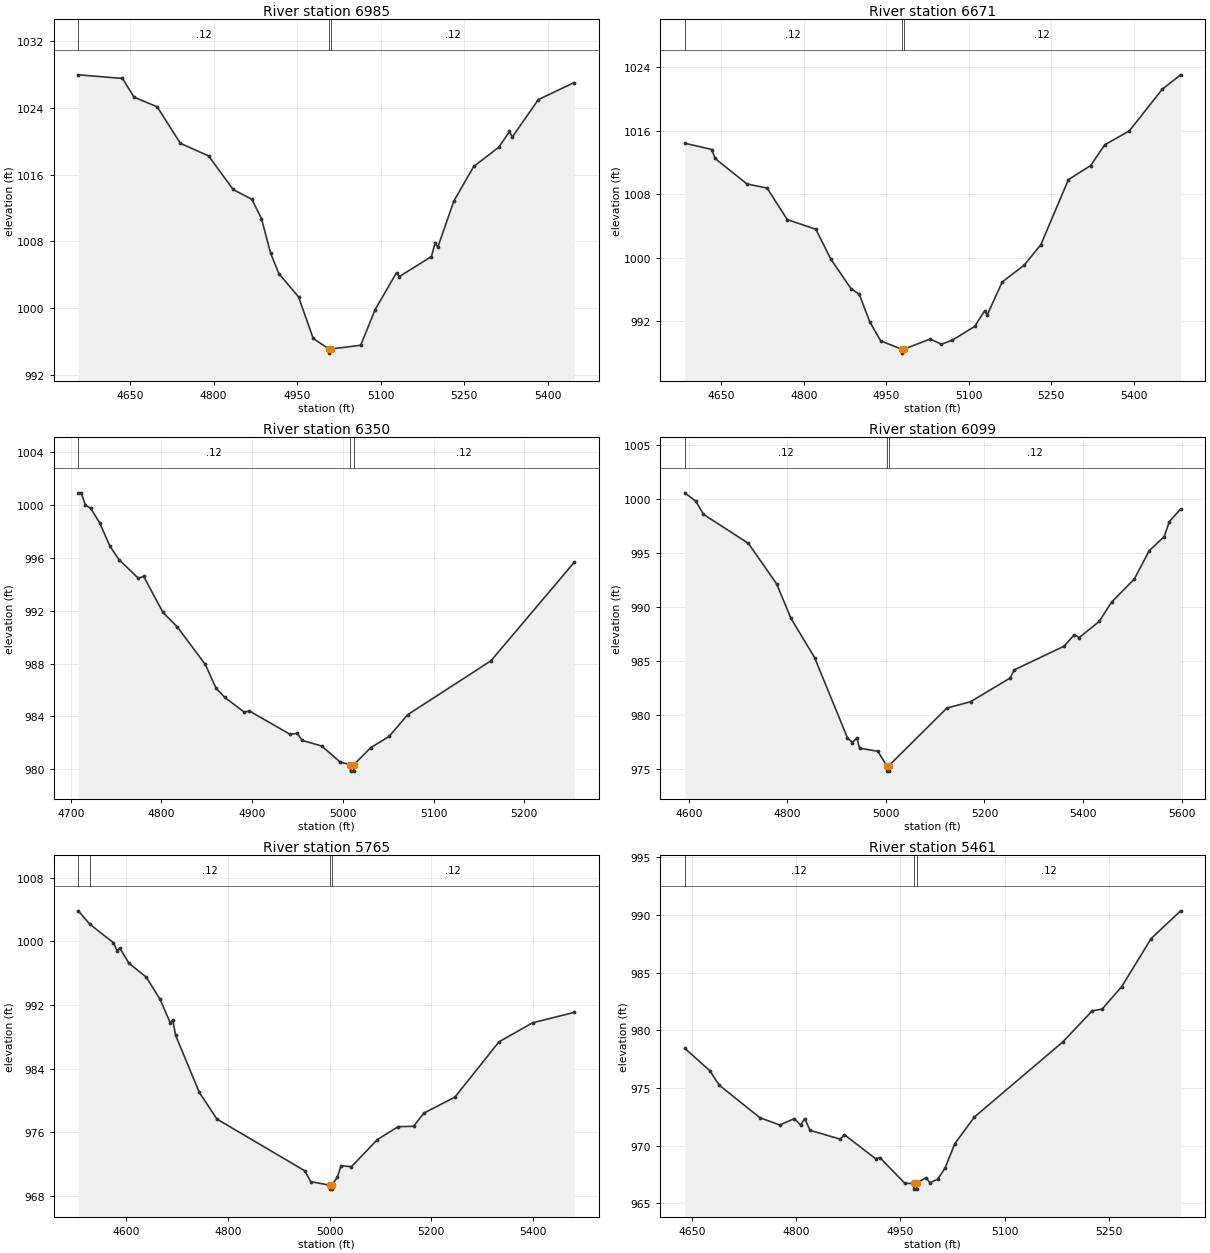
Type RM Length L Ch R = 1,6985,314,314,314
BEGIN DESCRIPTION:
West Fork Tributary 3 13.0
END DESCRIPTION:
XS GIS Cut Line= 3
      2194301.18     13809475.73      2193920.98     13809366.36
      2193431.40     13809293.44
#Sta/Elev= 30
  4557.2 1028.00  4636.5 1027.57  4657.3 1025.32  4698.9 1024.16  4740.5 1019.78
  4791.2 1018.27  4835.3 1014.24  4868.9 1013.06  4886.2 1010.74  4902.6 1006.59
  4917.4 1004.15  4952.8 1001.34  4979.1  996.36  5007.4  995.10  5007.7  994.60
  5011.4  995.10  5064.4  995.55  5090.3  999.82  5128.7 1004.25  5133.8 1003.79
  5191.4 1006.19  5198.0 1007.81  5203.1 1007.35  5231.8 1012.87  5267.4 1017.00
  5312.7 1019.33  5331.6 1021.20  5336.7 1020.54  5383.5 1025.03  5447.8 1027.07
#Mann=3,-1,0
  4557.2    0.12       0  5007.4    0.05       0  5011.4    0.12       0
Bank Sta=5007.4,5011.4
Exp/Cntr=0.3,0.1

Type RM Length L Ch R = 1,6671,321,321,321
BEGIN DESCRIPTION:
H21716
END DESCRIPTION:
XS GIS Cut Line= 3
      2194290.74     13809246.54      2194004.32     13809069.48
      2193441.85     13809017.40
#Sta/Elev= 30
  4583.6 1014.43  4632.8 1013.64  4638.7 1012.51  4696.6 1009.30  4733.2 1008.78
  4769.9 1004.81  4821.9 1003.59  4849.1  999.83  4885.7  996.12  4901.1  995.37
  4919.8  991.94  4939.7  989.53  4977.9  988.48  4978.2  987.98  4981.9  988.48
  5030.1  989.76  5050.2  989.10  5070.3  989.62  5110.5  991.34  5128.6  993.29
  5133.6  992.80  5160.7  996.94  5200.8  999.08  5231.0 1001.64  5281.2 1009.85
  5321.4 1011.61  5347.5 1014.25  5391.7 1015.97  5451.9 1021.24  5485.2 1023.05
#Mann=3,-1,0
  4583.6    0.12       0  4977.9    0.05       0  4981.9    0.12       0
Bank Sta=4977.9,4981.9
Exp/Cntr=0.3,0.1

Type RM Length L Ch R = 1,6350,251,251,251
BEGIN DESCRIPTION:
West Fork Tributary 3 12.0
END DESCRIPTION:
XS GIS Cut Line= 3
      2194175.03     13809025.04      2194025.00     13808775.00
      2193775.05     13808824.99
#Sta/Elev= 30
  4708.4 1000.92  4711.4 1000.92  4716.2 1000.00  4722.1  999.74  4731.8  998.66
  4743.4  996.86  4753.2  995.87  4774.5  994.46  4780.4  994.60  4801.7  991.87
  4817.3  990.79  4848.4  987.93  4860.1  986.15  4869.8  985.44  4891.2  984.33
  4897.0  984.41  4941.7  982.65  4949.5  982.72  4955.3  982.18  4976.7  981.76
  4997.1  980.54  5008.2  980.36  5008.4  979.86  5011.9  979.86  5012.2  980.36
  5030.6  981.63  5051.0  982.49  5071.4  984.13  5163.2  988.21  5254.9  995.66
#Mann=3,-1,0
  4708.4    0.12       0  5008.2    0.05       0  5012.2    0.12       0
Bank Sta=5008.2,5012.2
Exp/Cntr=0.3,0.1

Type RM Length L Ch R = 1,6099,334,334,334
BEGIN DESCRIPTION:
H21715
END DESCRIPTION:
XS GIS Cut Line= 3
      2194566.84     13808668.45      2193926.19     13808522.61
      2193582.46     13808585.10
#Sta/Elev= 30
  4591.8 1000.56  4614.2  999.78  4629.7  998.57  4720.9  995.88  4778.3  992.12
  4807.0  988.96  4855.2  985.30  4921.9  977.87  4932.1  977.42  4941.2  977.88
  4946.4  976.91  4983.4  976.62  5001.9  975.28  5002.2  974.78  5005.7  974.78
  5005.9  975.28  5123.6  980.62  5171.8  981.21  5252.0  983.40  5260.2  984.15
  5361.9  986.36  5382.2  987.42  5392.3  987.15  5433.0  988.65  5458.1  990.44
  5504.1  992.57  5534.6  995.21  5564.9  996.51  5575.3  997.90  5598.2  999.06
#Mann=3,-1,0
  4591.8    0.12       0  5001.9    0.05       0  5005.9    0.12       0
Bank Sta=5001.9,5005.9
Exp/Cntr=0.3,0.1

Type RM Length L Ch R = 1,5765,304,304,304
BEGIN DESCRIPTION:
H21714
END DESCRIPTION:
XS GIS Cut Line= 2
      2194592.88     13808215.31      2193634.56     13808397.60
#Sta/Elev= 30
  4505.6 1003.83  4528.3 1002.14  4574.7  999.82  4582.0  998.80  4587.1  999.17
  4605.2  997.24  4639.3  995.49  4666.3  992.72  4686.4  989.76  4691.5  990.12
  4696.9  988.20  4743.7  980.99  4778.3  977.65  4951.3  971.14  4962.7  969.78
  5000.2  969.34  5000.5  968.84  5004.0  968.84  5004.2  969.34  5014.9  970.31
  5022.6  971.78  5042.9  971.66  5093.8  975.06  5134.6  976.69  5165.1  976.74
  5185.5  978.40  5246.5  980.41  5333.2  987.36  5399.2  989.75  5481.1  991.06
#Mann=4,-1,0
  4505.6   0.035       0  4528.3    0.12       0  5000.2    0.05       0
  5004.2    0.12       0
Bank Sta=5000.2,5004.2
Exp/Cntr=0.3,0.1

Type RM Length L Ch R = 1,5461,238,238,238
BEGIN DESCRIPTION:
West Fork Tributary 3 10.0
END DESCRIPTION:
XS GIS Cut Line= 3
      2194225.02     13807874.99      2193925.00     13808075.00
      2193675.02     13808324.98
#Sta/Elev= 30
  4639.4  978.45  4675.5  976.50  4689.0  975.25  4747.6  972.43  4776.1  971.80
  4797.2  972.35  4806.2  971.80  4812.2  972.36  4819.7  971.34  4863.3  970.57
  4869.3  970.96  4914.3  968.87  4920.4  968.97  4956.4  966.74  4969.4  966.74
  4969.7  966.24  4973.2  966.24  4973.4  966.74  4986.5  967.23  4992.5  966.80
  5003.5  967.10  5014.1  968.05  5028.3  970.18  5056.5  972.49  5183.8  979.00
  5226.3  981.70  5240.4  981.84  5268.7  983.80  5311.1  987.96  5353.5  990.36
#Mann=3,-1,0
  4639.4    0.12       0  4969.4    0.05       0  4973.4    0.12       0
Bank Sta=4969.4,4973.4
Exp/Cntr=0.3,0.1

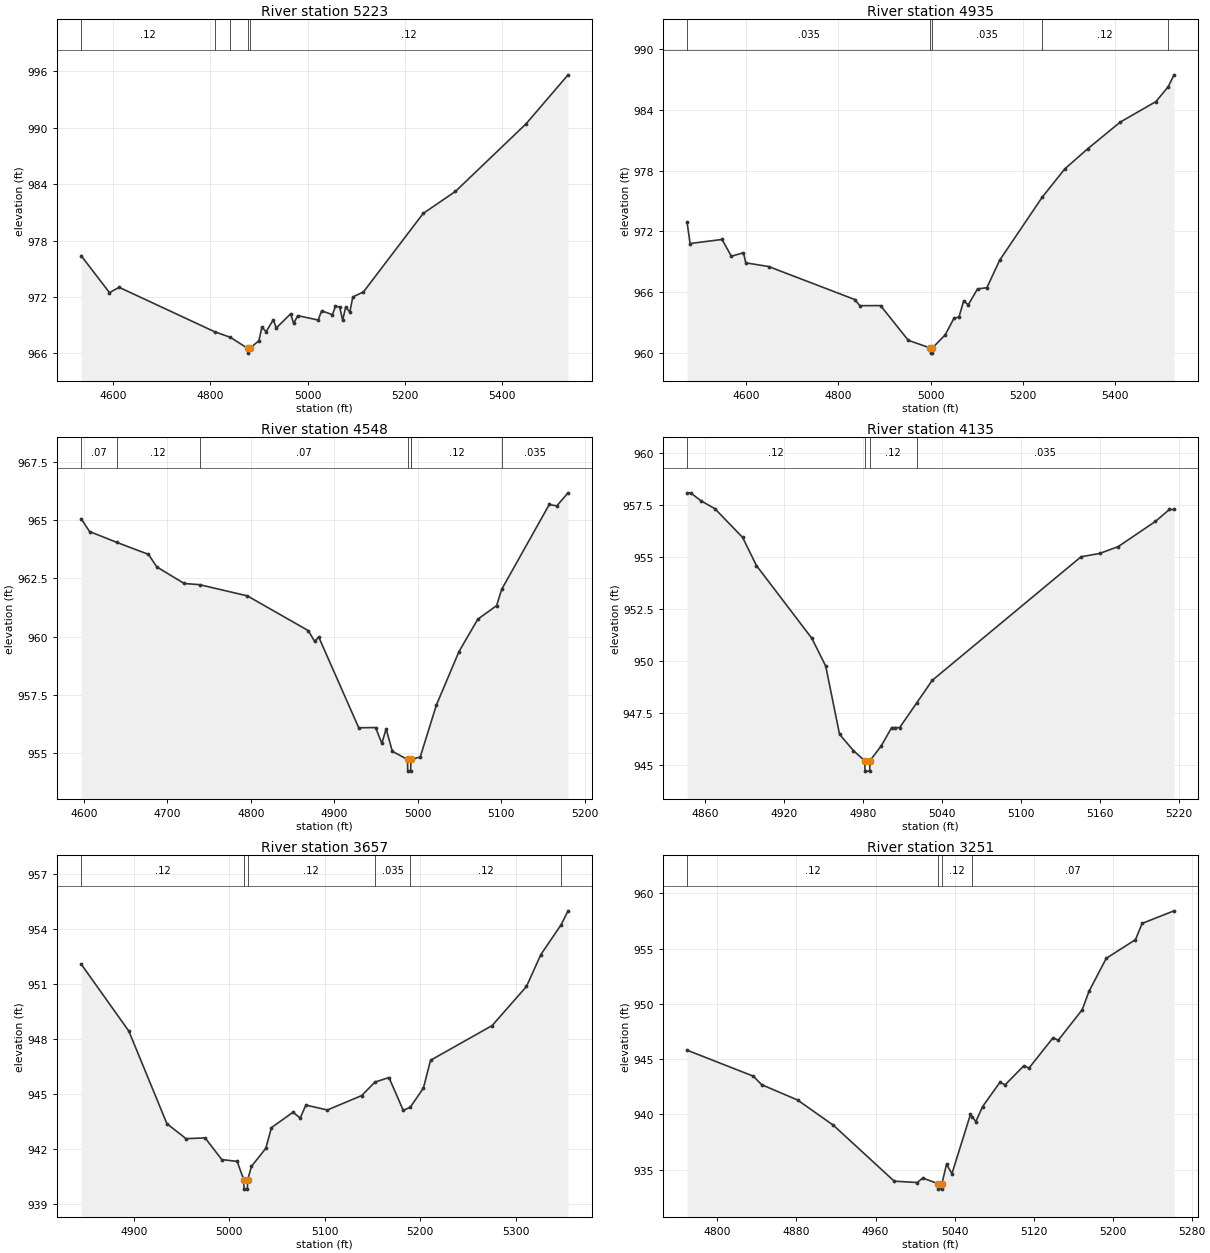
Type RM Length L Ch R = 1,5223,288,288,288
BEGIN DESCRIPTION:
H21713
END DESCRIPTION:
XS GIS Cut Line= 4
      2194223.09     13807777.81      2193920.98     13807793.44
      2193702.23     13807949.69      2193342.84     13808184.07
#Sta/Elev= 30
  4534.6  976.40  4592.8  972.47  4612.8  973.03  4809.1  968.30  4841.3  967.71
  4877.0  966.53  4877.2  966.03  4881.0  966.53  4899.9  967.36  4906.0  968.80
  4914.6  968.31  4929.4  969.58  4935.5  968.70  4965.0  970.21  4971.2  969.19
  4979.6  970.02  5021.6  969.55  5028.8  970.53  5051.0  970.12  5057.2  971.03
  5065.7  970.94  5071.9  969.54  5078.1  970.92  5086.7  970.42  5092.8  972.01
  5114.6  972.54  5237.3  980.89  5303.7  983.24  5448.6  990.42  5535.0  995.64
#Mann=5,-1,0
  4534.6    0.12       0  4809.1   0.035       0  4841.3    0.12       0
  4877.0    0.05       0  4881.0    0.12       0
Bank Sta=4877,4881
Exp/Cntr=0.3,0.1

Type RM Length L Ch R = 1,4935,387,387,387
BEGIN DESCRIPTION:
H21712
END DESCRIPTION:
XS GIS Cut Line= 4
      2194139.72     13807720.52      2193769.94     13807658.02
      2193499.11     13807673.65      2193208.71     13807964.05
#Sta/Elev= 30
  4471.6  972.87  4478.1  970.79  4547.4  971.19  4567.7  969.53  4593.9  969.88
  4599.0  968.88  4648.8  968.51  4835.6  965.25  4846.6  964.64  4891.6  964.65
  4951.7  961.22  4999.8  960.45  5000.1  959.95  5003.6  959.95  5003.8  960.45
  5031.9  961.76  5050.7  963.38  5061.9  963.54  5071.9  965.11  5082.0  964.73
  5102.0  966.30  5122.4  966.42  5150.1  969.14  5242.5  975.37  5291.5  978.17
  5341.0  980.15  5411.7  982.79  5489.5  984.83  5516.2  986.31  5528.6  987.47
#Mann=5,-1,0
  4471.6   0.035       0  4999.8   0.035       0  5003.8   0.035       0
  5242.5    0.12       0  5516.2    0.07       0
Bank Sta=4999.8,5003.8
Exp/Cntr=0.3,0.1

Type RM Length L Ch R = 1,4548,413,413,413
BEGIN DESCRIPTION:
West Fork Tributary 3 8.0
END DESCRIPTION:
XS GIS Cut Line= 3
      2193775.04     13807425.01      2193375.00     13807375.00
      2193275.02     13807524.97
#Sta/Elev= 30
  4596.6  965.06  4606.7  964.51  4639.6  964.04  4677.3  963.53  4687.3  962.99
  4720.1  962.28  4738.5  962.23  4795.7  961.75  4868.7  960.26  4876.3  959.80
  4881.3  959.98  4929.2  956.09  4949.4  956.10  4956.9  955.42  4962.0  956.04
  4969.5  955.08  4987.7  954.73  4987.9  954.23  4991.4  954.23  4991.7  954.73
  4992.1  954.74  5002.8  954.83  5022.3  957.07  5049.3  959.36  5071.9  960.75
  5094.4  961.33  5100.5  962.03  5157.5  965.67  5166.5  965.61  5180.0  966.17
#Mann=7,-1,0
  4596.6    0.07       0  4639.6    0.12       0  4738.5    0.07       0
  4987.7    0.05       0  4991.7    0.07       0  4992.1    0.12       0
  5100.5   0.035       0
Bank Sta=4987.7,4991.7
Exp/Cntr=0.3,0.1

Type RM Length L Ch R = 1,4135,478,478,478
BEGIN DESCRIPTION:
West Fork Tributary 3 7.0
END DESCRIPTION:
XS GIS Cut Line= 3
      2193424.99     13806975.00      2193275.00     13807025.00
      2193125.02     13807174.98
#Sta/Elev= 26
  4846.2  958.08  4848.8  958.08  4856.7  957.70  4867.3  957.32  4888.4  955.94
  4898.9  954.59  4941.1  951.09  4951.6  949.76  4962.1  946.49  4972.7  945.70
  4981.2  945.22  4981.5  944.72  4985.0  944.72  4985.2  945.22  4993.8  945.93
  5001.7  946.81  5004.3  946.81  5007.8  946.81  5020.7  947.99  5032.6  949.08
  5145.7  955.01  5159.9  955.17  5174.0  955.50  5202.3  956.71  5212.9  957.28
  5216.4  957.28
#Mann=4,-1,0
  4846.2    0.12       0  4981.2    0.05       0  4985.2    0.12       0
  5020.7   0.035       0
Bank Sta=4981.2,4985.2
Exp/Cntr=0.3,0.1

Type RM Length L Ch R = 1,3657,406,406,406
BEGIN DESCRIPTION:
West Fork Tributary 3 6.0
END DESCRIPTION:
XS GIS Cut Line= 3
      2193175.04     13806675.00      2193025.00     13806675.00
      2192725.00     13806875.00
#Sta/Elev= 30
  4844.5  952.07  4894.5  948.42  4934.5  943.37  4954.5  942.56  4974.5  942.60
  4992.0  941.42  5008.1  941.32  5015.1  940.31  5015.3  939.81  5018.8  939.81
  5019.1  940.31  5023.1  941.05  5038.1  942.03  5044.1  943.16  5066.7  944.00
  5074.2  943.68  5080.2  944.39  5102.7  944.12  5138.8  944.91  5152.6  945.64
  5167.3  945.89  5182.3  944.10  5189.6  944.27  5203.4  945.31  5210.9  946.83
  5275.5  948.72  5311.5  950.85  5326.6  952.59  5347.7  954.20  5355.1  954.97
#Mann=6,-1,0
  4844.5    0.12       0  5015.1    0.05       0  5019.1    0.12       0
  5152.6   0.035       0  5189.6    0.12       0  5347.7   0.035       0
Bank Sta=5015.1,5019.1
Exp/Cntr=0.3,0.1

Type RM Length L Ch R = 1,3251,426,426,426
BEGIN DESCRIPTION:
West Fork Tributary 3 5.0
END DESCRIPTION:
XS GIS Cut Line= 3
      2193074.97     13806474.98      2192875.00     13806375.00
      2192625.03     13806474.99
#Sta/Elev= 30
  4769.3  945.81  4836.3  943.46  4844.7  942.69  4881.1  941.30  4917.4  939.01
  4978.9  933.95  5002.3  933.83  5007.7  934.23  5023.2  933.73  5023.4  933.23
  5026.9  933.23  5027.2  933.73  5031.9  935.49  5037.3  934.62  5056.1  940.00
  5057.8  939.79  5061.5  939.34  5068.3  940.70  5085.8  942.89  5091.2  942.68
  5110.0  944.39  5115.4  944.20  5139.6  946.93  5145.0  946.72  5169.2  949.48
  5176.0  951.13  5193.5  954.13  5223.1  955.82  5229.8  957.29  5262.1  958.43
#Mann=4,-1,0
  4769.3    0.12       0  5023.2    0.05       0  5027.2    0.12       0
  5057.8    0.07       0
Bank Sta=5023.2,5027.2
Exp/Cntr=0.3,0.1

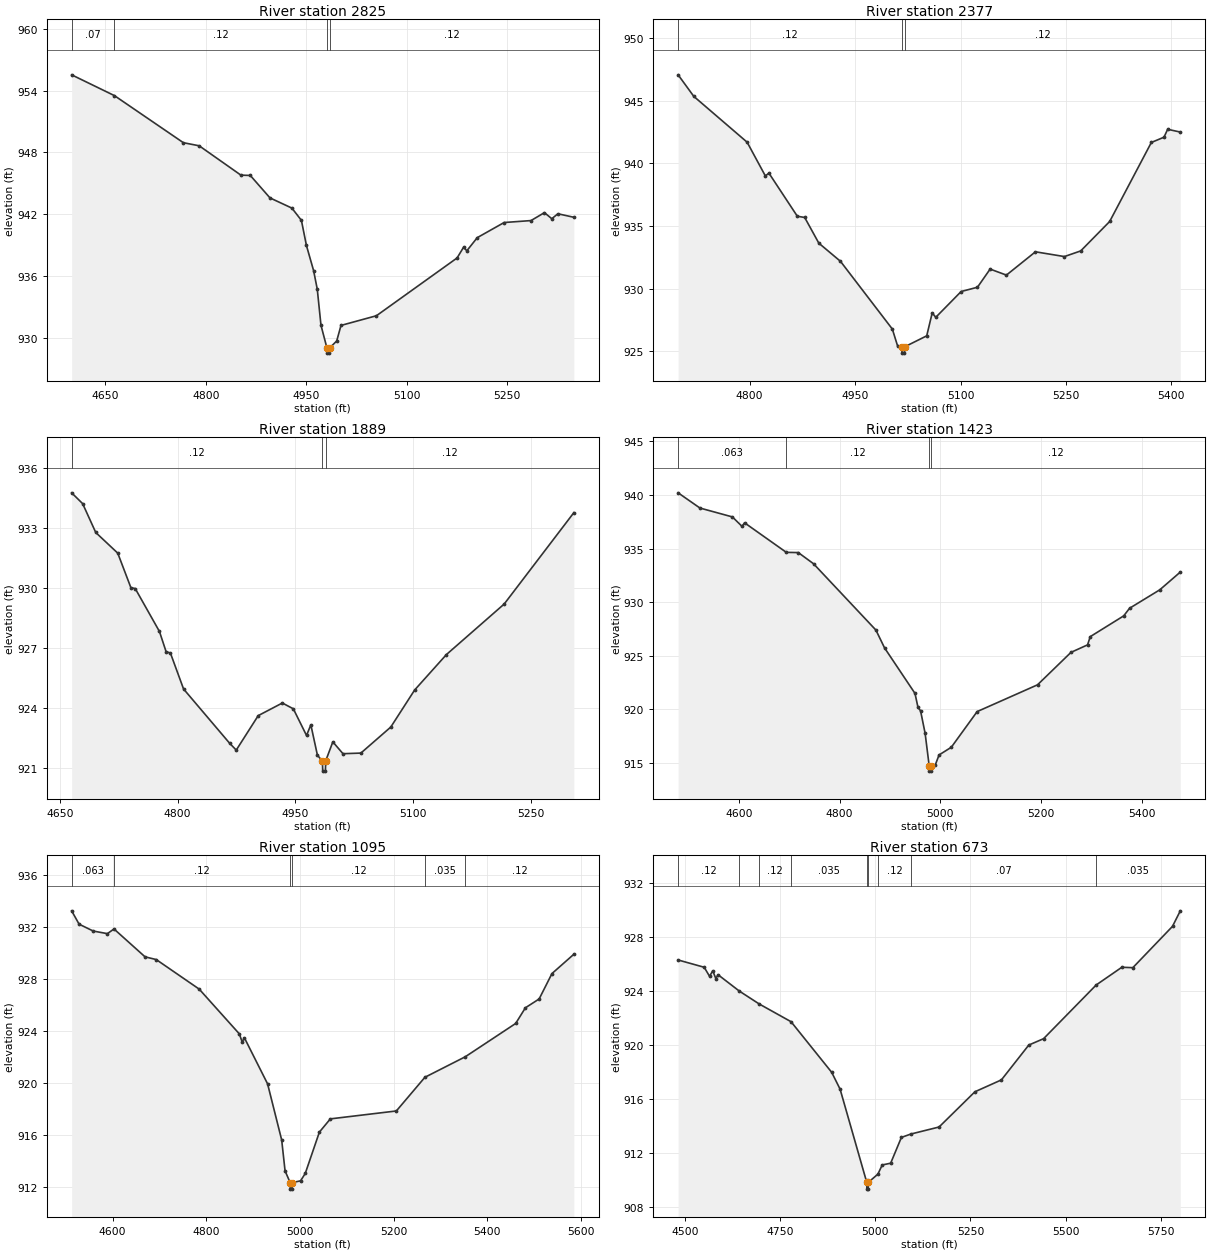
Type RM Length L Ch R = 1,2825,448,448,448
BEGIN DESCRIPTION:
West Fork Tributary 3 4.0
END DESCRIPTION:
XS GIS Cut Line= 3
      2193447.46     13806183.63      2193075.00     13806025.00
      2192731.28     13805997.00
#Sta/Elev= 30
  4599.7  955.54  4663.6  953.52  4766.5  948.95  4790.1  948.65  4852.4  945.80
  4866.4  945.77  4895.8  943.59  4928.5  942.60  4942.7  941.41  4950.2  938.97
  4960.9  936.53  4966.4  934.72  4971.9  931.23  4980.8  929.02  4981.1  928.52
  4984.6  928.52  4984.8  929.02  4995.4  929.70  5001.8  931.21  5054.7  932.15
  5175.1  937.76  5184.7  938.79  5189.7  938.46  5205.2  939.73  5245.3  941.20
  5285.5  941.39  5305.5  942.16  5316.5  941.57  5325.6  942.05  5349.4  941.71
#Mann=4,-1,0
  4599.7    0.07       0  4663.6    0.12       0  4980.8    0.05       0
  4984.8    0.12       0
Bank Sta=4980.8,4984.8
Exp/Cntr=0.3,0.1

Type RM Length L Ch R = 1,2377,488,488,488
BEGIN DESCRIPTION:
West Fork Tributary 3 3.0
END DESCRIPTION:
XS GIS Cut Line= 3
      2193521.28     13805684.51      2193225.00     13805625.00
      2192825.01     13805725.00
#Sta/Elev= 30
  4698.2  947.07  4720.5  945.35  4796.4  941.69  4822.3  939.00  4827.4  939.22
  4867.8  935.78  4878.3  935.68  4898.4  933.63  4929.2  932.18  5003.0  926.77
  5010.7  925.38  5016.4  925.35  5016.7  924.85  5020.2  924.85  5020.4  925.35
  5051.9  926.23  5059.7  928.06  5064.8  927.71  5100.9  929.77  5124.1  930.11
  5142.1  931.56  5165.3  931.08  5206.6  932.94  5247.8  932.56  5271.0  933.01
  5312.2  935.36  5371.5  941.67  5389.5  942.09  5394.7  942.72  5412.7  942.50
#Mann=3,-1,0
  4698.2    0.12       0  5016.4    0.05       0  5020.4    0.12       0
Bank Sta=5016.4,5020.4
Exp/Cntr=0.3,0.1

Type RM Length L Ch R = 1,1889,466,466,466
BEGIN DESCRIPTION:
West Fork Tributary 3 2.0
END DESCRIPTION:
XS GIS Cut Line= 3
      2193624.98     13805025.01      2193325.00     13805175.00
      2193025.03     13805125.00
#Sta/Elev= 30
  4665.1  934.74  4679.1  934.20  4695.8  932.76  4723.8  931.73  4740.5  930.01
  4746.1  929.96  4776.9  927.82  4785.3  926.82  4790.9  926.74  4807.6  924.95
  4866.3  922.24  4874.7  921.90  4902.7  923.62  4933.4  924.25  4947.4  923.96
  4964.2  922.63  4969.7  923.16  4978.1  921.64  4984.5  921.35  4984.8  920.85
  4988.3  920.85  4988.5  921.35  4997.7  922.31  5010.6  921.72  5033.4  921.75
  5071.5  923.05  5101.9  924.90  5142.4  926.67  5215.9  929.19  5304.6  933.75
#Mann=3,-1,0
  4665.1    0.12       0  4984.5    0.05       0  4988.5    0.12       0
Bank Sta=4984.5,4988.5
Exp/Cntr=0.3,0.1

Type RM Length L Ch R = 1,1423,328,328,328
BEGIN DESCRIPTION:
West Fork Tributary 3 1.0
END DESCRIPTION:
XS GIS Cut Line= 3
      2193891.94     13804664.87      2193375.00     13804725.00
      2192918.53     13804860.91
#Sta/Elev= 30
  4479.6  940.20  4522.9  938.78  4587.3  937.95  4606.4  937.07  4611.5  937.40
  4694.4  934.64  4718.1  934.62  4748.3  933.58  4872.2  927.38  4889.3  925.72
  4949.7  921.47  4955.7  920.16  4960.8  919.84  4969.8  917.75  4977.9  914.71
  4978.1  914.21  4981.6  914.21  4981.9  914.71  4990.0  914.79  4997.5  915.72
  5021.8  916.44  5073.1  919.77  5192.9  922.27  5259.3  925.30  5292.2  926.00
  5297.6  926.77  5364.0  928.71  5375.6  929.42  5435.5  931.14  5476.3  932.80
#Mann=4,-1,0
  4479.6   0.063       0  4694.4    0.12       0  4977.9    0.05       0
  4981.9    0.12       0
Bank Sta=4977.9,4981.9
Exp/Cntr=0.3,0.1

Type RM Length L Ch R = 1,1095,422,422,422
BEGIN DESCRIPTION:
H21711
END DESCRIPTION:
XS GIS Cut Line= 3
      2193810.82     13804360.68      2193124.73     13804435.04
      2192898.24     13804742.65
#Sta/Elev= 30
  4512.4  933.27  4528.3  932.24  4558.5  931.71  4588.7  931.51  4602.8  931.87
  4669.1  929.72  4693.0  929.51  4784.7  927.23  4870.3  923.78  4876.3  923.17
  4881.4  923.46  4930.7  919.92  4960.8  915.59  4968.0  913.21  4978.9  912.30
  4979.2  911.80  4982.7  911.80  4982.9  912.30  5001.1  912.44  5011.1  913.01
  5041.3  916.20  5064.7  917.22  5205.6  917.83  5266.6  920.43  5352.7  922.01
  5460.3  924.58  5481.1  925.79  5510.4  926.47  5537.8  928.43  5584.5  929.92
#Mann=6,-1,0
  4512.4   0.063       0  4602.8    0.12       0  4978.9    0.05       0
  4982.9    0.12       0  5266.6   0.035       0  5352.7    0.12       0
Bank Sta=4978.9,4982.9
Exp/Cntr=0.3,0.1

Type RM Length L Ch R = 1,673,464,464,464
BEGIN DESCRIPTION:
H21710
END DESCRIPTION:
XS GIS Cut Line= 3
      2193685.81     13803823.26      2192935.45     13804211.96
      2192834.05     13804675.03
#Sta/Elev= 30
  4482.2  926.28  4550.7  925.74  4564.8  925.07  4573.2  925.48  4581.3  924.90
  4587.0  925.19  4642.8  923.98  4695.3  923.02  4778.8  921.71  4885.6  917.96
  4907.7  916.71  4977.7  909.81  4978.0  909.31  4981.5  909.31  4981.7  909.81
  5007.0  910.42  5018.3  911.10  5040.5  911.23  5068.7  913.14  5093.6  913.39
  5167.6  913.91  5261.8  916.52  5331.4  917.40  5403.3  919.98  5442.1  920.45
  5580.4  924.43  5647.7  925.74  5676.6  925.71  5780.8  928.77  5801.3  929.92
#Mann=9,-1,0
  4482.2    0.12       0  4642.8    0.07       0  4695.3    0.12       0
  4778.8   0.035       0  4977.7   0.035       0  4981.7   0.035       0
  5007.0    0.12       0  5093.6    0.07       0  5580.4   0.035       0
Bank Sta=4977.7,4981.7
Exp/Cntr=0.3,0.1

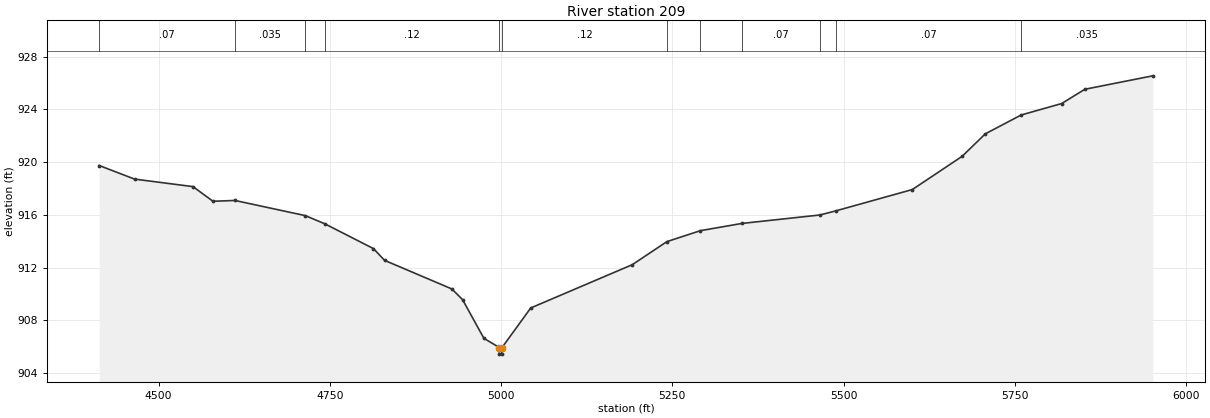
Type RM Length L Ch R = 1,209,0,0,0
BEGIN DESCRIPTION:
H21709
END DESCRIPTION:
XS GIS Cut Line= 4
      2193547.19     13803525.84      2192996.29     13803674.55
      2192709.00     13804215.34      2192807.00     13804556.66
#Sta/Elev= 30
  4413.3  919.75  4464.9  918.72  4550.2  918.15  4579.4  917.04  4611.5  917.10
  4714.3  915.95  4742.7  915.33  4813.7  913.45  4829.9  912.56  4928.2  910.39
  4943.8  909.58  4974.9  906.65  4997.4  905.95  4997.6  905.45  5001.1  905.45
  5001.4  905.95  5043.3  908.95  5191.5  912.23  5242.1  913.98  5291.0  914.81
  5351.8  915.36  5465.6  916.00  5489.3  916.32  5600.5  917.93  5673.2  920.45
  5706.9  922.15  5759.3  923.58  5818.5  924.45  5852.2  925.53  5951.4  926.55
#Mann=12,-1,0
  4413.3    0.07       0  4611.5   0.035       0  4714.3    0.07       0
  4742.7    0.12       0  4997.4    0.05       0  5001.4    0.12       0
  5242.1    0.07       0  5291.0    0.12       0  5351.8    0.07       0
  5465.6    0.12       0  5489.3    0.07       0  5759.3   0.035       0
Bank Sta=4997.4,5001.4
Exp/Cntr=0.3,0.1

Chan Stop Cuts=-1