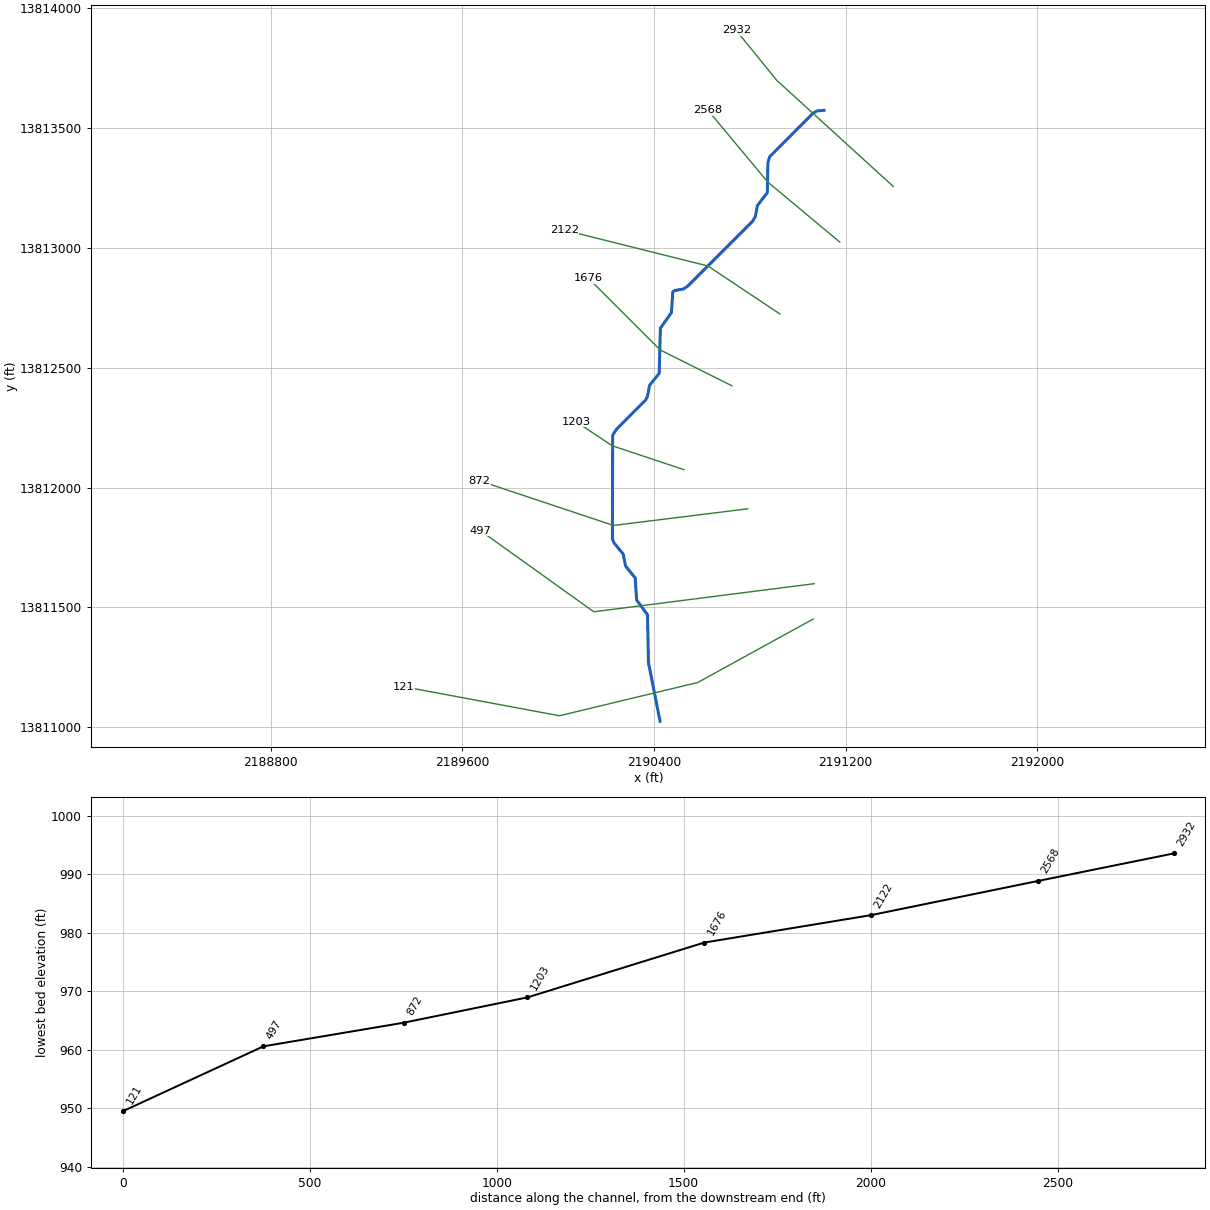
--- West Fork Tributary 4.prj (project) ---

Proj Title=West Fork Tributary 4 Base Level Engineering
Current Plan=p01
Default Exp/Contr=0.3,0.1
English Units
Geom File=g01
Flow File=f01
Plan File=p01
BEGIN DESCRIPTION:
West Fork Tributary 4
END DESCRIPTION:

--- West Fork Tributary 4.p01 (plan) ---

Plan Title=Multiple Run
Short Identifier=Multiple
Geom File=g01
Flow File=f01
Subcritical Flow
K Sum by GR= 0
Std Step Tol= 0.01
Critical Tol= 0.01
Num of Std Step Trials= 20
Max Error Tol= 0.3
Flow Tol Ratio= 0.001
Split Flow NTrial= 30
Split Flow Tol= 0.02
Split Flow Ratio= 0.02
Log Output Level= 0
Friction Slope Method= 1
Unsteady Friction Slope Method= 2
Unsteady Bridges Friction Slope Method= 1
Parabolic Critical Depth
Global Vel Dist=  1 , 1 , 1
Global Log Level= 0
CheckData=True
Encroach Param= -1, 0, 0, 0
BEGIN DESCRIPTION:
Multiple Run
END DESCRIPTION:

--- West Fork Tributary 4.f01 (steady flow) ---

Flow Title=Multiple
Number of Profiles=7
Profile Names=10-year,25-year,50-year,1pct_min,100-year,1pct_plu,500-year
River Rch & RM= West Fork Tribut,Reach-1,2932
     902    1516    2098    1409    2810    5608    4985
River Rch & RM= West Fork Tribut,Reach-1,121
    4924    8671   12350    8459   16879   33677   31235
Boundary for River Rch & Prof#=West Fork Tribut,Reach-1,1
Up Type=0
Dn Type=3
Dn Slope=0.005
Boundary for River Rch & Prof#=West Fork Tribut,Reach-1,2
Up Type=0
Dn Type=3
Dn Slope=0.005
Boundary for River Rch & Prof#=West Fork Tribut,Reach-1,3
Up Type=0
Dn Type=3
Dn Slope=0.005
Boundary for River Rch & Prof#=West Fork Tribut,Reach-1,4
Up Type=0
Dn Type=3
Dn Slope=0.005
Boundary for River Rch & Prof#=West Fork Tribut,Reach-1,5
Up Type=0
Dn Type=3
Dn Slope=0.005
Boundary for River Rch & Prof#=West Fork Tribut,Reach-1,6
Up Type=0
Dn Type=3
Dn Slope=0.005
Boundary for River Rch & Prof#=West Fork Tribut,Reach-1,7
Up Type=0
Dn Type=3
Dn Slope=0.005

--- West Fork Tributary 4.g01 (geometry) ---

Geom Title=Existing Conditions

River Reach=West Fork Tribut,Reach-1
Reach XY= 30
      2191109.40     13813575.00      2191079.57     13813572.05
      2191061.77     13813561.41      2190882.82     13813381.19
      2190875.11     13813356.77      2190872.75     13813230.93
      2190831.14     13813177.17      2190822.50     13813131.03
      2190811.38     13813111.78      2190541.45     13812841.74
      2190522.92     13812829.15      2190486.74     13812823.00
      2190478.16     13812816.66      2190472.49     13812730.66
      2190426.38     13812665.34      2190421.25     13812476.55
      2190381.14     13812427.17      2190372.50     13812381.03
      2190364.24     13812365.32      2190244.61     13812245.16
      2190227.06     13812219.15      2190226.20     13811785.50
      2190233.09     13811768.92      2190270.81     13811723.26
      2190281.11     13811672.82      2190321.17     13811623.42
      2190327.36     13811530.98      2190372.62     13811469.47
      2190376.55     13811270.15      2190425.00     13811025.00

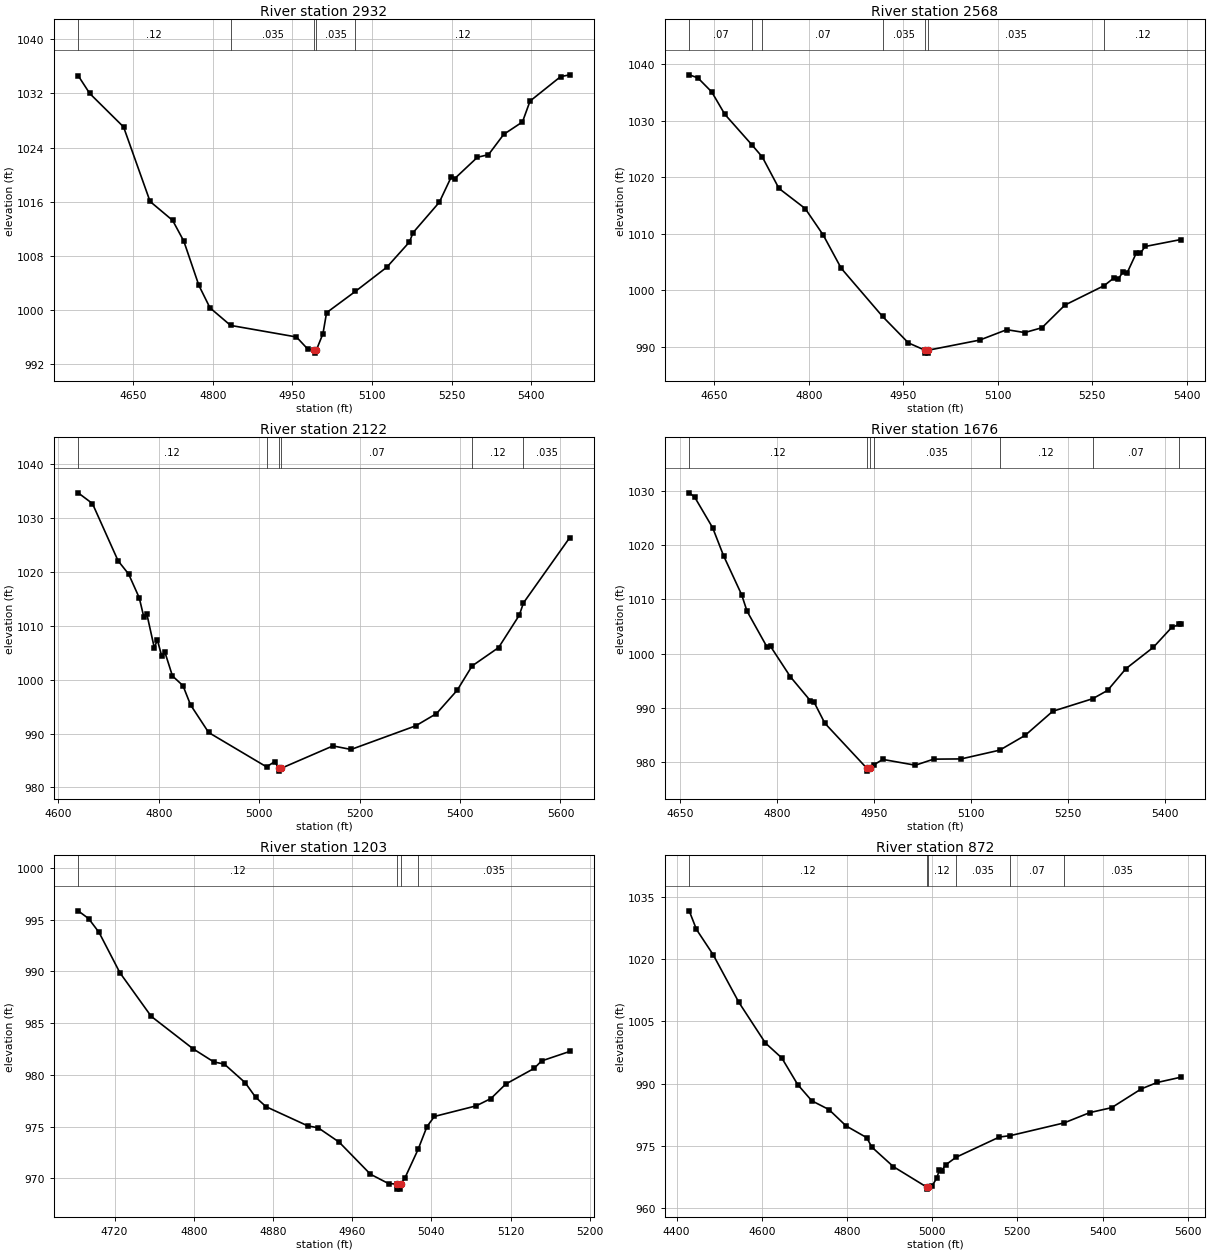
Type RM Length L Ch R = 1,2932,364,364,364
BEGIN DESCRIPTION:
H21720
END DESCRIPTION:
XS GIS Cut Line= 3
      2191398.31     13813257.12      2190912.18     13813699.84
      2190742.94     13813908.14
#Sta/Elev= 30
  4546.5 1034.64  4568.4 1031.99  4632.1 1027.04  4682.0 1016.02  4724.5 1013.22
  4745.5 1010.16  4773.9 1003.61  4794.8 1000.29  4833.6  997.69  4957.6  995.98
  4979.3  994.16  4991.4  994.09  4991.7  993.59  4995.4  994.09  5007.6  996.47
  5014.4  999.57  5068.5 1002.71  5127.9 1006.30  5170.5 1010.03  5177.2 1011.40
  5226.7 1015.90  5249.0 1019.61  5255.4 1019.38  5298.5 1022.56  5319.3 1022.94
  5348.1 1025.95  5383.3 1027.78  5397.6 1030.87  5455.1 1034.48  5472.4 1034.75
#Mann=5,-1,0
  4546.5    0.12       0  4833.6   0.035       0  4991.4   0.035       0
  4995.4   0.035       0  5068.5    0.12       0
Bank Sta=4991.4,4995.4
Exp/Cntr=0.3,0.1

Type RM Length L Ch R = 1,2568,446,446,446
BEGIN DESCRIPTION:
West Fork Tributary 4 5.0
END DESCRIPTION:
XS GIS Cut Line= 3
      2191175.02     13813024.99      2190875.00     13813275.00
      2190625.03     13813574.96
#Sta/Elev= 30
  4609.9 1038.14  4623.6 1037.61  4645.7 1035.11  4666.5 1031.15  4709.6 1025.73
  4726.0 1023.60  4752.5 1018.03  4794.1 1014.47  4822.8 1009.78  4851.4 1003.89
  4917.0  995.37  4958.1  990.68  4984.8  989.37  4985.0  988.87  4988.5  988.87
  4988.8  989.37  5071.4  991.18  5114.3  993.02  5143.0  992.51  5170.3  993.37
  5206.8  997.38  5269.1 1000.82  5284.9 1002.21  5291.4 1001.98  5299.2 1003.27
  5305.7 1003.11  5320.0 1006.55  5326.5 1006.56  5334.3 1007.75  5390.9 1008.98
#Mann=7,-1,0
  4609.9    0.07       0  4709.6    0.12       0  4726.0    0.07       0
  4917.0   0.035       0  4984.8   0.035       0  4988.8   0.035       0
  5269.1    0.12       0
Bank Sta=4984.8,4988.8
Exp/Cntr=0.3,0.1

Type RM Length L Ch R = 1,2122,446,446,446
BEGIN DESCRIPTION:
West Fork Tributary 4 4.0
END DESCRIPTION:
XS GIS Cut Line= 3
      2190924.98     13812725.02      2190625.00     13812925.00
      2190024.99     13813075.00
#Sta/Elev= 30
  4639.5 1034.68  4668.0 1032.69  4719.1 1022.06  4740.1 1019.60  4761.2 1015.20
  4770.2 1011.68  4776.2 1012.24  4791.2 1005.92  4797.2 1007.37  4806.2 1004.35
  4812.2 1005.14  4827.3 1000.70  4848.3  998.89  4863.3  995.34  4899.4  990.20
  5014.7  983.82  5030.9  984.79  5039.3  983.53  5039.5  983.03  5043.3  983.53
  5146.9  987.71  5183.0  987.05  5311.8  991.44  5353.1  993.71  5394.3  998.04
  5424.0 1002.55  5476.8 1005.96  5518.0 1011.97  5526.3 1014.25  5618.5 1026.37
#Mann=6,-1,0
  4639.5    0.12       0  5014.7    0.07       0  5039.3    0.05       0
  5043.3    0.07       0  5424.0    0.12       0  5526.3   0.035       0
Bank Sta=5039.3,5043.3
Exp/Cntr=0.3,0.1

Type RM Length L Ch R = 1,1676,473,473,473
BEGIN DESCRIPTION:
West Fork Tributary 4 3.0
END DESCRIPTION:
XS GIS Cut Line= 3
      2190724.99     13812425.01      2190425.00     13812575.00
      2190124.97     13812875.03
#Sta/Elev= 30
  4664.6 1029.64  4673.0 1028.86  4700.9 1023.19  4717.7 1018.05  4745.6 1010.87
  4754.0 1007.82  4784.8 1001.23  4790.4 1001.32  4821.1  995.71  4851.9  991.31
  4857.4  991.09  4874.2  987.17  4939.3  978.84  4939.6  978.34  4943.3  978.84
  4949.4  979.45  4963.7  980.50  5014.1  979.43  5042.4  980.55  5084.9  980.59
  5144.5  982.21  5183.8  984.94  5226.3  989.37  5288.1  991.69  5311.1  993.22
  5339.4  997.22  5381.8 1001.16  5410.1 1004.82  5422.2 1005.41  5424.3 1005.41
#Mann=7,-1,0
  4664.6    0.12       0  4939.3   0.035       0  4943.3    0.12       0
  4949.4   0.035       0  5144.5    0.12       0  5288.1    0.07       0
  5422.2    0.12       0
Bank Sta=4939.3,4943.3
Exp/Cntr=0.3,0.1

Type RM Length L Ch R = 1,1203,331,331,331
BEGIN DESCRIPTION:
West Fork Tributary 4 2.0
END DESCRIPTION:
XS GIS Cut Line= 3
      2190525.04     13812074.99      2190225.00     13812175.00
      2190075.04     13812274.98
#Sta/Elev= 30
  4683.2  995.84  4693.8  995.09  4704.3  993.76  4725.4  989.86  4757.0  985.65
  4799.2  982.52  4820.3  981.24  4830.8  981.04  4851.9  979.24  4862.4  977.84
  4873.0  976.92  4915.1  975.07  4925.7  974.88  4946.8  973.50  4978.4  970.40
  4996.8  969.49  5005.0  969.46  5005.2  968.96  5008.7  968.96  5009.0  969.46
  5013.0  969.99  5026.5  972.79  5035.5  975.00  5043.0  975.98  5085.1  977.00
  5100.1  977.71  5115.1  979.11  5143.7  980.62  5151.2  981.34  5179.7  982.26
#Mann=4,-1,0
  4683.2    0.12       0  5005.0    0.05       0  5009.0    0.12       0
  5026.5   0.035       0
Bank Sta=5005,5009
Exp/Cntr=0.3,0.1

Type RM Length L Ch R = 1,872,375,375,375
BEGIN DESCRIPTION:
H21719
END DESCRIPTION:
XS GIS Cut Line= 3
      2190790.63     13811911.64      2190230.76     13811842.20
      2189670.90     13812028.82
#Sta/Elev= 30
  4429.5 1031.65  4446.6 1027.16  4485.6 1021.11  4546.0 1009.63  4608.4  999.82
  4646.8  996.23  4684.3  989.80  4717.3  985.91  4757.6  983.79  4797.9  979.85
  4846.2  977.03  4858.4  974.74  4908.8  970.05  4987.0  965.13  4987.3  964.63
  4991.0  965.13  4999.7  965.42  5010.3  967.19  5016.9  969.22  5022.2  969.08
  5031.4  970.45  5056.1  972.31  5157.8  977.18  5183.4  977.51  5309.5  980.57
  5370.1  983.06  5421.4  984.25  5491.3  988.79  5528.2  990.31  5583.8  991.58
#Mann=6,-1,0
  4429.5    0.12       0  4987.0    0.05       0  4991.0    0.12       0
  5056.1   0.035       0  5183.4    0.07       0  5309.5   0.035       0
Bank Sta=4987,4991
Exp/Cntr=0.3,0.1

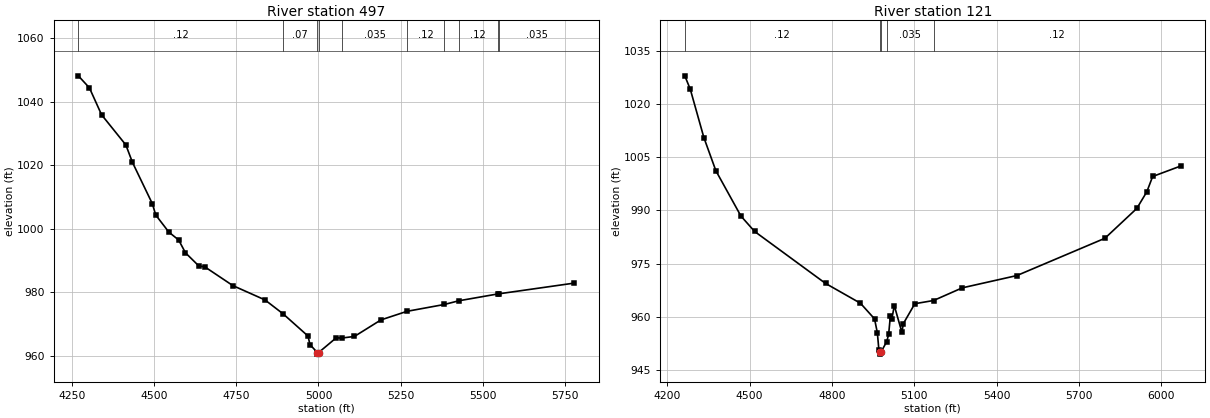
Type RM Length L Ch R = 1,497,376,376,376
BEGIN DESCRIPTION:
H21718
END DESCRIPTION:
XS GIS Cut Line= 3
      2191068.42     13811599.14      2190148.29     13811481.96
      2189675.53     13811820.26
#Sta/Elev= 30
  4269.2 1048.22  4302.9 1044.44  4339.9 1035.96  4413.8 1026.46  4433.9 1020.97
  4494.4 1007.96  4504.7 1004.40  4544.8  999.00  4574.5  996.53  4595.2  992.50
  4635.6  988.38  4654.4  988.05  4739.4  982.17  4837.2  977.66  4892.4  973.27
  4968.2  966.28  4974.0  963.61  4996.5  961.09  4996.7  960.59  5000.5  961.09
  5053.9  965.72  5071.4  965.66  5109.4  966.16  5190.0  971.36  5269.4  974.07
  5382.9  976.22  5427.2  977.39  5545.2  979.53  5550.3  979.60  5778.1  982.95
#Mann=10,-1,0
  4269.2    0.12       0  4892.4    0.07       0  4996.5    0.05       0
  5000.5    0.07       0  5071.4   0.035       0  5269.4    0.12       0
  5382.9    0.07       0  5427.2    0.12       0  5545.2    0.07       0
  5550.3   0.035       0
Bank Sta=4996.5,5000.5
Exp/Cntr=0.3,0.1

Type RM Length L Ch R = 1,121,0,0,0
BEGIN DESCRIPTION:
H21717
END DESCRIPTION:
XS GIS Cut Line= 4
      2191064.11     13811451.59      2190582.32     13811186.82
      2190005.06     13811047.93      2189353.99     13811169.46
#Sta/Elev= 30
  4264.1 1027.87  4284.2 1024.06  4333.5 1010.50  4377.2 1001.15  4468.5  988.38
  4518.2  984.05  4776.6  969.41  4903.7  963.83  4955.1  959.42  4965.4  955.49
  4970.9  950.75  4974.0  949.99  4974.3  949.49  4978.0  949.99  4999.6  953.02
  5006.5  955.08  5012.8  960.19  5018.0  959.32  5027.1  963.16  5054.8  955.61
  5059.9  958.06  5101.9  963.69  5170.0  964.59  5274.8  968.16  5473.6  971.62
  5794.2  982.12  5910.3  990.52  5946.8  995.21  5968.0  999.52  6069.9 1002.46
#Mann=5,-1,0
  4264.1    0.12       0  4974.0   0.035       0  4978.0    0.12       0
  4999.6   0.035       0  5170.0    0.12       0
Bank Sta=4974,4978
Exp/Cntr=0.3,0.1

Chan Stop Cuts=-1