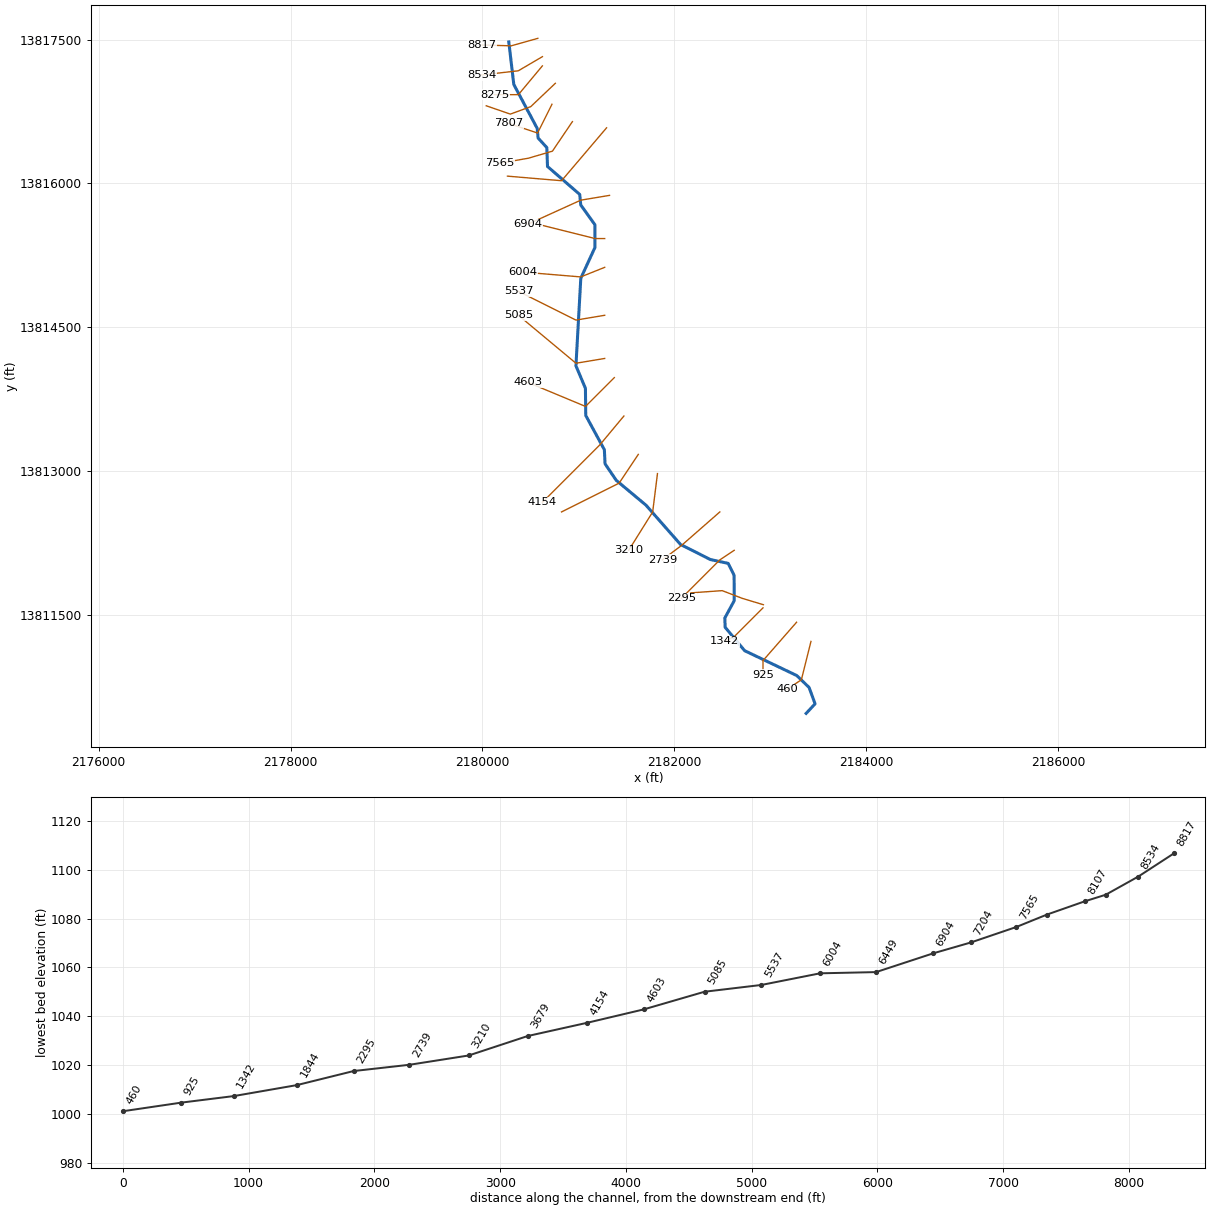
--- West Fork Tributary 5.prj (project) ---

Proj Title=West Fork Tributary 5 Base Level Engineering
Current Plan=p01
Default Exp/Contr=0.3,0.1
English Units
Geom File=g01
Flow File=f01
Plan File=p01
BEGIN DESCRIPTION:
West Fork Tributary 5
END DESCRIPTION:

--- West Fork Tributary 5.p01 (plan) ---

Plan Title=Multiple Run
Short Identifier=Multiple
Geom File=g01
Flow File=f01
Subcritical Flow
K Sum by GR= 0
Std Step Tol= 0.01
Critical Tol= 0.01
Num of Std Step Trials= 20
Max Error Tol= 0.3
Flow Tol Ratio= 0.001
Split Flow NTrial= 30
Split Flow Tol= 0.02
Split Flow Ratio= 0.02
Log Output Level= 0
Friction Slope Method= 1
Unsteady Friction Slope Method= 2
Unsteady Bridges Friction Slope Method= 1
Parabolic Critical Depth
Global Vel Dist=  1 , 1 , 1
Global Log Level= 0
CheckData=True
Encroach Param= -1, 0, 0, 0
BEGIN DESCRIPTION:
Multiple Run
END DESCRIPTION:

--- West Fork Tributary 5.f01 (steady flow) ---

Flow Title=Multiple
Number of Profiles=7
Profile Names=10-year,25-year,50-year,1pct_min,100-year,1pct_plu,500-year
River Rch & RM= West Fork Tribut,Reach-1,8817
     533     868    1176     775    1547    3087    2640
River Rch & RM= West Fork Tribut,Reach-1,6904
    1026    1722    2377    1588    3169    6324    5576
Boundary for River Rch & Prof#=West Fork Tribut,Reach-1,1
Up Type=0
Dn Type=3
Dn Slope=0.005
Boundary for River Rch & Prof#=West Fork Tribut,Reach-1,2
Up Type=0
Dn Type=3
Dn Slope=0.005
Boundary for River Rch & Prof#=West Fork Tribut,Reach-1,3
Up Type=0
Dn Type=3
Dn Slope=0.005
Boundary for River Rch & Prof#=West Fork Tribut,Reach-1,4
Up Type=0
Dn Type=3
Dn Slope=0.005
Boundary for River Rch & Prof#=West Fork Tribut,Reach-1,5
Up Type=0
Dn Type=3
Dn Slope=0.005
Boundary for River Rch & Prof#=West Fork Tribut,Reach-1,6
Up Type=0
Dn Type=3
Dn Slope=0.005
Boundary for River Rch & Prof#=West Fork Tribut,Reach-1,7
Up Type=0
Dn Type=3
Dn Slope=0.005

--- West Fork Tributary 5.g01 (geometry) ---

Geom Title=Existing Conditions

River Reach=West Fork Tribut,Reach-1
Reach XY= 30
      2180275.00     13817475.00      2180327.26     13817030.94
      2180571.17     13816573.41      2180580.54     13816472.58
      2180671.45     13816373.53      2180678.53     13816176.45
      2181014.57     13815884.82      2181025.00     13815775.00
      2181172.94     13815569.14      2181172.74     13815330.94
      2181025.67     13815011.09      2180974.90     13814097.69
      2181073.78     13813864.50      2181077.38     13813580.53
      2181271.24     13813223.44      2181278.55     13813076.47
      2181394.79     13812904.91      2181705.16     13812645.39
      2182065.32     13812235.76      2182376.56     13812078.76
      2182561.56     13812038.64      2182623.80     13811914.50
      2182625.21     13811649.91      2182527.26     13811469.44
      2182530.40     13811372.57      2182733.50     13811128.55
      2183277.30     13810869.17      2183405.38     13810745.16
      2183467.79     13810574.70      2183375.00     13810475.00

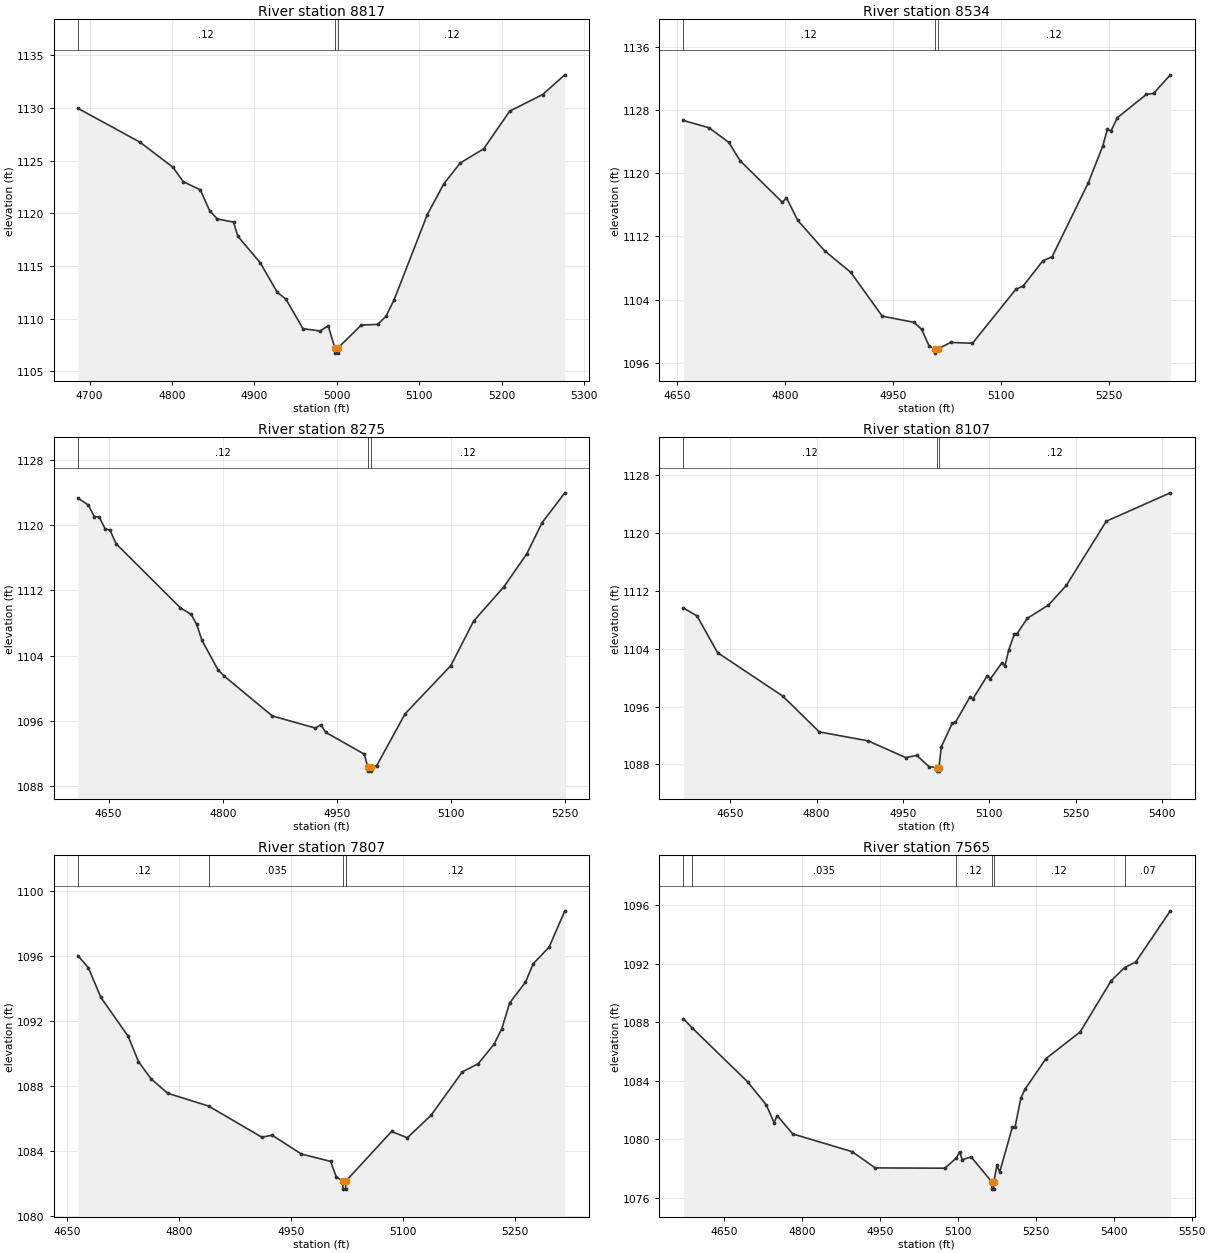
Type RM Length L Ch R = 1,8817,283,283,283
BEGIN DESCRIPTION:
West Fork Tributary 5 19.0
END DESCRIPTION:
XS GIS Cut Line= 3
      2180577.91     13817512.22      2180300.12     13817434.09
      2179998.11     13817442.72
#Sta/Elev= 30
  4685.8 1129.97  4761.5 1126.74  4801.3 1124.36  4813.5 1123.01  4834.3 1122.23
  4845.8 1120.23  4855.0 1119.47  4874.6 1119.17  4879.8 1117.83  4907.0 1115.31
  4927.7 1112.50  4938.1 1111.86  4958.9 1109.05  4979.5 1108.84  4989.5 1109.31
  4997.5 1107.23  4997.8 1106.73  5001.3 1106.73  5001.5 1107.23  5029.5 1109.39
  5049.5 1109.46  5059.5 1110.22  5069.5 1111.81  5109.5 1119.85  5129.6 1122.79
  5149.6 1124.78  5178.0 1126.12  5209.6 1129.70  5249.6 1131.28  5276.5 1133.15
#Mann=3,-1,0
  4685.8    0.12       0  4997.5    0.05       0  5001.5    0.12       0
Bank Sta=4997.5,5001.5
Exp/Cntr=0.3,0.1

Type RM Length L Ch R = 1,8534,259,259,259
BEGIN DESCRIPTION:
H21723
END DESCRIPTION:
XS GIS Cut Line= 3
      2180625.62     13817321.23      2180373.91     13817173.67
      2179991.94     13817130.26
#Sta/Elev= 30
  4659.0 1126.66  4694.5 1125.74  4722.1 1123.89  4737.8 1121.57  4796.4 1116.32
  4802.2 1116.87  4817.9 1114.02  4855.1 1110.19  4891.5 1107.45  4935.2 1101.91
  4979.1 1101.14  4989.9 1100.24  5000.0 1098.20  5008.1 1097.74  5008.3 1097.24
  5012.1 1097.74  5030.2 1098.60  5060.4 1098.48  5120.8 1105.32  5130.8 1105.72
  5158.2 1108.91  5171.1 1109.43  5221.4 1118.80  5241.5 1123.46  5247.8 1125.55
  5252.8 1125.33  5261.7 1127.01  5301.9 1129.95  5312.0 1130.08  5335.2 1132.43
#Mann=3,-1,0
  4659.0    0.12       0  5008.1    0.05       0  5012.1    0.12       0
Bank Sta=5008.1,5012.1
Exp/Cntr=0.3,0.1

Type RM Length L Ch R = 1,8275,168,168,168
BEGIN DESCRIPTION:
West Fork Tributary 5 18.0
END DESCRIPTION:
XS GIS Cut Line= 3
      2180624.99     13817224.99      2180375.00     13816925.00
      2180125.00     13816925.00
#Sta/Elev= 30
  4609.5 1123.35  4623.2 1122.51  4631.0 1121.09  4637.5 1121.03  4645.3 1119.58
  4651.8 1119.41  4659.6 1117.76  4744.2 1109.88  4758.5 1109.05  4765.7 1107.85
  4772.8 1105.85  4793.7 1102.27  4801.5 1101.51  4865.3 1096.57  4921.9 1095.08
  4929.1 1095.49  4935.6 1094.55  4986.3 1091.87  4990.8 1090.29  4991.1 1089.79
  4994.6 1089.79  4994.8 1090.29  5002.5 1090.46  5040.0 1096.85  5100.0 1102.76
  5130.0 1108.23  5170.0 1112.47  5200.0 1116.51  5220.0 1120.32  5250.0 1124.00
#Mann=3,-1,0
  4609.5    0.12       0  4990.8    0.05       0  4994.8    0.12       0
Bank Sta=4990.8,4994.8
Exp/Cntr=0.3,0.1

Type RM Length L Ch R = 1,8107,300,300,300
BEGIN DESCRIPTION:
H21722
END DESCRIPTION:
XS GIS Cut Line= 4
      2180760.22     13817043.49      2180504.11     13816800.41
      2180291.44     13816722.28      2180039.85     13816809.04
#Sta/Elev= 30
  4568.5 1109.66  4592.2 1108.56  4627.8 1103.48  4741.1 1097.46  4804.6 1092.50
  4889.5 1091.26  4954.9 1088.94  4973.9 1089.25  4995.2 1087.69  5008.5 1087.57
  5008.7 1087.07  5012.2 1087.07  5012.5 1087.57  5016.5 1090.42  5035.7 1093.74
  5041.0 1093.83  5066.1 1097.30  5071.5 1097.08  5096.6 1100.30  5101.9 1099.85
  5121.8 1102.07  5127.1 1101.66  5133.7 1103.85  5143.6 1106.10  5148.2 1106.10
  5165.6 1108.21  5202.6 1110.06  5233.8 1112.79  5303.1 1121.67  5414.3 1125.60
#Mann=3,-1,0
  4568.5    0.12       0  5008.5    0.05       0  5012.5    0.12       0
Bank Sta=5008.5,5012.5
Exp/Cntr=0.3,0.1

Type RM Length L Ch R = 1,7807,242,242,242
BEGIN DESCRIPTION:
West Fork Tributary 5 17.0
END DESCRIPTION:
XS GIS Cut Line= 3
      2180725.02     13816825.04      2180575.00     13816525.00
      2180274.98     13816625.01
#Sta/Elev= 30
  4664.5 1096.02  4678.5 1095.28  4695.3 1093.45  4731.6 1091.07  4745.6 1089.50
  4762.4 1088.44  4784.7 1087.55  4839.6 1086.76  4910.5 1084.85  4924.5 1084.97
  4963.6 1083.81  5002.6 1083.36  5010.5 1082.39  5019.0 1082.15  5019.3 1081.65
  5022.8 1081.65  5023.0 1082.15  5023.9 1082.18  5084.3 1085.20  5105.4 1084.81
  5137.0 1086.19  5179.1 1088.87  5200.2 1089.37  5221.3 1090.56  5231.9 1091.53
  5242.4 1093.11  5263.5 1094.39  5274.0 1095.53  5295.1 1096.54  5316.2 1098.78
#Mann=5,-1,0
  4664.5    0.12       0  4839.6   0.035       0  5019.0   0.035       0
  5023.0   0.035       0  5023.9    0.12       0
Bank Sta=5019,5023
Exp/Cntr=0.3,0.1

Type RM Length L Ch R = 1,7565,361,361,361
BEGIN DESCRIPTION:
H21721
END DESCRIPTION:
XS GIS Cut Line= 4
      2180938.15     13816644.17      2180729.81     13816336.00
      2180478.07     13816262.21      2180179.27     13816210.25
#Sta/Elev= 30
  4571.3 1088.24  4587.8 1087.62  4695.0 1083.92  4731.0 1082.34  4745.9 1081.13
  4752.0 1081.61  4781.9 1080.36  4896.2 1079.15  4940.7 1078.04  5074.9 1078.02
  5097.0 1078.72  5103.1 1079.14  5108.3 1078.60  5125.4 1078.79  5165.1 1077.09
  5165.4 1076.59  5168.9 1076.59  5169.1 1077.09  5175.1 1078.23  5180.3 1077.75
  5204.6 1080.80  5209.7 1080.80  5221.2 1082.82  5229.0 1083.41  5269.6 1085.51
  5335.4 1087.33  5395.1 1090.83  5420.8 1091.72  5442.2 1092.10  5508.9 1095.60
#Mann=6,-1,0
  4571.3    0.12       0  4587.8   0.035       0  5097.0    0.12       0
  5165.1   0.035       0  5169.1    0.12       0  5420.8    0.07       0
Bank Sta=5165.1,5169.1
Exp/Cntr=0.3,0.1

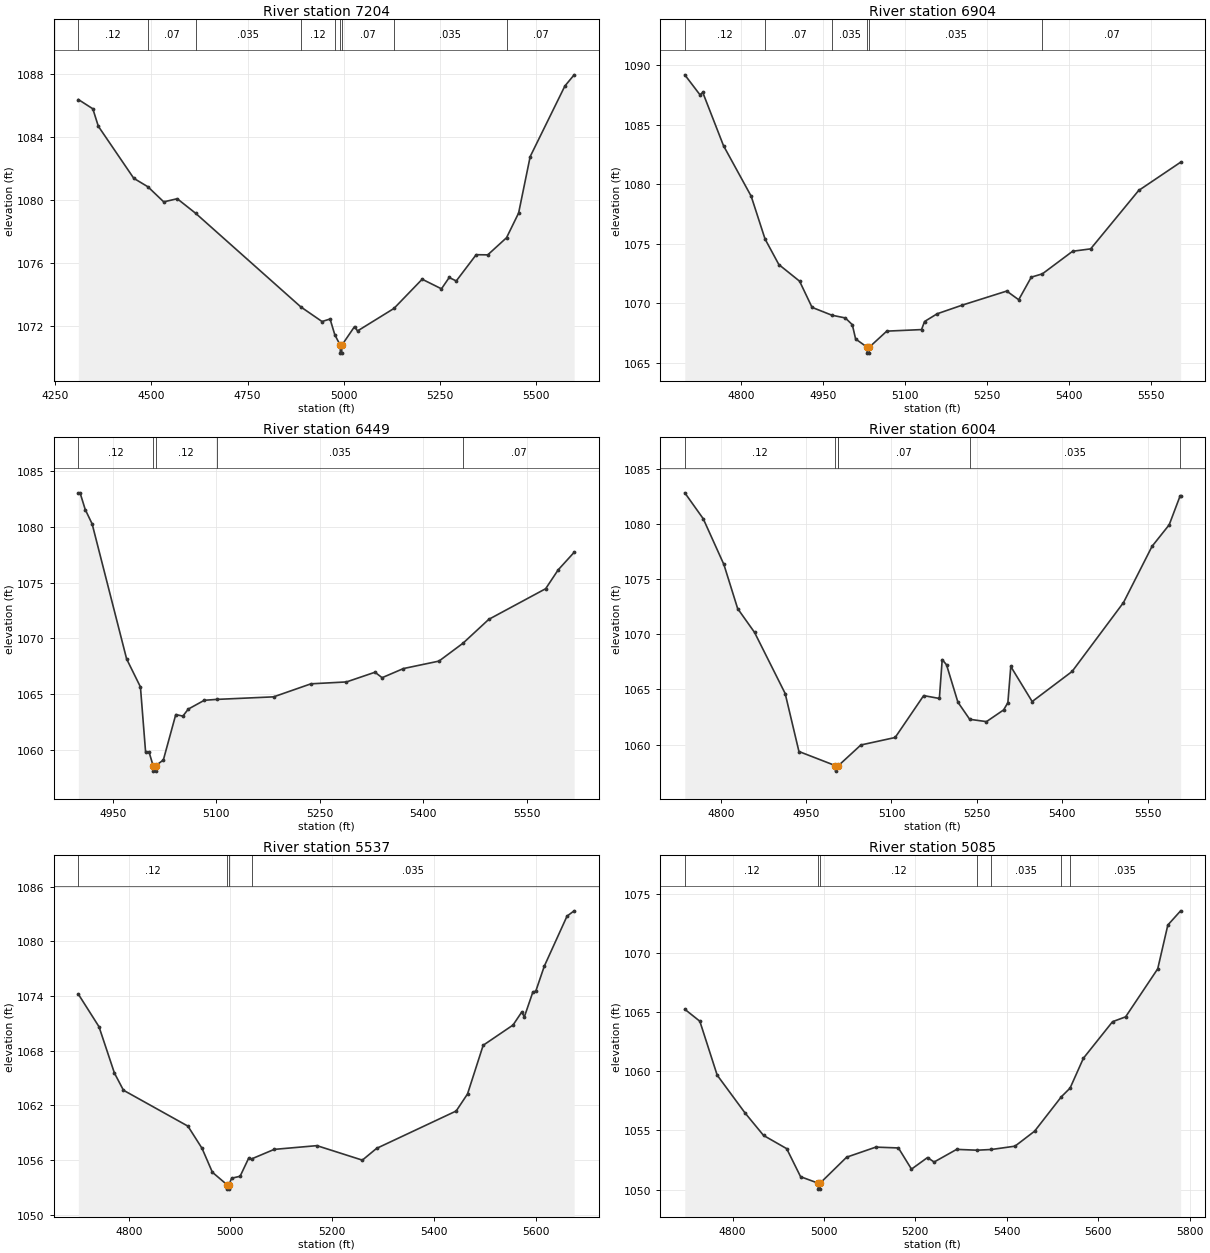
Type RM Length L Ch R = 1,7204,300,300,300
BEGIN DESCRIPTION:
West Fork Tributary 5 16.0
END DESCRIPTION:
XS GIS Cut Line= 3
      2181294.07     13816579.09      2180825.29     13816027.84
      2180261.03     13816075.58
#Sta/Elev= 30
  4309.9 1086.38  4347.6 1085.79  4361.9 1084.68  4454.1 1081.37  4490.9 1080.83
  4532.1 1079.87  4567.2 1080.07  4614.8 1079.15  4888.7 1073.19  4943.9 1072.26
  4964.8 1072.42  4977.1 1071.42  4991.3 1070.75  4991.6 1070.25  4995.1 1070.25
  4995.3 1070.75  5028.5 1071.94  5036.2 1071.66  5130.9 1073.09  5204.4 1074.95
  5254.6 1074.34  5274.7 1075.06  5293.1 1074.84  5344.9 1076.51  5375.0 1076.50
  5423.9 1077.59  5455.3 1079.16  5485.4 1082.75  5575.7 1087.24  5599.8 1087.95
#Mann=9,-1,0
  4309.9    0.12       0  4490.9    0.07       0  4614.8   0.035       0
  4888.7    0.12       0  4977.1    0.07       0  4991.3    0.05       0
  4995.3    0.07       0  5130.9   0.035       0  5423.9    0.07       0
Bank Sta=4991.3,4995.3
Exp/Cntr=0.3,0.1

Type RM Length L Ch R = 1,6904,455,455,455
BEGIN DESCRIPTION:
West Fork Tributary 5 15.0
END DESCRIPTION:
XS GIS Cut Line= 3
      2181324.97     13815874.99      2181025.00     13815825.00
      2180474.96     13815574.98
#Sta/Elev= 30
  4696.6 1089.20  4724.4 1087.52  4729.5 1087.72  4767.5 1083.24  4818.2 1078.99
  4843.6 1075.39  4868.9 1073.24  4906.9 1071.84  4929.7 1069.64  4966.0 1068.98
  4990.6 1068.75  5003.5 1068.18  5009.5 1066.98  5030.6 1066.29  5030.8 1065.79
  5034.3 1065.79  5034.6 1066.29  5066.6 1067.64  5130.3 1067.77  5135.8 1068.45
  5158.9 1069.10  5205.0 1069.83  5286.3 1071.01  5308.3 1070.28  5331.3 1072.18
  5351.7 1072.46  5407.1 1074.36  5440.1 1074.56  5528.0 1079.47  5604.9 1081.85
#Mann=6,-1,0
  4696.6    0.12       0  4843.6    0.07       0  4966.0   0.035       0
  5030.6   0.035       0  5034.6   0.035       0  5351.7    0.07       0
Bank Sta=5030.6,5034.6
Exp/Cntr=0.3,0.1

Type RM Length L Ch R = 1,6449,445,445,445
BEGIN DESCRIPTION:
West Fork Tributary 5 14.0
END DESCRIPTION:
XS GIS Cut Line= 3
      2181275.01     13815425.00      2181175.00     13815425.00
      2180574.98     13815575.01
#Sta/Elev= 30
  4900.1 1083.08  4902.6 1083.08  4910.1 1081.58  4920.1 1080.29  4970.1 1068.16
  4990.1 1065.65  4997.6 1059.78  5002.7 1059.78  5008.4 1058.59  5008.7 1058.09
  5012.2 1058.09  5012.4 1058.59  5023.3 1059.09  5041.3 1063.17  5051.6 1063.03
  5059.4 1063.66  5082.6 1064.45  5100.4 1064.53  5183.1 1064.76  5237.2 1065.93
  5288.7 1066.10  5330.0 1066.97  5340.3 1066.48  5371.2 1067.30  5422.7 1067.97
  5457.6 1069.58  5494.9 1071.72  5577.3 1074.47  5595.4 1076.16  5618.6 1077.74
#Mann=5,-1,0
  4900.1    0.12       0  5008.4    0.05       0  5012.4    0.12       0
  5100.4   0.035       0  5457.6    0.07       0
Bank Sta=5008.4,5012.4
Exp/Cntr=0.3,0.1

Type RM Length L Ch R = 1,6004,467,467,467
BEGIN DESCRIPTION:
West Fork Tributary 5 13.0
END DESCRIPTION:
XS GIS Cut Line= 3
      2181275.04     13815125.02      2181025.00     13815025.00
      2180424.98     13815075.00
#Sta/Elev= 30
  4736.8 1082.83  4769.2 1080.48  4805.5 1076.33  4829.7 1072.33  4859.4 1070.17
  4913.2 1064.63  4937.4 1059.37  5001.4 1058.09  5001.7 1057.59  5005.4 1058.09
  5006.8 1058.09  5046.2 1059.96  5106.5 1060.64  5156.6 1064.44  5184.2 1064.18
  5189.2 1067.71  5196.8 1067.23  5216.8 1063.84  5237.5 1062.29  5267.0 1062.08
  5297.1 1063.14  5304.6 1063.80  5309.7 1067.08  5347.3 1063.90  5417.5 1066.63
  5507.8 1072.88  5558.0 1077.98  5588.1 1079.93  5607.3 1082.55  5608.2 1082.55
#Mann=6,-1,0
  4736.8    0.12       0  5001.4    0.05       0  5005.4    0.12       0
  5006.8    0.07       0  5237.5   0.035       0  5607.3    0.07       0
Bank Sta=5001.4,5005.4
Exp/Cntr=0.3,0.1

Type RM Length L Ch R = 1,5537,452,452,452
BEGIN DESCRIPTION:
West Fork Tributary 5 12.0
END DESCRIPTION:
XS GIS Cut Line= 3
      2181275.02     13814625.00      2180975.00     13814575.00
      2180374.98     13814875.01
#Sta/Elev= 30
  4700.9 1074.21  4741.5 1070.64  4771.9 1065.55  4789.6 1063.67  4916.4 1059.73
  4944.2 1057.29  4964.5 1054.67  4992.9 1053.32  4993.2 1052.82  4996.7 1052.82
  4996.9 1053.32  5002.5 1054.02  5019.0 1054.23  5035.8 1056.21  5041.8 1056.14
  5086.1 1057.18  5170.0 1057.59  5259.4 1056.00  5287.4 1057.29  5443.9 1061.39
  5466.2 1063.26  5497.0 1068.60  5555.7 1070.82  5572.5 1072.22  5578.1 1071.74
  5594.8 1074.46  5600.4 1074.53  5617.2 1077.28  5661.9 1082.77  5675.9 1083.35
#Mann=4,-1,0
  4700.9    0.12       0  4992.9    0.05       0  4996.9    0.12       0
  5041.8   0.035       0
Bank Sta=4992.9,4996.9
Exp/Cntr=0.3,0.1

Type RM Length L Ch R = 1,5085,482,482,482
BEGIN DESCRIPTION:
West Fork Tributary 5 11.0
END DESCRIPTION:
XS GIS Cut Line= 3
      2181274.96     13814174.99      2180975.00     13814125.00
      2180375.02     13814624.98
#Sta/Elev= 30
  4695.4 1065.24  4728.3 1064.23  4766.3 1059.67  4827.2 1056.48  4867.7 1054.58
  4918.4 1053.46  4948.8 1051.09  4987.4 1050.54  4987.6 1050.04  4991.1 1050.04
  4991.4 1050.54  5049.6 1052.74  5113.4 1053.59  5162.9 1053.52  5191.5 1051.73
  5226.6 1052.71  5241.0 1052.33  5290.4 1053.40  5335.0 1053.33  5366.5 1053.39
  5418.0 1053.67  5461.0 1054.94  5519.6 1057.85  5538.6 1058.58  5567.7 1061.10
  5631.5 1064.19  5660.1 1064.60  5730.4 1068.66  5752.5 1072.36  5780.5 1073.56
#Mann=7,-1,0
  4695.4    0.12       0  4987.4    0.05       0  4991.4    0.12       0
  5335.0    0.07       0  5366.5   0.035       0  5519.6    0.12       0
  5538.6   0.035       0
Bank Sta=4987.4,4991.4
Exp/Cntr=0.3,0.1

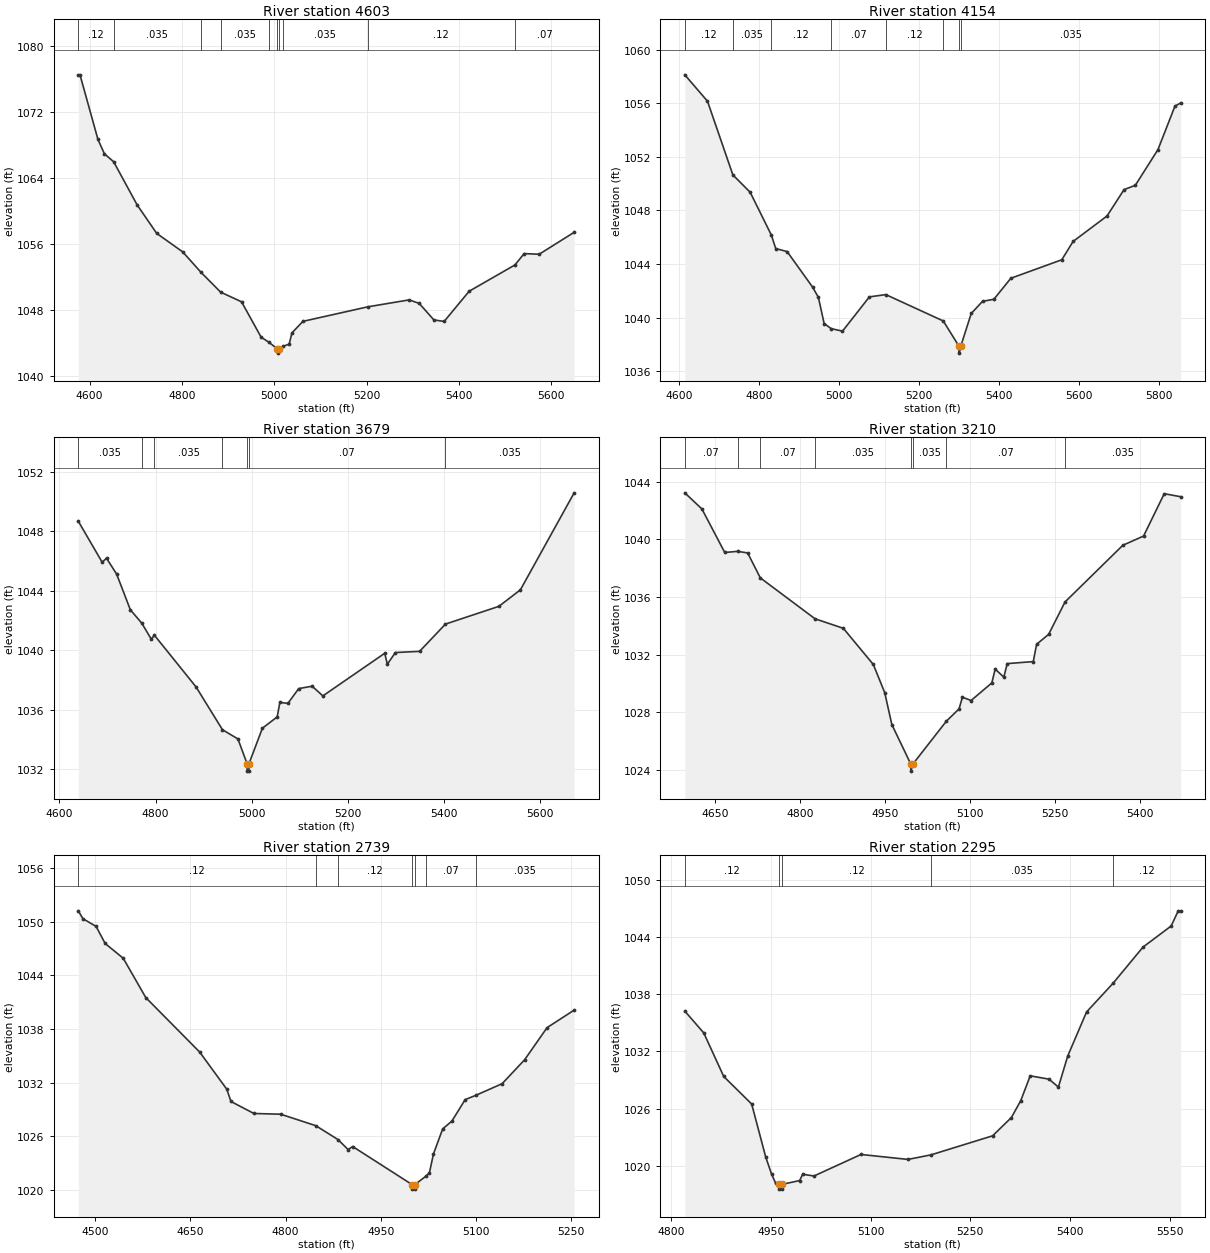
Type RM Length L Ch R = 1,4603,449,449,449
BEGIN DESCRIPTION:
West Fork Tributary 5 10.0
END DESCRIPTION:
XS GIS Cut Line= 3
      2181375.03     13813975.03      2181075.00     13813675.00
      2180475.01     13813925.00
#Sta/Elev= 30
  4575.6 1076.54  4579.2 1076.54  4618.1 1068.71  4632.2 1066.96  4652.1 1066.01
  4702.9 1060.79  4745.4 1057.33  4801.9 1055.08  4841.4 1052.61  4883.9 1050.21
  4929.2 1049.04  4971.6 1044.76  4988.7 1044.13  5007.1 1043.32  5007.4 1042.82
  5011.1 1043.32  5018.5 1043.64  5032.4 1043.90  5038.4 1045.27  5062.2 1046.67
  5202.8 1048.43  5292.4 1049.27  5314.1 1048.85  5346.0 1046.84  5368.2 1046.66
  5422.4 1050.32  5521.5 1053.50  5541.6 1054.88  5574.1 1054.80  5649.9 1057.46
#Mann=10,-1,0
  4575.6    0.12       0  4652.1   0.035       0  4841.4    0.12       0
  4883.9   0.035       0  4988.7    0.12       0  5007.1    0.05       0
  5011.1    0.12       0  5018.5   0.035       0  5202.8    0.12       0
  5521.5    0.07       0
Bank Sta=5007.1,5011.1
Exp/Cntr=0.3,0.1

Type RM Length L Ch R = 1,4154,475,475,475
BEGIN DESCRIPTION:
West Fork Tributary 5 9.0
END DESCRIPTION:
XS GIS Cut Line= 3
      2181475.02     13813575.03      2181225.00     13813275.00
      2180624.98     13812674.98
#Sta/Elev= 30
  4614.8 1058.12  4671.5 1056.15  4734.9 1050.65  4778.2 1049.35  4831.2 1046.15
  4842.0 1045.15  4870.6 1044.92  4934.4 1042.26  4948.7 1041.50  4963.0 1039.55
  4980.6 1039.17  5008.9 1038.98  5076.1 1041.54  5117.2 1041.71  5260.8 1039.74
  5300.3 1037.84  5300.6 1037.34  5304.3 1037.84  5330.6 1040.30  5358.9 1041.21
  5387.2 1041.36  5429.6 1042.93  5556.9 1044.31  5585.2 1045.68  5670.0 1047.58
  5712.5 1049.55  5740.7 1049.87  5797.3 1052.54  5839.7 1055.78  5853.9 1056.02
#Mann=8,-1,0
  4614.8    0.12       0  4734.9   0.035       0  4831.2    0.12       0
  4980.6    0.07       0  5117.2    0.12       0  5260.8   0.035       0
  5300.3    0.05       0  5304.3   0.035       0
Bank Sta=5300.3,5304.3
Exp/Cntr=0.3,0.1

Type RM Length L Ch R = 1,3679,469,469,469
BEGIN DESCRIPTION:
West Fork Tributary 5 8.0
END DESCRIPTION:
XS GIS Cut Line= 3
      2181624.99     13813174.99      2181425.00     13812875.00
      2180824.97     13812574.98
#Sta/Elev= 30
  4639.2 1048.66  4688.8 1045.91  4697.8 1046.18  4718.8 1045.12  4747.4 1042.72
  4771.2 1041.82  4790.9 1040.75  4797.5 1041.01  4884.1 1037.54  4939.0 1034.67
  4971.2 1034.05  4990.2 1032.39  4990.5 1031.89  4994.0 1031.89  4994.2 1032.39
  5022.1 1034.77  5052.9 1035.53  5058.4 1036.50  5075.2 1036.44  5097.6 1037.43
  5125.5 1037.59  5147.9 1036.94  5276.5 1039.80  5282.0 1039.07  5298.8 1039.85
  5349.1 1039.93  5402.9 1041.76  5514.0 1042.95  5558.8 1044.06  5670.6 1050.57
#Mann=7,-1,0
  4639.2   0.035       0  4771.2    0.07       0  4797.5   0.035       0
  4939.0    0.07       0  4990.2    0.05       0  4994.2    0.07       0
  5402.9   0.035       0
Bank Sta=4990.2,4994.2
Exp/Cntr=0.3,0.1

Type RM Length L Ch R = 1,3210,471,471,471
BEGIN DESCRIPTION:
West Fork Tributary 5 7.0
END DESCRIPTION:
XS GIS Cut Line= 3
      2181825.00     13812975.00      2181775.00     13812575.00
      2181525.01     13812175.01
#Sta/Elev= 30
  4597.2 1043.23  4627.4 1042.11  4667.7 1039.09  4690.3 1039.17  4708.1 1039.06
  4730.4 1037.33  4827.0 1034.49  4876.9 1033.83  4929.8 1031.32  4949.9 1029.37
  4962.5 1027.15  4995.8 1024.42  4996.0 1023.92  4999.8 1024.42  5058.8 1027.39
  5081.1 1028.24  5087.0 1029.05  5102.3 1028.82  5138.9 1030.04  5144.8 1031.00
  5160.1 1030.44  5166.0 1031.38  5212.0 1031.52  5217.9 1032.72  5239.1 1033.41
  5268.1 1035.66  5370.0 1039.59  5406.6 1040.23  5443.1 1043.17  5472.0 1042.96
#Mann=8,-1,0
  4597.2    0.07       0  4690.3   0.035       0  4730.4    0.07       0
  4827.0   0.035       0  4995.8   0.035       0  4999.8   0.035       0
  5058.8    0.07       0  5268.1   0.035       0
Bank Sta=4995.8,4999.8
Exp/Cntr=0.3,0.1

Type RM Length L Ch R = 1,2739,444,444,444
BEGIN DESCRIPTION:
West Fork Tributary 5 6.0
END DESCRIPTION:
XS GIS Cut Line= 3
      2182475.03     13812575.03      2182075.00     13812225.00
      2181875.04     13812075.03
#Sta/Elev= 30
  4473.4 1051.20  4480.6 1050.32  4501.4 1049.46  4515.7 1047.55  4544.2 1045.90
  4579.7 1041.51  4664.7 1035.42  4707.4 1031.27  4714.0 1029.90  4750.1 1028.56
  4792.3 1028.48  4847.6 1027.20  4882.6 1025.65  4898.6 1024.53  4905.8 1024.87
  4999.6 1020.61  4999.8 1020.11  5003.4 1020.11  5003.7 1020.61  5021.0 1021.54
  5026.8 1021.94  5033.1 1024.03  5047.7 1026.84  5062.2 1027.71  5083.1 1030.11
  5099.6 1030.58  5141.4 1031.89  5176.8 1034.56  5212.2 1038.15  5254.9 1040.11
#Mann=7,-1,0
  4473.4    0.12       0  4847.6    0.07       0  4882.6    0.12       0
  4999.6    0.05       0  5003.7    0.12       0  5021.0    0.07       0
  5099.6   0.035       0
Bank Sta=4999.6,5003.7
Exp/Cntr=0.3,0.1

Type RM Length L Ch R = 1,2295,451,451,451
BEGIN DESCRIPTION:
West Fork Tributary 5 5.0
END DESCRIPTION:
XS GIS Cut Line= 3
      2182624.99     13812174.99      2182475.00     13812075.00
      2182074.97     13811674.97
#Sta/Elev= 30
  4820.4 1036.24  4848.9 1033.95  4879.0 1029.37  4921.0 1026.48  4942.1 1020.92
  4951.1 1019.09  4957.1 1018.16  4962.6 1018.04  4962.8 1017.54  4966.4 1017.54
  4966.7 1018.04  4993.2 1018.44  4997.7 1019.10  5014.8 1018.92  5085.5 1021.18
  5156.2 1020.66  5190.9 1021.14  5283.5 1023.14  5311.8 1025.06  5325.9 1026.84
  5340.1 1029.44  5368.4 1029.09  5382.5 1028.26  5396.6 1031.53  5424.9 1036.15
  5464.6 1039.15  5509.8 1042.96  5552.2 1045.18  5562.8 1046.77  5566.4 1046.77
#Mann=5,-1,0
  4820.4    0.12       0  4962.6    0.05       0  4966.7    0.12       0
  5190.9   0.035       0  5464.6    0.12       0
Bank Sta=4962.6,4966.7
Exp/Cntr=0.3,0.1

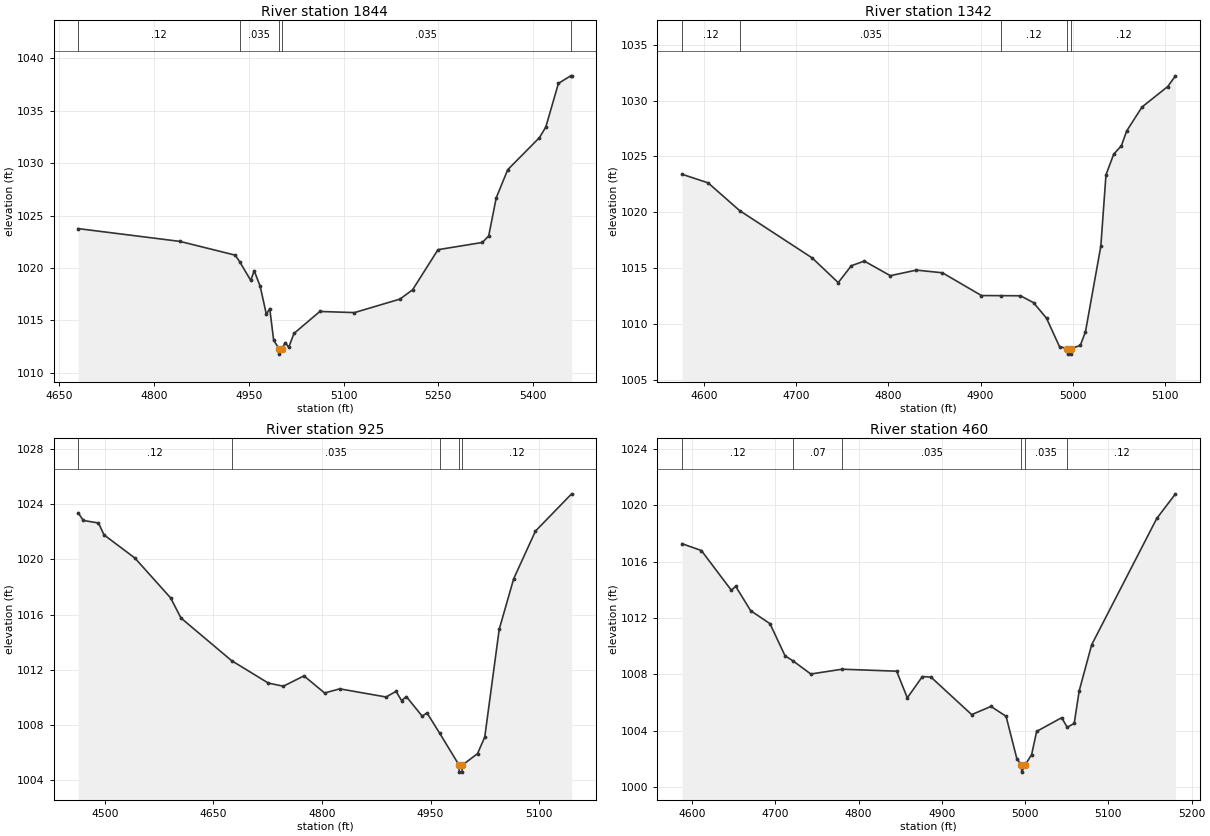
Type RM Length L Ch R = 1,1844,502,502,502
BEGIN DESCRIPTION:
West Fork Tributary 5 4.0
END DESCRIPTION:
XS GIS Cut Line= 4
      2182929.07     13811607.84      2182709.03     13811674.03
      2182499.75     13811754.53      2182174.18     13811731.27
#Sta/Elev= 30
  4680.4 1023.75  4841.3 1022.53  4928.7 1021.22  4935.6 1020.61  4953.3 1018.81
  4958.7 1019.74  4968.1 1018.27  4978.0 1015.57  4983.3 1016.13  4989.5 1013.12
  4998.1 1012.28  4998.4 1011.78  5002.3 1012.28  5008.0 1012.88  5013.3 1012.42
  5021.6 1013.75  5062.6 1015.85  5117.3 1015.74  5189.3 1017.03  5209.3 1017.92
  5249.4 1021.74  5319.6 1022.43  5329.6 1023.05  5341.5 1026.68  5359.7 1029.37
  5409.9 1032.43  5419.9 1033.43  5439.9 1037.60  5459.3 1038.32  5460.8 1038.32
#Mann=5,-1,0
  4680.4    0.12       0  4935.6   0.035       0  4998.1   0.035       0
  5002.3   0.035       0  5459.3    0.12       0
Bank Sta=4998.1,5002.3
Exp/Cntr=0.3,0.1

Type RM Length L Ch R = 1,1342,417,417,417
BEGIN DESCRIPTION:
West Fork Tributary 5 3.0
END DESCRIPTION:
XS GIS Cut Line= 3
      2182925.02     13811575.02      2182625.00     13811275.00
      2182525.00     13811225.00
#Sta/Elev= 30
  4575.7 1023.40  4604.0 1022.63  4638.3 1020.14  4717.1 1015.90  4745.4 1013.69
  4759.6 1015.20  4773.7 1015.62  4802.0 1014.31  4830.3 1014.81  4858.6 1014.57
  4901.0 1012.53  4922.5 1012.52  4943.4 1012.51  4957.6 1011.89  4971.7 1010.50
  4985.8 1007.95  4994.4 1007.78  4994.6 1007.28  4998.3 1007.28  4998.6 1007.78
  5008.4 1008.06  5014.0 1009.28  5030.7 1016.96  5036.3 1023.35  5044.7 1025.20
  5053.1 1025.96  5058.7 1027.27  5075.5 1029.43  5103.4 1031.26  5111.8 1032.22
#Mann=5,-1,0
  4575.7    0.12       0  4638.3   0.035       0  4922.5    0.12       0
  4994.4    0.05       0  4998.6    0.12       0
Bank Sta=4994.4,4998.6
Exp/Cntr=0.3,0.1

Type RM Length L Ch R = 1,925,465,465,465
BEGIN DESCRIPTION:
West Fork Tributary 5 2.0
END DESCRIPTION:
XS GIS Cut Line= 3
      2183275.01     13811425.01      2182925.00     13811025.00
      2182925.00     13810875.03
#Sta/Elev= 30
  4463.4 1023.37  4470.5 1022.82  4491.4 1022.64  4499.0 1021.78  4541.7 1020.10
  4591.1 1017.21  4605.3 1015.76  4675.3 1012.67  4725.9 1011.05  4746.7 1010.82
  4775.2 1011.57  4803.7 1010.33  4824.6 1010.63  4888.6 1010.04  4902.4 1010.45
  4910.0 1009.78  4916.6 1010.07  4938.5 1008.65  4945.1 1008.89  4962.6 1007.42
  4989.5 1005.10  4989.7 1004.60  4993.5 1004.60  4993.8 1005.10  5014.9 1005.94
  5024.9 1007.14  5044.9 1014.95  5064.9 1018.61  5094.9 1022.05  5144.9 1024.75
#Mann=5,-1,0
  4463.4    0.12       0  4675.3   0.035       0  4962.6    0.12       0
  4989.5    0.05       0  4993.8    0.12       0
Bank Sta=4989.5,4993.8
Exp/Cntr=0.3,0.1

Type RM Length L Ch R = 1,460,0,0,0
BEGIN DESCRIPTION:
West Fork Tributary 5 1.0
END DESCRIPTION:
XS GIS Cut Line= 3
      2183424.99     13811224.96      2183325.00     13810825.00
      2183175.04     13810725.03
#Sta/Elev= 30
  4588.0 1017.27  4611.2 1016.79  4647.2 1013.97  4652.4 1014.25  4670.4 1012.52
  4693.6 1011.60  4711.7 1009.32  4721.3 1008.96  4742.6 1008.03  4780.2 1008.37
  4845.7 1008.23  4858.5 1006.34  4876.6 1007.85  4886.9 1007.81  4935.8 1005.15
  4959.0 1005.73  4977.1 1005.03  4990.0 1002.03  4995.5 1001.57  4995.8 1001.07
  4999.9 1001.57  5007.8 1002.32  5013.8 1003.96  5043.8 1004.93  5050.6 1004.25
  5058.9 1004.53  5064.9 1006.84  5079.9 1010.11  5158.0 1019.06  5180.5 1020.81
#Mann=6,-1,0
  4588.0    0.12       0  4721.3    0.07       0  4780.2   0.035       0
  4995.5   0.035       0  4999.9   0.035       0  5050.6    0.12       0
Bank Sta=4995.5,4999.9
Exp/Cntr=0.3,0.1

Chan Stop Cuts=-1