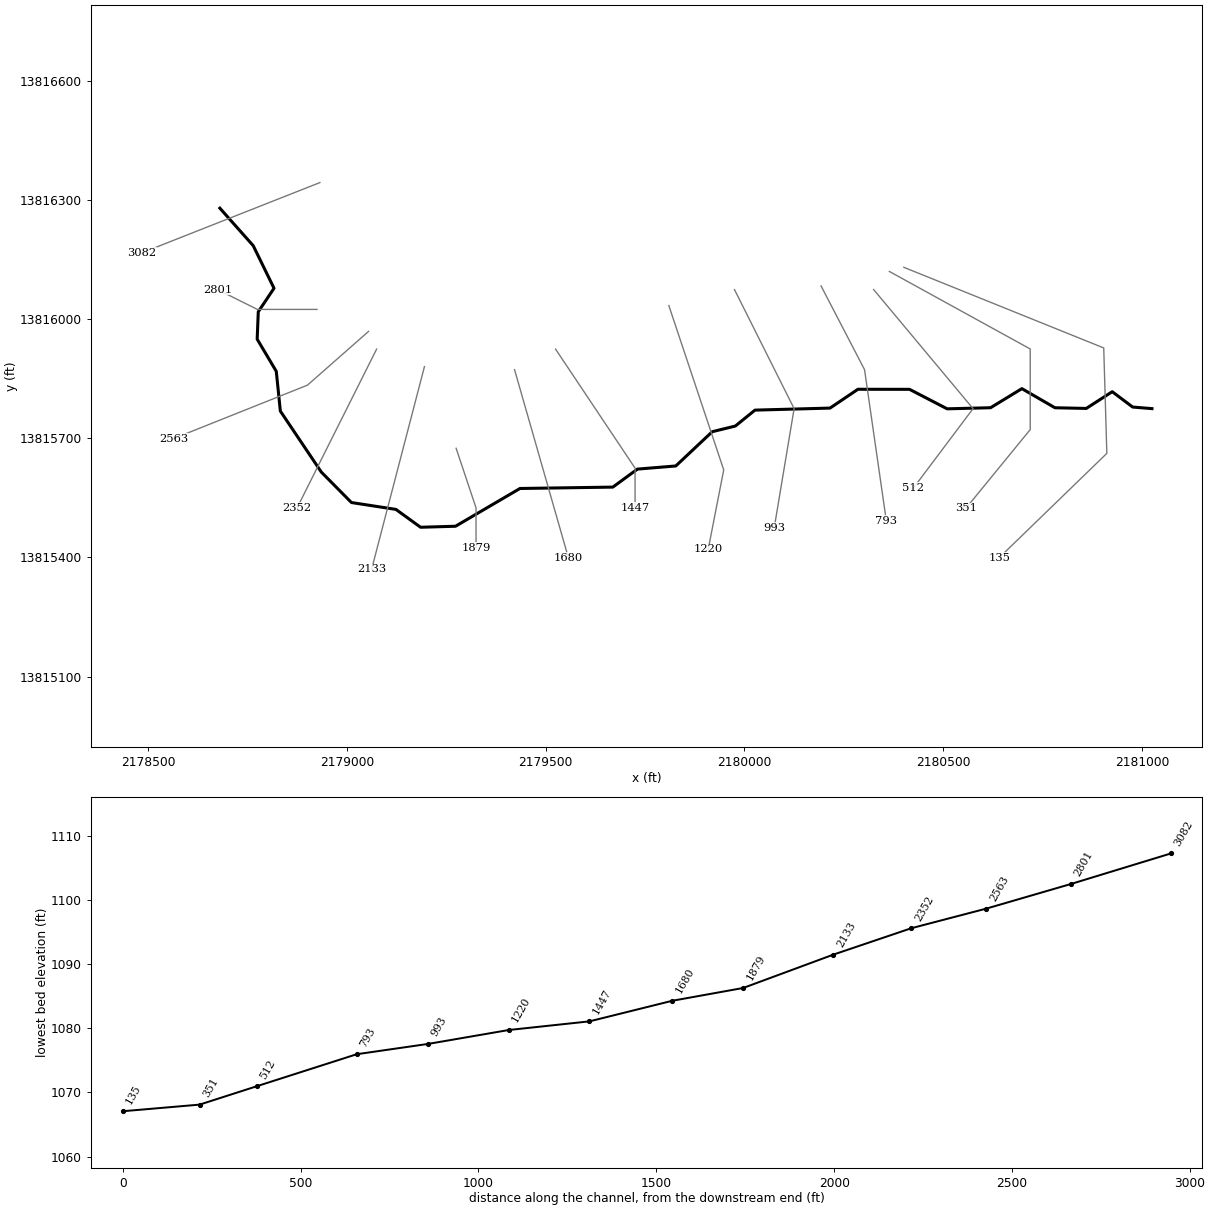
--- West Fork Tributary 5b.prj (project) ---

Proj Title=West Fork Tributary 5b Base Level Engineering
Current Plan=p01
Default Exp/Contr=0.3,0.1
English Units
Geom File=g01
Flow File=f01
Plan File=p01
BEGIN DESCRIPTION:
West Fork Tributary 5b
END DESCRIPTION:

--- West Fork Tributary 5b.p01 (plan) ---

Plan Title=Multiple Run
Short Identifier=Multiple
Geom File=g01
Flow File=f01
Subcritical Flow
K Sum by GR= 0
Std Step Tol= 0.01
Critical Tol= 0.01
Num of Std Step Trials= 20
Max Error Tol= 0.3
Flow Tol Ratio= 0.001
Split Flow NTrial= 30
Split Flow Tol= 0.02
Split Flow Ratio= 0.02
Log Output Level= 0
Friction Slope Method= 1
Unsteady Friction Slope Method= 2
Unsteady Bridges Friction Slope Method= 1
Parabolic Critical Depth
Global Vel Dist=  1 , 1 , 1
Global Log Level= 0
CheckData=True
Encroach Param= -1, 0, 0, 0
BEGIN DESCRIPTION:
Multiple Run
END DESCRIPTION:

--- West Fork Tributary 5b.f01 (steady flow) ---

Flow Title=Multiple
Number of Profiles=7
Profile Names=10-year,25-year,50-year,1pct_min,100-year,1pct_plu,500-year
River Rch & RM= West Fork Tribut,Reach-1,3082
     368     579     767     494     986    1967    1606
Boundary for River Rch & Prof#=West Fork Tribut,Reach-1,1
Up Type=0
Dn Type=3
Dn Slope=0.005
Boundary for River Rch & Prof#=West Fork Tribut,Reach-1,2
Up Type=0
Dn Type=3
Dn Slope=0.005
Boundary for River Rch & Prof#=West Fork Tribut,Reach-1,3
Up Type=0
Dn Type=3
Dn Slope=0.005
Boundary for River Rch & Prof#=West Fork Tribut,Reach-1,4
Up Type=0
Dn Type=3
Dn Slope=0.005
Boundary for River Rch & Prof#=West Fork Tribut,Reach-1,5
Up Type=0
Dn Type=3
Dn Slope=0.005
Boundary for River Rch & Prof#=West Fork Tribut,Reach-1,6
Up Type=0
Dn Type=3
Dn Slope=0.005
Boundary for River Rch & Prof#=West Fork Tribut,Reach-1,7
Up Type=0
Dn Type=3
Dn Slope=0.005

--- West Fork Tributary 5b.g01 (geometry) ---

Geom Title=Existing Conditions

River Reach=West Fork Tribut,Reach-1
Reach XY= 30
      2178680.76     13816280.07      2178764.64     13816185.61
      2178816.95     13816078.31      2178777.37     13816019.11
      2178774.61     13815950.00      2178822.64     13815869.02
      2178832.88     13815768.84      2178935.77     13815615.30
      2179011.67     13815538.39      2179123.40     13815521.14
      2179185.55     13815476.10      2179273.42     13815478.67
      2179435.50     13815573.80      2179669.06     13815577.26
      2179730.98     13815622.64      2179827.42     13815630.54
      2179918.95     13815716.84      2179977.17     13815731.14
      2180026.55     13815771.25      2180215.34     13815776.38
      2180285.51     13815823.79      2180415.33     13815823.63
      2180509.84     13815774.53      2180619.07     13815777.28
      2180697.81     13815825.38      2180780.97     13815777.20
      2180859.78     13815775.51      2180925.04     13815817.68
      2180976.36     13815779.00      2181025.00     13815775.00

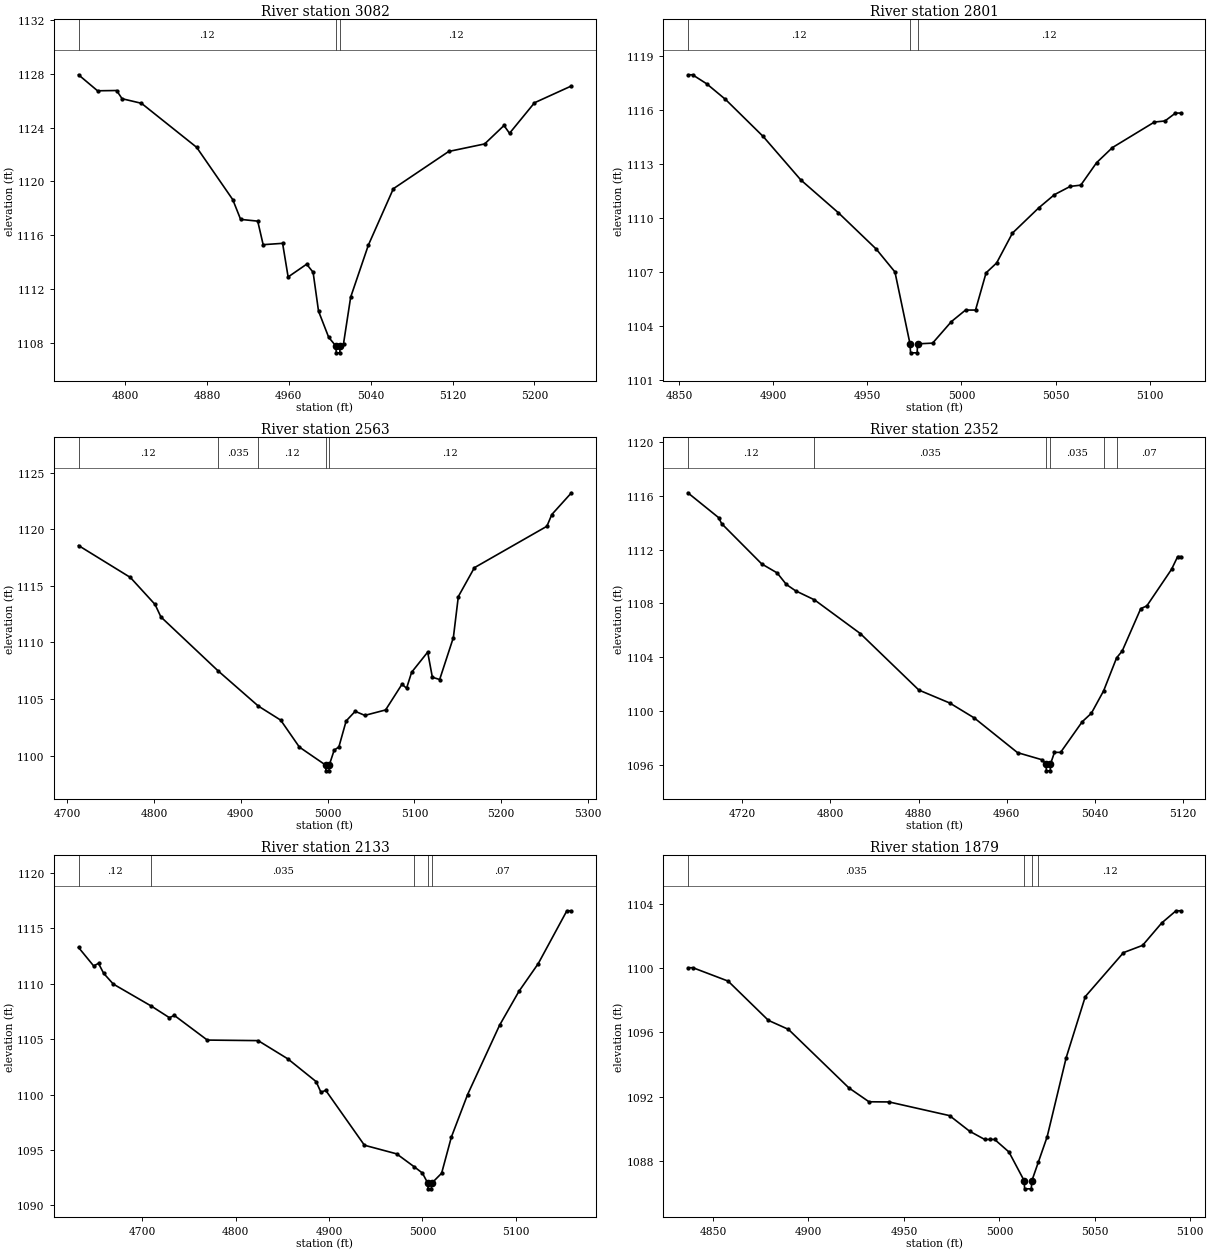
Type RM Length L Ch R = 1,3082,281,281,281
BEGIN DESCRIPTION:
H21731
END DESCRIPTION:
XS GIS Cut Line= 2
      2178932.30     13816344.57      2178484.43     13816167.50
#Sta/Elev= 30
  4754.5 1127.92  4773.1 1126.73  4791.7 1126.75  4797.1 1126.14  4816.0 1125.80
  4869.9 1122.53  4905.2 1118.64  4912.9 1117.17  4929.6 1117.04  4934.9 1115.29
  4953.9 1115.39  4959.3 1112.89  4977.4 1113.84  4983.7 1113.24  4989.0 1110.35
  4998.9 1108.41  5006.0 1107.75  5006.3 1107.25  5009.8 1107.25  5010.0 1107.75
  5013.4 1107.92  5020.4 1111.39  5037.7 1115.26  5062.1 1119.45  5116.2 1122.22
  5151.3 1122.78  5170.2 1124.15  5175.6 1123.57  5200.0 1125.84  5236.1 1127.09
#Mann=3,-1,0
  4754.5    0.12       0  5006.0    0.05       0  5010.0    0.12       0
Bank Sta=5006,5010
Exp/Cntr=0.3,0.1

Type RM Length L Ch R = 1,2801,238,238,238
BEGIN DESCRIPTION:
West Fork Tributary 5b 6.0
END DESCRIPTION:
XS GIS Cut Line= 3
      2178925.01     13816025.00      2178775.00     13816025.00
      2178675.01     13816074.99
#Sta/Elev= 30
  4854.7 1117.96  4857.2 1117.96  4864.7 1117.46  4874.7 1116.59  4894.7 1114.53
  4914.7 1112.11  4934.7 1110.28  4954.7 1108.27  4964.7 1106.99  4972.7 1102.99
  4973.0 1102.49  4976.5 1102.49  4976.7 1102.99  4984.7 1103.03  4994.7 1104.23
  5002.2 1104.87  5007.5 1104.87  5013.1 1106.94  5018.7 1107.49  5027.1 1109.15
  5041.0 1110.55  5049.4 1111.29  5057.8 1111.75  5063.4 1111.82  5071.8 1113.07
  5080.2 1113.91  5102.5 1115.33  5108.1 1115.39  5113.7 1115.83  5116.5 1115.83
#Mann=3,-1,0
  4854.7    0.12       0  4972.7    0.05       0  4976.7    0.12       0
Bank Sta=4972.7,4976.7
Exp/Cntr=0.3,0.1

Type RM Length L Ch R = 1,2563,211,211,211
BEGIN DESCRIPTION:
H21730
END DESCRIPTION:
XS GIS Cut Line= 3
      2179054.73     13815969.59      2178901.06     13815834.16
      2178564.05     13815699.35
#Sta/Elev= 30
  4713.1 1118.56  4772.8 1115.74  4801.3 1113.35  4808.0 1112.25  4873.8 1107.49
  4920.3 1104.37  4946.0 1103.13  4967.5 1100.75  4997.9 1099.15  4998.1 1098.65
  5001.6 1098.65  5001.9 1099.15  5007.6 1100.48  5013.0 1100.76  5021.4 1103.06
  5031.8 1103.91  5042.9 1103.55  5066.8 1104.03  5085.7 1106.30  5091.0 1105.95
  5096.8 1107.36  5115.3 1109.14  5120.7 1106.92  5129.1 1106.72  5144.9 1110.43
  5150.6 1114.05  5169.1 1116.60  5252.6 1120.26  5258.3 1121.30  5280.9 1123.22
#Mann=5,-1,0
  4713.1    0.12       0  4873.8   0.035       0  4920.3    0.12       0
  4997.9    0.05       0  5001.9    0.12       0
Bank Sta=4997.9,5001.9
Exp/Cntr=0.3,0.1

Type RM Length L Ch R = 1,2352,219,219,219
BEGIN DESCRIPTION:
West Fork Tributary 5b 5.0
END DESCRIPTION:
XS GIS Cut Line= 3
      2179074.99     13815924.98      2178925.00     13815625.00
      2178875.00     13815524.99
#Sta/Elev= 30
  4670.7 1116.21  4698.6 1114.37  4701.4 1113.92  4737.8 1110.93  4751.7 1110.27
  4760.1 1109.41  4768.5 1108.94  4785.6 1108.27  4827.2 1105.77  4880.3 1101.58
  4908.3 1100.62  4930.6 1099.51  4969.8 1096.94  4992.1 1096.41  4995.7 1096.09
  4996.0 1095.59  4999.5 1095.59  4999.7 1096.09  5003.3 1096.96  5008.9 1096.96
  5028.5 1099.23  5036.8 1099.86  5047.9 1101.52  5059.7 1103.97  5064.8 1104.48
  5081.6 1107.62  5087.1 1107.82  5109.5 1110.53  5115.1 1111.48  5117.9 1111.48
#Mann=6,-1,0
  4670.7    0.12       0  4785.6   0.035       0  4995.7   0.035       0
  4999.7   0.035       0  5047.9    0.12       0  5059.7    0.07       0
Bank Sta=4995.7,4999.7
Exp/Cntr=0.3,0.1

Type RM Length L Ch R = 1,2133,254,254,254
BEGIN DESCRIPTION:
H21729
END DESCRIPTION:
XS GIS Cut Line= 2
      2179195.32     13815881.00      2179062.51     13815370.60
#Sta/Elev= 30
  4632.0 1113.29  4648.2 1111.62  4653.4 1111.85  4658.9 1110.95  4669.2 1109.98
  4709.9 1107.99  4729.3 1106.94  4734.5 1107.15  4769.8 1104.92  4824.2 1104.87
  4856.0 1103.22  4886.2 1101.17  4891.4 1100.20  4896.5 1100.38  4937.9 1095.42
  4972.4 1094.64  4990.9 1093.49  4999.9 1092.91  5005.8 1091.98  5006.0 1091.48
  5009.5 1091.48  5009.8 1091.98  5020.5 1092.89  5030.9 1096.15  5048.3 1100.00
  5082.5 1106.26  5103.2 1109.32  5123.9 1111.83  5154.5 1116.60  5159.4 1116.60
#Mann=5,-1,0
  4632.0    0.12       0  4709.9   0.035       0  4990.9    0.07       0
  5005.8    0.05       0  5009.8    0.07       0
Bank Sta=5005.8,5009.8
Exp/Cntr=0.3,0.1

Type RM Length L Ch R = 1,1879,199,199,199
BEGIN DESCRIPTION:
West Fork Tributary 5b 4.0
END DESCRIPTION:
XS GIS Cut Line= 3
      2179274.99     13815675.04      2179325.00     13815525.00
      2179325.00     13815424.95
#Sta/Elev= 27
  4836.8 1100.01  4839.5 1100.01  4857.9 1099.18  4879.0 1096.74  4889.5 1096.18
  4921.2 1092.54  4931.7 1091.68  4942.2 1091.67  4973.9 1090.82  4984.4 1089.85
  4992.3 1089.34  4995.0 1089.34  4997.5 1089.34  5005.0 1088.56  5013.0 1086.77
  5013.2 1086.27  5016.7 1086.27  5017.0 1086.77  5020.4 1087.93  5025.0 1089.50
  5035.0 1094.43  5045.0 1098.22  5065.0 1100.95  5075.0 1101.40  5085.0 1102.79
  5092.5 1103.55  5095.0 1103.55
#Mann=4,-1,0
  4836.8   0.035       0  5013.0   0.035       0  5017.0   0.035       0
  5020.4    0.12       0
Bank Sta=5013,5017
Exp/Cntr=0.3,0.1

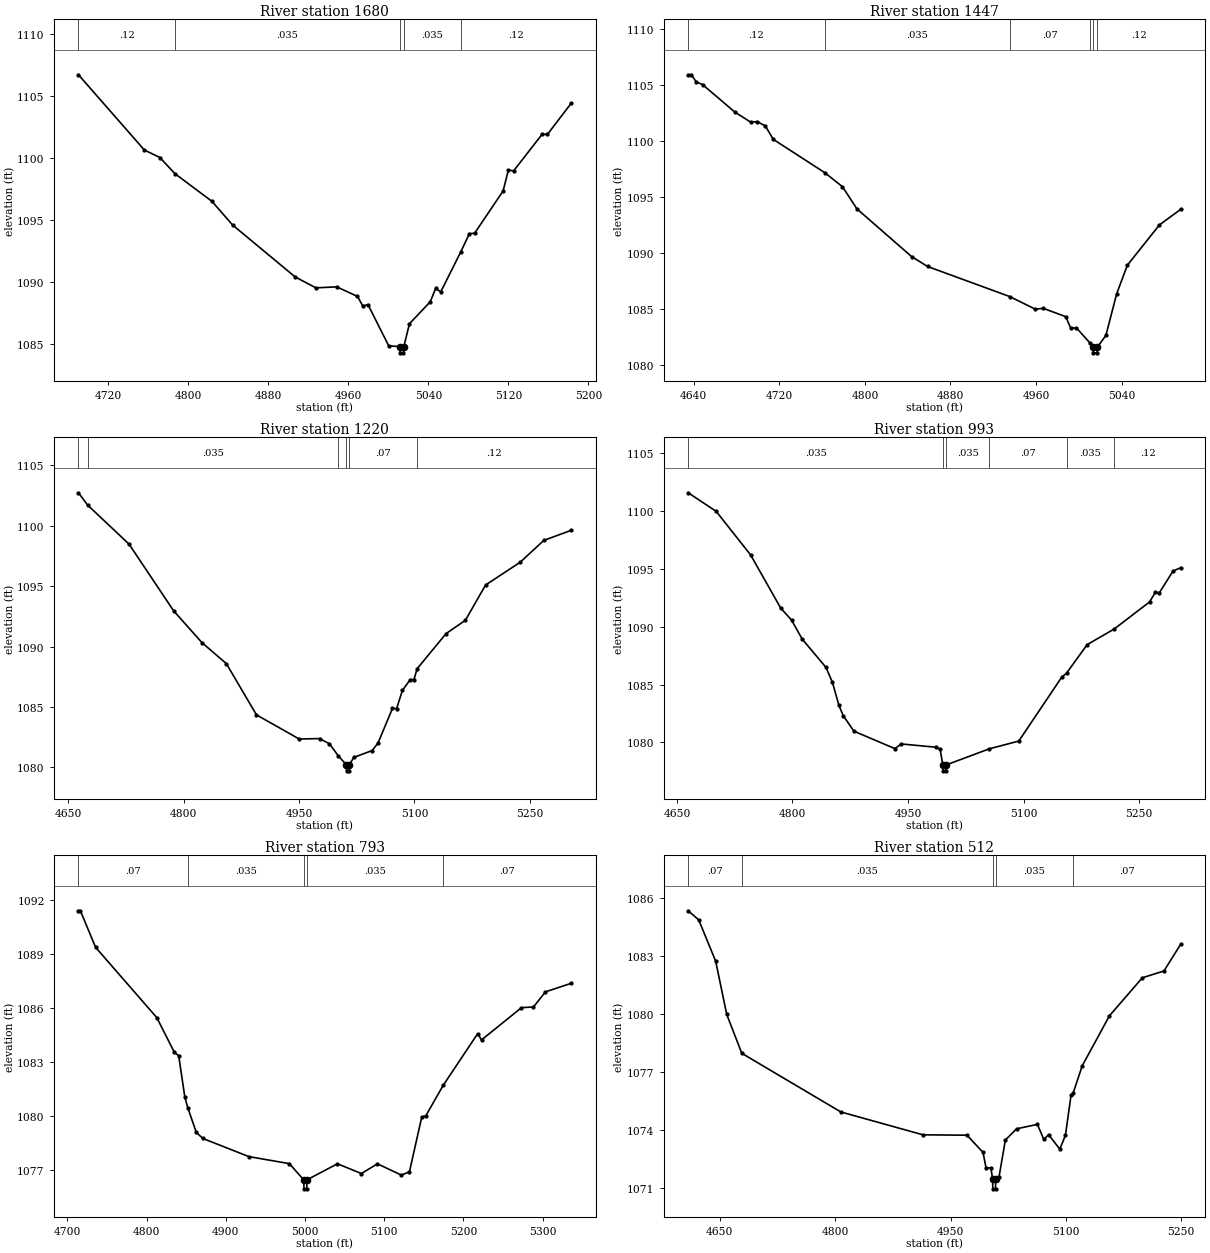
Type RM Length L Ch R = 1,1680,233,233,233
BEGIN DESCRIPTION:
H21728
END DESCRIPTION:
XS GIS Cut Line= 2
      2179421.88     13815873.25      2179557.21     13815399.60
#Sta/Elev= 30
  4690.0 1106.70  4755.9 1100.63  4771.4 1100.03  4786.4 1098.73  4823.4 1096.50
  4844.2 1094.58  4906.7 1090.40  4927.4 1089.52  4948.2 1089.60  4969.0 1088.83
  4974.3 1088.06  4979.5 1088.17  5000.2 1084.85  5011.3 1084.78  5011.5 1084.28
  5015.0 1084.28  5015.3 1084.78  5021.0 1086.63  5041.8 1088.40  5047.1 1089.47
  5052.3 1089.20  5072.3 1092.42  5080.9 1093.89  5086.1 1093.92  5114.6 1097.33
  5119.9 1099.02  5125.1 1098.95  5153.7 1101.91  5158.9 1101.89  5182.6 1104.39
#Mann=5,-1,0
  4690.0    0.12       0  4786.4   0.035       0  5011.3   0.035       0
  5015.3   0.035       0  5072.3    0.12       0
Bank Sta=5011.3,5015.3
Exp/Cntr=0.3,0.1

Type RM Length L Ch R = 1,1447,227,227,227
BEGIN DESCRIPTION:
West Fork Tributary 5b 3.0
END DESCRIPTION:
XS GIS Cut Line= 3
      2179525.01     13815924.99      2179725.00     13815625.00
      2179725.00     13815525.04
#Sta/Elev= 30
  4634.8 1105.90  4637.8 1105.90  4642.3 1105.27  4648.3 1105.02  4678.4 1102.57
  4693.4 1101.66  4699.4 1101.72  4706.9 1101.33  4714.4 1100.13  4762.3 1097.17
  4779.0 1095.91  4792.5 1093.93  4843.6 1089.67  4858.6 1088.78  4935.3 1086.10
  4959.3 1084.97  4966.8 1085.04  4987.8 1084.30  4992.3 1083.29  4997.8 1083.29
  5010.3 1081.96  5013.3 1081.57  5013.6 1081.07  5017.1 1081.07  5017.3 1081.57
  5025.3 1082.63  5035.3 1086.32  5045.3 1088.89  5075.3 1092.49  5095.3 1093.89
#Mann=6,-1,0
  4634.8    0.12       0  4762.3   0.035       0  4935.3    0.07       0
  5010.3    0.12       0  5013.3    0.05       0  5017.3    0.12       0
Bank Sta=5013.3,5017.3
Exp/Cntr=0.3,0.1

Type RM Length L Ch R = 1,1220,227,227,227
BEGIN DESCRIPTION:
H21727
END DESCRIPTION:
XS GIS Cut Line= 3
      2179809.92     13816034.65      2179947.93     13815620.61
      2179908.87     13815420.11
#Sta/Elev= 30
  4663.1 1102.72  4675.0 1101.70  4728.9 1098.47  4786.9 1092.95  4823.8 1090.32
  4855.4 1088.59  4894.6 1084.35  4950.3 1082.35  4976.6 1082.39  4989.5 1081.96
  5000.8 1080.98  5011.5 1080.22  5011.8 1079.72  5015.3 1079.72  5015.5 1080.22
  5021.1 1080.83  5045.1 1081.40  5052.7 1082.02  5071.5 1084.89  5076.8 1084.86
  5084.4 1086.37  5094.6 1087.27  5099.5 1087.27  5103.5 1088.16  5141.0 1091.06
  5166.4 1092.18  5192.6 1095.09  5237.7 1096.98  5268.3 1098.78  5303.8 1099.61
#Mann=6,-1,0
  4663.1    0.12       0  4675.0   0.035       0  5000.8    0.07       0
  5011.5   0.035       0  5015.5    0.07       0  5103.5    0.12       0
Bank Sta=5011.5,5015.5
Exp/Cntr=0.3,0.1

Type RM Length L Ch R = 1,993,200,200,200
BEGIN DESCRIPTION:
West Fork Tributary 5b 2.0
END DESCRIPTION:
XS GIS Cut Line= 3
      2179975.01     13816074.99      2180125.00     13815775.00
      2180075.01     13815475.04
#Sta/Elev= 30
  4664.6 1101.55  4700.9 1099.95  4745.6 1096.19  4784.8 1091.59  4798.8 1090.56
  4812.7 1088.91  4843.5 1086.48  4851.9 1085.18  4860.2 1083.22  4865.8 1082.32
  4879.8 1080.97  4932.9 1079.47  4941.3 1079.87  4986.0 1079.59  4991.6 1079.43
  4995.2 1078.05  4995.5 1077.55  4999.0 1077.55  4999.2 1078.05  5055.5 1079.45
  5093.8 1080.12  5149.5 1085.63  5155.8 1085.98  5182.5 1088.44  5217.6 1089.79
  5263.6 1092.13  5271.2 1092.97  5276.3 1092.92  5294.0 1094.79  5304.1 1095.09
#Mann=6,-1,0
  4664.6   0.035       0  4995.2   0.035       0  4999.2   0.035       0
  5055.5    0.07       0  5155.8   0.035       0  5217.6    0.12       0
Bank Sta=4995.2,4999.2
Exp/Cntr=0.3,0.1

Type RM Length L Ch R = 1,793,281,281,281
BEGIN DESCRIPTION:
H21726
END DESCRIPTION:
XS GIS Cut Line= 3
      2180192.72     13816084.17      2180302.10     13815873.22
      2180356.78     13815493.05
#Sta/Elev= 30
  4714.1 1091.39  4716.5 1091.39  4735.7 1089.36  4812.9 1085.46  4835.0 1083.54
  4840.6 1083.34  4848.3 1081.05  4852.0 1080.46  4862.7 1079.09  4870.9 1078.75
  4929.1 1077.74  4980.2 1077.35  4998.4 1076.45  4998.7 1075.95  5002.2 1075.95
  5002.4 1076.45  5040.9 1077.34  5071.2 1076.80  5091.4 1077.34  5121.7 1076.71
  5131.8 1076.90  5147.3 1079.93  5152.4 1080.00  5174.3 1081.69  5217.8 1084.56
  5222.8 1084.22  5273.2 1086.01  5288.3 1086.05  5303.5 1086.89  5335.8 1087.36
#Mann=5,-1,0
  4714.1    0.07       0  4852.0   0.035       0  4998.4   0.035       0
  5002.4   0.035       0  5174.3    0.07       0
Bank Sta=4998.4,5002.4
Exp/Cntr=0.3,0.1

Type RM Length L Ch R = 1,512,161,161,161
BEGIN DESCRIPTION:
West Fork Tributary 5b 1.0
END DESCRIPTION:
XS GIS Cut Line= 3
      2180325.00     13816075.00      2180575.00     13815775.00
      2180425.01     13815575.01
#Sta/Elev= 30
  4608.9 1085.32  4622.6 1084.85  4644.7 1082.71  4659.0 1079.97  4678.6 1077.96
  4807.4 1074.93  4914.2 1073.75  4971.4 1073.73  4992.3 1072.84  4996.2 1072.04
  5002.5 1072.04  5004.7 1071.46  5005.0 1070.96  5008.5 1070.96  5008.7 1071.46
  5013.0 1071.56  5021.3 1073.48  5035.9 1074.06  5063.0 1074.29  5071.3 1073.51
  5077.5 1073.76  5092.1 1073.01  5099.4 1073.72  5106.7 1075.79  5109.3 1075.89
  5121.3 1077.32  5156.7 1079.90  5199.4 1081.86  5227.5 1082.21  5249.4 1083.60
#Mann=5,-1,0
  4608.9    0.07       0  4678.6   0.035       0  5004.7   0.035       0
  5008.7   0.035       0  5109.3    0.07       0
Bank Sta=5004.7,5008.7
Exp/Cntr=0.3,0.1

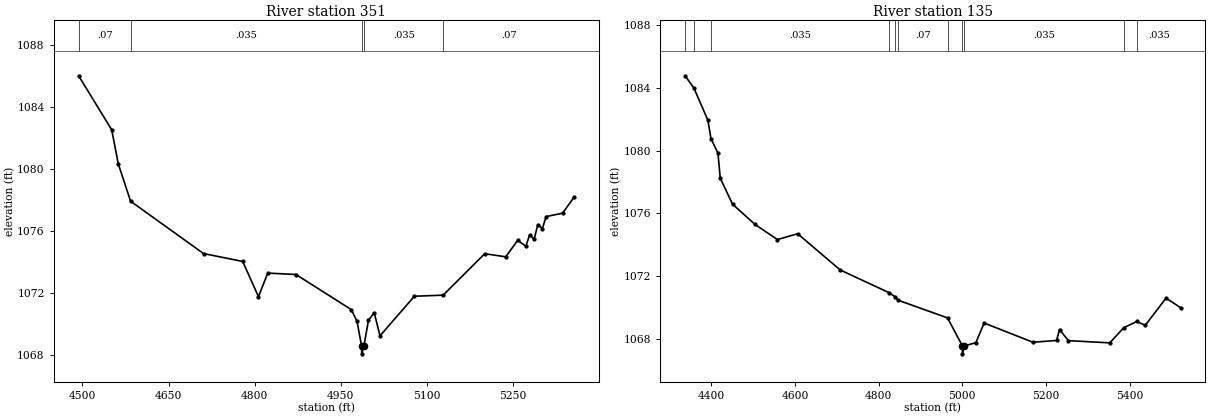
Type RM Length L Ch R = 1,351,216,216,216
BEGIN DESCRIPTION:
H21725
END DESCRIPTION:
XS GIS Cut Line= 4
      2180364.57     13816120.63      2180718.77     13815925.30
      2180718.77     13815722.18      2180557.33     13815524.28
#Sta/Elev= 30
  4493.4 1086.00  4551.0 1082.52  4562.5 1080.32  4583.9 1077.92  4710.9 1074.55
  4779.1 1074.04  4806.6 1071.77  4822.7 1073.29  4871.9 1073.20  4968.2 1070.94
  4978.2 1070.19  4986.2 1068.59  4986.4 1068.09  4990.2 1068.59  4998.2 1070.26
  5008.2 1070.74  5018.2 1069.25  5078.2 1071.80  5128.2 1071.87  5200.6 1074.54
  5237.2 1074.34  5258.0 1075.40  5272.3 1075.02  5278.8 1075.75  5286.7 1075.47
  5293.1 1076.42  5301.1 1076.16  5307.5 1076.93  5336.2 1077.15  5356.4 1078.19
#Mann=5,-1,0
  4493.4    0.07       0  4583.9   0.035       0  4986.2   0.035       0
  4990.2   0.035       0  5128.2    0.07       0
Bank Sta=4986.2,4990.2
Exp/Cntr=0.3,0.1

Type RM Length L Ch R = 1,135,0,0,0
BEGIN DESCRIPTION:
H21724
END DESCRIPTION:
XS GIS Cut Line= 4
      2180401.04     13816131.04      2180903.66     13815927.91
      2180911.48     13815662.28      2180640.99     13815399.60
#Sta/Elev= 30
  4337.0 1084.77  4358.2 1083.98  4391.5 1081.94  4398.8 1080.77  4415.6 1079.84
  4421.0 1078.25  4450.5 1076.59  4504.2 1075.30  4557.8 1074.34  4606.1 1074.71
  4708.0 1072.40  4824.3 1070.96  4838.2 1070.71  4846.9 1070.47  4964.5 1069.35
  5000.1 1067.56  5000.3 1067.06  5004.1 1067.56  5032.1 1067.77  5052.1 1069.02
  5168.6 1067.80  5225.2 1067.91  5232.4 1068.61  5253.5 1067.90  5352.5 1067.76
  5385.8 1068.72  5416.7 1069.12  5437.4 1068.88  5487.0 1070.61  5521.9 1070.00
#Mann=11,-1,0
  4337.0    0.12       0  4358.2    0.07       0  4398.8   0.035       0
  4824.3    0.07       0  4838.2    0.12       0  4846.9    0.07       0
  4964.5   0.035       0  5000.1   0.035       0  5004.1   0.035       0
  5385.8    0.07       0  5416.7   0.035       0
Bank Sta=5000.1,5004.1
Exp/Cntr=0.3,0.1

Chan Stop Cuts=-1