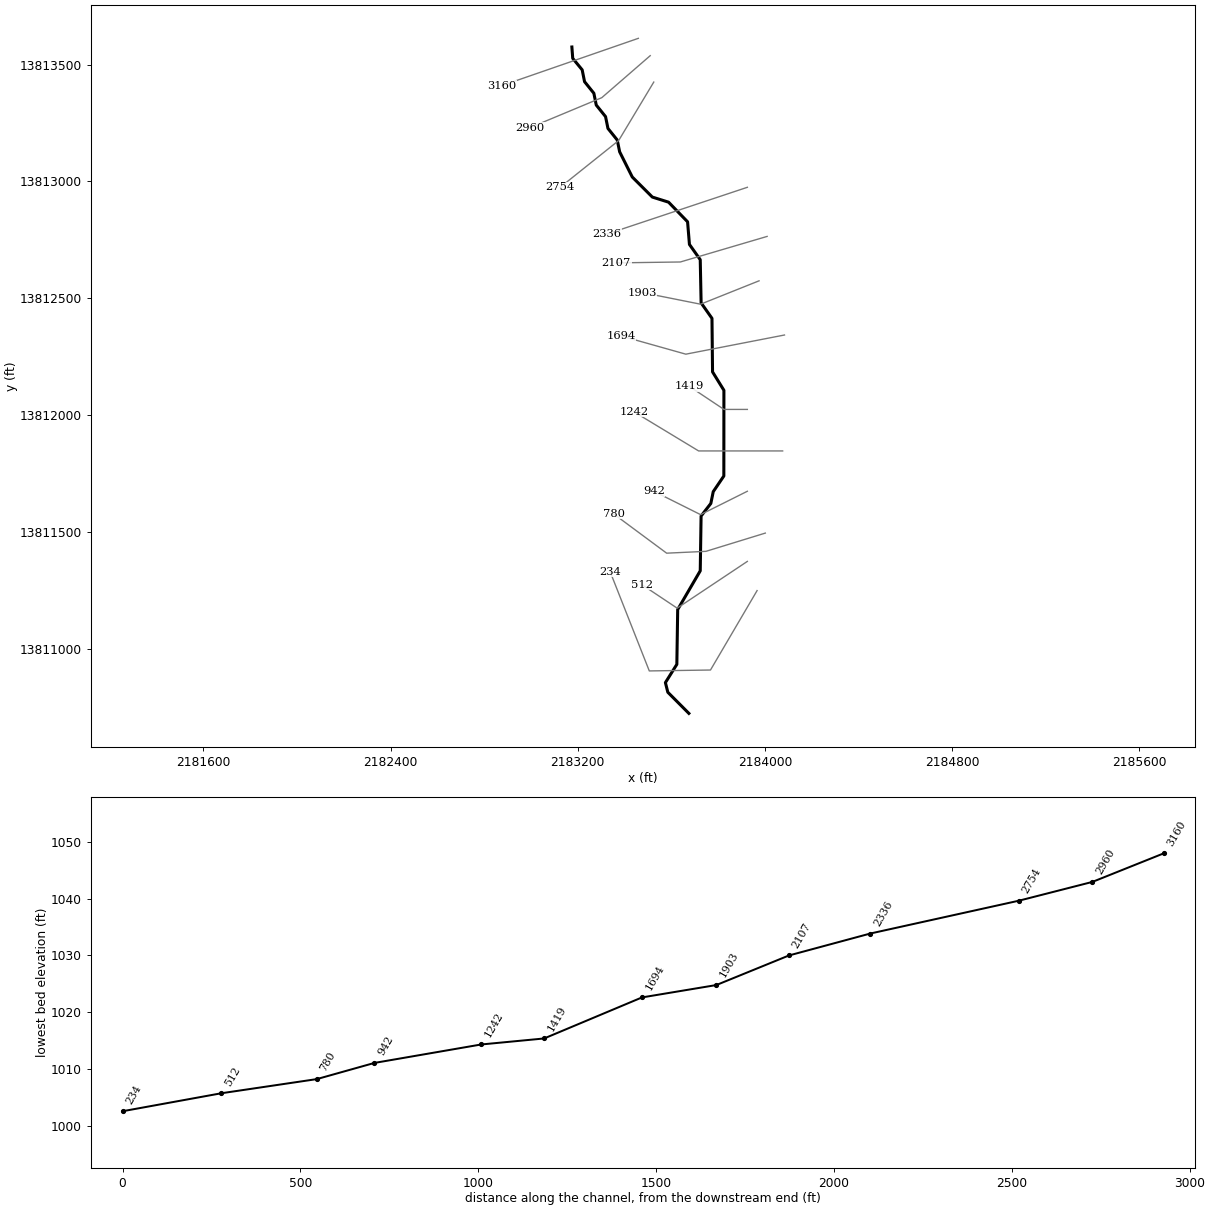
--- West Fork Tributary 6.prj (project) ---

Proj Title=West Fork Tributary 6 Base Level Engineering
Current Plan=p01
Default Exp/Contr=0.3,0.1
English Units
Geom File=g01
Flow File=f01
Plan File=p01
BEGIN DESCRIPTION:
West Fork Tributary 6
END DESCRIPTION:

--- West Fork Tributary 6.p01 (plan) ---

Plan Title=Multiple Run
Short Identifier=Multiple
Geom File=g01
Flow File=f01
Subcritical Flow
K Sum by GR= 0
Std Step Tol= 0.01
Critical Tol= 0.01
Num of Std Step Trials= 20
Max Error Tol= 0.3
Flow Tol Ratio= 0.001
Split Flow NTrial= 30
Split Flow Tol= 0.02
Split Flow Ratio= 0.02
Log Output Level= 0
Friction Slope Method= 1
Unsteady Friction Slope Method= 2
Unsteady Bridges Friction Slope Method= 1
Parabolic Critical Depth
Global Vel Dist=  1 , 1 , 1
Global Log Level= 0
CheckData=True
Encroach Param= -1, 0, 0, 0
BEGIN DESCRIPTION:
Multiple Run
END DESCRIPTION:

--- West Fork Tributary 6.f01 (steady flow) ---

Flow Title=Multiple
Number of Profiles=7
Profile Names=10-year,25-year,50-year,1pct_min,100-year,1pct_plu,500-year
River Rch & RM= West Fork Tribut,Reach-1,3160
     369     580     768     495     987    1969    1606
Boundary for River Rch & Prof#=West Fork Tribut,Reach-1,1
Up Type=0
Dn Type=3
Dn Slope=0.005
Boundary for River Rch & Prof#=West Fork Tribut,Reach-1,2
Up Type=0
Dn Type=3
Dn Slope=0.005
Boundary for River Rch & Prof#=West Fork Tribut,Reach-1,3
Up Type=0
Dn Type=3
Dn Slope=0.005
Boundary for River Rch & Prof#=West Fork Tribut,Reach-1,4
Up Type=0
Dn Type=3
Dn Slope=0.005
Boundary for River Rch & Prof#=West Fork Tribut,Reach-1,5
Up Type=0
Dn Type=3
Dn Slope=0.005
Boundary for River Rch & Prof#=West Fork Tribut,Reach-1,6
Up Type=0
Dn Type=3
Dn Slope=0.005
Boundary for River Rch & Prof#=West Fork Tribut,Reach-1,7
Up Type=0
Dn Type=3
Dn Slope=0.005

--- West Fork Tributary 6.g01 (geometry) ---

Geom Title=Existing Conditions

River Reach=West Fork Tribut,Reach-1
Reach XY= 30
      2183175.00     13813575.00      2183178.60     13813526.49
      2183219.05     13813477.25      2183229.14     13813426.72
      2183268.92     13813377.20      2183279.16     13813326.72
      2183318.92     13813277.20      2183329.16     13813226.72
      2183368.92     13813177.20      2183379.16     13813126.72
      2183433.13     13813018.93      2183518.94     13812933.15
      2183588.24     13812911.38      2183669.48     13812827.44
      2183677.47     13812730.57      2183723.62     13812665.34
      2183727.38     13812480.53      2183773.78     13812414.50
      2183776.22     13812185.50      2183824.79     13812106.73
      2183824.49     13811740.21      2183779.19     13811673.26
      2183768.88     13811622.82      2183727.24     13811569.07
      2183723.64     13811334.65      2183627.24     13811169.07
      2183623.60     13810934.65      2183574.74     13810856.55
      2183585.08     13810815.29      2183675.00     13810725.00

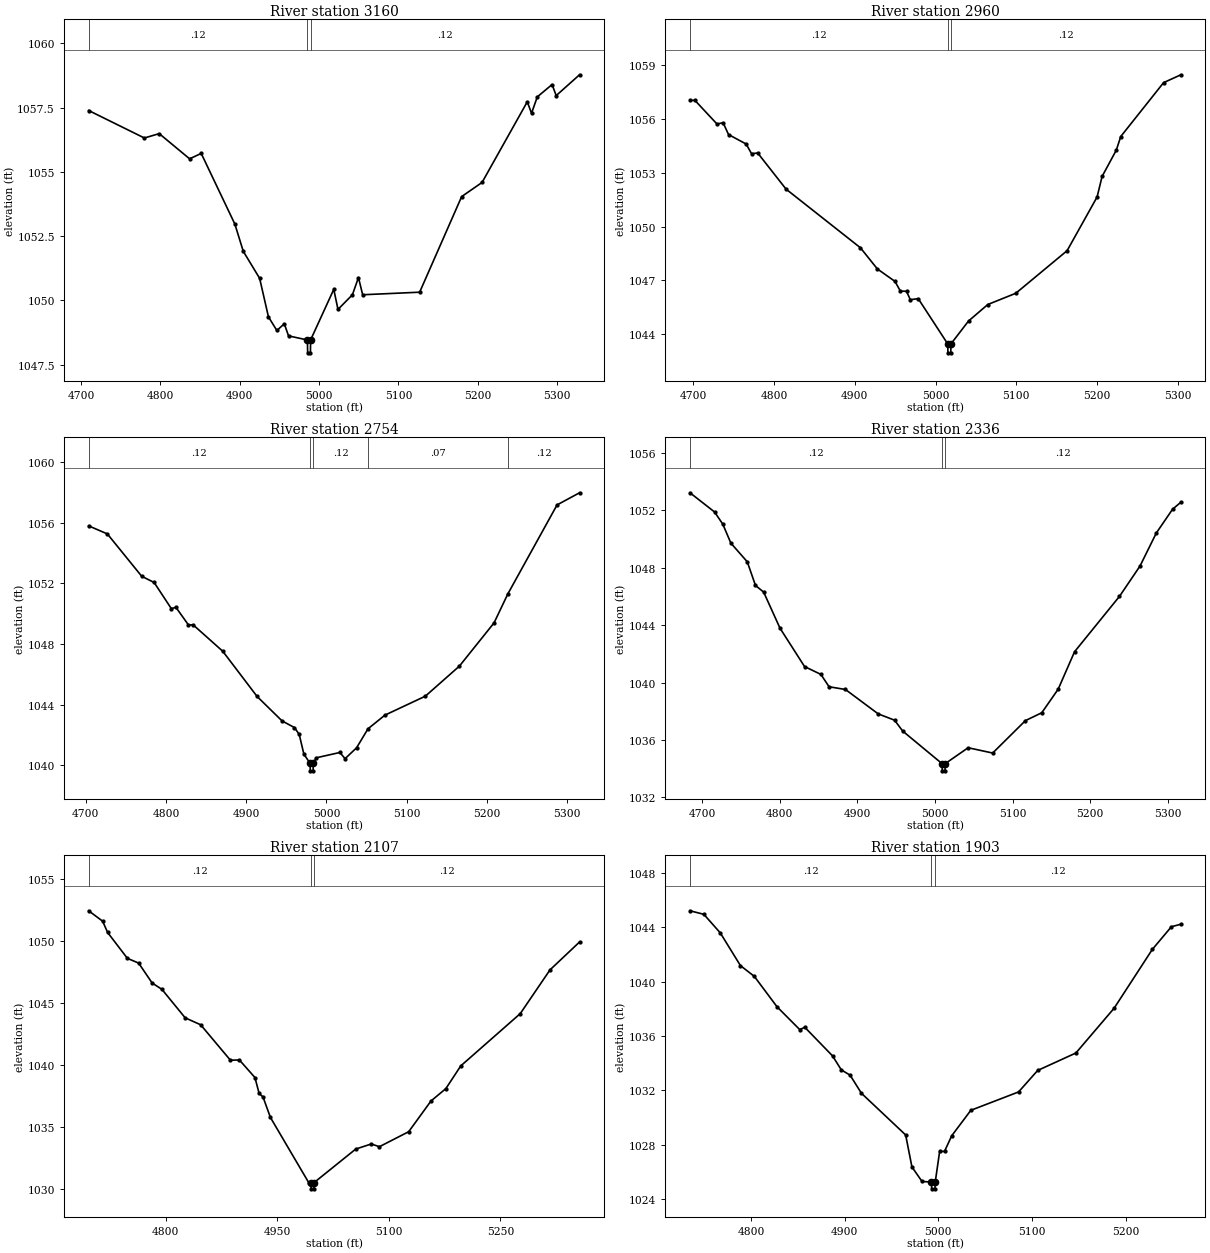
Type RM Length L Ch R = 1,3160,200,200,200
BEGIN DESCRIPTION:
H21735
END DESCRIPTION:
XS GIS Cut Line= 2
      2183459.01     13813612.08      2182874.73     13813409.53
#Sta/Elev= 30
  4709.7 1057.39  4779.9 1056.32  4798.6 1056.49  4836.9 1055.51  4851.5 1055.72
  4893.9 1052.97  4904.5 1051.91  4925.1 1050.86  4936.2 1049.36  4946.8 1048.83
  4956.2 1049.09  4961.5 1048.62  4985.3 1048.46  4985.6 1047.96  4989.1 1047.96
  4989.3 1048.46  5018.5 1050.43  5023.8 1049.65  5042.0 1050.22  5049.6 1050.89
  5054.9 1050.22  5126.7 1050.32  5179.6 1054.04  5205.3 1054.59  5262.3 1057.73
  5267.6 1057.28  5274.9 1057.92  5293.5 1058.40  5298.7 1057.97  5328.1 1058.78
#Mann=3,-1,0
  4709.7    0.12       0  4985.3    0.05       0  4989.3    0.12       0
Bank Sta=4985.3,4989.3
Exp/Cntr=0.3,0.1

Type RM Length L Ch R = 1,2960,206,206,206
BEGIN DESCRIPTION:
H21736
END DESCRIPTION:
XS GIS Cut Line= 3
      2183509.81     13813537.93      2183302.86     13813358.32
      2182995.06     13813229.75
#Sta/Elev= 30
  4696.1 1057.05  4702.2 1057.05  4729.5 1055.73  4737.1 1055.80  4743.8 1055.14
  4765.6 1054.61  4772.3 1054.07  4779.9 1054.11  4815.0 1052.09  4907.1 1048.81
  4928.0 1047.63  4949.9 1046.93  4956.5 1046.39  4964.1 1046.38  4968.8 1045.91
  4978.6 1045.97  5015.1 1043.44  5015.4 1042.94  5018.9 1042.94  5019.1 1043.44
  5040.9 1044.72  5064.7 1045.64  5099.4 1046.27  5162.9 1048.65  5200.0 1051.65
  5206.2 1052.80  5223.8 1054.27  5229.3 1055.03  5282.3 1058.04  5303.7 1058.48
#Mann=3,-1,0
  4696.1    0.12       0  5015.1    0.05       0  5019.1    0.12       0
Bank Sta=5015.1,5019.1
Exp/Cntr=0.3,0.1

Type RM Length L Ch R = 1,2754,418,418,418
BEGIN DESCRIPTION:
West Fork Tributary 6 6.0
END DESCRIPTION:
XS GIS Cut Line= 3
      2183524.98     13813424.97      2183375.00     13813175.00
      2183124.98     13812974.98
#Sta/Elev= 30
  4703.7 1055.78  4727.0 1055.25  4769.8 1052.46  4785.3 1052.05  4806.7 1050.33
  4812.5 1050.41  4828.1 1049.25  4833.9 1049.26  4870.8 1047.52  4913.6 1044.54
  4944.7 1042.93  4960.2 1042.49  4966.1 1042.04  4971.9 1040.74  4979.6 1040.14
  4979.9 1039.64  4983.4 1039.64  4983.6 1040.14  4987.4 1040.50  5016.8 1040.85
  5023.2 1040.44  5037.6 1041.16  5051.8 1042.41  5072.9 1043.31  5123.3 1044.56
  5165.7 1046.54  5208.9 1049.39  5226.1 1051.30  5287.4 1057.16  5315.4 1057.96
#Mann=5,-1,0
  4703.7    0.12       0  4979.6    0.05       0  4983.6    0.12       0
  5051.8    0.07       0  5226.1    0.12       0
Bank Sta=4979.6,4983.6
Exp/Cntr=0.3,0.1

Type RM Length L Ch R = 1,2336,229,229,229
BEGIN DESCRIPTION:
West Fork Tributary 6 5.0
END DESCRIPTION:
XS GIS Cut Line= 3
      2183925.03     13812975.01      2183625.00     13812875.00
      2183324.99     13812775.00
#Sta/Elev= 30
  4684.3 1053.23  4716.0 1051.89  4726.5 1051.05  4737.0 1049.72  4758.1 1048.42
  4768.7 1046.77  4779.2 1046.31  4800.3 1043.79  4831.9 1041.12  4853.0 1040.57
  4863.5 1039.71  4884.6 1039.52  4926.8 1037.82  4947.9 1037.38  4958.4 1036.62
  5009.1 1034.35  5009.4 1033.85  5012.9 1033.85  5013.1 1034.35  5042.7 1035.46
  5074.3 1035.09  5116.5 1037.35  5137.6 1037.90  5158.7 1039.54  5179.8 1042.15
  5237.7 1046.01  5264.1 1048.12  5285.2 1050.43  5306.2 1052.09  5316.8 1052.57
#Mann=3,-1,0
  4684.3    0.12       0  5009.1    0.05       0  5013.1    0.12       0
Bank Sta=5009.1,5013.1
Exp/Cntr=0.3,0.1

Type RM Length L Ch R = 1,2107,204,204,204
BEGIN DESCRIPTION:
H21737
END DESCRIPTION:
XS GIS Cut Line= 3
      2184009.48     13812764.89      2183638.61     13812655.58
      2183365.28     13812651.68
#Sta/Elev= 30
  4696.3 1052.42  4715.1 1051.58  4721.8 1050.67  4748.4 1048.58  4763.5 1048.20
  4781.7 1046.59  4794.8 1046.08  4826.1 1043.78  4846.9 1043.22  4886.9 1040.36
  4899.0 1040.38  4919.9 1038.96  4925.5 1037.68  4930.7 1037.40  4940.7 1035.74
  4992.1 1030.49  4995.3 1030.48  4995.6 1029.98  4999.1 1029.98  4999.3 1030.48
  5055.4 1033.19  5076.3 1033.60  5087.2 1033.38  5126.6 1034.59  5156.6 1037.07
  5176.6 1038.07  5196.6 1039.90  5276.6 1044.12  5316.6 1047.65  5356.3 1049.90
#Mann=3,-1,0
  4696.3    0.12       0  4995.3    0.05       0  4999.3    0.12       0
Bank Sta=4995.3,4999.3
Exp/Cntr=0.3,0.1

Type RM Length L Ch R = 1,1903,209,209,209
BEGIN DESCRIPTION:
West Fork Tributary 6 4.0
END DESCRIPTION:
XS GIS Cut Line= 3
      2183975.04     13812575.01      2183725.00     13812475.00
      2183475.05     13812524.99
#Sta/Elev= 30
  4734.8 1045.20  4749.6 1044.94  4767.1 1043.58  4788.7 1041.17  4803.5 1040.38
  4827.7 1038.15  4852.0 1036.47  4857.4 1036.64  4887.0 1034.54  4896.4 1033.51
  4905.8 1033.12  4917.9 1031.79  4965.1 1028.73  4971.8 1026.38  4982.6 1025.31
  4992.7 1025.27  4992.9 1024.77  4996.4 1024.77  4996.7 1025.27  5001.4 1027.52
  5006.6 1027.52  5014.3 1028.67  5034.7 1030.54  5085.7 1031.89  5106.1 1033.47
  5146.9 1034.75  5187.7 1038.04  5228.5 1042.36  5248.9 1044.03  5259.0 1044.21
#Mann=3,-1,0
  4734.8    0.12       0  4992.7    0.05       0  4996.7    0.12       0
Bank Sta=4992.7,4996.7
Exp/Cntr=0.3,0.1

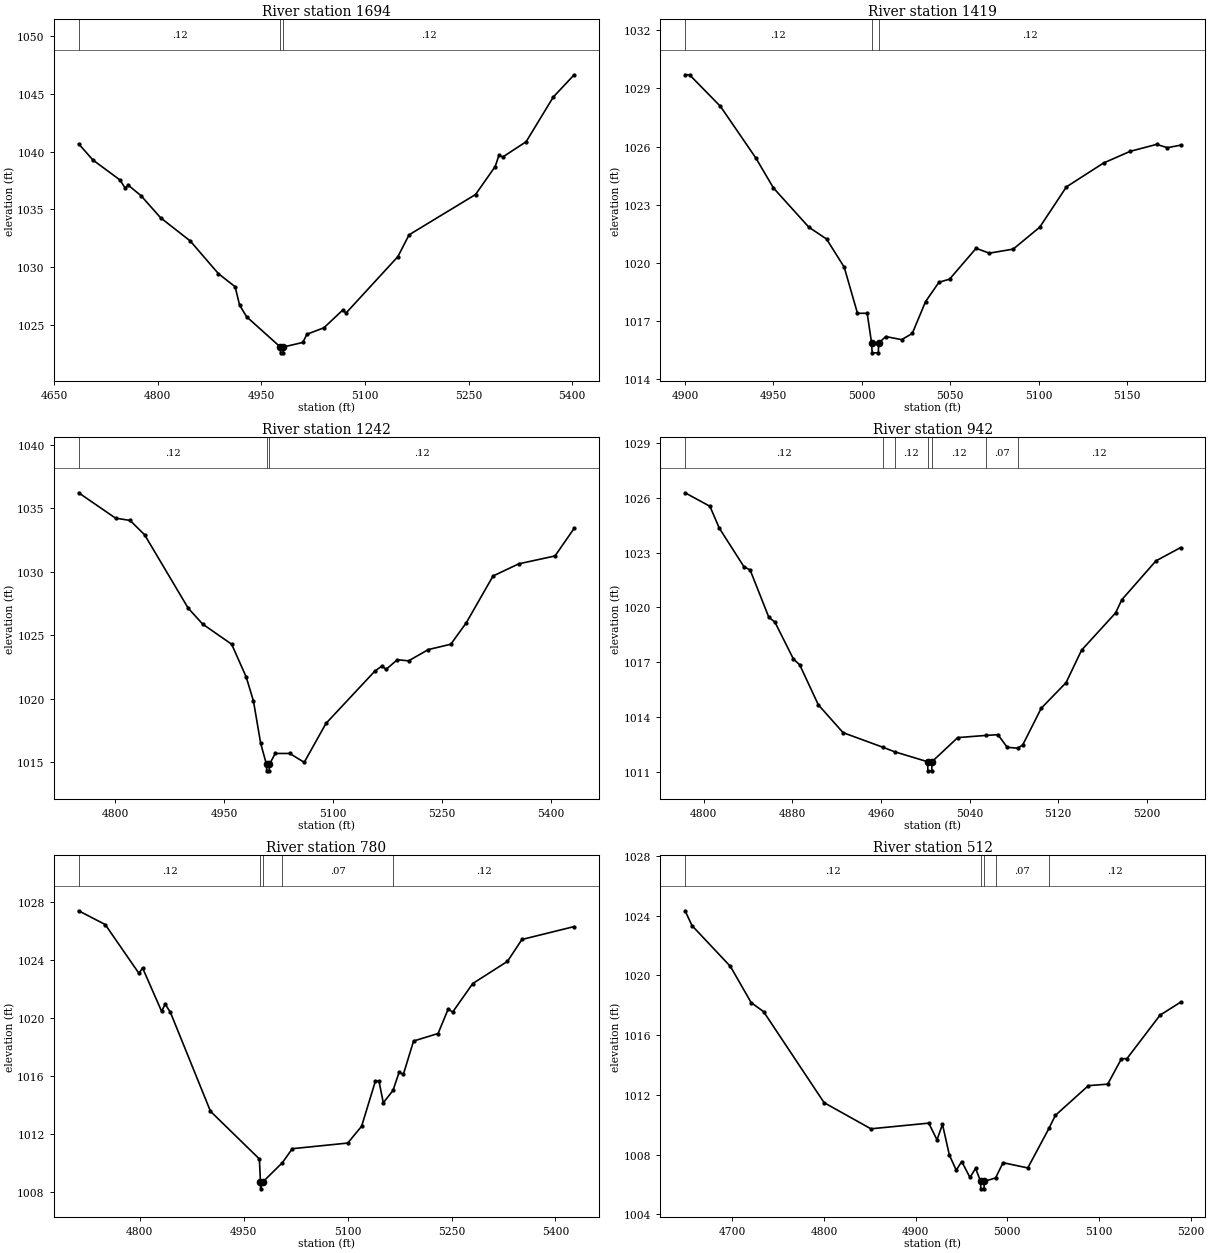
Type RM Length L Ch R = 1,1694,275,275,275
BEGIN DESCRIPTION:
H21734
END DESCRIPTION:
XS GIS Cut Line= 3
      2184083.67     13812343.25      2183662.04     13812261.27
      2183384.86     13812339.35
#Sta/Elev= 30
  4685.5 1040.68  4706.1 1039.28  4745.3 1037.55  4752.6 1036.87  4757.7 1037.08
  4775.8 1036.19  4804.3 1034.27  4847.1 1032.27  4887.9 1029.44  4912.1 1028.31
  4918.5 1026.73  4928.6 1025.72  4977.6 1023.09  4977.8 1022.59  4981.3 1022.59
  4981.6 1023.09  5010.1 1023.49  5016.1 1024.20  5040.7 1024.76  5067.7 1026.28
  5072.8 1026.04  5147.8 1030.92  5163.9 1032.80  5260.2 1036.29  5288.6 1038.71
  5294.3 1039.72  5299.5 1039.53  5333.5 1040.86  5372.7 1044.72  5403.0 1046.65
#Mann=3,-1,0
  4685.5    0.12       0  4977.6    0.05       0  4981.6    0.12       0
Bank Sta=4977.6,4981.6
Exp/Cntr=0.3,0.1

Type RM Length L Ch R = 1,1419,177,177,177
BEGIN DESCRIPTION:
West Fork Tributary 6 3.0
END DESCRIPTION:
XS GIS Cut Line= 3
      2183924.99     13812025.00      2183825.00     13812025.00
      2183674.97     13812125.02
#Sta/Elev= 30
  4900.1 1029.70  4902.6 1029.70  4920.1 1028.07  4940.1 1025.41  4950.1 1023.86
  4970.1 1021.84  4980.1 1021.23  4990.1 1019.78  4997.6 1017.40  5003.1 1017.40
  5005.6 1015.86  5005.9 1015.36  5009.4 1015.36  5009.6 1015.86  5013.6 1016.20
  5022.6 1016.04  5028.6 1016.36  5036.1 1018.00  5043.7 1019.00  5049.7 1019.16
  5064.7 1020.75  5072.2 1020.50  5085.7 1020.71  5100.7 1021.84  5115.8 1023.92
  5136.8 1025.15  5151.8 1025.75  5166.8 1026.11  5172.9 1025.94  5180.4 1026.07
#Mann=3,-1,0
  4900.1    0.12       0  5005.6    0.05       0  5009.6    0.12       0
Bank Sta=5005.6,5009.6
Exp/Cntr=0.3,0.1

Type RM Length L Ch R = 1,1242,300,300,300
BEGIN DESCRIPTION:
H21733
END DESCRIPTION:
XS GIS Cut Line= 3
      2184075.85     13811847.43      2183716.70     13811847.43
      2183439.78     13812015.14
#Sta/Elev= 30
  4749.2 1036.22  4800.1 1034.22  4820.1 1034.04  4840.1 1032.91  4900.1 1027.13
  4920.1 1025.87  4960.1 1024.28  4980.1 1021.70  4990.1 1019.81  5000.1 1016.46
  5008.1 1014.80  5008.3 1014.30  5011.8 1014.30  5012.1 1014.80  5020.1 1015.67
  5040.1 1015.67  5060.1 1014.97  5090.1 1018.04  5157.4 1022.16  5167.1 1022.56
  5172.9 1022.30  5188.4 1023.06  5203.9 1022.97  5231.1 1023.86  5262.1 1024.28
  5283.5 1025.98  5320.3 1029.66  5355.8 1030.62  5405.7 1031.24  5432.1 1033.42
#Mann=3,-1,0
  4749.2    0.12       0  5008.1    0.05       0  5012.1    0.12       0
Bank Sta=5008.1,5012.1
Exp/Cntr=0.3,0.1

Type RM Length L Ch R = 1,942,162,162,162
BEGIN DESCRIPTION:
West Fork Tributary 6 2.0
END DESCRIPTION:
XS GIS Cut Line= 3
      2183925.01     13811675.00      2183725.00     13811575.00
      2183525.02     13811674.99
#Sta/Elev= 30
  4783.3 1026.28  4805.7 1025.54  4814.1 1024.35  4836.4 1022.23  4842.0 1022.05
  4858.8 1019.47  4864.4 1019.19  4881.1 1017.17  4886.7 1016.86  4903.5 1014.67
  4925.9 1013.14  4961.9 1012.34  4972.6 1012.09  5002.1 1011.55  5002.4 1011.05
  5005.9 1011.05  5006.1 1011.55  5029.3 1012.87  5054.8 1012.99  5065.6 1013.03
  5074.0 1012.34  5083.4 1012.29  5088.0 1012.47  5104.7 1014.48  5127.1 1015.88
  5141.1 1017.66  5171.8 1019.70  5177.4 1020.42  5208.2 1022.55  5230.5 1023.28
#Mann=7,-1,0
  4783.3    0.12       0  4961.9    0.07       0  4972.6    0.12       0
  5002.1    0.05       0  5006.1    0.12       0  5054.8    0.07       0
  5083.4    0.12       0
Bank Sta=5002.1,5006.1
Exp/Cntr=0.3,0.1

Type RM Length L Ch R = 1,780,268,268,268
BEGIN DESCRIPTION:
H21738
END DESCRIPTION:
XS GIS Cut Line= 4
      2184001.74     13811496.07      2183747.93     13811417.98
      2183580.05     13811410.17      2183353.61     13811578.06
#Sta/Elev= 30
  4711.6 1027.39  4750.0 1026.44  4798.7 1023.07  4803.9 1023.45  4831.4 1020.45
  4836.6 1020.95  4844.2 1020.37  4902.0 1013.55  4972.6 1010.26  4974.1 1008.70
  4974.3 1008.20  4978.1 1008.70  5005.9 1010.01  5020.1 1010.97  5100.2 1011.36
  5120.2 1012.52  5140.2 1015.65  5145.2 1015.65  5151.5 1014.14  5165.5 1014.99
  5174.3 1016.24  5180.6 1016.12  5195.2 1018.40  5230.6 1018.92  5245.3 1020.62
  5251.5 1020.39  5280.7 1022.37  5330.8 1023.90  5351.7 1025.41  5427.1 1026.30
#Mann=5,-1,0
  4711.6    0.12       0  4974.1    0.05       0  4978.1    0.12       0
  5005.9    0.07       0  5165.5    0.12       0
Bank Sta=4974.1,4978.1
Exp/Cntr=0.3,0.1

Type RM Length L Ch R = 1,512,278,278,278
BEGIN DESCRIPTION:
West Fork Tributary 6 1.0
END DESCRIPTION:
XS GIS Cut Line= 3
      2183924.97     13811374.98      2183625.00     13811175.00
      2183475.00     13811275.00
#Sta/Elev= 30
  4648.3 1024.33  4655.8 1023.34  4697.8 1020.60  4720.4 1018.18  4733.9 1017.58
  4800.0 1011.48  4851.1 1009.73  4914.2 1010.11  4923.2 1008.99  4929.2 1010.03
  4936.7 1007.97  4944.2 1006.96  4950.2 1007.54  4959.2 1006.47  4965.3 1007.08
  4970.8 1006.21  4971.0 1005.71  4974.5 1005.71  4974.8 1006.21  4987.1 1006.44
  4995.3 1007.46  5022.3 1007.11  5045.5 1009.77  5052.4 1010.63  5088.4 1012.62
  5109.5 1012.72  5124.5 1014.42  5130.5 1014.43  5166.6 1017.34  5189.1 1018.21
#Mann=5,-1,0
  4648.3    0.12       0  4970.8    0.05       0  4974.8    0.12       0
  4987.1    0.07       0  5045.5    0.12       0
Bank Sta=4970.8,4974.8
Exp/Cntr=0.3,0.1

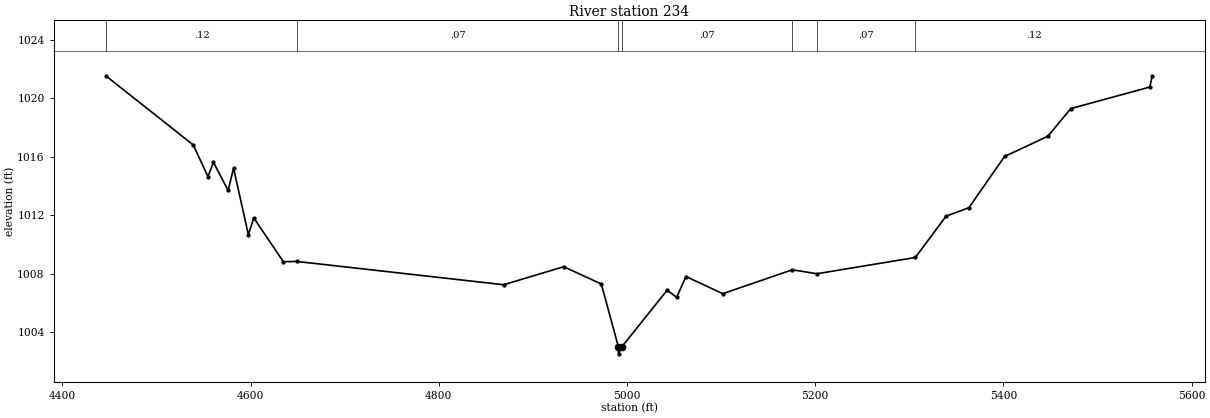
Type RM Length L Ch R = 1,234,0,0,0
BEGIN DESCRIPTION:
H21732
END DESCRIPTION:
XS GIS Cut Line= 4
      2183966.57     13811250.12      2183767.45     13810910.45
      2183505.88     13810906.54      2183338.41     13811331.06
#Sta/Elev= 30
  4446.5 1021.51  4539.0 1016.81  4554.7 1014.65  4560.5 1015.62  4576.1 1013.70
  4581.9 1015.22  4597.6 1010.68  4603.4 1011.82  4634.8 1008.83  4649.1 1008.85
  4868.9 1007.26  4932.7 1008.49  4972.7 1007.31  4990.7 1003.04  4991.0 1002.54
  4994.7 1003.04  5042.7 1006.89  5052.7 1006.40  5062.7 1007.82  5101.8 1006.65
  5175.6 1008.28  5201.8 1008.01  5306.4 1009.12  5339.0 1011.94  5363.3 1012.52
  5401.2 1016.02  5447.2 1017.40  5471.6 1019.29  5555.5 1020.76  5558.2 1021.53
#Mann=7,-1,0
  4446.5    0.12       0  4649.1    0.07       0  4990.7    0.05       0
  4994.7    0.07       0  5175.6   0.035       0  5201.8    0.07       0
  5306.4    0.12       0
Bank Sta=4990.7,4994.7
Exp/Cntr=0.3,0.1

Chan Stop Cuts=-1