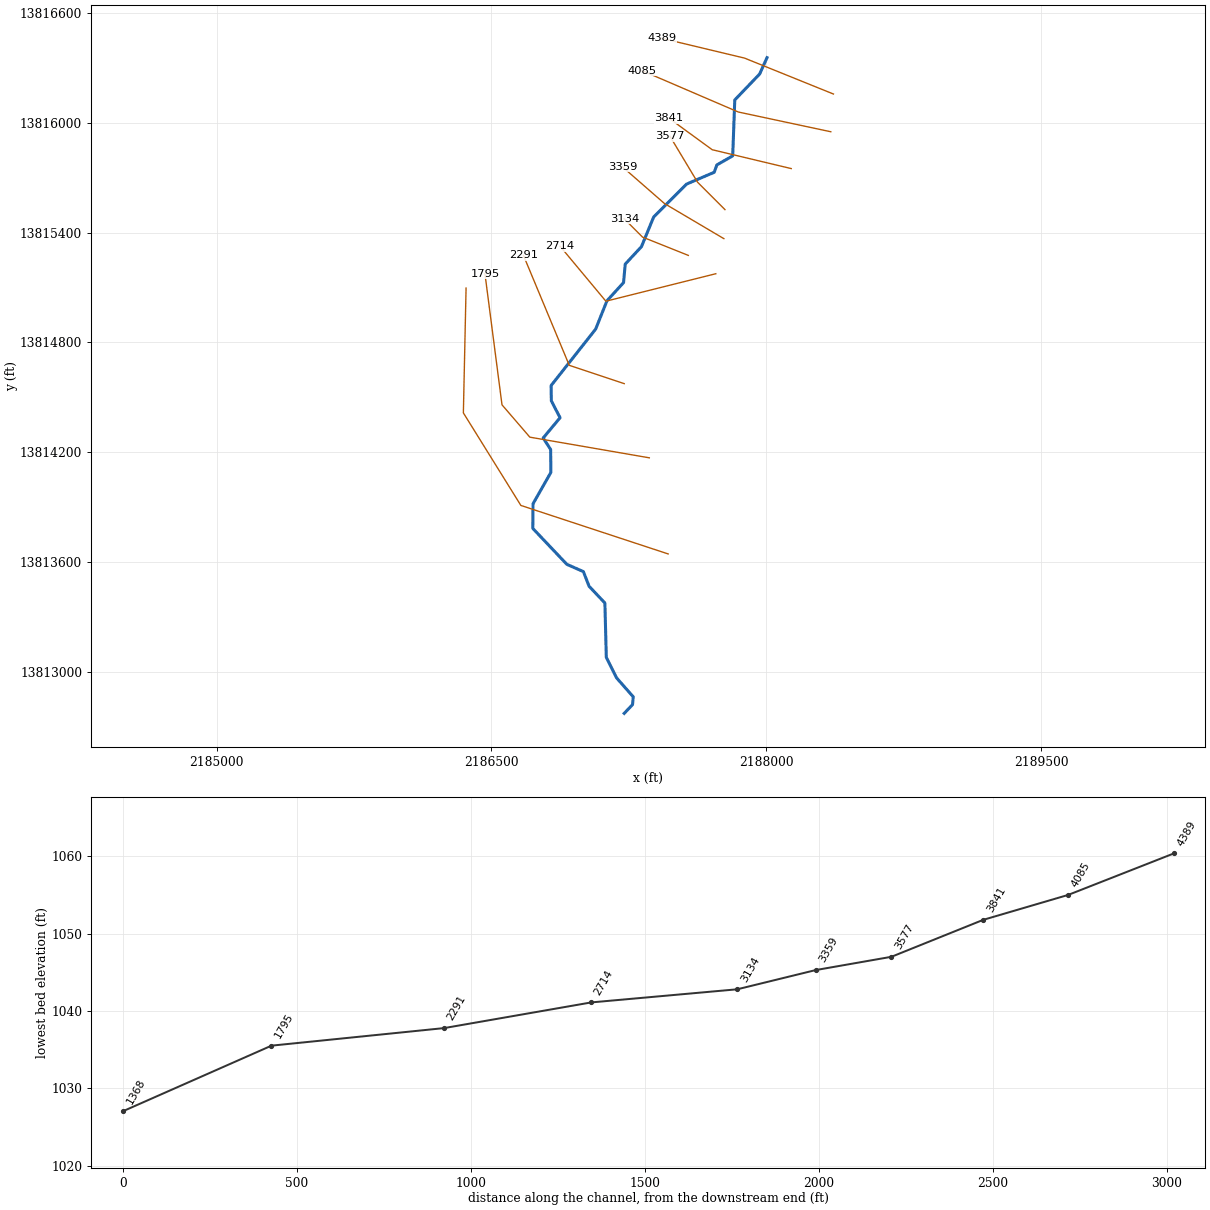
--- West Fork Tributary 7.prj (project) ---

Proj Title=West Fork Tributary 7 Base Level Engineering
Current Plan=p01
Default Exp/Contr=0.3,0.1
English Units
Geom File=g01
Flow File=f01
Plan File=p01
BEGIN DESCRIPTION:
West Fork Tributary 7
END DESCRIPTION:

--- West Fork Tributary 7.p01 (plan) ---

Plan Title=Multiple Run
Short Identifier=Multiple
Geom File=g01
Flow File=f01
Subcritical Flow
K Sum by GR= 0
Std Step Tol= 0.01
Critical Tol= 0.01
Num of Std Step Trials= 20
Max Error Tol= 0.3
Flow Tol Ratio= 0.001
Split Flow NTrial= 30
Split Flow Tol= 0.02
Split Flow Ratio= 0.02
Log Output Level= 0
Friction Slope Method= 1
Unsteady Friction Slope Method= 2
Unsteady Bridges Friction Slope Method= 1
Parabolic Critical Depth
Global Vel Dist=  1 , 1 , 1
Global Log Level= 0
CheckData=True
Encroach Param= -1, 0, 0, 0
BEGIN DESCRIPTION:
Multiple Run
END DESCRIPTION:

--- West Fork Tributary 7.f01 (steady flow) ---

Flow Title=Multiple
Number of Profiles=7
Profile Names=10-year,25-year,50-year,1pct_min,100-year,1pct_plu,500-year
River Rch & RM= West Fork Tribut,Reach-1,4389
     499     798    1066     691    1379    2752    2283
Boundary for River Rch & Prof#=West Fork Tribut,Reach-1,1
Up Type=0
Dn Type=3
Dn Slope=0.005
Boundary for River Rch & Prof#=West Fork Tribut,Reach-1,2
Up Type=0
Dn Type=3
Dn Slope=0.005
Boundary for River Rch & Prof#=West Fork Tribut,Reach-1,3
Up Type=0
Dn Type=3
Dn Slope=0.005
Boundary for River Rch & Prof#=West Fork Tribut,Reach-1,4
Up Type=0
Dn Type=3
Dn Slope=0.005
Boundary for River Rch & Prof#=West Fork Tribut,Reach-1,5
Up Type=0
Dn Type=3
Dn Slope=0.005
Boundary for River Rch & Prof#=West Fork Tribut,Reach-1,6
Up Type=0
Dn Type=3
Dn Slope=0.005
Boundary for River Rch & Prof#=West Fork Tribut,Reach-1,7
Up Type=0
Dn Type=3
Dn Slope=0.005

--- West Fork Tributary 7.g01 (geometry) ---

Geom Title=Existing Conditions

River Reach=West Fork Tribut,Reach-1
Reach XY= 30
      2188004.54     13816354.54      2187964.40     13816265.25
      2187828.54     13816123.54      2187817.26     13815818.54
      2187730.80     13815769.00      2187716.38     13815728.84
      2187565.32     13815664.24      2187385.76     13815484.68
      2187319.15     13815322.71      2187230.54     13815227.42
      2187221.37     13815126.50      2187130.85     13815027.29
      2187069.15     13814872.71      2186825.93     13814564.52
      2186827.19     13814480.97      2186874.89     13814389.04
      2186782.81     13814278.41      2186823.46     13814215.41
      2186824.51     13814090.22      2186727.23     13813919.07
      2186726.19     13813784.59      2186911.80     13813588.64
      2187002.14     13813548.84      2187033.19     13813468.98
      2187119.53     13813377.45      2187127.24     13813080.93
      2187183.16     13812968.95      2187274.34     13812865.29
      2187270.43     13812822.65      2187225.00     13812775.00

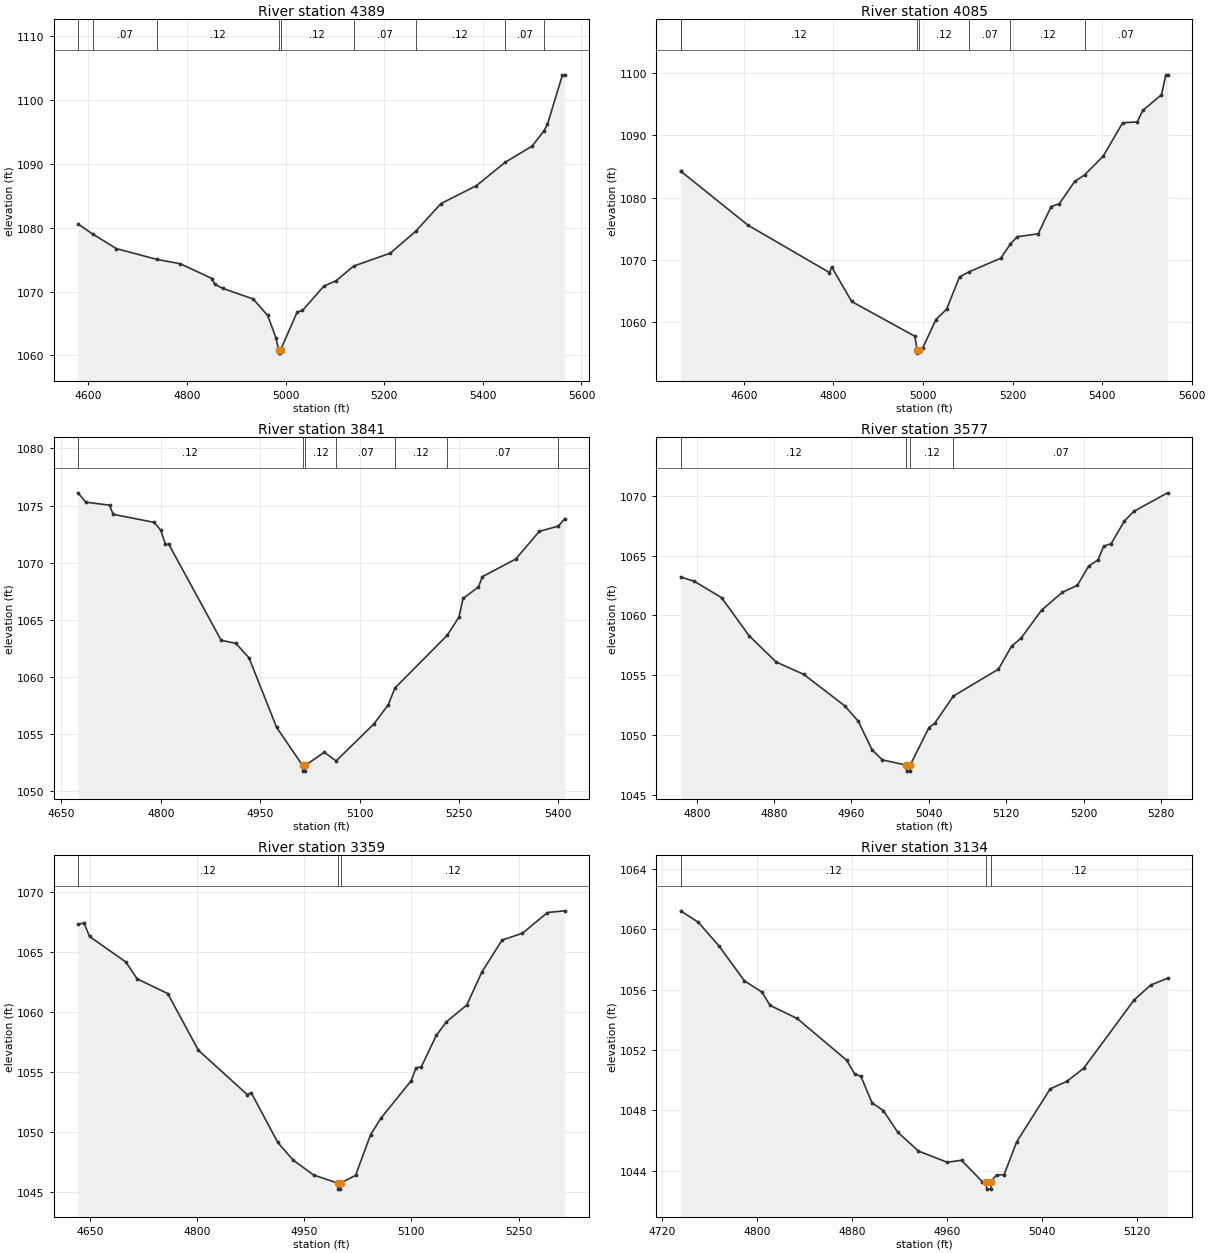
Type RM Length L Ch R = 1,4389,304,304,304
BEGIN DESCRIPTION:
H21743
END DESCRIPTION:
XS GIS Cut Line= 3
      2188367.25     13816155.95      2187881.81     13816352.09
      2187430.70     13816459.97
#Sta/Elev= 30
  4578.9 1080.58  4608.6 1079.01  4656.8 1076.72  4738.7 1075.03  4786.3 1074.35
  4851.0 1072.03  4856.5 1071.12  4872.5 1070.50  4934.3 1068.83  4963.8 1066.25
  4980.4 1062.77  4985.9 1060.86  4986.2 1060.36  4989.7 1060.36  4989.9 1060.86
  5023.5 1066.79  5034.3 1067.04  5077.5 1070.83  5102.5 1071.69  5138.0 1073.98
  5212.3 1076.00  5263.8 1079.42  5315.1 1083.76  5387.1 1086.57  5445.1 1090.21
  5500.2 1092.77  5523.8 1095.13  5531.0 1096.17  5561.5 1103.91  5566.3 1103.91
#Mann=9,-1,0
  4578.9   0.035       0  4608.6    0.07       0  4738.7    0.12       0
  4985.9    0.05       0  4989.9    0.12       0  5138.0    0.07       0
  5263.8    0.12       0  5445.1    0.07       0  5523.8    0.12       0
Bank Sta=4985.9,4989.9
Exp/Cntr=0.3,0.1

Type RM Length L Ch R = 1,4085,244,244,244
BEGIN DESCRIPTION:
West Fork Tributary 7 5.0
END DESCRIPTION:
XS GIS Cut Line= 3
      2188352.59     13815950.00      2187847.49     13816057.88
      2187322.82     13816283.44
#Sta/Elev= 30
  4458.6 1084.29  4459.0 1084.23  4609.5 1075.53  4791.1 1067.94  4796.2 1068.81
  4840.6 1063.29  4981.9 1057.70  4986.7 1055.49  4986.9 1054.99  4990.7 1055.49
  4999.6 1055.86  5028.9 1060.39  5052.5 1062.04  5081.5 1067.24  5102.3 1068.04
  5173.7 1070.25  5194.6 1072.46  5210.1 1073.69  5257.2 1074.17  5286.2 1078.55
  5304.3 1078.99  5338.7 1082.58  5361.2 1083.65  5402.3 1086.64  5445.9 1092.01
  5478.5 1092.16  5490.8 1093.99  5532.5 1096.51  5542.3 1099.72  5546.2 1099.72
#Mann=7,-1,0
  4458.6   0.035       0  4459.0    0.12       0  4986.7    0.05       0
  4990.7    0.12       0  5102.3    0.07       0  5194.6    0.12       0
  5361.2    0.07       0
Bank Sta=4986.7,4990.7
Exp/Cntr=0.3,0.1

Type RM Length L Ch R = 1,3841,264,264,264
BEGIN DESCRIPTION:
H21742
END DESCRIPTION:
XS GIS Cut Line= 3
      2188136.75     13815748.97      2187705.29     13815851.94
      2187469.98     13816023.52
#Sta/Elev= 30
  4675.0 1076.11  4687.1 1075.29  4722.8 1075.03  4728.2 1074.23  4789.9 1073.53
  4800.2 1072.83  4807.0 1071.60  4812.1 1071.62  4891.2 1063.21  4913.3 1062.95
  4933.3 1061.67  4974.9 1055.59  5014.1 1052.27  5014.3 1051.77  5017.8 1051.77
  5018.1 1052.27  5046.9 1053.42  5064.6 1052.66  5121.9 1055.91  5143.4 1057.58
  5153.4 1059.04  5232.2 1063.64  5250.0 1065.24  5256.2 1066.87  5279.3 1067.87
  5285.5 1068.78  5335.7 1070.32  5371.3 1072.74  5400.0 1073.20  5409.8 1073.86
#Mann=7,-1,0
  4675.0    0.12       0  5014.1    0.05       0  5018.1    0.12       0
  5064.6    0.07       0  5153.4    0.12       0  5232.2    0.07       0
  5400.0    0.12       0
Bank Sta=5014.1,5018.1
Exp/Cntr=0.3,0.1

Type RM Length L Ch R = 1,3577,218,218,218
BEGIN DESCRIPTION:
West Fork Tributary 7 4.0
END DESCRIPTION:
XS GIS Cut Line= 3
      2187774.97     13815525.03      2187625.00     13815675.00
      2187475.02     13815924.97
#Sta/Elev= 30
  4783.3 1063.21  4797.4 1062.85  4825.7 1061.48  4854.0 1058.31  4882.2 1056.10
  4910.5 1055.08  4953.0 1052.45  4967.1 1051.15  4981.2 1048.78  4991.9 1047.93
  5016.7 1047.49  5017.0 1046.99  5020.5 1046.99  5020.7 1047.49  5040.1 1050.62
  5045.9 1050.97  5065.4 1053.26  5112.0 1055.51  5125.6 1057.43  5135.3 1058.09
  5156.7 1060.45  5178.1 1061.93  5193.6 1062.51  5205.3 1064.12  5215.0 1064.64
  5220.8 1065.78  5228.6 1066.00  5242.2 1067.88  5251.9 1068.69  5286.9 1070.24
#Mann=4,-1,0
  4783.3    0.12       0  5016.7    0.05       0  5020.7    0.12       0
  5065.4    0.07       0
Bank Sta=5016.7,5020.7
Exp/Cntr=0.3,0.1

Type RM Length L Ch R = 1,3359,225,225,225
BEGIN DESCRIPTION:
H21741
END DESCRIPTION:
XS GIS Cut Line= 3
      2187769.05     13815366.48      2187445.40     13815557.73
      2187214.91     13815758.80
#Sta/Elev= 30
  4633.0 1067.31  4641.7 1067.40  4649.3 1066.29  4700.2 1064.16  4715.9 1062.76
  4758.8 1061.54  4801.6 1056.83  4870.0 1053.14  4875.8 1053.28  4912.9 1049.15
  4934.3 1047.69  4962.9 1046.45  4996.7 1045.77  4996.9 1045.27  5000.4 1045.27
  5000.7 1045.77  5021.8 1046.42  5042.7 1049.78  5057.0 1051.15  5099.7 1054.29
  5106.3 1055.35  5113.9 1055.45  5134.8 1058.05  5149.0 1059.19  5177.5 1060.58
  5198.4 1063.30  5226.9 1065.99  5255.4 1066.55  5290.5 1068.28  5314.8 1068.42
#Mann=3,-1,0
  4633.0    0.12       0  4996.7    0.05       0  5000.7    0.12       0
Bank Sta=4996.7,5000.7
Exp/Cntr=0.3,0.1

Type RM Length L Ch R = 1,3134,420,420,420
BEGIN DESCRIPTION:
West Fork Tributary 7 3.0
END DESCRIPTION:
XS GIS Cut Line= 3
      2187574.98     13815275.01      2187325.00     13815375.00
      2187224.97     13815475.03
#Sta/Elev= 30
  4735.3 1061.22  4750.1 1060.47  4767.6 1058.90  4789.1 1056.58  4803.9 1055.84
  4810.7 1054.96  4833.6 1054.09  4875.3 1051.33  4882.0 1050.43  4887.4 1050.25
  4896.8 1048.50  4906.3 1047.99  4918.4 1046.56  4935.9 1045.31  4960.1 1044.57
  4972.2 1044.70  4989.7 1043.29  4993.1 1043.29  4993.4 1042.79  4996.9 1042.79
  4997.1 1043.29  5001.8 1043.74  5008.1 1043.74  5018.7 1045.92  5047.0 1049.43
  5061.1 1049.93  5075.2 1050.79  5117.7 1055.31  5131.8 1056.31  5146.0 1056.75
#Mann=3,-1,0
  4735.3    0.12       0  4993.1    0.05       0  4997.1    0.12       0
Bank Sta=4993.1,4997.1
Exp/Cntr=0.3,0.1

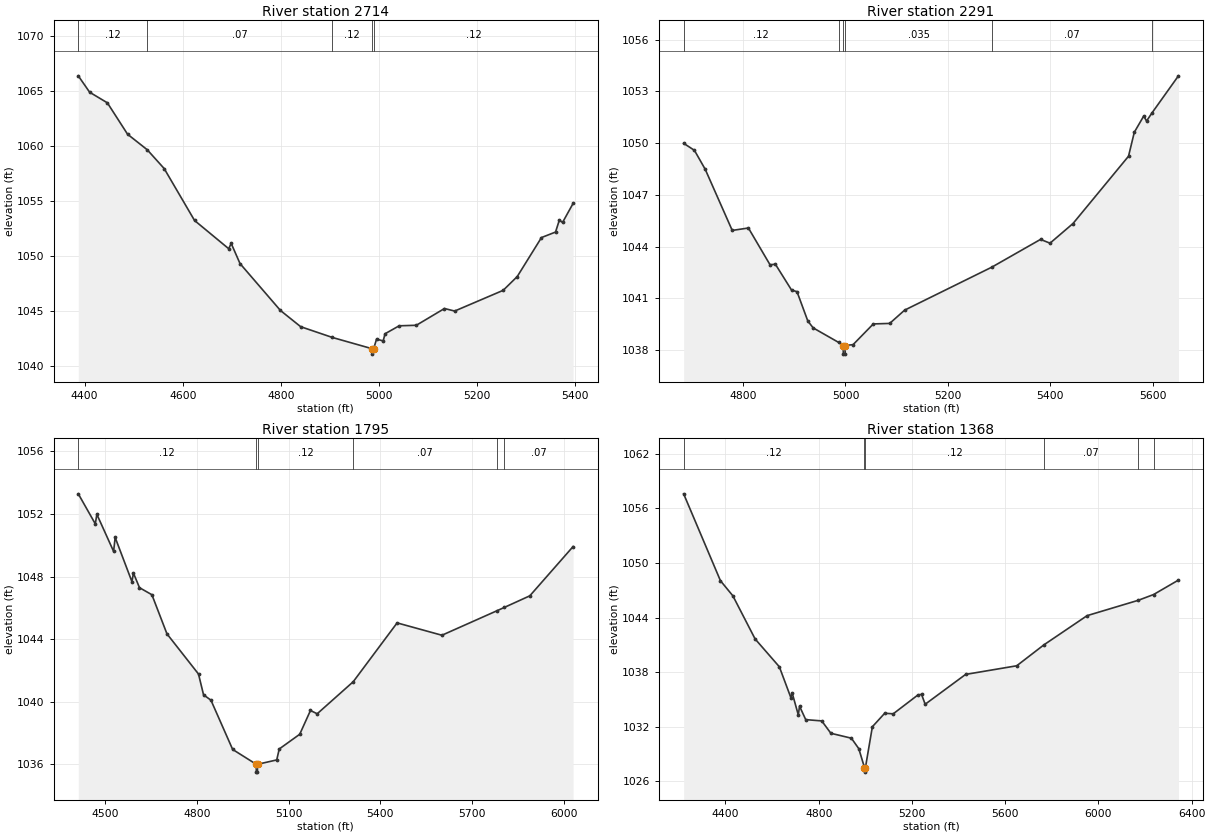
Type RM Length L Ch R = 1,2714,423,423,423
BEGIN DESCRIPTION:
West Fork Tributary 7 2.0
END DESCRIPTION:
XS GIS Cut Line= 3
      2187724.99     13815175.00      2187125.00     13815025.00
      2186874.98     13815325.02
#Sta/Elev= 30
  4387.1 1066.35  4410.3 1064.86  4446.4 1063.90  4487.6 1061.05  4527.7 1059.64
  4562.3 1057.93  4624.2 1053.22  4693.8 1050.66  4698.9 1051.14  4716.9 1049.31
  4799.4 1045.05  4840.6 1043.58  4905.4 1042.60  4985.5 1041.59  4985.8 1041.09
  4989.5 1041.59  4995.3 1042.45  5008.8 1042.29  5012.7 1042.94  5041.4 1043.66
  5076.5 1043.71  5133.8 1045.23  5154.6 1045.00  5253.5 1046.88  5282.2 1048.13
  5331.6 1051.67  5360.3 1052.17  5368.1 1053.26  5374.6 1053.04  5396.1 1054.77
#Mann=5,-1,0
  4387.1    0.12       0  4527.7    0.07       0  4905.4    0.12       0
  4985.5    0.05       0  4989.5    0.12       0
Bank Sta=4985.5,4989.5
Exp/Cntr=0.3,0.1

Type RM Length L Ch R = 1,2291,496,496,496
BEGIN DESCRIPTION:
West Fork Tributary 7 1.0
END DESCRIPTION:
XS GIS Cut Line= 3
      2187225.03     13814574.99      2186925.00     13814675.00
      2186674.98     13815275.04
#Sta/Elev= 30
  4684.0 1049.99  4705.1 1049.58  4726.2 1048.48  4778.9 1044.94  4810.5 1045.08
  4852.7 1042.95  4863.2 1042.98  4894.8 1041.48  4905.4 1041.39  4926.5 1039.69
  4937.0 1039.29  4986.6 1038.45  4995.6 1038.27  4995.9 1037.77  4999.4 1037.77
  4999.6 1038.27  5014.9 1038.32  5054.4 1039.52  5086.4 1039.55  5115.6 1040.32
  5285.8 1042.81  5381.0 1044.42  5399.5 1044.20  5444.4 1045.34  5552.8 1049.24
  5564.1 1050.63  5582.5 1051.57  5588.0 1051.28  5599.1 1051.77  5650.3 1053.90
#Mann=6,-1,0
  4684.0    0.12       0  4986.6   0.035       0  4995.6   0.035       0
  4999.6   0.035       0  5285.8    0.07       0  5599.1    0.12       0
Bank Sta=4995.6,4999.6
Exp/Cntr=0.3,0.1

Type RM Length L Ch R = 1,1795,427,427,427
BEGIN DESCRIPTION:
H21740
END DESCRIPTION:
XS GIS Cut Line= 4
      2187362.03     13814170.04      2186709.88     13814282.82
      2186557.87     13814459.35      2186464.71     13815175.23
#Sta/Elev= 30
  4413.0 1053.29  4468.6 1051.37  4473.7 1051.98  4528.4 1049.61  4533.5 1050.50
  4588.2 1047.68  4593.3 1048.22  4613.0 1047.29  4653.5 1046.84  4702.7 1044.34
  4805.8 1041.77  4822.3 1040.44  4846.4 1040.10  4917.4 1036.95  4994.6 1036.00
  4994.8 1035.50  4998.3 1035.50  4998.6 1036.00  5061.4 1036.28  5069.6 1036.98
  5136.5 1037.92  5171.6 1039.44  5193.6 1039.23  5311.4 1041.28  5454.7 1045.04
  5601.1 1044.25  5781.4 1045.82  5805.2 1046.03  5888.3 1046.77  6029.7 1049.92
#Mann=6,-1,0
  4413.0    0.12       0  4994.6    0.05       0  4998.6    0.12       0
  5311.4    0.07       0  5781.4   0.035       0  5805.2    0.07       0
Bank Sta=4994.6,4998.6
Exp/Cntr=0.3,0.1

Type RM Length L Ch R = 1,1368,0,0,0
BEGIN DESCRIPTION:
H21739
END DESCRIPTION:
XS GIS Cut Line= 4
      2187465.02     13813645.37      2186660.85     13813910.16
      2186347.02     13814415.22      2186361.73     13815096.80
#Sta/Elev= 30
  4220.4 1057.61  4378.3 1048.06  4431.6 1046.40  4527.0 1041.66  4631.0 1038.60
  4680.6 1035.20  4685.9 1035.74  4712.4 1033.31  4717.7 1034.27  4744.2 1032.79
  4813.0 1032.65  4852.1 1031.29  4940.1 1030.75  4971.9 1029.60  4996.4 1027.52
  4996.7 1027.02  5000.4 1027.52  5030.2 1032.01  5083.1 1033.49  5119.7 1033.43
  5226.0 1035.51  5241.3 1035.56  5256.7 1034.48  5430.2 1037.76  5649.6 1038.71
  5766.2 1041.01  5951.5 1044.22  6171.4 1045.91  6236.7 1046.54  6343.4 1048.13
#Mann=6,-1,0
  4220.4    0.12       0  4996.4    0.05       0  5000.4    0.12       0
  5766.2    0.07       0  6171.4   0.035       0  6236.7    0.07       0
Bank Sta=4996.4,5000.4
Exp/Cntr=0.3,0.1

Chan Stop Cuts=-1