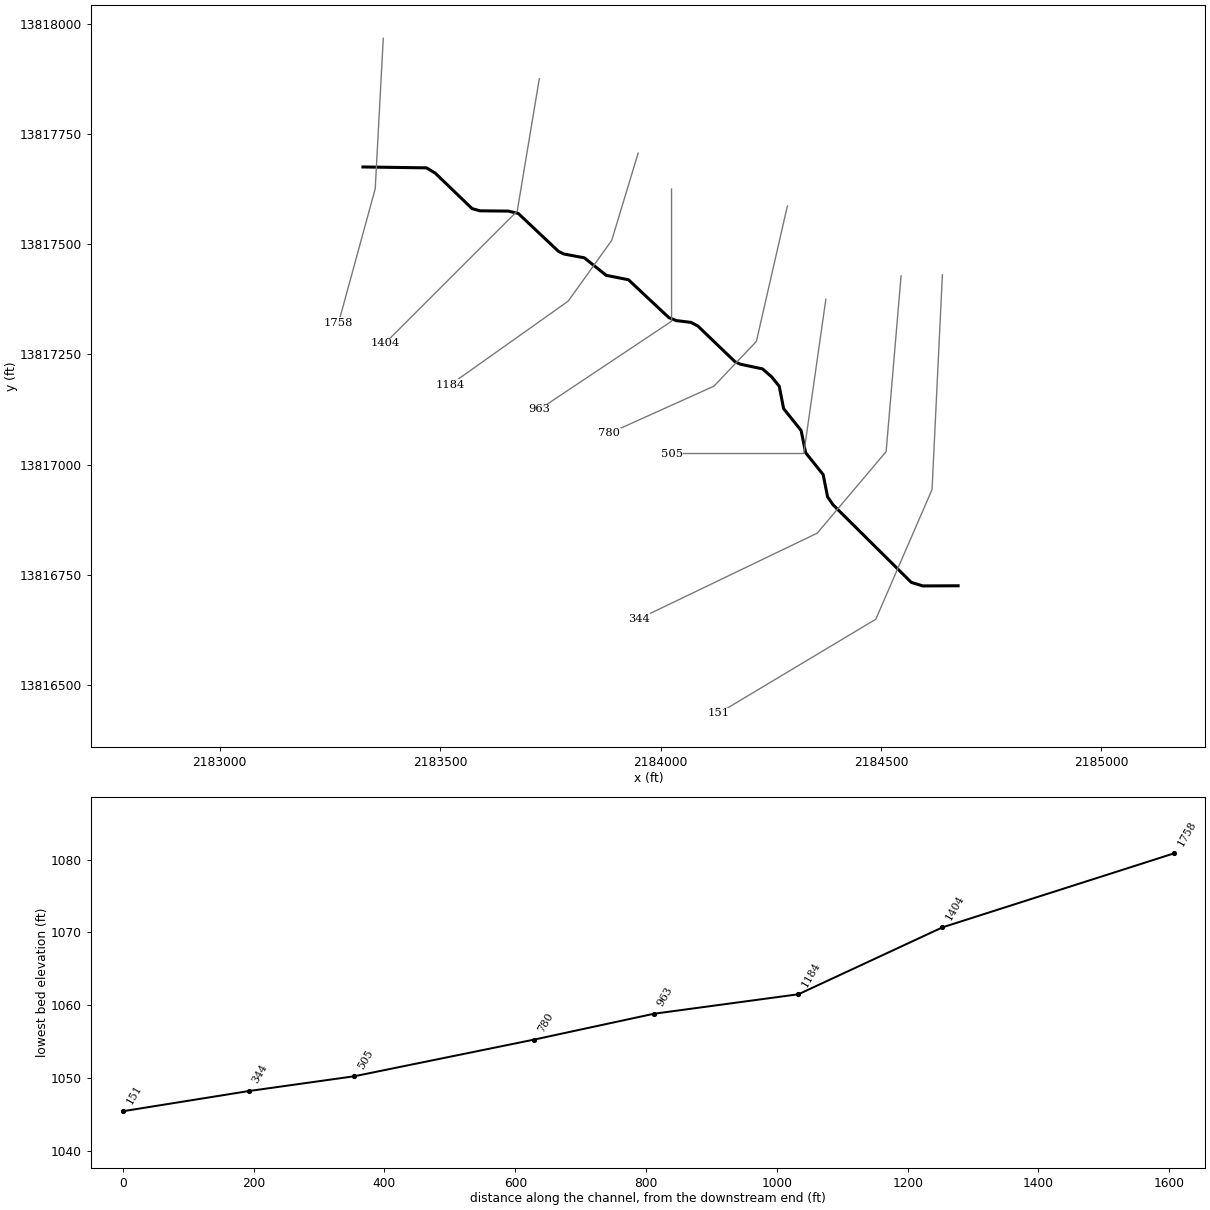
--- West Fork Tributary 8.prj (project) ---

Proj Title=West Fork Tributary 8 Base Level Engineering
Current Plan=p01
Default Exp/Contr=0.3,0.1
English Units
Geom File=g01
Flow File=f01
Plan File=p01
BEGIN DESCRIPTION:
West Fork Tributary 8
END DESCRIPTION:

--- West Fork Tributary 8.p01 (plan) ---

Plan Title=Multiple Run
Short Identifier=Multiple
Geom File=g01
Flow File=f01
Subcritical Flow
K Sum by GR= 0
Std Step Tol= 0.01
Critical Tol= 0.01
Num of Std Step Trials= 20
Max Error Tol= 0.3
Flow Tol Ratio= 0.001
Split Flow NTrial= 30
Split Flow Tol= 0.02
Split Flow Ratio= 0.02
Log Output Level= 0
Friction Slope Method= 1
Unsteady Friction Slope Method= 2
Unsteady Bridges Friction Slope Method= 1
Parabolic Critical Depth
Global Vel Dist=  1 , 1 , 1
Global Log Level= 0
CheckData=True
Encroach Param= -1, 0, 0, 0
BEGIN DESCRIPTION:
Multiple Run
END DESCRIPTION:

--- West Fork Tributary 8.f01 (steady flow) ---

Flow Title=Multiple
Number of Profiles=7
Profile Names=10-year,25-year,50-year,1pct_min,100-year,1pct_plu,500-year
River Rch & RM= West Fork Tribut,Reach-1,1758
     310     486     642     414     825    1647    1342
Boundary for River Rch & Prof#=West Fork Tribut,Reach-1,1
Up Type=0
Dn Type=3
Dn Slope=0.005
Boundary for River Rch & Prof#=West Fork Tribut,Reach-1,2
Up Type=0
Dn Type=3
Dn Slope=0.005
Boundary for River Rch & Prof#=West Fork Tribut,Reach-1,3
Up Type=0
Dn Type=3
Dn Slope=0.005
Boundary for River Rch & Prof#=West Fork Tribut,Reach-1,4
Up Type=0
Dn Type=3
Dn Slope=0.005
Boundary for River Rch & Prof#=West Fork Tribut,Reach-1,5
Up Type=0
Dn Type=3
Dn Slope=0.005
Boundary for River Rch & Prof#=West Fork Tribut,Reach-1,6
Up Type=0
Dn Type=3
Dn Slope=0.005
Boundary for River Rch & Prof#=West Fork Tribut,Reach-1,7
Up Type=0
Dn Type=3
Dn Slope=0.005

--- West Fork Tributary 8.g01 (geometry) ---

Geom Title=Existing Conditions

River Reach=West Fork Tribut,Reach-1
Reach XY= 30
      2183325.00     13817675.00      2183469.16     13817672.98
      2183488.79     13817661.19      2183572.45     13817580.61
      2183590.22     13817575.53      2183654.94     13817574.86
      2183677.42     13817569.46      2183768.95     13817483.16
      2183781.04     13817477.51      2183827.19     13817468.90
      2183876.73     13817429.19      2183927.29     13817419.15
      2184018.96     13817333.18      2184035.64     13817326.55
      2184068.95     13817322.46      2184084.67     13817314.20
      2184168.98     13817233.18      2184180.68     13817227.67
      2184231.33     13817216.96      2184252.14     13817198.84
      2184269.27     13817177.55      2184279.20     13817126.76
      2184318.92     13817077.20      2184329.16     13817026.72
      2184368.90     13816977.19      2184378.95     13816926.63
      2184391.64     13816908.32      2184568.78     13816732.74
      2184594.86     13816724.67      2184675.00     13816725.00

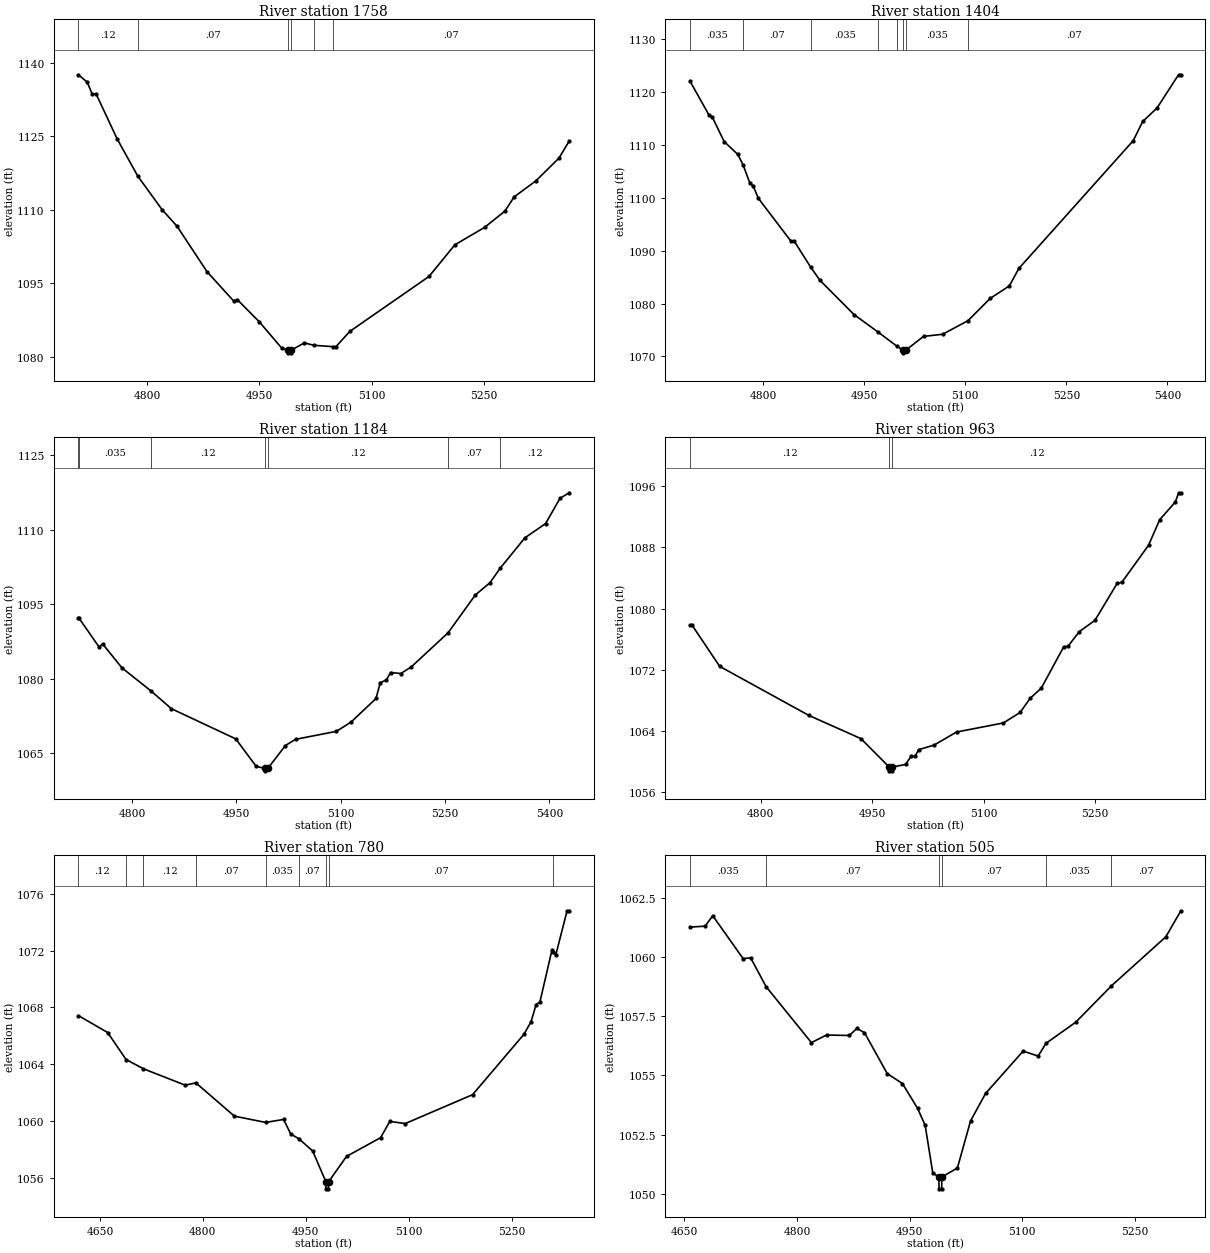
Type RM Length L Ch R = 1,1758,354,354,354
BEGIN DESCRIPTION:
H21748
END DESCRIPTION:
XS GIS Cut Line= 3
      2183371.09     13817966.76      2183352.86     13817625.67
      2183269.76     13817321.81
#Sta/Elev= 30
  4707.9 1137.59  4719.7 1136.09  4726.5 1133.61  4731.5 1133.71  4759.7 1124.51
  4787.2 1116.94  4819.8 1110.07  4839.9 1106.67  4879.9 1097.41  4915.4 1091.45
  4920.4 1091.71  4950.0 1087.15  4980.1 1081.76  4988.1 1081.34  4988.3 1080.84
  4991.8 1080.84  4992.1 1081.34  5010.1 1082.87  5022.9 1082.38  5048.3 1082.10
  5052.4 1082.10  5070.9 1085.21  5176.9 1096.43  5211.4 1102.88  5251.1 1106.43
  5278.3 1109.75  5290.8 1112.67  5319.7 1115.92  5350.8 1120.60  5364.5 1124.09
#Mann=6,-1,0
  4707.9    0.12       0  4787.2    0.07       0  4988.1    0.05       0
  4992.1    0.07       0  5022.9   0.035       0  5048.3    0.07       0
Bank Sta=4988.1,4992.1
Exp/Cntr=0.3,0.1

Type RM Length L Ch R = 1,1404,220,220,220
BEGIN DESCRIPTION:
West Fork Tributary 8 3.0
END DESCRIPTION:
XS GIS Cut Line= 3
      2183725.00     13817874.99      2183675.00     13817575.00
      2183374.99     13817274.99
#Sta/Elev= 30
  4691.5 1122.06  4719.4 1115.71  4724.4 1115.31  4742.2 1110.63  4762.5 1108.19
  4770.5 1106.15  4780.2 1102.82  4785.3 1102.22  4792.9 1099.90  4841.0 1091.84
  4846.1 1091.80  4870.7 1086.86  4884.1 1084.42  4934.8 1077.92  4971.0 1074.56
  4998.2 1071.96  5007.8 1071.17  5008.0 1070.67  5011.8 1071.17  5038.0 1073.78
  5066.3 1074.18  5103.9 1076.74  5137.0 1080.97  5165.3 1083.32  5179.5 1086.63
  5349.2 1110.80  5363.3 1114.43  5384.5 1116.97  5416.4 1123.26  5419.9 1123.26
#Mann=8,-1,0
  4691.5   0.035       0  4770.5    0.07       0  4870.7   0.035       0
  4971.0    0.07       0  4998.2   0.035       0  5007.8   0.035       0
  5011.8   0.035       0  5103.9    0.07       0
Bank Sta=5007.8,5011.8
Exp/Cntr=0.3,0.1

Type RM Length L Ch R = 1,1184,221,221,221
BEGIN DESCRIPTION:
H21747
END DESCRIPTION:
XS GIS Cut Line= 4
      2183949.21     13817706.37      2183889.32     13817508.48
      2183790.36     13817370.46      2183522.10     13817180.33
#Sta/Elev= 30
  4723.1 1092.30  4723.6 1092.30  4752.8 1086.42  4758.0 1087.03  4785.7 1082.22
  4827.4 1077.57  4856.8 1073.99  4949.2 1067.92  4978.7 1062.36  4991.4 1061.98
  4991.7 1061.48  4995.4 1061.98  5020.5 1066.57  5035.2 1067.83  5093.8 1069.43
  5115.1 1071.32  5150.8 1076.06  5156.9 1079.25  5165.5 1079.76  5171.7 1081.28
  5186.4 1081.08  5201.2 1082.38  5254.4 1089.29  5293.5 1096.90  5314.6 1099.37
  5329.5 1102.34  5364.8 1108.42  5394.4 1111.27  5415.3 1116.39  5428.5 1117.48
#Mann=7,-1,0
  4723.1    0.07       0  4723.6   0.035       0  4827.4    0.12       0
  4991.4    0.05       0  4995.4    0.12       0  5254.4    0.07       0
  5329.5    0.12       0
Bank Sta=4991.4,4995.4
Exp/Cntr=0.3,0.1

Type RM Length L Ch R = 1,963,183,183,183
BEGIN DESCRIPTION:
West Fork Tributary 8 2.0
END DESCRIPTION:
XS GIS Cut Line= 3
      2184025.00     13817624.98      2184025.00     13817325.00
      2183725.03     13817125.02
#Sta/Elev= 30
  4704.8 1077.88  4707.3 1077.88  4744.8 1072.45  4864.8 1066.04  4934.8 1063.01
  4972.8 1059.30  4973.0 1058.80  4976.5 1058.80  4976.8 1059.30  4994.8 1059.63
  5002.3 1060.70  5007.8 1060.70  5012.3 1061.56  5033.3 1062.17  5063.4 1063.87
  5126.5 1065.06  5149.0 1066.43  5162.5 1068.28  5177.5 1069.61  5207.6 1075.00
  5213.6 1075.10  5228.6 1076.99  5249.7 1078.47  5279.7 1083.32  5285.7 1083.42
  5321.8 1088.28  5336.8 1091.62  5357.8 1093.93  5362.3 1095.14  5365.3 1095.14
#Mann=3,-1,0
  4704.8    0.12       0  4972.8    0.05       0  4976.8    0.12       0
Bank Sta=4972.8,4976.8
Exp/Cntr=0.3,0.1

Type RM Length L Ch R = 1,780,275,275,275
BEGIN DESCRIPTION:
H21746
END DESCRIPTION:
XS GIS Cut Line= 4
      2184287.75     13817586.57      2184217.45     13817279.31
      2184121.09     13817177.75      2183884.13     13817070.99
#Sta/Elev= 30
  4618.7 1067.43  4661.3 1066.24  4688.2 1064.34  4713.5 1063.69  4774.2 1062.54
  4789.9 1062.70  4846.0 1060.36  4891.5 1059.92  4917.6 1060.13  4928.1 1059.10
  4939.6 1058.78  4959.9 1057.92  4979.2 1055.75  4979.4 1055.25  4982.9 1055.25
  4983.2 1055.75  5009.3 1057.53  5059.0 1058.85  5072.3 1059.99  5094.9 1059.84
  5192.9 1061.87  5267.8 1066.12  5278.0 1066.99  5285.5 1068.21  5291.0 1068.38
  5308.6 1072.05  5310.7 1071.91  5314.1 1071.69  5330.6 1074.80  5333.8 1074.80
#Mann=9,-1,0
  4618.7    0.12       0  4688.2    0.07       0  4713.5    0.12       0
  4789.9    0.07       0  4891.5   0.035       0  4939.6    0.07       0
  4979.2    0.05       0  4983.2    0.07       0  5310.7    0.12       0
Bank Sta=4979.2,4983.2
Exp/Cntr=0.3,0.1

Type RM Length L Ch R = 1,505,161,161,161
BEGIN DESCRIPTION:
West Fork Tributary 8 1.0
END DESCRIPTION:
XS GIS Cut Line= 3
      2184375.00     13817374.98      2184325.00     13817025.00
      2184025.03     13817025.00
#Sta/Elev= 30
  4657.7 1061.27  4677.9 1061.31  4688.0 1061.75  4728.4 1059.94  4738.5 1059.97
  4759.1 1058.75  4819.3 1056.39  4839.5 1056.71  4869.8 1056.69  4879.9 1056.99
  4890.0 1056.81  4920.3 1055.08  4940.5 1054.66  4960.7 1053.61  4970.8 1052.89
  4980.9 1050.88  4989.0 1050.71  4989.3 1050.21  4992.8 1050.21  4993.0 1050.71
  5013.7 1051.09  5031.2 1053.08  5051.2 1054.24  5101.2 1056.03  5121.2 1055.82
  5131.7 1056.36  5171.2 1057.25  5218.8 1058.79  5291.2 1060.86  5311.2 1061.96
#Mann=6,-1,0
  4657.7   0.035       0  4759.1    0.07       0  4989.0    0.05       0
  4993.0    0.07       0  5131.7   0.035       0  5218.8    0.07       0
Bank Sta=4989,4993
Exp/Cntr=0.3,0.1

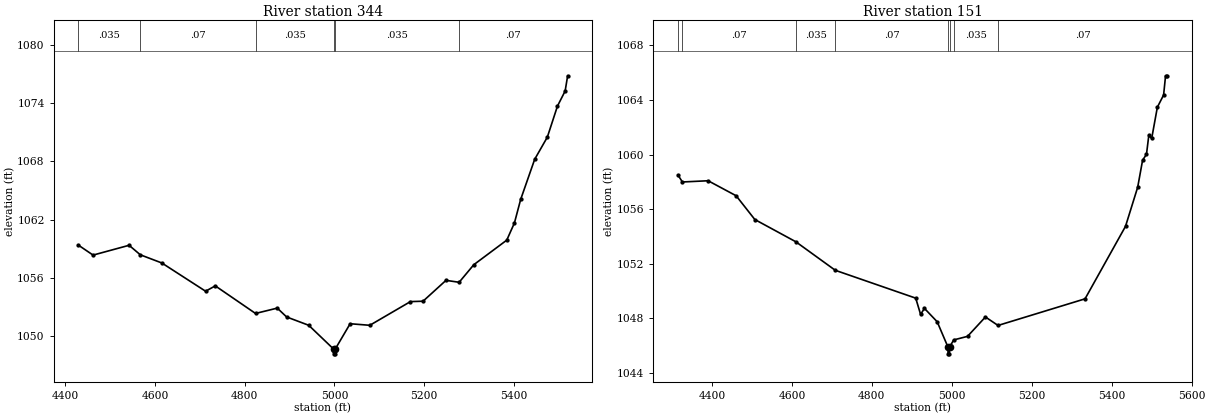
Type RM Length L Ch R = 1,344,193,193,193
BEGIN DESCRIPTION:
H21745
END DESCRIPTION:
XS GIS Cut Line= 4
      2184545.58     13817427.79      2184511.72     13817029.31
      2184355.47     13816844.42      2183950.52     13816649.73
#Sta/Elev= 30
  4428.7 1059.38  4461.6 1058.35  4541.9 1059.36  4567.0 1058.38  4614.9 1057.54
  4712.5 1054.63  4734.2 1055.18  4823.9 1052.34  4872.4 1052.89  4893.2 1051.98
  4942.6 1051.12  4997.8 1048.68  4998.1 1048.18  5001.6 1048.18  5001.8 1048.68
  5034.9 1051.28  5078.8 1051.12  5169.4 1053.56  5197.5 1053.60  5248.7 1055.75
  5278.0 1055.55  5310.7 1057.36  5384.2 1059.89  5401.3 1061.66  5415.2 1064.08
  5446.5 1068.22  5474.7 1070.50  5497.3 1073.70  5514.4 1075.25  5520.0 1076.82
#Mann=6,-1,0
  4428.7   0.035       0  4567.0    0.07       0  4823.9   0.035       0
  4997.8   0.035       0  5001.8   0.035       0  5278.0    0.07       0
Bank Sta=4997.8,5001.8
Exp/Cntr=0.3,0.1

Type RM Length L Ch R = 1,151,0,0,0
BEGIN DESCRIPTION:
H21744
END DESCRIPTION:
XS GIS Cut Line= 4
      2184639.33     13817430.40      2184615.89     13816943.38
      2184488.28     13816649.10      2184131.54     13816435.58
#Sta/Elev= 30
  4314.9 1058.50  4326.0 1057.99  4390.4 1058.08  4460.5 1056.98  4507.2 1055.24
  4609.8 1053.61  4708.5 1051.52  4909.7 1049.48  4921.9 1048.29  4931.5 1048.73
  4963.4 1047.75  4990.3 1045.90  4990.6 1045.40  4994.1 1045.40  4994.3 1045.90
  5004.8 1046.42  5039.3 1046.68  5084.1 1048.10  5115.6 1047.48  5333.3 1049.43
  5434.5 1054.74  5465.0 1057.61  5477.2 1059.58  5487.0 1060.02  5492.8 1061.41
  5500.0 1061.18  5514.2 1063.47  5529.8 1064.36  5534.7 1065.77  5539.0 1065.77
#Mann=8,-1,0
  4314.9   0.035       0  4326.0    0.07       0  4609.8   0.035       0
  4708.5    0.07       0  4990.3    0.05       0  4994.3    0.07       0
  5004.8   0.035       0  5115.6    0.07       0
Bank Sta=4990.3,4994.3
Exp/Cntr=0.3,0.1

Chan Stop Cuts=-1