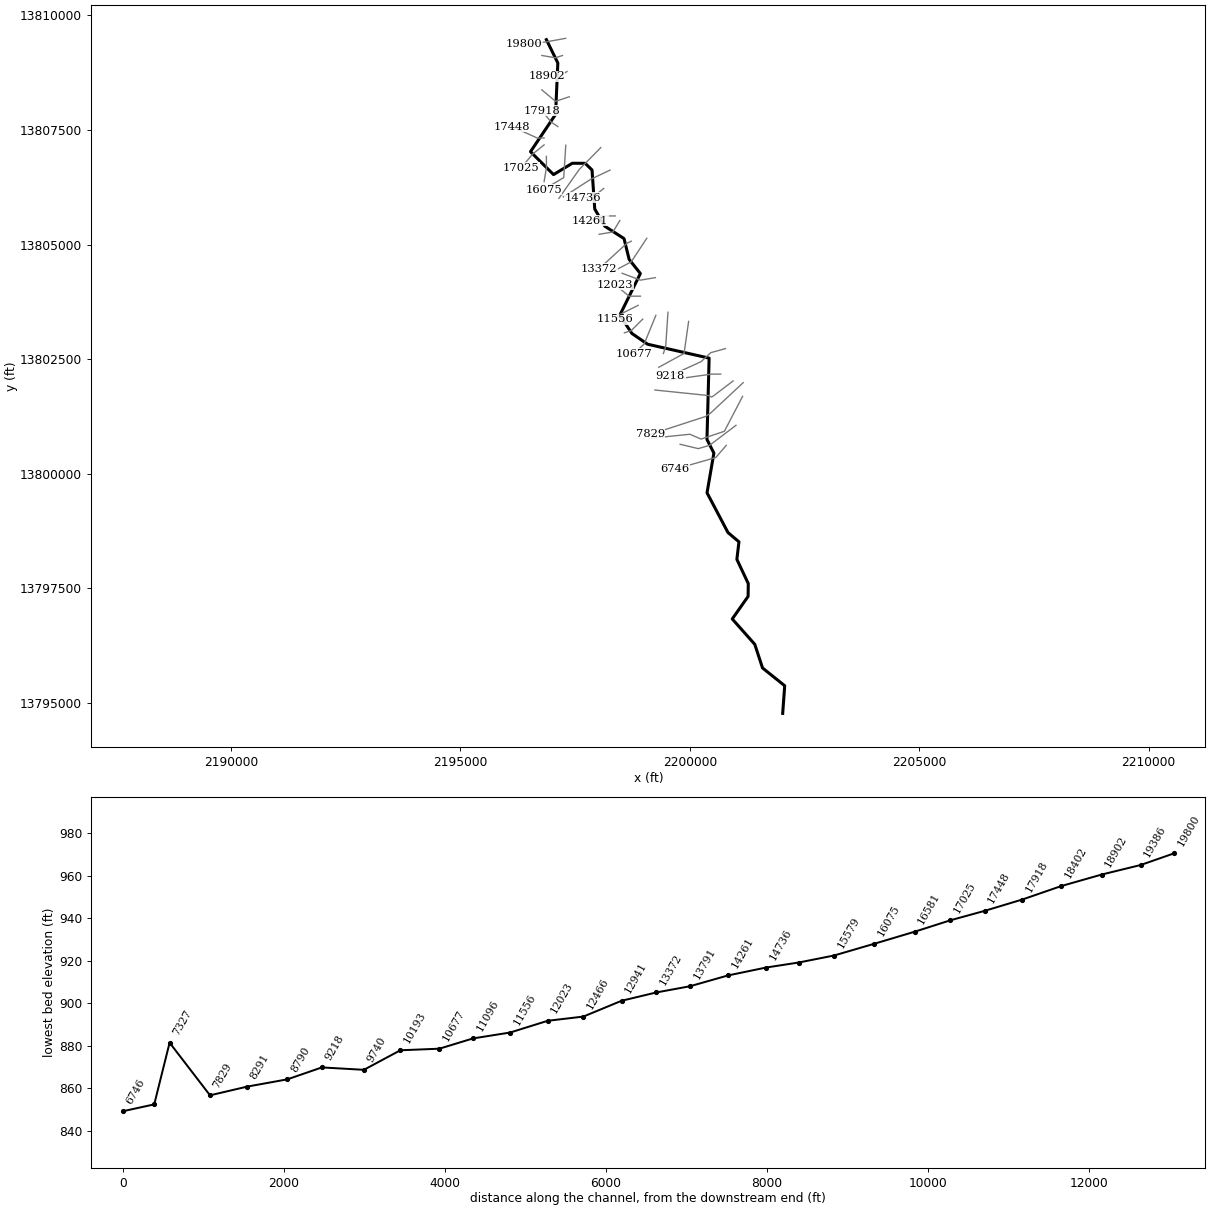
--- West Fork Tributary.prj (project) ---

Proj Title=West Fork Tributary Base Level Engineering
Current Plan=p01
Default Exp/Contr=0.3,0.1
English Units
Geom File=g01
Flow File=f01
Plan File=p01
BEGIN DESCRIPTION:
West Fork Tributary
END DESCRIPTION:

--- West Fork Tributary.p01 (plan) ---

Plan Title=Multiple Run
Short Identifier=Multiple
Geom File=g01
Flow File=f01
Subcritical Flow
K Sum by GR= 0
Std Step Tol= 0.01
Critical Tol= 0.01
Num of Std Step Trials= 20
Max Error Tol= 0.3
Flow Tol Ratio= 0.001
Split Flow NTrial= 30
Split Flow Tol= 0.02
Split Flow Ratio= 0.02
Log Output Level= 0
Friction Slope Method= 1
Unsteady Friction Slope Method= 2
Unsteady Bridges Friction Slope Method= 1
Parabolic Critical Depth
Global Vel Dist=  1 , 1 , 1
Global Log Level= 0
CheckData=True
Encroach Param= -1, 0, 0, 0
BEGIN DESCRIPTION:
Multiple Run
END DESCRIPTION:

--- West Fork Tributary.f01 (steady flow) ---

Flow Title=Multiple
Number of Profiles=7
Profile Names=10-year,25-year,50-year,1pct_min,100-year,1pct_plu,500-year
River Rch & RM= West Fork Tribut,Reach-1,19800
     731    1201    1635    1079    2153    4295    3689
River Rch & RM= West Fork Tribut,Reach-1,13791
    1013    1696    2337    1558    3109    6204    5448
River Rch & RM= West Fork Tribut,Reach-1,9218
    1251    2114    2930    1964    3918    7818    6938
River Rch & RM= West Fork Tribut,Reach-1,6440
    1727    2964    4151    2807    5600   11174   10101
Boundary for River Rch & Prof#=West Fork Tribut,Reach-1,1
Up Type=0
Dn Type=3
Dn Slope=0.005
Boundary for River Rch & Prof#=West Fork Tribut,Reach-1,2
Up Type=0
Dn Type=3
Dn Slope=0.005
Boundary for River Rch & Prof#=West Fork Tribut,Reach-1,3
Up Type=0
Dn Type=3
Dn Slope=0.005
Boundary for River Rch & Prof#=West Fork Tribut,Reach-1,4
Up Type=0
Dn Type=3
Dn Slope=0.005
Boundary for River Rch & Prof#=West Fork Tribut,Reach-1,5
Up Type=0
Dn Type=3
Dn Slope=0.005
Boundary for River Rch & Prof#=West Fork Tribut,Reach-1,6
Up Type=0
Dn Type=3
Dn Slope=0.005
Boundary for River Rch & Prof#=West Fork Tribut,Reach-1,7
Up Type=0
Dn Type=3
Dn Slope=0.005

--- West Fork Tributary.g01 (geometry) ---

Geom Title=Existing Conditions

River Reach=West Fork Tribut,Reach-1
Reach XY= 30
      2196875.00     13809469.98      2197124.33     13808961.09
      2197074.33     13807838.91      2196528.47     13807026.50
      2197030.48     13806527.07      2197440.16     13806774.61
      2197719.56     13806772.83      2197869.60     13806627.43
      2197928.61     13805776.50      2198147.85     13805401.16
      2198566.87     13805131.07      2198678.76     13804676.56
      2198922.84     13804369.55      2198475.16     13803460.56
      2198738.63     13803061.79      2199080.93     13802827.24
      2200421.56     13802523.78      2200374.70     13800749.88
      2200525.40     13800452.13      2200376.05     13799585.44
      2200832.86     13798718.83      2201072.17     13798516.79
      2201026.25     13798134.70      2201274.79     13797606.73
      2201271.46     13797326.46      2200925.86     13796834.86
      2201416.86     13796281.06      2201585.76     13795765.32
      2202069.27     13795377.55      2202025.00     13794775.00

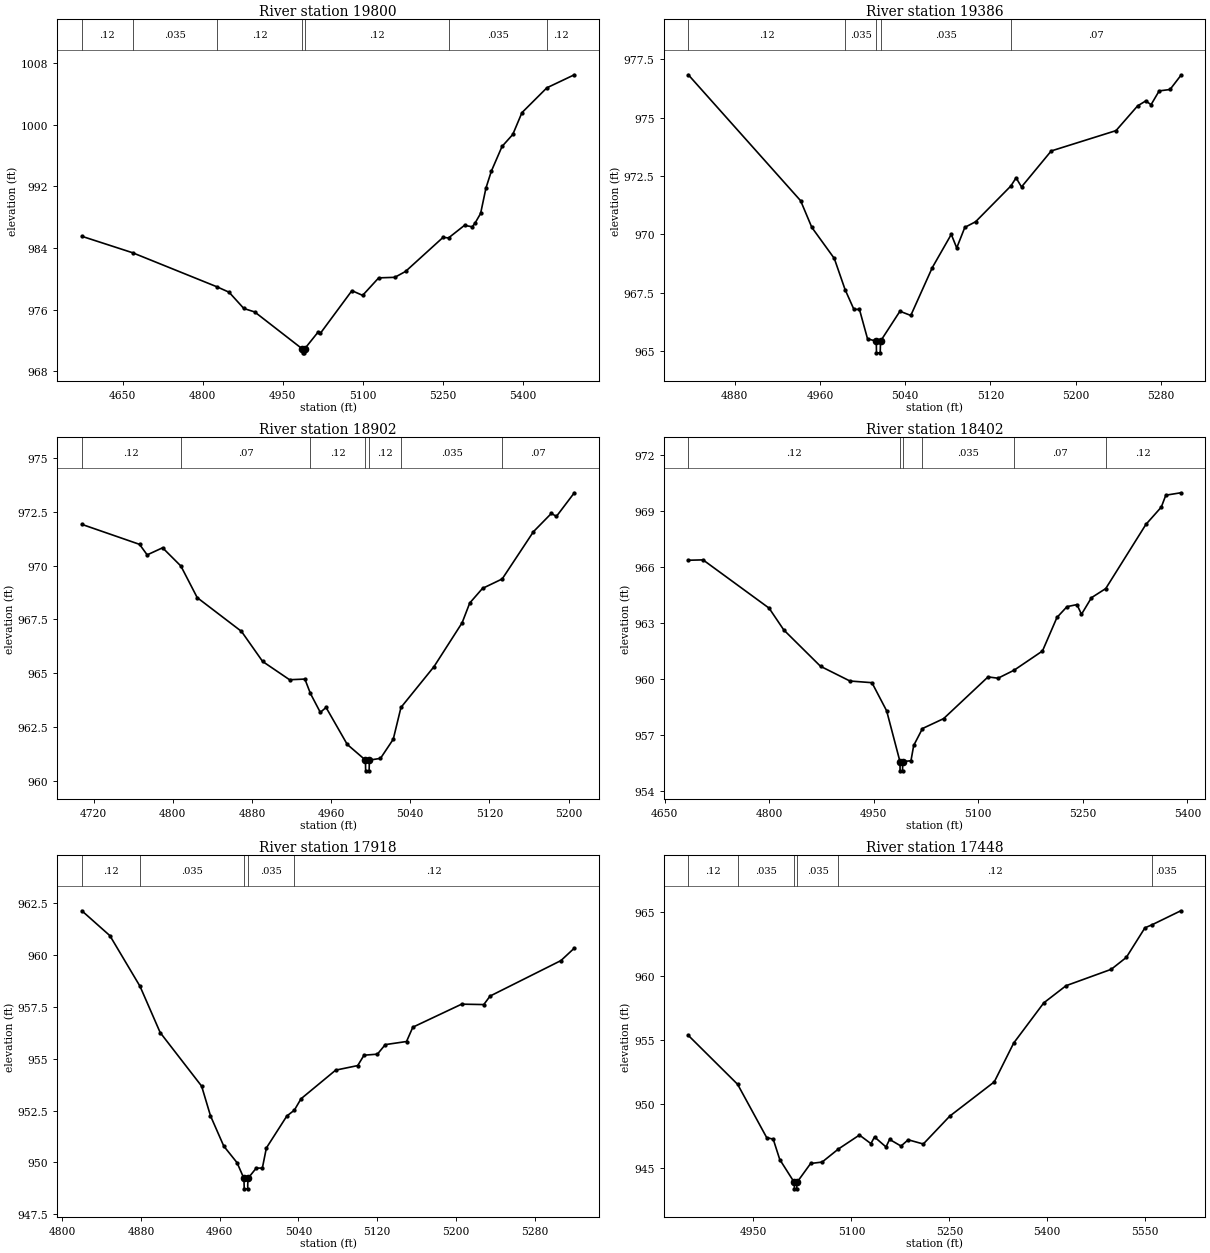
Type RM Length L Ch R = 1,19800,414,414,414
BEGIN DESCRIPTION:
H21696
END DESCRIPTION:
XS GIS Cut Line= 3
      2197293.79     13809499.16      2196864.18     13809420.74
      2196380.25     13809369.97
#Sta/Elev= 30
  4573.6  985.51  4668.6  983.38  4826.6  978.97  4849.6  978.26  4877.3  976.15
  4897.7  975.70  4987.1  970.90  4987.4  970.40  4990.9  970.40  4991.1  970.90
  5015.9  973.04  5021.0  972.95  5079.9  978.46  5100.0  977.85  5130.1  980.12
  5160.3  980.19  5180.4  980.95  5250.8  985.37  5261.1  985.30  5291.0  986.93
  5305.5  986.74  5311.1  987.26  5321.2  988.47  5331.2  991.76  5341.3  993.95
  5361.4  997.16  5381.5  998.71  5398.7 1001.54  5445.4 1004.76  5496.9 1006.45
#Mann=7,-1,0
  4573.6    0.12       0  4668.6   0.035       0  4826.6    0.12       0
  4987.1    0.05       0  4991.1    0.12       0  5261.1   0.035       0
  5445.4    0.12       0
Bank Sta=4987.1,4991.1
Exp/Cntr=0.3,0.1

Type RM Length L Ch R = 1,19386,484,484,484
BEGIN DESCRIPTION:
West Fork Tributary 41.0
END DESCRIPTION:
XS GIS Cut Line= 3
      2197224.97     13809124.99      2197075.00     13809075.00
      2196775.02     13809125.00
#Sta/Elev= 30
  4836.4  976.83  4941.8  971.44  4952.3  970.30  4973.4  968.97  4983.5  967.64
  4991.8  966.79  4997.0  966.79  5004.6  965.53  5012.8  965.43  5013.0  964.93
  5016.5  964.93  5016.8  965.43  5035.0  966.71  5045.2  966.53  5065.4  968.58
  5083.2  970.00  5088.3  969.42  5095.9  970.30  5106.0  970.54  5139.1  972.07
  5144.0  972.42  5149.1  972.03  5177.0  973.57  5237.8  974.44  5258.1  975.50
  5265.7  975.71  5270.7  975.55  5278.3  976.14  5288.5  976.20  5298.6  976.80
#Mann=5,-1,0
  4836.4    0.12       0  4983.5   0.035       0  5012.8   0.035       0
  5016.8   0.035       0  5139.1    0.07       0
Bank Sta=5012.8,5016.8
Exp/Cntr=0.3,0.1

Type RM Length L Ch R = 1,18902,500,500,500
BEGIN DESCRIPTION:
West Fork Tributary 40.0
END DESCRIPTION:
XS GIS Cut Line= 3
      2197324.96     13808774.98      2197075.00     13808625.00
      2196874.96     13808675.01
#Sta/Elev= 30
  4708.1  971.92  4766.4  970.99  4774.1  970.50  4789.7  970.83  4808.2  969.98
  4824.7  968.51  4869.4  966.94  4890.8  965.54  4918.0  964.69  4933.5  964.72
  4939.1  964.05  4949.1  963.17  4954.9  963.40  4976.3  961.68  4994.7  960.95
  4994.9  960.45  4998.4  960.45  4998.7  960.95  5009.9  961.03  5022.8  961.92
  5030.6  963.40  5064.0  965.30  5092.4  967.34  5100.1  968.26  5113.0  968.94
  5132.9  969.38  5164.5  971.58  5182.6  972.43  5187.7  972.29  5205.8  973.39
#Mann=7,-1,0
  4708.1    0.12       0  4808.2    0.07       0  4939.1    0.12       0
  4994.7    0.05       0  4998.7    0.12       0  5030.6   0.035       0
  5132.9    0.07       0
Bank Sta=4994.7,4998.7
Exp/Cntr=0.3,0.1

Type RM Length L Ch R = 1,18402,484,484,484
BEGIN DESCRIPTION:
West Fork Tributary 39.0
END DESCRIPTION:
XS GIS Cut Line= 3
      2197374.98     13808224.99      2197075.00     13808125.00
      2196775.02     13808374.99
#Sta/Elev= 30
  4683.8  966.36  4704.9  966.38  4799.7  963.79  4820.8  962.62  4873.5  960.67
  4915.7  959.88  4947.3  959.79  4968.4  958.28  4987.5  955.56  4987.7  955.06
  4991.2  955.06  4991.5  955.56  5003.3  955.60  5007.2  956.42  5019.8  957.33
  5050.1  957.86  5113.9  960.10  5128.2  960.03  5151.3  960.46  5192.0  961.49
  5212.8  963.29  5227.2  963.87  5241.5  963.98  5248.0  963.46  5262.3  964.35
  5282.8  964.84  5340.4  968.28  5362.5  969.21  5369.0  969.85  5390.5  969.98
#Mann=6,-1,0
  4683.8    0.12       0  4987.5    0.05       0  4991.5    0.12       0
  5019.8   0.035       0  5151.3    0.07       0  5282.8    0.12       0
Bank Sta=4987.5,4991.5
Exp/Cntr=0.3,0.1

Type RM Length L Ch R = 1,17918,470,470,470
BEGIN DESCRIPTION:
West Fork Tributary 38.0
END DESCRIPTION:
XS GIS Cut Line= 3
      2197124.98     13807575.02      2196975.00     13807675.00
      2196775.00     13807925.00
#Sta/Elev= 30
  4820.0  962.13  4848.5  960.93  4879.1  958.49  4899.6  956.26  4941.7  953.68
  4950.7  952.25  4964.2  950.79  4977.7  949.99  4984.7  949.23  4985.0  948.73
  4988.5  948.73  4988.7  949.23  4997.2  949.73  5003.4  949.73  5007.5  950.70
  5028.3  952.24  5035.9  952.52  5042.7  953.07  5077.9  954.45  5100.3  954.67
  5106.7  955.17  5120.3  955.22  5128.3  955.68  5149.9  955.83  5156.3  956.52
  5205.9  957.63  5228.4  957.61  5234.8  958.02  5306.8  959.73  5320.4  960.33
#Mann=5,-1,0
  4820.0    0.12       0  4879.1   0.035       0  4984.7   0.035       0
  4988.7   0.035       0  5035.9    0.12       0
Bank Sta=4984.7,4988.7
Exp/Cntr=0.3,0.1

Type RM Length L Ch R = 1,17448,423,423,423
BEGIN DESCRIPTION:
West Fork Tributary 37.0
END DESCRIPTION:
XS GIS Cut Line= 3
      2196824.99     13807325.00      2196675.00     13807325.00
      2196125.04     13807574.98
#Sta/Elev= 30
  4850.3  955.35  4925.8  951.53  4970.3  947.37  4980.3  947.25  4990.3  945.66
  5012.6  943.87  5012.8  943.37  5016.3  943.37  5016.6  943.87  5037.6  945.35
  5055.2  945.46  5080.1  946.48  5112.3  947.57  5129.9  946.90  5135.4  947.42
  5153.0  946.64  5158.5  947.23  5176.0  946.71  5187.0  947.20  5210.1  946.87
  5250.7  949.05  5318.8  951.72  5348.5  954.75  5394.6  957.89  5428.7  959.23
  5497.9  960.51  5521.0  961.44  5549.5  963.75  5560.5  963.99  5604.4  965.08
#Mann=6,-1,0
  4850.3    0.12       0  4925.8   0.035       0  5012.6   0.035       0
  5016.6   0.035       0  5080.1    0.12       0  5560.5   0.035       0
Bank Sta=5012.6,5016.6
Exp/Cntr=0.3,0.1

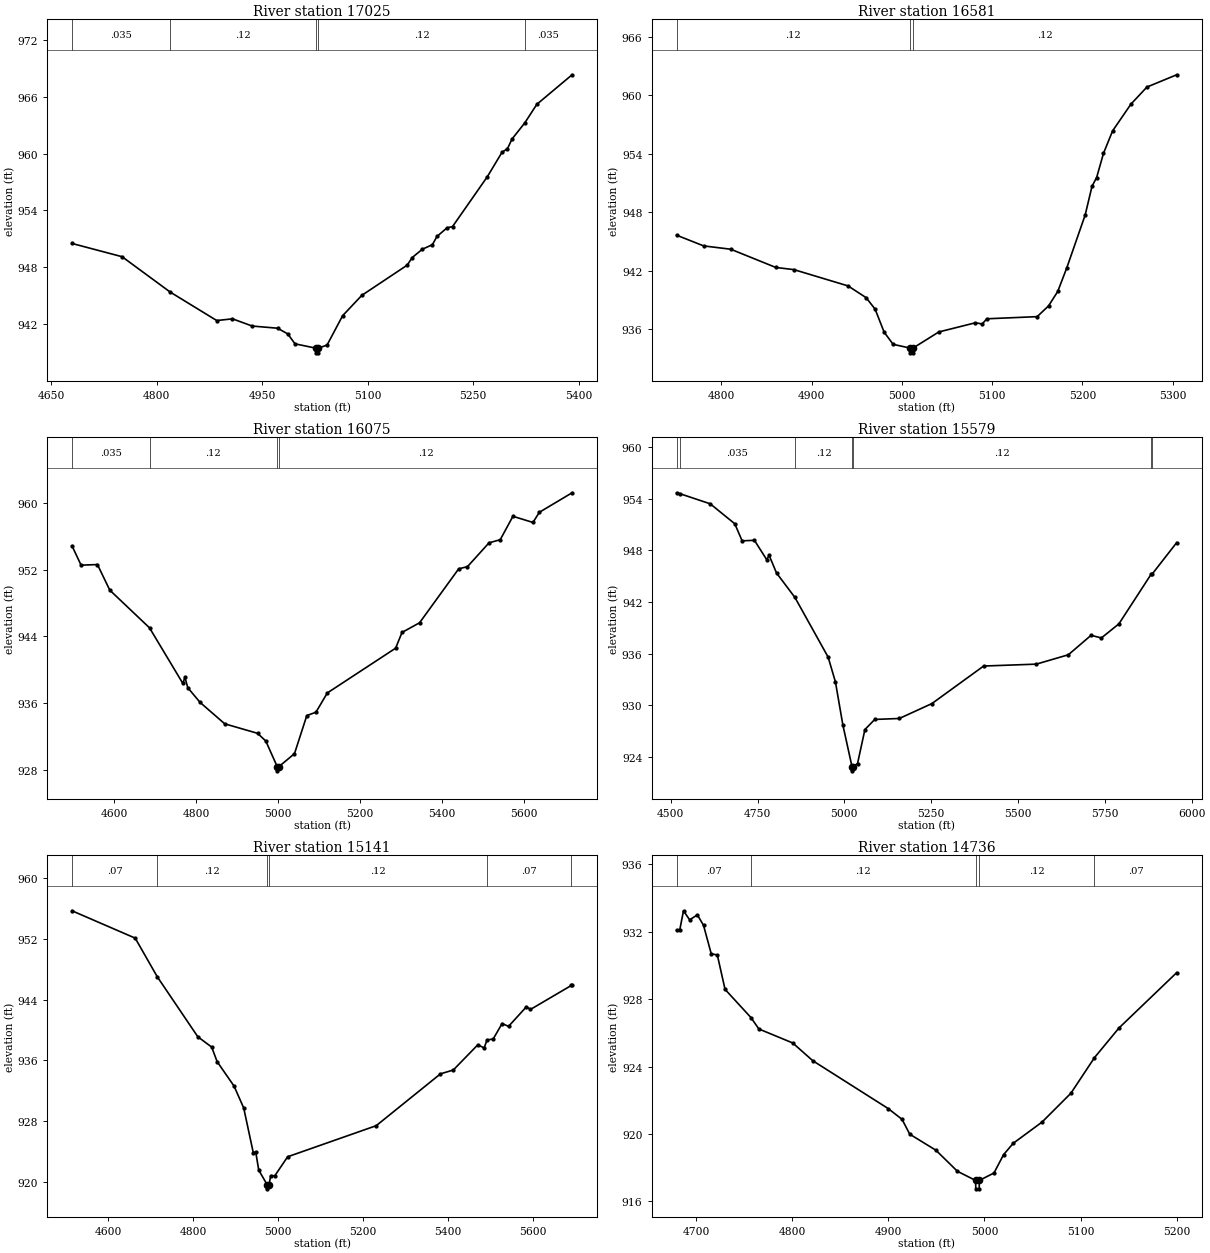
Type RM Length L Ch R = 1,17025,444,444,444
BEGIN DESCRIPTION:
West Fork Tributary 36.0
END DESCRIPTION:
XS GIS Cut Line= 3
      2196825.01     13807175.01      2196575.00     13806975.00
      2196324.99     13806674.98
#Sta/Elev= 30
  4679.8  950.52  4751.0  949.12  4819.3  945.39  4885.5  942.38  4907.9  942.56
  4935.9  941.80  4972.0  941.57  4986.4  940.97  4996.8  939.92  5026.0  939.47
  5026.2  938.97  5029.7  938.97  5030.0  939.47  5042.3  939.79  5064.4  942.89
  5091.7  945.04  5156.2  948.23  5163.3  949.03  5177.7  949.91  5192.0  950.39
  5198.5  951.26  5212.8  952.17  5220.6  952.30  5270.1  957.57  5290.9  960.14
  5298.7  960.53  5305.2  961.55  5323.4  963.26  5340.4  965.21  5390.5  968.33
#Mann=5,-1,0
  4679.8   0.035       0  4819.3    0.12       0  5026.0    0.05       0
  5030.0    0.12       0  5323.4   0.035       0
Bank Sta=5026,5030
Exp/Cntr=0.3,0.1

Type RM Length L Ch R = 1,16581,506,506,506
BEGIN DESCRIPTION:
West Fork Tributary 35.0
END DESCRIPTION:
XS GIS Cut Line= 3
      2196875.00     13806925.02      2196875.00     13806675.00
      2196824.99     13806374.96
#Sta/Elev= 30
  4750.3  945.65  4780.3  944.55  4810.3  944.21  4860.3  942.34  4880.3  942.12
  4940.3  940.45  4960.3  939.25  4970.3  938.07  4980.3  935.71  4990.3  934.46
  5008.5  934.09  5008.7  933.59  5012.2  933.59  5012.5  934.09  5040.9  935.73
  5081.4  936.67  5089.0  936.55  5094.1  937.08  5149.9  937.30  5162.5  938.40
  5172.7  939.88  5182.8  942.32  5203.1  947.72  5210.7  950.67  5215.8  951.56
  5223.4  954.04  5233.5  956.34  5253.8  959.08  5271.5  960.83  5304.5  962.09
#Mann=3,-1,0
  4750.3    0.12       0  5008.5    0.05       0  5012.5    0.12       0
Bank Sta=5008.5,5012.5
Exp/Cntr=0.3,0.1

Type RM Length L Ch R = 1,16075,496,496,496
BEGIN DESCRIPTION:
H21695
END DESCRIPTION:
XS GIS Cut Line= 3
      2197297.16     13807167.12      2197252.84     13806461.43
      2196810.75     13806199.58
#Sta/Elev= 30
  4496.3  954.87  4518.5  952.55  4558.5  952.62  4588.6  949.55  4685.6  945.03
  4767.0  938.36  4772.0  939.11  4779.0  937.85  4809.0  936.09  4869.2  933.52
  4949.3  932.38  4969.4  931.46  4997.4  928.38  4997.7  927.88  5001.4  928.38
  5039.5  929.94  5069.6  934.51  5091.9  934.91  5119.6  937.22  5286.4  942.59
  5302.0  944.48  5344.9  945.64  5440.4  952.11  5461.8  952.37  5514.5  955.23
  5541.8  955.60  5572.8  958.41  5621.7  957.67  5637.3  958.89  5717.2  961.23
#Mann=4,-1,0
  4496.3   0.035       0  4685.6    0.12       0  4997.4    0.05       0
  5001.4    0.12       0
Bank Sta=4997.4,5001.4
Exp/Cntr=0.3,0.1

Type RM Length L Ch R = 1,15579,438,438,438
BEGIN DESCRIPTION:
H21694
END DESCRIPTION:
XS GIS Cut Line= 3
      2198060.87     13807116.04      2197590.37     13806638.72
      2197147.85     13806008.98
#Sta/Elev= 30
  4517.0  954.69  4526.2  954.59  4613.8  953.41  4684.6  951.09  4705.7  949.11
  4741.1  949.17  4776.4  946.93  4783.6  947.41  4804.7  945.38  4857.8  942.53
  4953.3  935.61  4974.4  932.72  4995.7  927.74  5022.0  922.90  5022.2  922.40
  5026.0  922.90  5038.0  923.25  5059.3  927.20  5087.6  928.37  5158.3  928.48
  5252.1  930.21  5401.1  934.57  5552.7  934.79  5645.1  935.88  5710.4  938.14
  5740.1  937.83  5790.6  939.47  5884.0  945.27  5886.1  945.24  5956.9  948.90
#Mann=7,-1,0
  4517.0    0.12       0  4526.2   0.035       0  4857.8    0.12       0
  5022.0    0.05       0  5026.0    0.12       0  5884.0    0.07       0
  5886.1    0.12       0
Bank Sta=5022,5026
Exp/Cntr=0.3,0.1

Type RM Length L Ch R = 1,15141,405,405,405
BEGIN DESCRIPTION:
H21693
END DESCRIPTION:
XS GIS Cut Line= 3
      2198261.99     13806625.08      2197839.25     13806423.93
      2197243.68     13806039.36
#Sta/Elev= 30
  4514.5  955.70  4663.3  952.10  4715.2  947.02  4810.7  939.12  4843.4  937.76
  4856.1  935.85  4896.0  932.63  4918.7  929.75  4941.4  923.82  4946.9  923.99
  4954.1  921.57  4974.3  919.61  4974.5  919.11  4978.3  919.61  4982.2  920.85
  4991.8  920.82  5022.1  923.33  5230.6  927.42  5381.8  934.24  5412.1  934.75
  5469.5  938.05  5484.7  937.66  5491.5  938.71  5505.8  938.82  5526.9  940.86
  5542.1  940.49  5584.3  943.08  5593.5  942.71  5689.7  945.87  5691.6  945.92
#Mann=6,-1,0
  4514.5    0.07       0  4715.2    0.12       0  4974.3    0.05       0
  4978.3    0.12       0  5491.5    0.07       0  5689.7    0.12       0
Bank Sta=4974.3,4978.3
Exp/Cntr=0.3,0.1

Type RM Length L Ch R = 1,14736,475,475,475
BEGIN DESCRIPTION:
West Fork Tributary 31.0
END DESCRIPTION:
XS GIS Cut Line= 3
      2198124.97     13806224.97      2197875.00     13806025.00
      2197675.02     13806025.00
#Sta/Elev= 30
  4679.8  932.08  4683.0  932.08  4687.0  933.24  4693.4  932.70  4701.4  933.00
  4707.8  932.38  4715.8  930.70  4722.2  930.61  4730.2  928.58  4757.1  926.91
  4765.4  926.23  4800.6  925.40  4821.4  924.35  4899.9  921.51  4914.3  920.87
  4922.3  919.99  4949.5  919.04  4971.9  917.79  4990.7  917.25  4991.0  916.75
  4994.5  916.75  4994.7  917.25  5009.9  917.69  5019.9  918.78  5029.9  919.45
  5059.9  920.71  5089.9  922.42  5114.4  924.53  5139.9  926.29  5199.9  929.57
#Mann=5,-1,0
  4679.8    0.07       0  4757.1    0.12       0  4990.7    0.05       0
  4994.7    0.12       0  5114.4    0.07       0
Bank Sta=4990.7,4994.7
Exp/Cntr=0.3,0.1

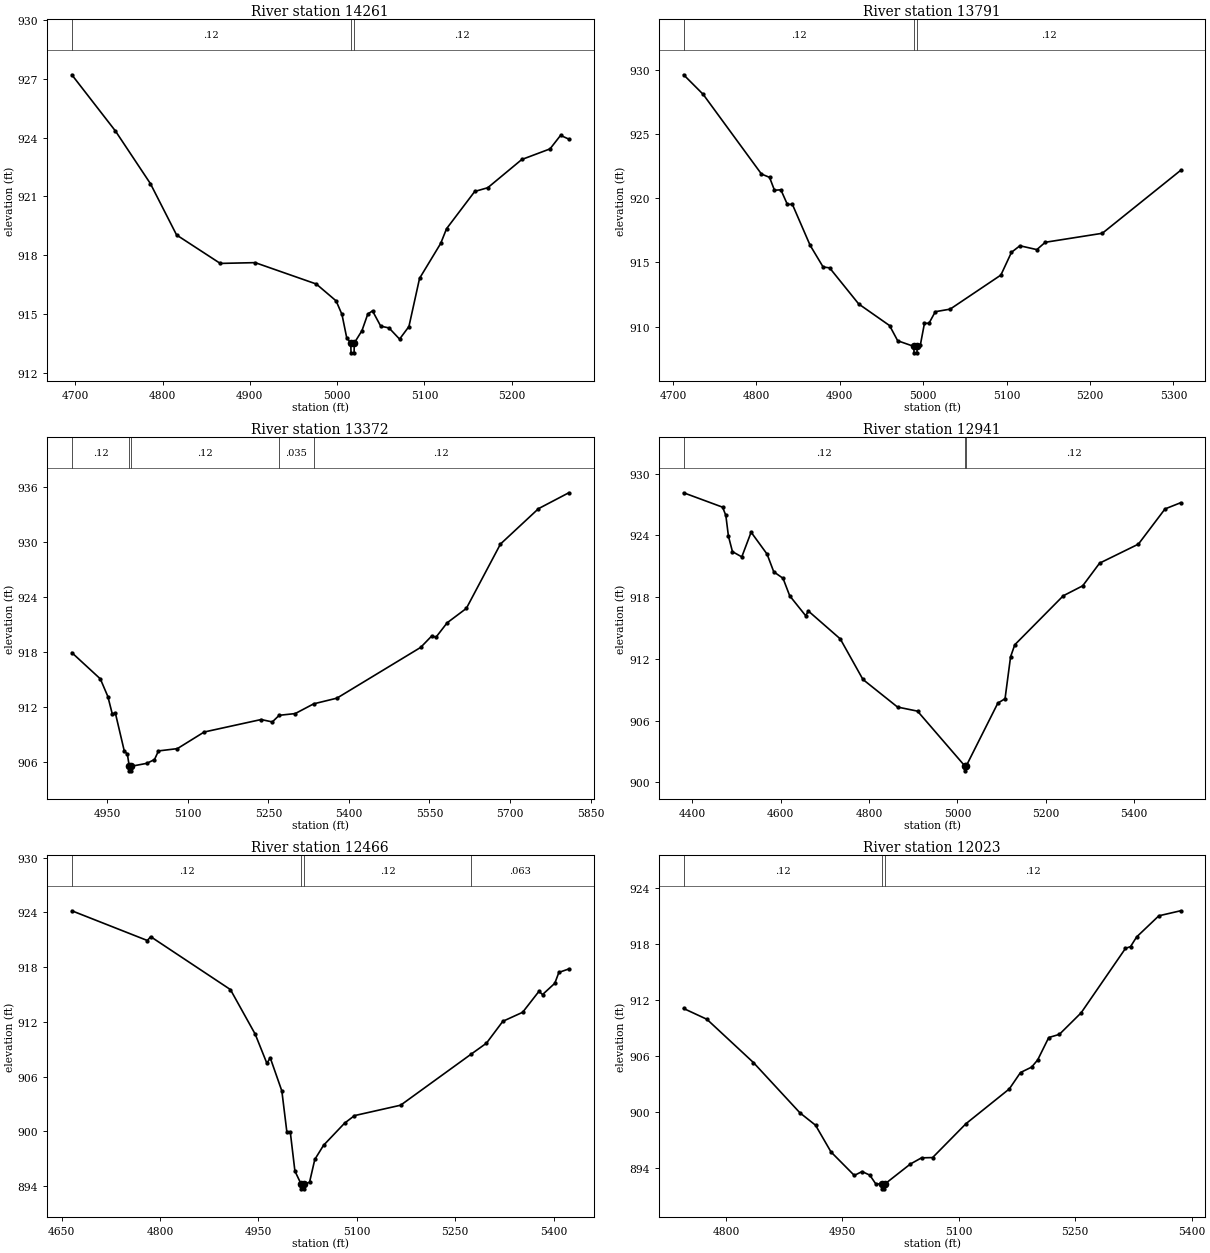
Type RM Length L Ch R = 1,14261,470,470,470
BEGIN DESCRIPTION:
West Fork Tributary 30.0
END DESCRIPTION:
XS GIS Cut Line= 3
      2198374.99     13805625.00      2198075.00     13805625.00
      2197825.04     13805525.02
#Sta/Elev= 30
  4696.1  927.20  4746.1  924.33  4786.1  921.65  4816.1  919.03  4866.1  917.58
  4906.1  917.62  4976.1  916.53  4998.8  915.67  5005.5  914.98  5010.9  913.80
  5015.6  913.52  5015.9  913.02  5019.4  913.02  5019.6  913.52  5028.4  914.15
  5035.1  915.00  5040.5  915.16  5049.9  914.38  5059.4  914.29  5071.5  913.72
  5082.2  914.36  5094.4  916.82  5118.6  918.60  5125.3  919.35  5157.6  921.25
  5172.5  921.44  5211.5  922.88  5243.8  923.42  5255.9  924.11  5265.3  923.92
#Mann=3,-1,0
  4696.1    0.12       0  5015.6    0.05       0  5019.6    0.12       0
Bank Sta=5015.6,5019.6
Exp/Cntr=0.3,0.1

Type RM Length L Ch R = 1,13791,419,419,419
BEGIN DESCRIPTION:
West Fork Tributary 29.0
END DESCRIPTION:
XS GIS Cut Line= 3
      2198475.01     13805525.02      2198325.00     13805275.00
      2198025.01     13805225.00
#Sta/Elev= 30
  4712.8  929.59  4736.2  928.07  4806.1  921.87  4815.8  921.61  4821.7  920.61
  4829.4  920.64  4837.2  919.50  4843.1  919.52  4864.4  916.33  4880.0  914.64
  4887.8  914.57  4922.7  911.76  4959.7  910.08  4969.4  908.90  4988.8  908.46
  4989.0  907.96  4992.5  907.96  4992.8  908.46  4996.6  908.58  5001.5  910.26
  5006.9  910.26  5014.5  911.16  5032.3  911.36  5093.1  914.01  5105.8  915.78
  5115.9  916.29  5136.2  915.99  5146.3  916.56  5214.7  917.26  5308.5  922.15
#Mann=3,-1,0
  4712.8    0.12       0  4988.8    0.05       0  4992.8    0.12       0
Bank Sta=4988.8,4992.8
Exp/Cntr=0.3,0.1

Type RM Length L Ch R = 1,13372,431,431,431
BEGIN DESCRIPTION:
West Fork Tributary 28.0
END DESCRIPTION:
XS GIS Cut Line= 3
      2198724.98     13805074.99      2198625.00     13805025.00
      2198025.02     13804475.02
#Sta/Elev= 30
  4883.8  917.91  4936.9  915.05  4950.9  913.13  4959.2  911.22  4964.8  911.35
  4981.6  907.17  4987.2  906.87  4990.8  905.53  4991.0  905.03  4994.5  905.03
  4994.8  905.53  5023.6  905.85  5037.8  906.26  5045.2  907.20  5080.4  907.45
  5130.3  909.26  5236.4  910.62  5257.3  910.36  5270.0  911.08  5299.9  911.27
  5334.3  912.33  5377.6  912.95  5533.6  918.48  5554.6  919.75  5562.0  919.58
  5582.9  921.16  5618.7  922.73  5682.2  929.74  5753.1  933.60  5809.5  935.33
#Mann=5,-1,0
  4883.8    0.12       0  4990.8    0.05       0  4994.8    0.12       0
  5270.0   0.035       0  5334.3    0.12       0
Bank Sta=4990.8,4994.8
Exp/Cntr=0.3,0.1

Type RM Length L Ch R = 1,12941,475,475,475
BEGIN DESCRIPTION:
West Fork Tributary 27.0
END DESCRIPTION:
XS GIS Cut Line= 3
      2199063.21     13805138.63      2198725.00     13804625.00
      2198275.68     13804385.17
#Sta/Elev= 30
  4380.4  928.15  4468.6  926.75  4475.9  925.95  4481.8  923.93  4490.9  922.43
  4512.0  921.92  4533.1  924.32  4569.2  922.19  4584.3  920.47  4605.3  919.84
  4620.4  918.14  4656.6  916.20  4662.6  916.66  4734.8  913.95  4786.1  910.01
  4864.3  907.33  4909.6  906.93  5016.1  901.63  5016.3  901.13  5020.1  901.63
  5091.3  907.71  5107.6  908.14  5120.1  912.21  5129.6  913.38  5239.3  918.14
  5283.3  919.11  5321.5  921.31  5409.3  923.16  5469.5  926.58  5504.7  927.18
#Mann=3,-1,0
  4380.4    0.12       0  5016.1    0.05       0  5020.1    0.12       0
Bank Sta=5016.1,5020.1
Exp/Cntr=0.3,0.1

Type RM Length L Ch R = 1,12466,443,443,443
BEGIN DESCRIPTION:
West Fork Tributary 26.0
END DESCRIPTION:
XS GIS Cut Line= 3
      2199250.71     13804279.46      2198925.00     13804225.00
      2198525.03     13804374.99
#Sta/Elev= 30
  4665.7  924.18  4780.8  920.92  4785.9  921.34  4907.4  915.54  4945.2  910.65
  4963.0  907.45  4968.1  908.06  4985.8  904.42  4993.4  899.95  4998.6  899.95
  5005.7  895.64  5015.3  894.19  5015.5  893.69  5019.0  893.69  5019.3  894.19
  5028.0  894.41  5036.0  896.91  5049.3  898.46  5081.4  900.89  5096.5  901.72
  5166.8  902.86  5274.5  908.47  5297.6  909.66  5322.6  912.06  5352.8  913.05
  5377.7  915.35  5383.1  914.99  5401.8  916.23  5408.0  917.42  5423.1  917.80
#Mann=4,-1,0
  4665.7    0.12       0  5015.3    0.05       0  5019.3    0.12       0
  5274.5   0.063       0
Bank Sta=5015.3,5019.3
Exp/Cntr=0.3,0.1

Type RM Length L Ch R = 1,12023,467,467,467
BEGIN DESCRIPTION:
West Fork Tributary 25.0
END DESCRIPTION:
XS GIS Cut Line= 3
      2198924.97     13803875.00      2198675.00     13803875.00
      2198374.99     13804125.01
#Sta/Elev= 30
  4745.4  911.09  4775.4  909.93  4835.4  905.28  4895.4  899.87  4915.4  898.55
  4935.4  895.67  4965.4  893.15  4975.4  893.57  4985.4  893.18  4992.9  892.26
  5000.5  892.21  5000.8  891.71  5004.3  891.71  5004.5  892.21  5037.7  894.38
  5052.0  895.04  5066.3  895.07  5109.3  898.71  5165.2  902.45  5179.6  904.21
  5193.9  904.79  5201.7  905.56  5216.0  907.97  5229.7  908.31  5257.7  910.62
  5314.9  917.55  5321.4  917.74  5329.3  918.78  5357.9  921.05  5385.9  921.59
#Mann=3,-1,0
  4745.4    0.12       0  5000.5    0.05       0  5004.5    0.12       0
Bank Sta=5000.5,5004.5
Exp/Cntr=0.3,0.1

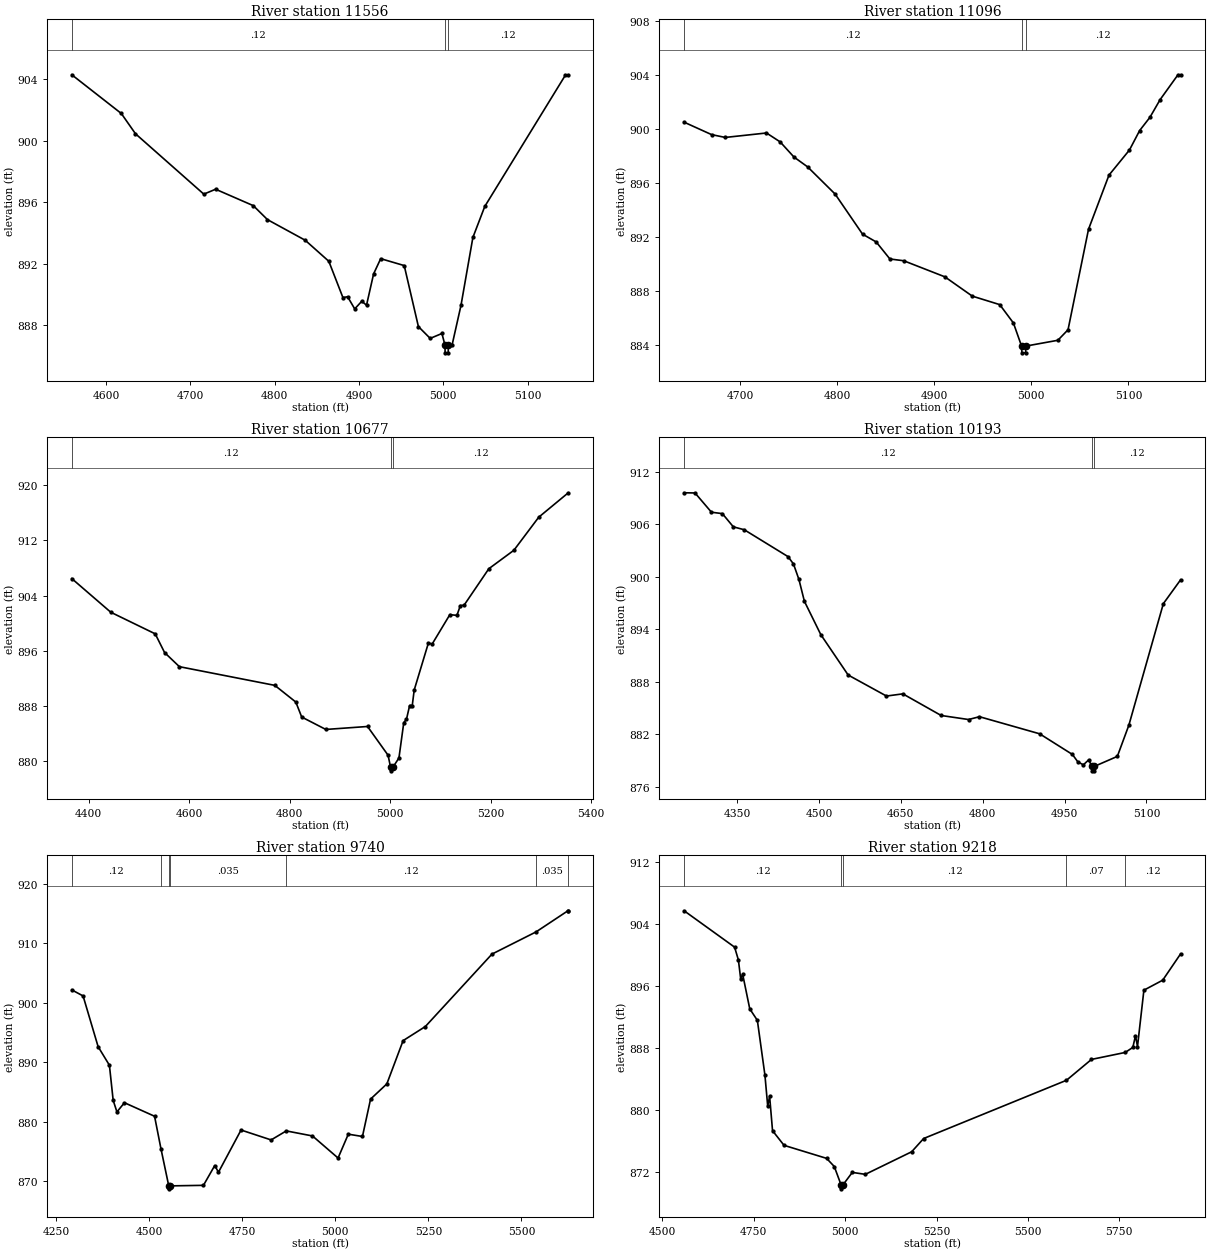
Type RM Length L Ch R = 1,11556,460,460,460
BEGIN DESCRIPTION:
West Fork Tributary 24.0
END DESCRIPTION:
XS GIS Cut Line= 3
      2198875.01     13803675.00      2198475.00     13803475.00
      2198375.03     13803375.03
#Sta/Elev= 30
  4559.5  904.29  4618.2  901.77  4635.0  900.45  4716.0  896.52  4730.0  896.84
  4774.7  895.77  4791.5  894.86  4836.2  893.52  4864.2  892.15  4880.9  889.79
  4886.5  889.84  4894.9  889.05  4903.3  889.55  4908.9  889.29  4917.3  891.33
  4925.7  892.32  4953.6  891.87  4970.4  887.90  4984.4  887.13  4998.3  887.45
  5001.9  886.69  5002.1  886.19  5005.7  886.19  5006.0  886.69  5010.3  886.69
  5020.9  889.28  5035.0  893.70  5049.1  895.72  5144.6  904.26  5148.1  904.26
#Mann=3,-1,0
  4559.5    0.12       0  5001.9    0.05       0  5006.0    0.12       0
Bank Sta=5001.9,5006
Exp/Cntr=0.3,0.1

Type RM Length L Ch R = 1,11096,419,419,419
BEGIN DESCRIPTION:
West Fork Tributary 23.0
END DESCRIPTION:
XS GIS Cut Line= 3
      2198975.01     13803375.01      2198725.00     13803125.00
      2198574.98     13803074.99
#Sta/Elev= 30
  4642.1  900.51  4670.4  899.59  4684.5  899.38  4727.0  899.71  4741.1  899.05
  4755.3  897.93  4769.4  897.20  4797.7  895.19  4826.0  892.22  4840.1  891.64
  4854.2  890.38  4868.4  890.25  4910.8  889.06  4939.1  887.63  4967.4  887.00
  4981.5  885.64  4989.9  883.93  4990.2  883.43  4994.0  883.43  4994.3  883.93
  5027.3  884.36  5037.8  885.14  5058.9  892.58  5080.0  896.59  5101.1  898.45
  5111.6  899.89  5122.2  900.87  5132.7  902.18  5151.1  904.02  5153.8  904.02
#Mann=3,-1,0
  4642.1    0.12       0  4989.9    0.05       0  4994.3    0.12       0
Bank Sta=4989.9,4994.3
Exp/Cntr=0.3,0.1

Type RM Length L Ch R = 1,10677,484,484,484
BEGIN DESCRIPTION:
West Fork Tributary 22.0
END DESCRIPTION:
XS GIS Cut Line= 3
      2199260.95     13803457.83      2199005.24     13802830.49
      2198777.31     13802619.57
#Sta/Elev= 30
  4366.6  906.46  4444.2  901.58  4532.6  898.45  4551.2  895.74  4580.7  893.69
  4770.6  890.98  4812.4  888.56  4824.1  886.39  4872.1  884.59  4955.1  885.02
  4996.0  880.85  5001.0  879.09  5001.3  878.59  5005.4  879.09  5017.6  880.45
  5027.2  885.57  5032.6  886.07  5038.9  888.06  5044.1  888.06  5048.0  890.31
  5076.3  897.14  5083.7  896.97  5118.9  901.23  5133.0  901.13  5139.8  902.55
  5147.2  902.60  5196.5  907.89  5246.4  910.57  5295.8  915.36  5354.6  918.90
#Mann=3,-1,0
  4366.6    0.12       0  5001.0    0.05       0  5005.4    0.12       0
Bank Sta=5001,5005.4
Exp/Cntr=0.3,0.1

Type RM Length L Ch R = 1,10193,453,453,453
BEGIN DESCRIPTION:
West Fork Tributary 21.0
END DESCRIPTION:
XS GIS Cut Line= 3
      2199525.00     13803524.95      2199475.00     13802775.00
      2199425.01     13802625.03
#Sta/Elev= 30
  4252.9  909.60  4272.9  909.58  4303.0  907.38  4323.0  907.22  4343.1  905.71
  4363.1  905.38  4443.3  902.31  4453.3  901.47  4463.3  899.70  4473.3  897.21
  4503.4  893.40  4553.5  888.79  4623.7  886.39  4653.7  886.64  4723.9  884.17
  4774.0  883.71  4794.1  884.03  4904.3  882.08  4964.4  879.72  4974.5  878.86
  4984.5  878.54  4994.5  879.12  4999.8  878.35  5000.1  877.85  5003.9  877.85
  5004.3  878.35  5046.7  879.50  5067.8  883.06  5131.0  896.94  5162.6  899.66
#Mann=3,-1,0
  4252.9    0.12       0  4999.8    0.05       0  5004.3    0.12       0
Bank Sta=4999.8,5004.3
Exp/Cntr=0.3,0.1

Type RM Length L Ch R = 1,9740,522,522,522
BEGIN DESCRIPTION:
West Fork Tributary 20.0
END DESCRIPTION:
XS GIS Cut Line= 3
      2199975.00     13803325.03      2199875.00     13802625.00
      2199325.03     13802325.01
#Sta/Elev= 30
  4292.1  902.18  4322.4  901.16  4362.8  892.61  4393.1  889.49  4403.2  883.58
  4413.3  881.62  4433.5  883.17  4514.4  880.89  4531.5  875.44  4552.5  869.16
  4552.8  868.66  4557.0  869.16  4645.7  869.25  4676.0  872.58  4686.1  871.46
  4746.7  878.57  4827.5  876.90  4868.2  878.42  4938.6  877.57  5007.3  873.85
  5034.8  877.87  5072.8  877.48  5094.6  883.78  5138.3  886.34  5182.0  893.63
  5241.8  896.01  5420.7  908.21  5539.1  911.95  5624.7  915.51  5625.7  915.51
#Mann=7,-1,0
  4292.1    0.12       0  4531.5   0.035       0  4552.5    0.05       0
  4557.0   0.035       0  4868.2    0.12       0  5539.1   0.035       0
  5624.7   0.063       0
Bank Sta=4552.5,4557
Exp/Cntr=0.3,0.1

Type RM Length L Ch R = 1,9218,428,428,428
BEGIN DESCRIPTION:
H21692
END DESCRIPTION:
XS GIS Cut Line= 4
      2200778.12     13802731.63      2200457.62     13802642.98
      2200249.65     13802448.65      2199576.32     13802139.19
#Sta/Elev= 30
  4559.3  905.65  4697.4  900.96  4707.8  899.31  4714.2  896.82  4719.4  897.48
  4738.9  893.00  4759.7  891.52  4780.4  884.45  4788.0  880.46  4793.2  881.73
  4801.2  877.29  4832.7  875.40  4949.1  873.72  4970.1  872.67  4988.8  870.29
  4989.1  869.79  4993.7  870.29  5019.4  871.91  5055.1  871.66  5181.8  874.57
  5214.6  876.28  5605.3  883.79  5673.7  886.48  5766.0  887.38  5786.9  888.03
  5794.1  889.54  5799.6  888.14  5817.1  895.41  5868.6  896.70  5917.5  900.09
#Mann=5,-1,0
  4559.3    0.12       0  4988.8    0.05       0  4993.7    0.12       0
  5605.3    0.07       0  5766.0    0.12       0
Bank Sta=4988.8,4993.7
Exp/Cntr=0.3,0.1

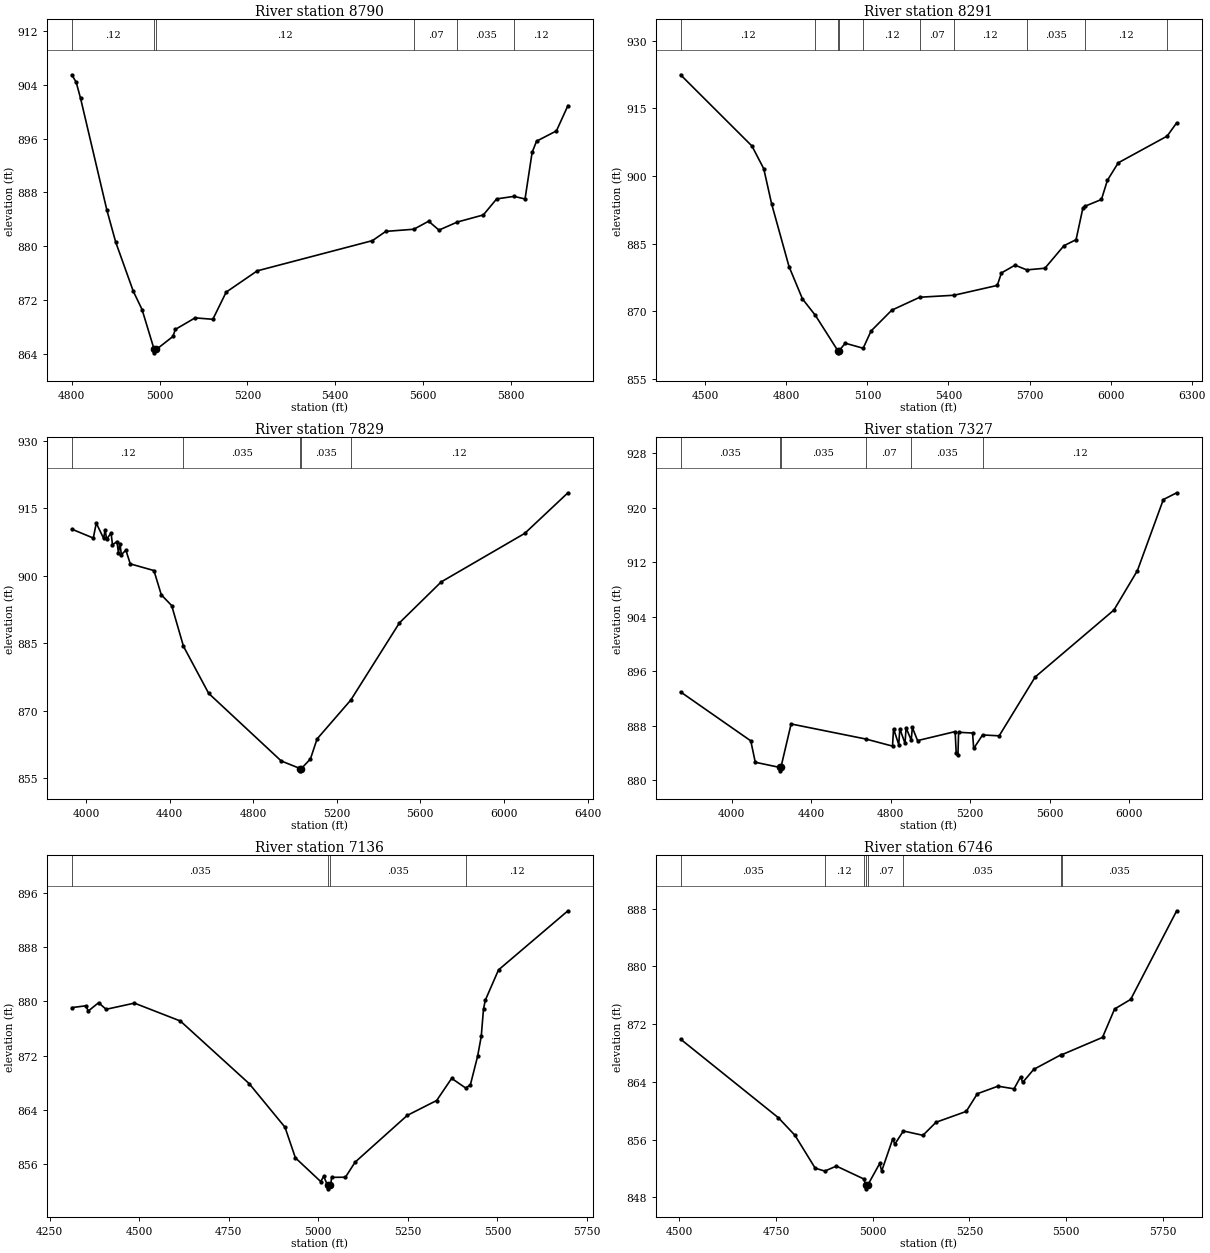
Type RM Length L Ch R = 1,8790,499,499,499
BEGIN DESCRIPTION:
West Fork Tributary 19.0
END DESCRIPTION:
XS GIS Cut Line= 3
      2200675.03     13802175.00      2200475.00     13802175.00
      2199554.17     13802046.35
#Sta/Elev= 30
  4800.0  905.47  4810.0  904.37  4820.0  901.97  4880.0  885.35  4900.0  880.63
  4940.0  873.34  4960.0  870.62  4987.6  864.69  4987.9  864.19  4992.5  864.69
  5030.3  866.62  5035.8  867.67  5080.8  869.38  5121.2  869.17  5151.5  873.20
  5222.2  876.36  5484.7  880.85  5515.0  882.22  5578.9  882.54  5612.6  883.73
  5636.1  882.41  5677.9  883.61  5737.1  884.66  5767.4  887.04  5807.0  887.42
  5832.1  887.03  5848.2  893.94  5858.3  895.61  5903.6  897.14  5929.8  900.90
#Mann=6,-1,0
  4800.0    0.12       0  4987.6    0.05       0  4992.5    0.12       0
  5578.9    0.07       0  5677.9   0.035       0  5807.0    0.12       0
Bank Sta=4987.6,4992.5
Exp/Cntr=0.3,0.1

Type RM Length L Ch R = 1,8291,462,462,462
BEGIN DESCRIPTION:
West Fork Tributary 18.0
END DESCRIPTION:
XS GIS Cut Line= 5
      2200944.95     13802026.76      2200517.48     13801700.49
      2200475.00     13801675.00      2200410.39     13801707.31
      2199239.86     13801828.32
#Sta/Elev= 30
  4408.4  922.42  4672.8  906.62  4716.4  901.59  4745.4  893.83  4809.9  879.90
  4859.7  872.72  4907.7  869.06  4990.3  861.27  4990.7  860.77  4995.3  861.27
  5018.1  862.90  5084.3  861.79  5113.6  865.62  5190.2  870.23  5293.9  873.10
  5420.8  873.54  5580.7  875.72  5596.1  878.49  5646.4  880.21  5689.9  879.16
  5757.0  879.53  5827.3  884.52  5872.3  885.86  5897.7  892.93  5903.9  893.24
  5966.2  894.77  5988.2  899.02  6028.4  902.90  6209.2  908.82  6244.7  911.77
#Mann=10,-1,0
  4408.4    0.12       0  4907.7   0.035       0  4990.3   0.035       0
  4995.3   0.035       0  5084.3    0.12       0  5293.9    0.07       0
  5420.8    0.12       0  5689.9   0.035       0  5903.9    0.12       0
  6209.2   0.035       0
Bank Sta=4990.3,4995.3
Exp/Cntr=0.3,0.1

Type RM Length L Ch R = 1,7829,502,502,502
BEGIN DESCRIPTION:
West Fork Tributary 17.0
END DESCRIPTION:
XS GIS Cut Line= 5
      2201165.50     13801990.04      2200449.52     13801321.58
      2200375.00     13801275.00      2200339.02     13801249.30
      2199138.41     13800858.62
#Sta/Elev= 30
  3932.1  910.36  4035.1  908.38  4049.2  911.70  4084.4  908.32  4091.7  910.23
  4098.6  908.16  4120.1  909.47  4126.9  906.88  4148.4  907.61  4155.2  905.14
  4162.6  907.15  4169.4  904.69  4190.9  905.69  4211.9  902.65  4325.2  901.16
  4360.4  895.78  4410.2  893.37  4466.5  884.34  4587.1  873.88  4934.1  858.87
  5025.1  857.17  5025.5  856.67  5030.5  857.17  5074.0  859.31  5105.9  863.76
  5267.4  872.41  5500.1  889.55  5699.9  898.64  6099.6  909.42  6306.3  918.44
#Mann=5,-1,0
  3932.1    0.12       0  4466.5   0.035       0  5025.1   0.035       0
  5030.5   0.035       0  5267.4    0.12       0
Bank Sta=5025.1,5030.5
Exp/Cntr=0.3,0.1

Type RM Length L Ch R = 1,7327,191,191,191
BEGIN DESCRIPTION:
West Fork Tributary 16.0
END DESCRIPTION:
XS GIS Cut Line= 5
      2201150.78     13801688.67      2200754.23     13800928.08
      2200246.24     13800757.62      2200002.21     13800863.22
      2199168.09     13800777.45
#Sta/Elev= 30
  3742.0  893.00  4095.7  885.81  4118.3  882.67  4241.9  881.91  4242.3  881.41
  4247.3  881.91  4298.7  888.29  4675.0  886.08  4809.2  885.04  4814.5  887.59
  4840.7  885.26  4846.0  887.58  4872.3  885.45  4877.5  887.73  4903.5  885.91
  4909.1  887.78  4935.3  885.85  5124.6  887.17  5129.9  884.00  5138.6  883.76
  5142.0  887.07  5212.4  886.96  5217.9  884.69  5262.6  886.68  5346.2  886.55
  5527.6  895.19  5924.1  905.02  6042.1  910.80  6172.7  921.23  6240.0  922.23
#Mann=6,-1,0
  3742.0   0.035       0  4241.9   0.035       0  4247.3   0.035       0
  4675.0    0.07       0  4903.5   0.035       0  5262.6    0.12       0
Bank Sta=4241.9,4247.3
Exp/Cntr=0.3,0.1

Type RM Length L Ch R = 1,7136,390,390,390
BEGIN DESCRIPTION:
H21691
END DESCRIPTION:
XS GIS Cut Line= 4
      2201006.54     13801057.65      2200430.34     13800621.24
      2200184.87     13800549.65      2199789.73     13800645.03
#Sta/Elev= 30
  4311.8  879.08  4351.3  879.35  4357.6  878.57  4386.7  879.80  4407.6  878.83
  4486.6  879.74  4614.8  877.11  4807.0  867.89  4906.9  861.48  4936.0  856.97
  5006.7  853.48  5015.0  854.25  5025.9  852.91  5026.3  852.41  5031.3  852.91
  5034.6  852.91  5037.0  854.10  5075.7  854.12  5102.7  856.34  5248.3  863.22
  5330.3  865.41  5372.2  868.67  5411.2  867.25  5424.4  867.71  5444.5  871.89
  5454.8  874.85  5461.1  878.89  5466.2  880.18  5503.0  884.63  5696.8  893.33
#Mann=4,-1,0
  4311.8   0.035       0  5025.9   0.035       0  5031.3   0.035       0
  5411.2    0.12       0
Bank Sta=5025.9,5031.3
Exp/Cntr=0.3,0.1

Type RM Length L Ch R = 1,6746,306,306,306
BEGIN DESCRIPTION:
West Fork Tributary 15.0
END DESCRIPTION:
XS GIS Cut Line= 3
      2200795.13     13800621.23      2200566.72     13800355.32
      2199670.69     13800099.80
#Sta/Elev= 30
  4503.2  869.92  4756.0  859.04  4798.8  856.61  4851.2  852.05  4876.0  851.65
  4906.0  852.34  4977.5  850.54  4981.3  849.69  4981.7  849.19  4986.8  849.69
  5017.9  852.70  5023.1  851.66  5051.7  856.11  5056.9  855.37  5079.1  857.20
  5129.7  856.60  5163.6  858.41  5241.6  859.91  5270.3  862.36  5323.5  863.40
  5365.1  863.04  5382.2  864.70  5387.4  863.92  5416.0  865.73  5485.3  867.72
  5488.3  867.75  5593.8  870.16  5625.0  874.09  5666.6  875.42  5785.5  887.69
#Mann=8,-1,0
  4503.2   0.035       0  4876.0    0.12       0  4977.5    0.07       0
  4981.3    0.05       0  4986.8    0.07       0  5079.1   0.035       0
  5485.3    0.12       0  5488.3   0.035       0
Bank Sta=4981.3,4986.8
Exp/Cntr=0.3,0.1