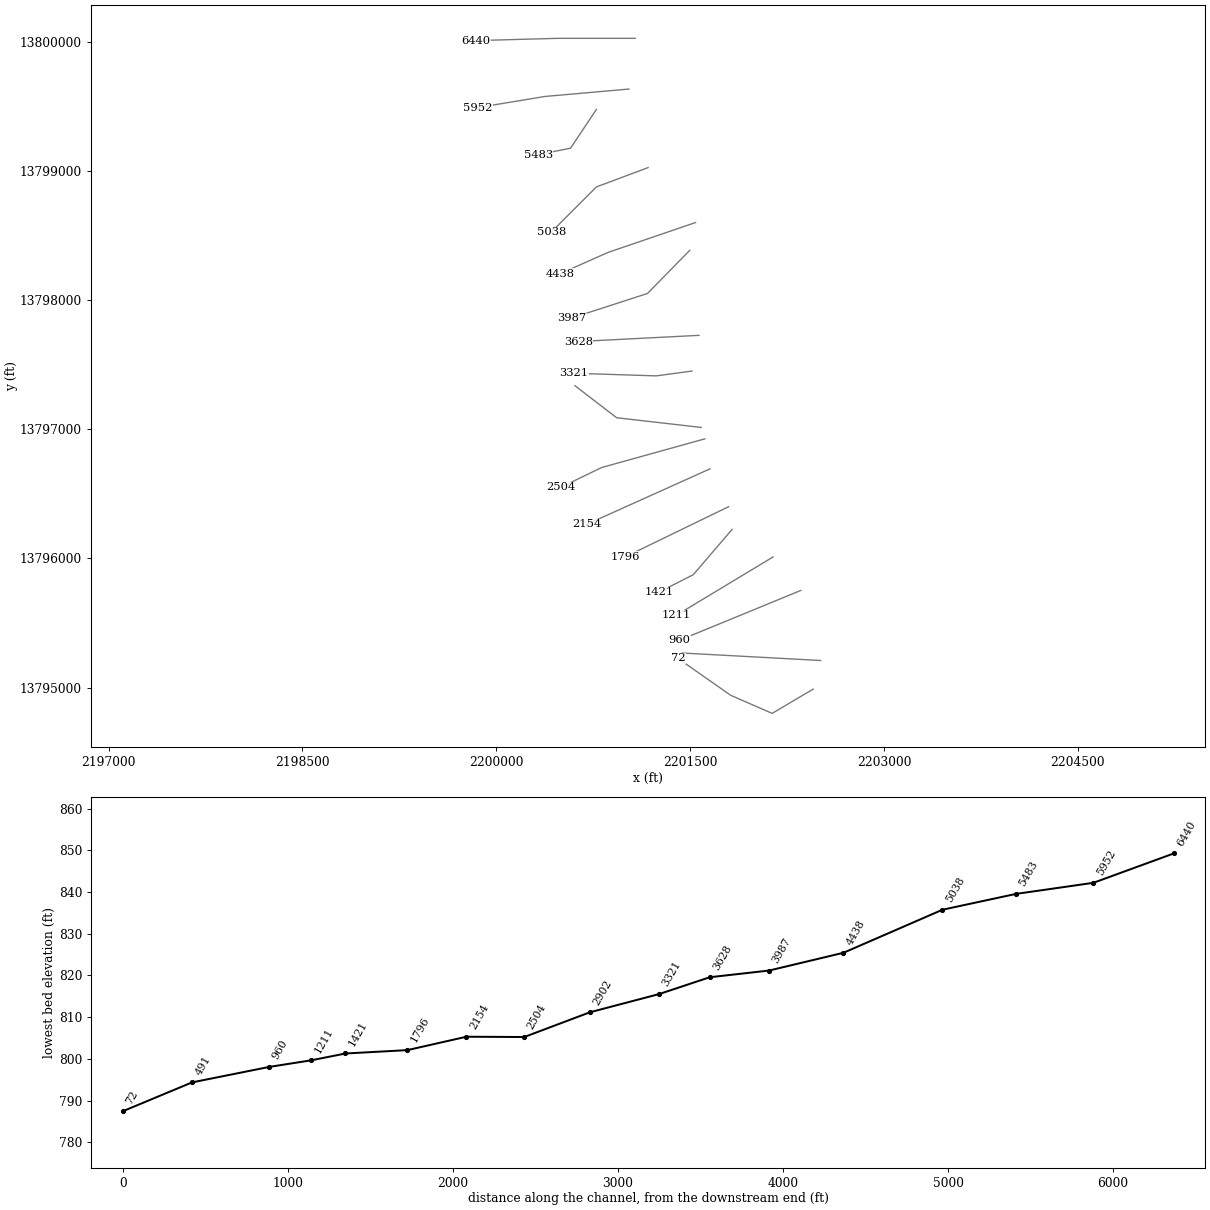
HEC-RAS study West Fork Tributary.prj: West Fork Tributary Base Level Engineering

--- West Fork Tributary.g01 (geometry) --- (continued)

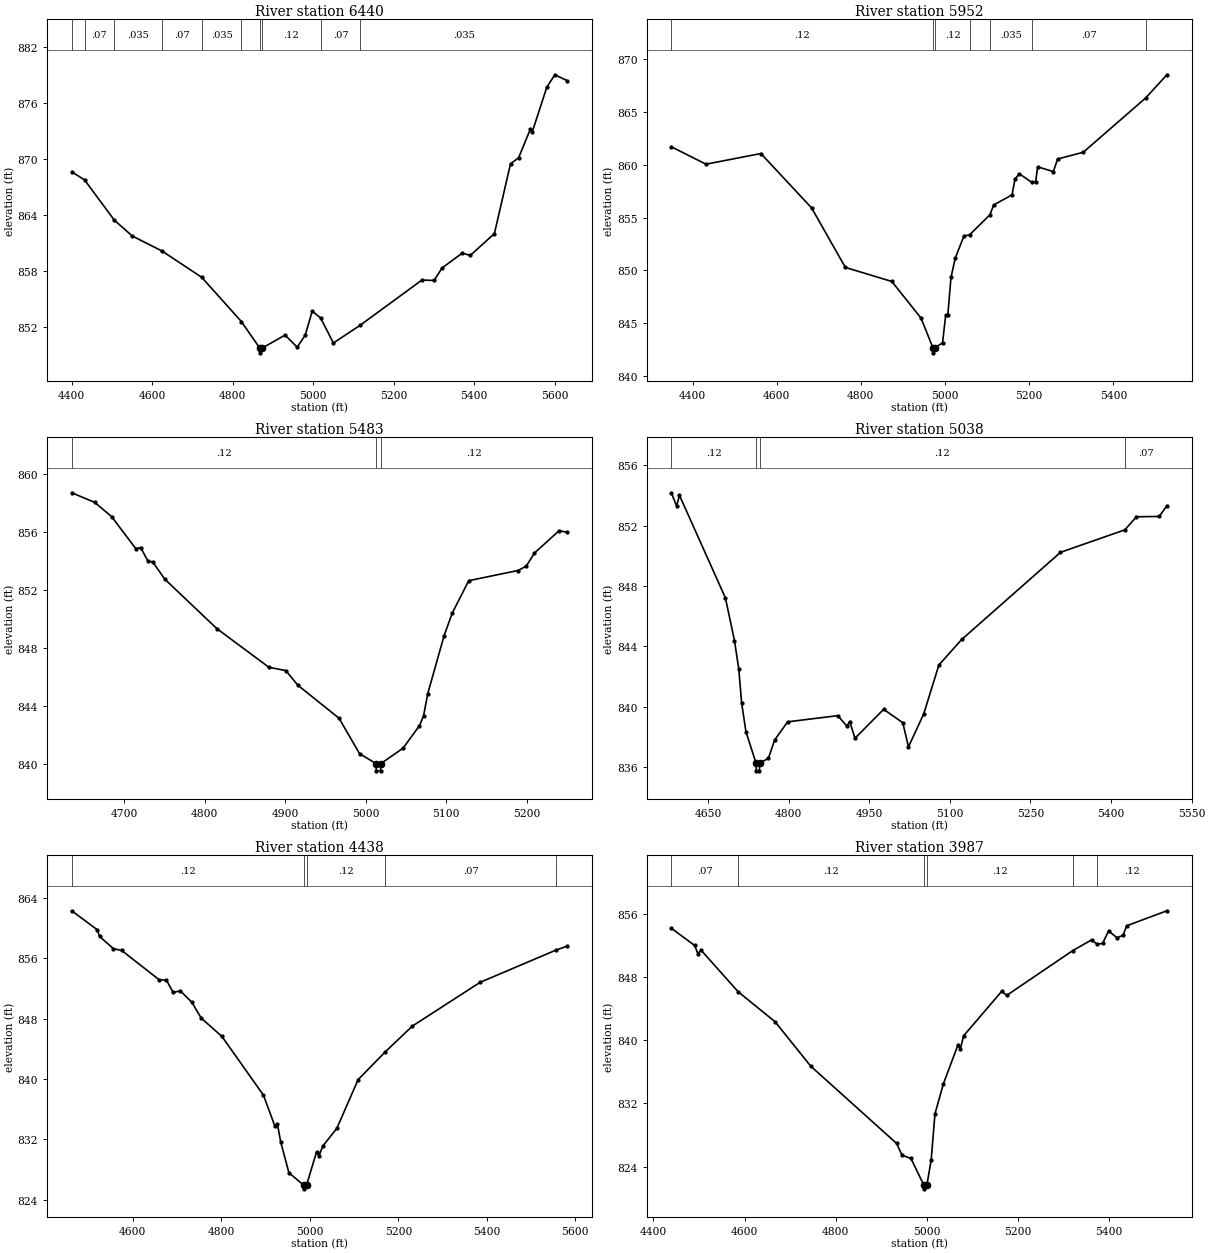
Type RM Length L Ch R = 1,6440,488,488,488
BEGIN DESCRIPTION:
West Fork Tributary 14.0
END DESCRIPTION:
XS GIS Cut Line= 3
      2201075.04     13800025.00      2200475.00     13800025.00
      2199843.98     13800007.57
#Sta/Elev= 30
  4400.0  868.62  4431.8  867.75  4505.7  863.45  4550.0  861.76  4624.4  860.14
  4722.9  857.33  4821.4  852.60  4867.3  849.75  4867.7  849.25  4872.8  849.75
  4930.0  851.15  4960.0  849.86  4980.0  851.12  4997.5  853.71  5018.4  852.98
  5050.1  850.30  5116.9  852.21  5270.1  857.04  5300.2  856.99  5320.2  858.33
  5370.2  859.92  5390.2  859.67  5450.2  862.01  5490.2  869.48  5510.2  870.11
  5539.2  873.15  5544.2  872.88  5580.3  877.66  5600.3  879.00  5631.3  878.37
#Mann=10,-1,0
  4400.0   0.035       0  4431.8    0.07       0  4505.7   0.035       0
  4624.4    0.07       0  4722.9   0.035       0  4821.4    0.12       0
  4867.3    0.05       0  4872.8    0.12       0  5018.4    0.07       0
  5116.9   0.035       0
Bank Sta=4867.3,4872.8
Exp/Cntr=0.3,0.1

Type RM Length L Ch R = 1,5952,469,469,469
BEGIN DESCRIPTION:
West Fork Tributary 13.0
END DESCRIPTION:
XS GIS Cut Line= 3
      2201026.97     13799632.54      2200375.00     13799575.00
      2199858.83     13799489.55
#Sta/Elev= 30
  4349.6  861.72  4431.9  860.07  4562.4  861.08  4682.9  855.93  4763.2  850.29
  4873.6  848.96  4943.0  845.49  4971.0  842.70  4971.5  842.20  4977.0  842.70
  4994.1  843.15  5001.6  845.76  5006.6  845.76  5014.2  849.35  5024.4  851.19
  5044.7  853.24  5059.2  853.41  5106.8  855.28  5115.6  856.21  5159.2  857.16
  5166.3  858.65  5176.4  859.17  5206.1  858.35  5215.2  858.39  5220.2  859.82
  5257.5  859.37  5267.6  860.56  5328.5  861.20  5476.5  866.33  5527.3  868.54
#Mann=7,-1,0
  4349.6    0.12       0  4971.0    0.05       0  4977.0    0.12       0
  5059.2    0.07       0  5106.8   0.035       0  5206.1    0.07       0
  5476.5   0.035       0
Bank Sta=4971,4977
Exp/Cntr=0.3,0.1

Type RM Length L Ch R = 1,5483,445,445,445
BEGIN DESCRIPTION:
West Fork Tributary 12.0
END DESCRIPTION:
XS GIS Cut Line= 3
      2200774.98     13799474.97      2200575.00     13799175.00
      2200324.97     13799124.99
#Sta/Elev= 30
  4634.8  858.68  4663.3  858.02  4684.3  857.04  4714.4  854.83  4720.4  854.91
  4729.4  853.98  4735.4  853.92  4750.4  852.73  4815.0  849.33  4879.6  846.67
  4900.7  846.44  4915.7  845.43  4966.8  843.16  4992.3  840.72  5012.7  840.04
  5013.2  839.54  5018.3  839.54  5018.8  840.04  5046.3  841.10  5066.7  842.65
  5071.8  843.33  5076.9  844.84  5097.3  848.85  5107.5  850.41  5127.9  852.63
  5189.1  853.33  5199.3  853.63  5209.5  854.53  5240.1  856.07  5250.3  855.96
#Mann=3,-1,0
  4634.8    0.12       0  5012.7    0.05       0  5018.8    0.12       0
Bank Sta=5012.7,5018.8
Exp/Cntr=0.3,0.1

Type RM Length L Ch R = 1,5038,600,600,600
BEGIN DESCRIPTION:
West Fork Tributary 11.0
END DESCRIPTION:
XS GIS Cut Line= 3
      2201174.98     13799024.99      2200775.00     13798875.00
      2200424.97     13798524.97
#Sta/Elev= 30
  4581.7  854.19  4591.5  853.31  4596.8  854.02  4682.3  847.22  4699.2  844.38
  4707.2  842.50  4712.5  840.25  4720.5  838.35  4739.4  836.25  4739.9  835.75
  4745.6  835.75  4746.1  836.25  4762.4  836.59  4773.9  837.79  4798.0  839.00
  4891.4  839.41  4908.3  838.72  4913.7  839.02  4923.4  837.91  4976.8  839.83
  5012.4  838.94  5023.0  837.34  5051.3  839.52  5079.6  842.77  5122.0  844.46
  5305.9  850.24  5425.5  851.73  5447.3  852.60  5489.7  852.62  5503.9  853.34
#Mann=4,-1,0
  4581.7    0.12       0  4739.4    0.05       0  4746.1    0.12       0
  5425.5    0.07       0
Bank Sta=4739.4,4746.1
Exp/Cntr=0.3,0.1

Type RM Length L Ch R = 1,4438,451,451,451
BEGIN DESCRIPTION:
H21690
END DESCRIPTION:
XS GIS Cut Line= 3
      2201541.79     13798599.51      2200863.33     13798367.67
      2200495.13     13798204.03
#Sta/Elev= 30
  4462.0  862.29  4519.5  859.78  4524.8  858.89  4556.1  857.27  4574.8  857.03
  4659.4  853.15  4676.1  853.08  4691.1  851.46  4707.4  851.68  4733.4  850.16
  4754.5  848.07  4801.4  845.63  4895.3  837.84  4921.3  833.70  4926.6  834.05
  4934.2  831.66  4952.7  827.57  4985.8  825.93  4986.3  825.43  4992.7  825.93
  5015.3  830.35  5020.6  829.80  5029.3  831.10  5061.0  833.44  5109.2  839.91
  5170.5  843.59  5231.9  847.01  5385.1  852.81  5556.8  857.09  5581.9  857.61
#Mann=5,-1,0
  4462.0    0.12       0  4985.8    0.05       0  4992.7    0.12       0
  5170.5    0.07       0  5556.8    0.12       0
Bank Sta=4985.8,4992.7
Exp/Cntr=0.3,0.1

Type RM Length L Ch R = 1,3987,359,359,359
BEGIN DESCRIPTION:
H21689
END DESCRIPTION:
XS GIS Cut Line= 3
      2201497.47     13798384.73      2201170.17     13798050.61
      2200580.80     13797859.83
#Sta/Elev= 30
  4439.2  854.23  4490.3  852.05  4497.3  851.02  4504.4  851.45  4585.9  846.17
  4667.0  842.36  4744.9  836.74  4933.4  826.93  4945.3  825.44  4964.9  825.02
  4992.9  821.67  4993.4  821.17  4999.9  821.67  5009.3  824.85  5017.5  830.67
  5036.0  834.49  5068.0  839.42  5073.3  838.91  5080.5  840.59  5164.0  846.23
  5175.1  845.72  5319.7  851.39  5361.3  852.76  5373.3  852.20  5385.3  852.31
  5398.5  853.89  5416.9  853.03  5430.5  853.35  5437.9  854.54  5526.4  856.45
#Mann=6,-1,0
  4439.2    0.07       0  4585.9    0.12       0  4992.9    0.05       0
  4999.9    0.12       0  5319.7    0.07       0  5373.3    0.12       0
Bank Sta=4992.9,4999.9
Exp/Cntr=0.3,0.1

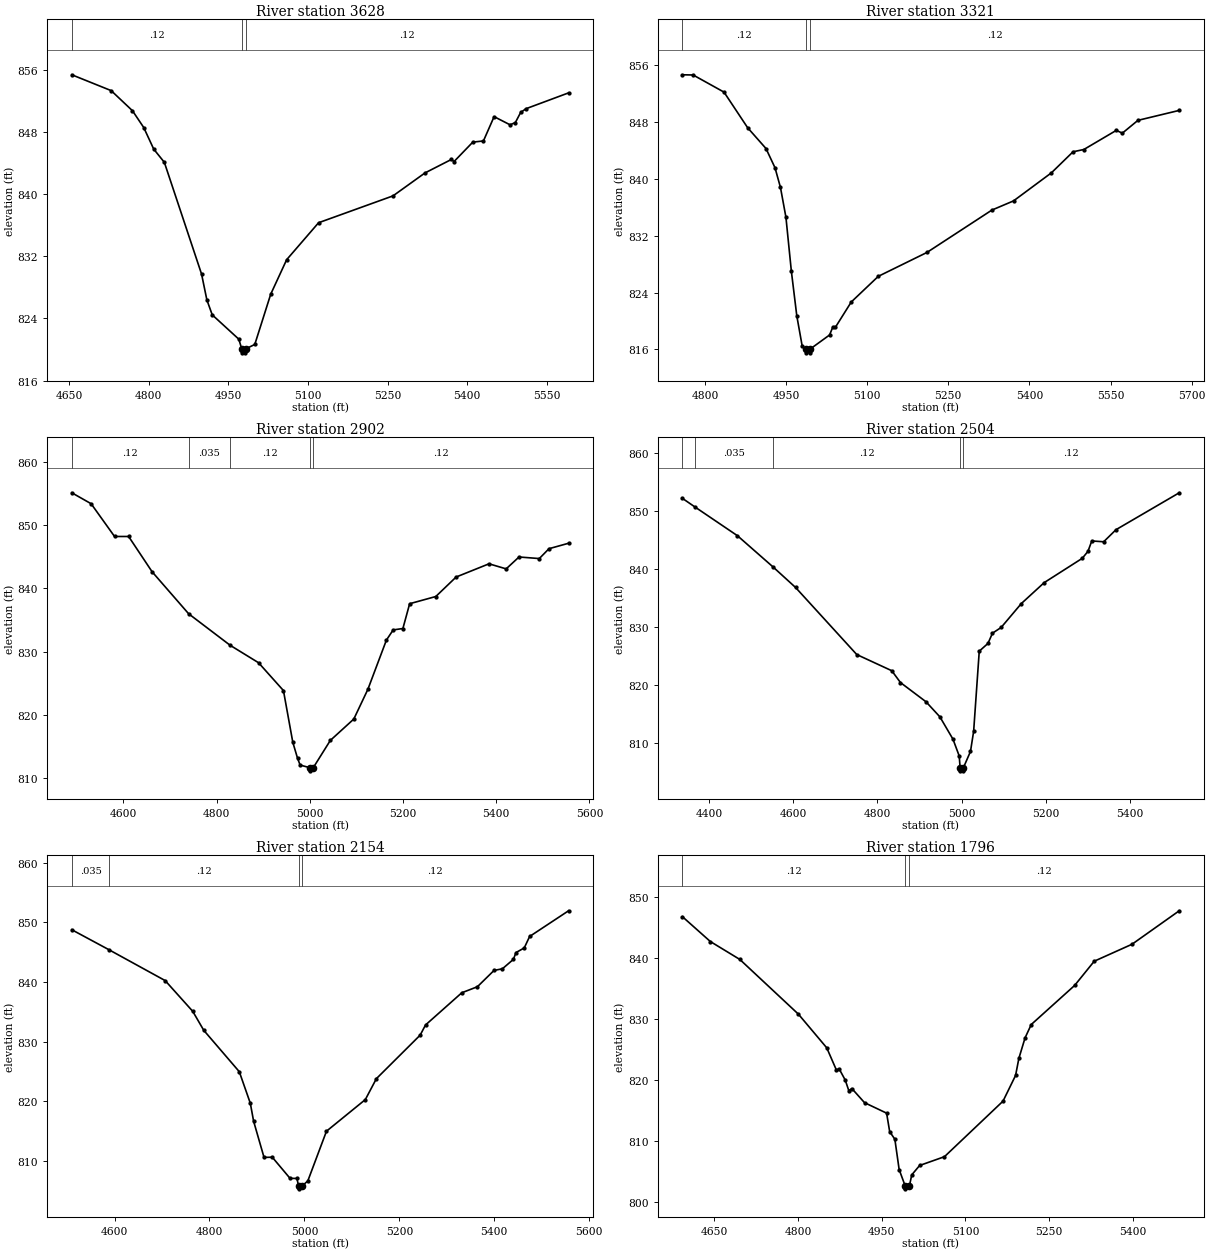
Type RM Length L Ch R = 1,3628,307,307,307
BEGIN DESCRIPTION:
H21688
END DESCRIPTION:
XS GIS Cut Line= 2
      2201569.01     13797726.72      2200634.93     13797678.99
#Sta/Elev= 30
  4655.4  855.37  4729.5  853.33  4769.6  850.74  4790.8  848.58  4809.6  845.80
  4829.6  844.10  4899.7  829.71  4909.7  826.38  4919.8  824.46  4969.8  821.33
  4975.4  820.07  4975.9  819.57  4982.0  819.57  4982.5  820.07  4999.9  820.65
  5029.9  827.12  5059.9  831.56  5120.0  836.32  5260.2  839.78  5320.3  842.73
  5370.1  844.47  5375.1  844.20  5410.4  846.70  5430.4  846.85  5450.5  849.98
  5480.5  848.93  5490.5  849.22  5500.5  850.52  5510.5  851.00  5590.7  853.04
#Mann=3,-1,0
  4655.4    0.12       0  4975.4    0.05       0  4982.5    0.12       0
Bank Sta=4975.4,4982.5
Exp/Cntr=0.3,0.1

Type RM Length L Ch R = 1,3321,419,419,419
BEGIN DESCRIPTION:
H21687
END DESCRIPTION:
XS GIS Cut Line= 3
      2201514.51     13797450.56      2201238.36     13797413.06
      2200598.67     13797433.48
#Sta/Elev= 30
  4758.4  854.64  4778.1  854.61  4835.2  852.20  4879.0  847.18  4912.8  844.27
  4929.5  841.56  4939.6  838.79  4949.7  834.60  4959.7  827.04  4969.8  820.73
  4979.9  816.43  4986.7  816.03  4987.2  815.53  4993.4  815.53  4993.9  816.03
  5030.4  818.04  5036.3  819.14  5041.3  819.14  5070.5  822.68  5120.5  826.29
  5210.5  829.65  5330.6  835.61  5370.6  836.90  5440.7  840.85  5480.7  843.81
  5500.7  844.13  5560.7  846.82  5571.9  846.43  5600.7  848.23  5677.1  849.63
#Mann=3,-1,0
  4758.4    0.12       0  4986.7    0.05       0  4993.9    0.12       0
Bank Sta=4986.7,4993.9
Exp/Cntr=0.3,0.1

Type RM Length L Ch R = 1,2902,398,398,398
BEGIN DESCRIPTION:
H21686
END DESCRIPTION:
XS GIS Cut Line= 3
      2201586.14     13797014.16      2200931.52     13797089.17
      2200608.80     13797337.16
#Sta/Elev= 30
  4489.4  855.13  4530.8  853.40  4581.1  848.22  4611.3  848.22  4661.7  842.64
  4740.1  836.00  4829.1  831.02  4890.1  828.26  4943.5  823.86  4963.6  815.68
  4973.7  813.17  4979.3  812.08  5000.2  811.67  5000.7  811.17  5007.5  811.67
  5044.1  815.98  5094.5  819.36  5124.7  824.06  5164.5  831.85  5179.0  833.45
  5199.8  833.67  5214.3  837.59  5270.4  838.73  5314.0  841.81  5384.6  843.90
  5421.4  843.10  5449.0  844.98  5492.5  844.73  5513.3  846.29  5555.3  847.15
#Mann=5,-1,0
  4489.4    0.12       0  4740.1   0.035       0  4829.1    0.12       0
  5000.2    0.05       0  5007.5    0.12       0
Bank Sta=5000.2,5007.5
Exp/Cntr=0.3,0.1

Type RM Length L Ch R = 1,2504,350,350,350
BEGIN DESCRIPTION:
H21685
END DESCRIPTION:
XS GIS Cut Line= 3
      2201613.38     13796925.52      2200815.60     13796703.92
      2200499.99     13796551.20
#Sta/Elev= 30
  4337.5  852.12  4366.6  850.67  4467.9  845.70  4552.6  840.31  4605.7  836.80
  4751.0  825.25  4834.0  822.47  4854.7  820.43  4915.2  817.13  4948.2  814.53
  4979.3  810.68  4994.1  807.79  4996.2  805.74  4996.7  805.24  5003.3  805.24
  5003.8  805.74  5020.8  808.58  5028.3  812.05  5041.6  825.83  5062.3  827.17
  5073.0  828.93  5093.5  829.91  5141.5  834.03  5195.7  837.63  5286.0  841.81
  5299.5  843.01  5308.6  844.80  5336.8  844.66  5366.1  846.74  5516.1  853.09
#Mann=5,-1,0
  4337.5    0.12       0  4366.6   0.035       0  4552.6    0.12       0
  4996.2    0.05       0  5003.8    0.12       0
Bank Sta=4996.2,5003.8
Exp/Cntr=0.3,0.1

Type RM Length L Ch R = 1,2154,358,358,358
BEGIN DESCRIPTION:
H21684
END DESCRIPTION:
XS GIS Cut Line= 2
      2201654.34     13796693.71      2200699.83     13796264.18
#Sta/Elev= 30
  4509.9  848.73  4588.9  845.35  4706.6  840.21  4764.7  835.06  4787.9  831.88
  4862.8  824.94  4886.0  819.66  4893.0  816.63  4914.9  810.58  4932.3  810.61
  4969.7  807.07  4984.1  807.05  4987.8  805.81  4988.3  805.31  4995.5  805.81
  5007.2  806.64  5046.5  814.97  5128.4  820.27  5151.6  823.77  5243.9  831.07
  5255.2  832.77  5331.6  838.17  5364.5  839.18  5399.5  841.91  5417.2  842.19
  5440.4  843.77  5445.8  844.91  5463.2  845.68  5474.5  847.60  5556.6  851.91
#Mann=4,-1,0
  4509.9   0.035       0  4588.9    0.12       0  4987.8    0.05       0
  4995.5    0.12       0
Bank Sta=4987.8,4995.5
Exp/Cntr=0.3,0.1

Type RM Length L Ch R = 1,1796,375,375,375
BEGIN DESCRIPTION:
H21683
END DESCRIPTION:
XS GIS Cut Line= 2
      2201797.50     13796400.50      2200996.30     13796011.83
#Sta/Elev= 30
  4592.8  846.71  4642.7  842.65  4695.6  839.71  4800.7  830.73  4851.4  825.22
  4868.4  821.64  4873.9  821.73  4884.6  819.92  4890.9  818.21  4896.5  818.54
  4919.1  816.23  4958.7  814.51  4964.2  811.48  4973.5  810.23  4981.2  805.26
  4991.9  802.60  4992.4  802.10  4999.6  802.60  5003.8  804.39  5017.9  805.93
  5062.4  807.37  5167.4  816.48  5189.9  820.69  5195.8  823.49  5206.9  826.85
  5218.0  829.04  5295.8  835.45  5330.9  839.42  5398.6  842.20  5483.3  847.69
#Mann=3,-1,0
  4592.8    0.12       0  4991.9    0.05       0  4999.6    0.12       0
Bank Sta=4991.9,4999.6
Exp/Cntr=0.3,0.1

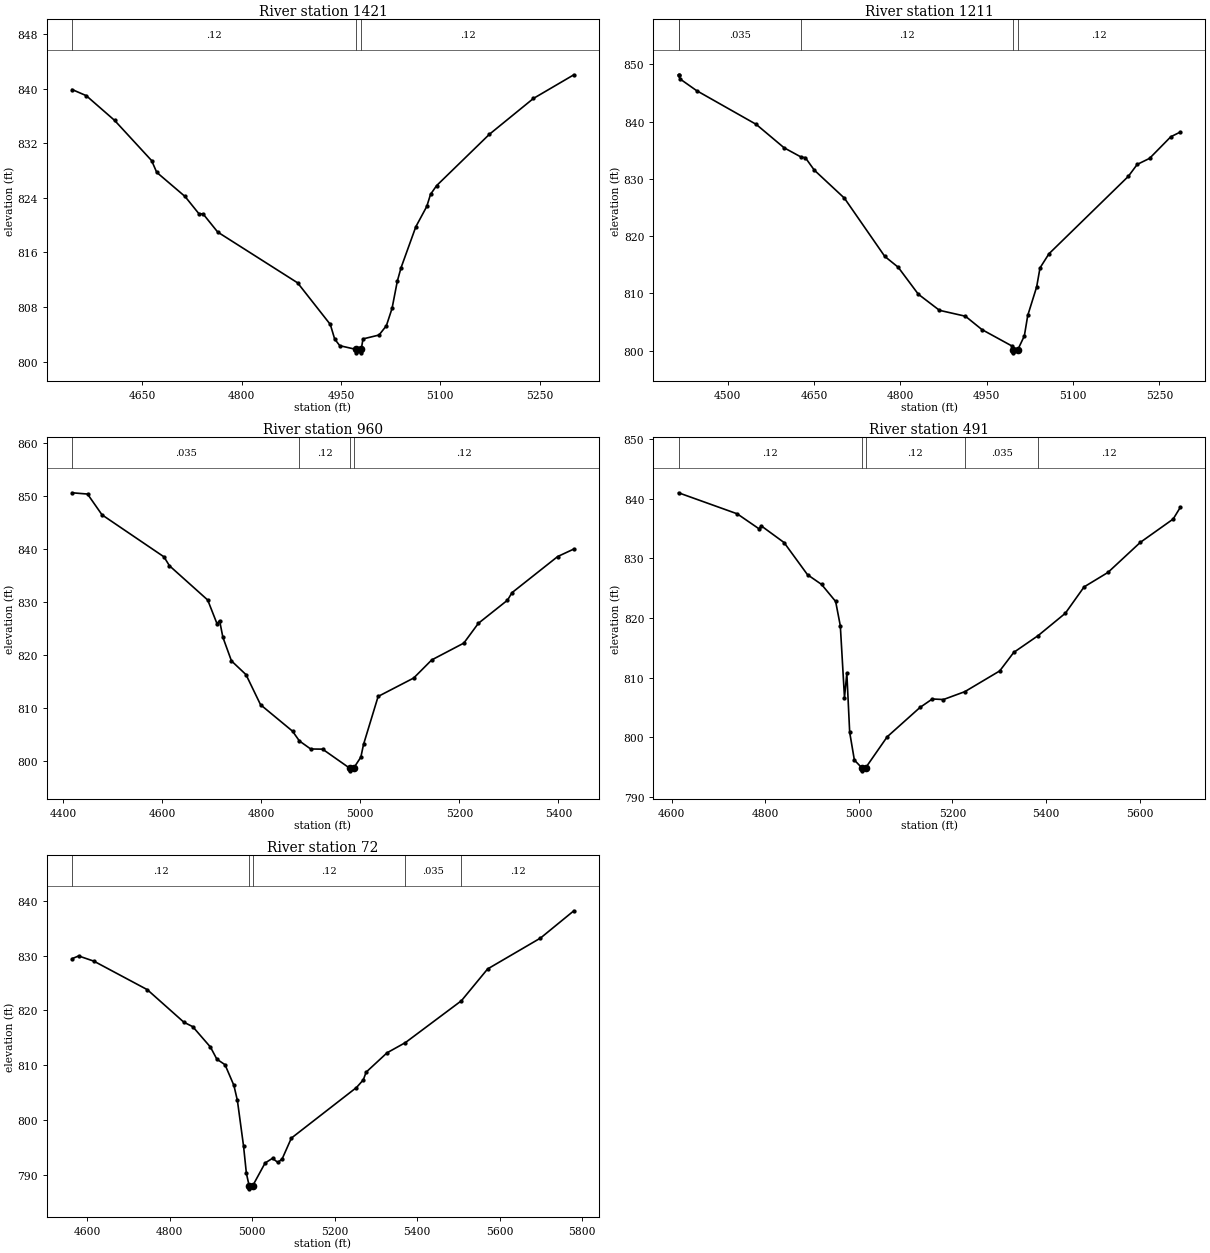
Type RM Length L Ch R = 1,1421,210,210,210
BEGIN DESCRIPTION:
West Fork Tributary 3.0
END DESCRIPTION:
XS GIS Cut Line= 3
      2201825.01     13796225.01      2201525.00     13795875.00
      2201260.31     13795739.84
#Sta/Elev= 30
  4543.7  839.89  4565.1  838.99  4607.9  835.37  4663.9  829.47  4671.6  827.75
  4714.4  824.21  4735.2  821.70  4741.8  821.64  4763.8  818.99  4884.5  811.55
  4933.9  805.45  4940.5  803.31  4948.2  802.34  4972.8  801.79  4973.3  801.29
  4980.1  801.29  4980.6  801.79  4983.3  803.33  5007.5  803.90  5018.6  805.26
  5027.2  807.81  5035.2  811.82  5040.8  813.77  5063.1  819.77  5079.7  822.76
  5085.3  824.52  5094.5  825.80  5174.2  833.32  5240.8  838.58  5301.9  842.05
#Mann=3,-1,0
  4543.7    0.12       0  4972.8    0.05       0  4980.6    0.12       0
Bank Sta=4972.8,4980.6
Exp/Cntr=0.3,0.1

Type RM Length L Ch R = 1,1211,251,251,251
BEGIN DESCRIPTION:
H21682
END DESCRIPTION:
XS GIS Cut Line= 2
      2202141.83     13796011.82      2201395.17     13795561.78
#Sta/Elev= 30
  4414.4  848.16  4414.5  848.13  4417.2  847.42  4445.7  845.40  4549.3  839.51
  4597.8  835.42  4627.8  833.78  4634.7  833.70  4650.2  831.53  4702.6  826.63
  4772.7  816.47  4796.0  814.58  4831.0  809.87  4867.7  807.06  4912.8  806.03
  4941.5  803.70  4993.9  800.82  4995.8  800.14  4996.3  799.64  5003.6  800.14
  5015.2  802.59  5021.1  806.16  5036.6  811.15  5042.4  814.46  5058.0  816.93
  5195.8  830.43  5211.3  832.52  5232.7  833.57  5269.6  837.34  5286.2  838.17
#Mann=5,-1,0
  4414.4    0.12       0  4414.5   0.035       0  4627.8    0.12       0
  4995.8    0.05       0  5003.6    0.12       0
Bank Sta=4995.8,5003.6
Exp/Cntr=0.3,0.1

Type RM Length L Ch R = 1,960,469,469,469
BEGIN DESCRIPTION:
H21681
END DESCRIPTION:
XS GIS Cut Line= 2
      2202356.66     13795752.73      2201419.50     13795367.64
#Sta/Elev= 30
  4417.9  850.63  4449.1  850.39  4478.4  846.46  4603.5  838.52  4614.5  836.84
  4691.8  830.36  4710.4  825.92  4715.8  826.46  4722.4  823.33  4739.7  818.86
  4769.1  816.26  4798.5  810.57  4863.0  805.58  4876.9  803.73  4899.7  802.21
  4923.7  802.18  4978.5  798.58  4979.0  798.08  4986.4  798.58  5001.0  800.67
  5006.4  803.07  5035.9  812.14  5107.7  815.62  5144.1  819.04  5208.9  822.22
  5238.3  825.96  5297.1  830.33  5306.2  831.75  5398.4  838.58  5431.1  840.00
#Mann=4,-1,0
  4417.9   0.035       0  4876.9    0.12       0  4978.5    0.05       0
  4986.4    0.12       0
Bank Sta=4978.5,4986.4
Exp/Cntr=0.3,0.1

Type RM Length L Ch R = 1,491,419,419,419
BEGIN DESCRIPTION:
H21680
END DESCRIPTION:
XS GIS Cut Line= 2
      2202510.07     13795210.63      2201439.74     13795268.58
#Sta/Elev= 30
  4614.8  841.03  4740.1  837.50  4786.6  834.99  4791.6  835.47  4840.2  832.68
  4890.3  827.28  4920.3  825.65  4950.4  822.79  4960.4  818.70  4969.3  806.66
  4974.3  810.75  4980.4  800.83  4990.4  796.17  5006.4  794.86  5006.9  794.36
  5014.4  794.86  5060.5  800.07  5130.6  805.00  5156.9  806.42  5180.7  806.33
  5226.4  807.65  5300.9  811.13  5330.9  814.24  5383.0  817.06  5441.1  820.81
  5481.1  825.23  5532.1  827.66  5601.3  832.71  5671.4  836.62  5686.7  838.59
#Mann=5,-1,0
  4614.8    0.12       0  5006.4    0.05       0  5014.4    0.12       0
  5226.4   0.035       0  5383.0    0.12       0
Bank Sta=5006.4,5014.4
Exp/Cntr=0.3,0.1

Type RM Length L Ch R = 1,72,0,0,0
BEGIN DESCRIPTION:
H21679
END DESCRIPTION:
XS GIS Cut Line= 4
      2202452.06     13794989.01      2202135.01     13794801.51
      2201814.53     13794941.29      2201405.39     13795227.69
#Sta/Elev= 30
  4562.8  829.43  4578.7  829.93  4615.7  828.98  4745.3  823.78  4834.1  817.84
  4855.6  817.03  4898.5  813.31  4914.1  811.10  4933.9  810.09  4955.4  806.32
  4963.9  803.57  4978.8  795.27  4985.7  790.28  4992.6  787.95  4993.1  787.45
  5000.6  787.95  5031.1  792.16  5049.1  793.02  5062.1  792.26  5072.5  792.91
  5094.8  796.70  5252.8  805.93  5269.4  807.33  5276.2  808.73  5326.9  812.26
  5371.6  814.13  5507.4  821.76  5571.0  827.56  5699.2  833.19  5780.2  838.17
#Mann=5,-1,0
  4562.8    0.12       0  4992.6    0.05       0  5000.6    0.12       0
  5371.6   0.035       0  5507.4    0.12       0
Bank Sta=4992.6,5000.6
Exp/Cntr=0.3,0.1

Chan Stop Cuts=-1