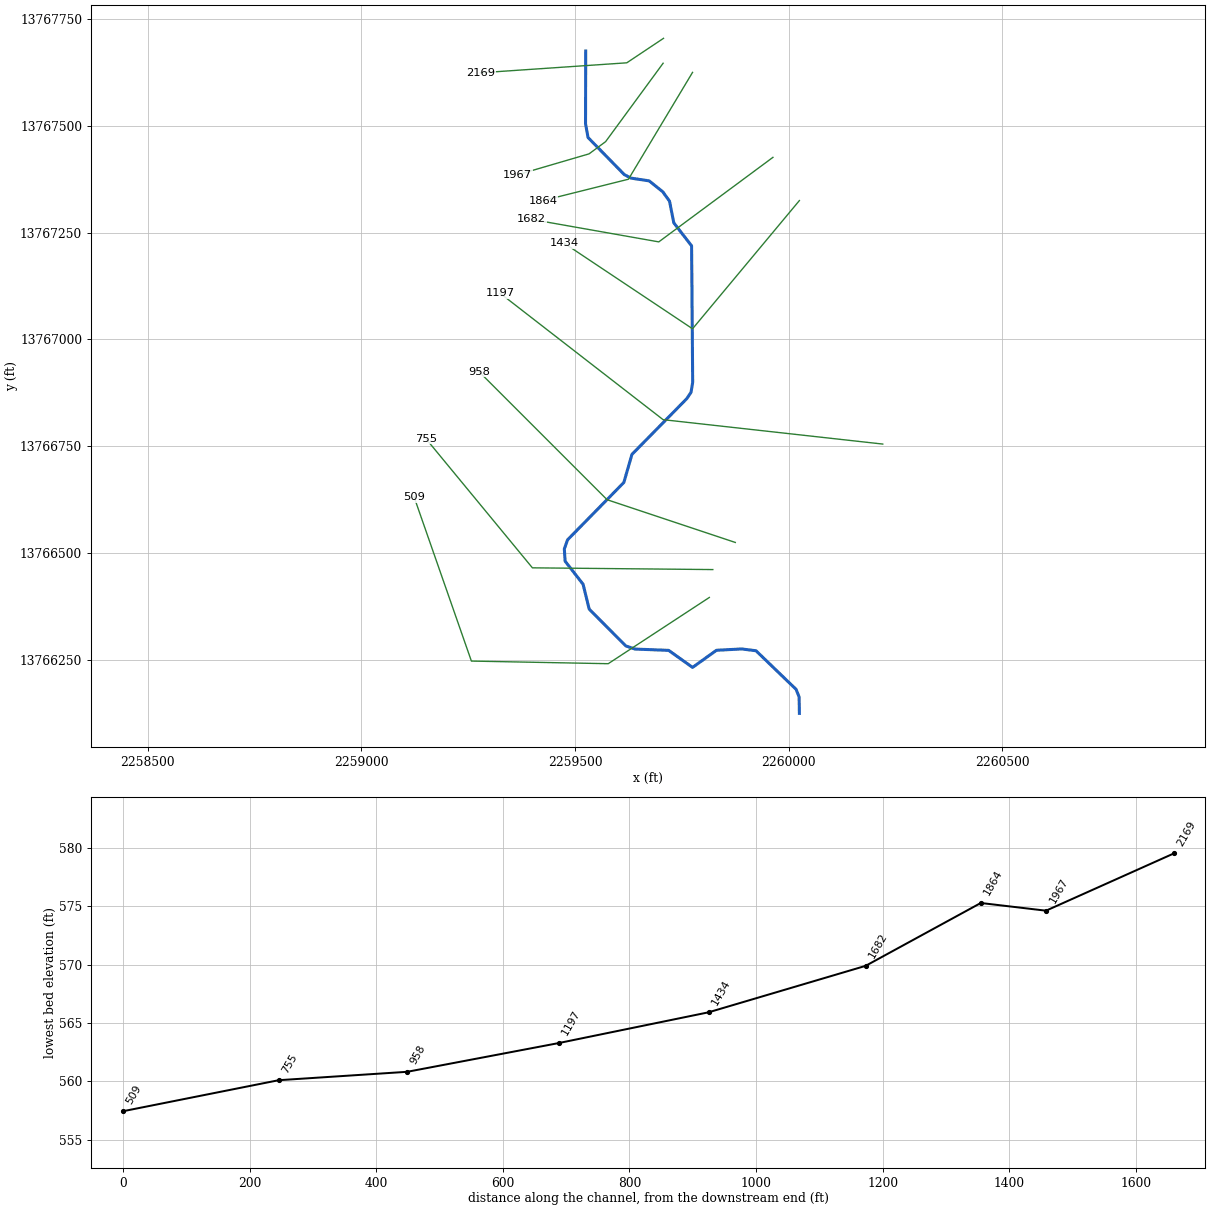
--- YOUNGS CREEK TRIBUTARY B.prj (project) ---

Proj Title=YOUNGS CREEK TRIBUTARY B Base Level Engineering
Current Plan=p01
Default Exp/Contr=0.3,0.1
English Units
Geom File=g01
Flow File=f01
Plan File=p01
BEGIN DESCRIPTION:
YOUNGS CREEK TRIBUTARY B
END DESCRIPTION:

--- YOUNGS CREEK TRIBUTARY B.p01 (plan) ---

Plan Title=Multiple Run
Short Identifier=Multiple
Geom File=g01
Flow File=f01
Subcritical Flow
K Sum by GR= 0
Std Step Tol= 0.01
Critical Tol= 0.01
Num of Std Step Trials= 20
Max Error Tol= 0.3
Flow Tol Ratio= 0.001
Split Flow NTrial= 30
Split Flow Tol= 0.02
Split Flow Ratio= 0.02
Log Output Level= 0
Friction Slope Method= 1
Unsteady Friction Slope Method= 2
Unsteady Bridges Friction Slope Method= 1
Parabolic Critical Depth
Global Vel Dist=  1 , 1 , 1
Global Log Level= 0
CheckData=True
Encroach Param= -1, 0, 0, 0
BEGIN DESCRIPTION:
Multiple Run
END DESCRIPTION:

--- YOUNGS CREEK TRIBUTARY B.f01 (steady flow) ---

Flow Title=Multiple
Number of Profiles=7
Profile Names=10-year,25-year,50-year,1pct_min,100-year,1pct_plu,500-year
River Rch & RM= YOUNGS CREEK TRI,Reach-1,2169
     221     336     433     272     543    1083     841
Boundary for River Rch & Prof#=YOUNGS CREEK TRI,Reach-1,1
Up Type=0
Dn Type=3
Dn Slope=0.005
Boundary for River Rch & Prof#=YOUNGS CREEK TRI,Reach-1,2
Up Type=0
Dn Type=3
Dn Slope=0.005
Boundary for River Rch & Prof#=YOUNGS CREEK TRI,Reach-1,3
Up Type=0
Dn Type=3
Dn Slope=0.005
Boundary for River Rch & Prof#=YOUNGS CREEK TRI,Reach-1,4
Up Type=0
Dn Type=3
Dn Slope=0.005
Boundary for River Rch & Prof#=YOUNGS CREEK TRI,Reach-1,5
Up Type=0
Dn Type=3
Dn Slope=0.005
Boundary for River Rch & Prof#=YOUNGS CREEK TRI,Reach-1,6
Up Type=0
Dn Type=3
Dn Slope=0.005
Boundary for River Rch & Prof#=YOUNGS CREEK TRI,Reach-1,7
Up Type=0
Dn Type=3
Dn Slope=0.005

--- YOUNGS CREEK TRIBUTARY B.g01 (geometry) ---

Geom Title=Existing Conditions

River Reach=YOUNGS CREEK TRI,Reach-1
Reach XY= 30
      2259525.00     13767675.00      2259524.55     13767504.81
      2259530.45     13767472.53      2259615.31     13767385.78
      2259631.08     13767377.55      2259673.57     13767371.11
      2259705.38     13767345.47      2259721.14     13767323.58
      2259731.15     13767272.85      2259772.76     13767219.07
      2259775.30     13766899.88      2259771.46     13766876.46
      2259761.63     13766861.68      2259633.16     13766731.05
      2259614.22     13766665.32      2259482.48     13766531.06
      2259474.95     13766509.66      2259476.76     13766481.12
      2259518.82     13766427.19      2259533.13     13766368.93
      2259618.81     13766282.85      2259640.21     13766275.51
      2259719.10     13766272.44      2259775.00     13766232.56
      2259830.90     13766272.64      2259890.08     13766275.76
      2259923.51     13766271.55      2260017.25     13766181.24
      2260024.41     13766163.17      2260025.00     13766125.00

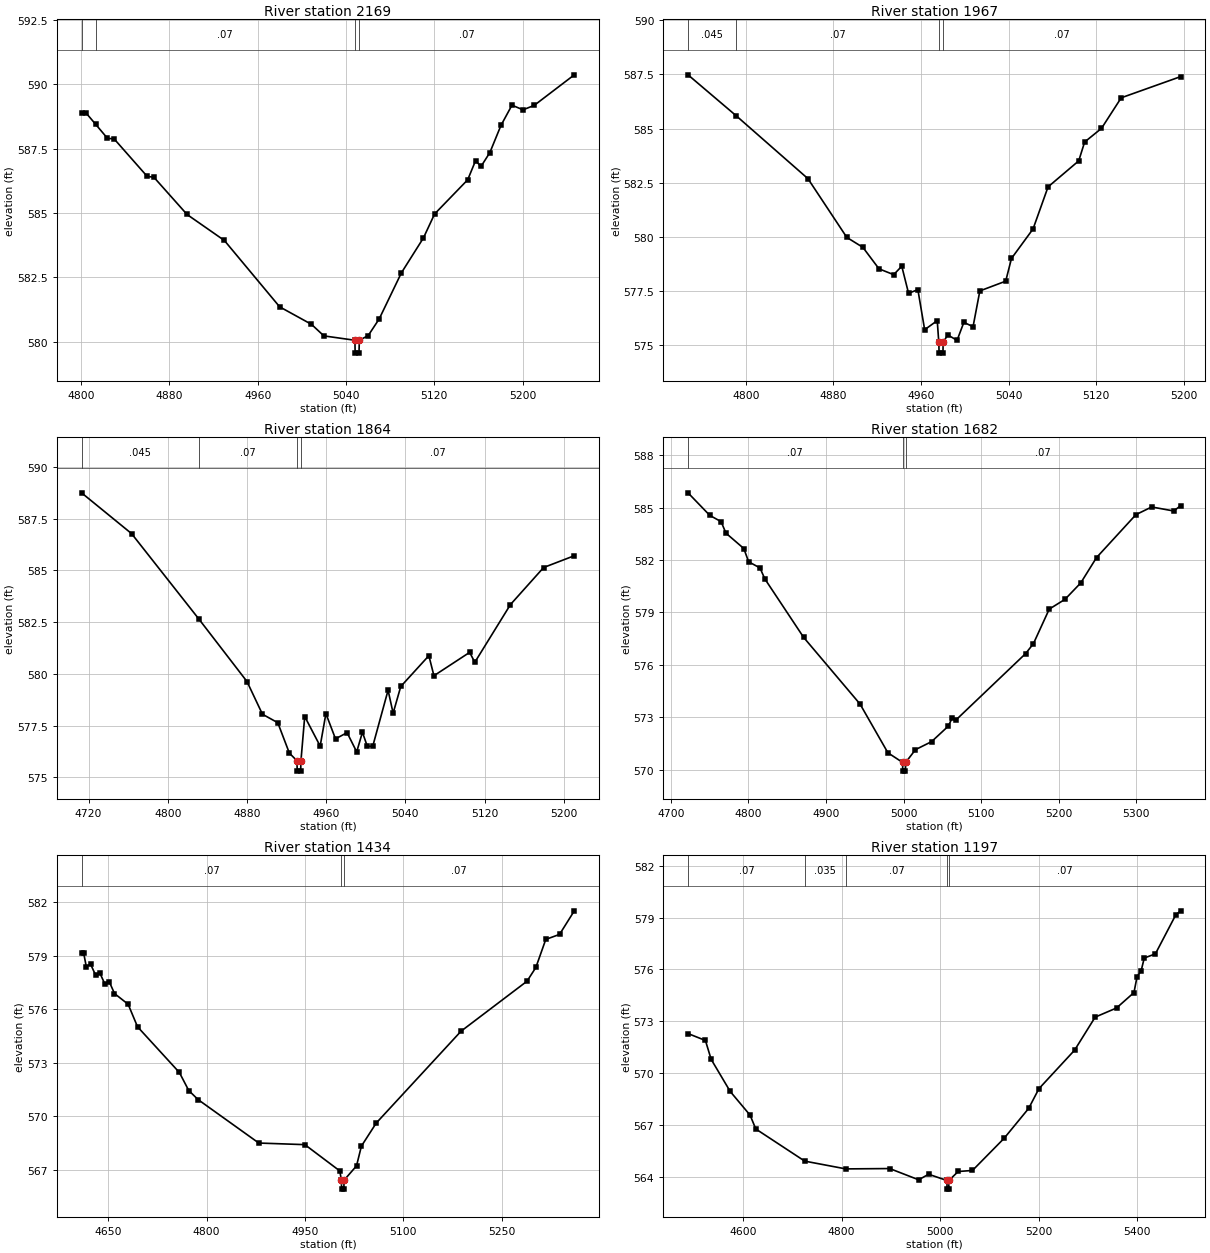
Type RM Length L Ch R = 1,2169,202,202,202
BEGIN DESCRIPTION:
J21812
END DESCRIPTION:
XS GIS Cut Line= 3
      2259707.01     13767704.68      2259621.09     13767647.40
      2259278.65     13767624.05
#Sta/Elev= 30
  4800.4  588.88  4804.6  588.88  4813.1  588.45  4823.9  587.90  4829.9  587.88
  4859.9  586.42  4865.9  586.39  4896.0  584.94  4929.8  583.93  4979.9  581.35
  5008.7  580.67  5020.0  580.22  5048.1  580.05  5048.3  579.55  5051.8  579.55
  5052.1  580.05  5060.1  580.23  5070.1  580.88  5090.2  582.67  5110.2  584.03
  5120.3  584.96  5150.3  586.29  5157.4  587.03  5162.4  586.81  5170.4  587.35
  5180.4  588.40  5190.4  589.19  5200.4  589.01  5210.5  589.18  5246.9  590.37
#Mann=4,-1,0
  4800.4   0.045       0  4813.1    0.07       0  5048.1    0.05       0
  5052.1    0.07       0
Bank Sta=5048.1,5052.1
Exp/Cntr=0.3,0.1

Type RM Length L Ch R = 1,1967,103,103,103
BEGIN DESCRIPTION:
J21811
END DESCRIPTION:
XS GIS Cut Line= 4
      2259706.15     13767646.45      2259571.54     13767462.89
      2259532.79     13767434.34      2259365.56     13767385.40
#Sta/Elev= 30
  4747.2  587.48  4791.0  585.60  4856.7  582.69  4892.2  579.98  4906.9  579.52
  4921.6  578.53  4935.0  578.26  4942.4  578.65  4948.6  577.40  4957.1  577.57
  4963.3  575.72  4974.8  576.14  4976.2  575.14  4976.5  574.64  4980.0  574.64
  4980.2  575.14  4984.4  575.48  4992.9  575.23  4999.1  576.06  5007.5  575.86
  5013.7  577.51  5037.3  577.96  5042.6  579.01  5062.3  580.37  5076.0  582.31
  5104.0  583.51  5109.4  584.38  5124.8  585.01  5142.8  586.42  5197.2  587.40
#Mann=4,-1,0
  4747.2   0.045       0  4791.0    0.07       0  4976.2    0.05       0
  4980.2    0.07       0
Bank Sta=4976.2,4980.2
Exp/Cntr=0.3,0.1

Type RM Length L Ch R = 1,1864,182,182,182
BEGIN DESCRIPTION:
YOUNGS CREEK TRIBUTARY B 3.0
END DESCRIPTION:
XS GIS Cut Line= 3
      2259774.98     13767624.97      2259625.00     13767375.00
      2259424.97     13767324.99
#Sta/Elev= 30
  4712.9  588.75  4763.4  586.78  4831.4  582.65  4880.0  579.63  4895.6  578.05
  4911.1  577.64  4922.8  576.17  4930.5  575.80  4930.7  575.30  4934.2  575.30
  4934.5  575.80  4938.3  577.94  4953.9  576.51  4959.7  578.08  4969.4  576.86
  4981.1  577.16  4990.8  576.23  4996.6  577.18  5001.5  576.50  5007.0  576.50
  5022.5  579.21  5027.6  578.10  5035.3  579.39  5063.7  580.88  5068.8  579.91
  5104.9  581.04  5110.1  580.56  5146.1  583.35  5179.6  585.14  5210.6  585.71
#Mann=4,-1,0
  4712.9   0.045       0  4831.4    0.07       0  4930.5    0.05       0
  4934.5    0.07       0
Bank Sta=4930.5,4934.5
Exp/Cntr=0.3,0.1

Type RM Length L Ch R = 1,1682,248,248,248
BEGIN DESCRIPTION:
J21810
END DESCRIPTION:
XS GIS Cut Line= 3
      2259963.15     13767426.20      2259695.95     13767228.36
      2259398.05     13767281.05
#Sta/Elev= 30
  4722.3  585.85  4750.3  584.56  4764.9  584.20  4771.2  583.54  4794.2  582.66
  4800.4  581.90  4815.0  581.55  4821.3  580.92  4871.3  577.57  4944.0  573.75
  4979.9  570.96  4998.8  570.41  4999.0  569.91  5002.5  569.91  5002.8  570.41
  5015.4  571.14  5036.2  571.60  5057.8  572.49  5062.5  572.94  5067.6  572.84
  5157.3  576.64  5167.4  577.21  5187.8  579.19  5208.1  579.75  5228.4  580.69
  5248.7  582.14  5299.5  584.60  5319.8  585.04  5348.2  584.81  5357.3  585.12
#Mann=3,-1,0
  4722.3    0.07       0  4998.8    0.05       0  5002.8    0.07       0
Bank Sta=4998.8,5002.8
Exp/Cntr=0.3,0.1

Type RM Length L Ch R = 1,1434,237,237,237
BEGIN DESCRIPTION:
YOUNGS CREEK TRIBUTARY B 2.0
END DESCRIPTION:
XS GIS Cut Line= 3
      2260025.03     13767325.04      2259775.00     13767025.00
      2259475.01     13767224.99
#Sta/Elev= 30
  4609.5  579.13  4612.8  579.13  4616.7  578.39  4623.2  578.53  4631.0  577.90
  4637.5  578.02  4645.3  577.39  4651.9  577.53  4659.7  576.88  4680.5  576.28
  4694.8  575.02  4758.6  572.46  4772.9  571.45  4787.2  570.94  4879.7  568.51
  4949.9  568.42  5003.1  566.95  5005.6  566.43  5005.8  565.93  5009.3  565.93
  5009.6  566.43  5028.6  567.23  5036.1  568.34  5058.7  569.63  5187.9  574.77
  5288.5  577.57  5302.0  578.34  5317.1  579.91  5338.1  580.19  5360.6  581.51
#Mann=3,-1,0
  4609.5    0.07       0  5005.6    0.05       0  5009.6    0.07       0
Bank Sta=5005.6,5009.6
Exp/Cntr=0.3,0.1

Type RM Length L Ch R = 1,1197,239,239,239
BEGIN DESCRIPTION:
J21809
END DESCRIPTION:
XS GIS Cut Line= 3
      2260220.08     13766755.20      2259706.15     13766812.30
      2259324.76     13767108.03
#Sta/Elev= 30
  4488.6  572.29  4523.9  571.89  4535.5  570.80  4574.2  568.94  4614.5  567.57
  4626.1  566.77  4725.4  564.91  4808.8  564.46  4897.7  564.48  4956.5  563.83
  4976.7  564.15  5013.9  563.79  5014.1  563.29  5017.6  563.29  5017.9  563.79
  5036.7  564.31  5065.7  564.37  5129.9  566.23  5179.7  567.96  5200.5  569.10
  5272.9  571.33  5314.6  573.24  5358.0  573.77  5393.3  574.66  5399.7  575.59
  5407.8  575.91  5414.2  576.66  5436.8  576.90  5478.4  579.17  5488.3  579.39
#Mann=5,-1,0
  4488.6    0.07       0  4725.4   0.035       0  4808.8    0.07       0
  5013.9    0.05       0  5017.9    0.07       0
Bank Sta=5013.9,5017.9
Exp/Cntr=0.3,0.1

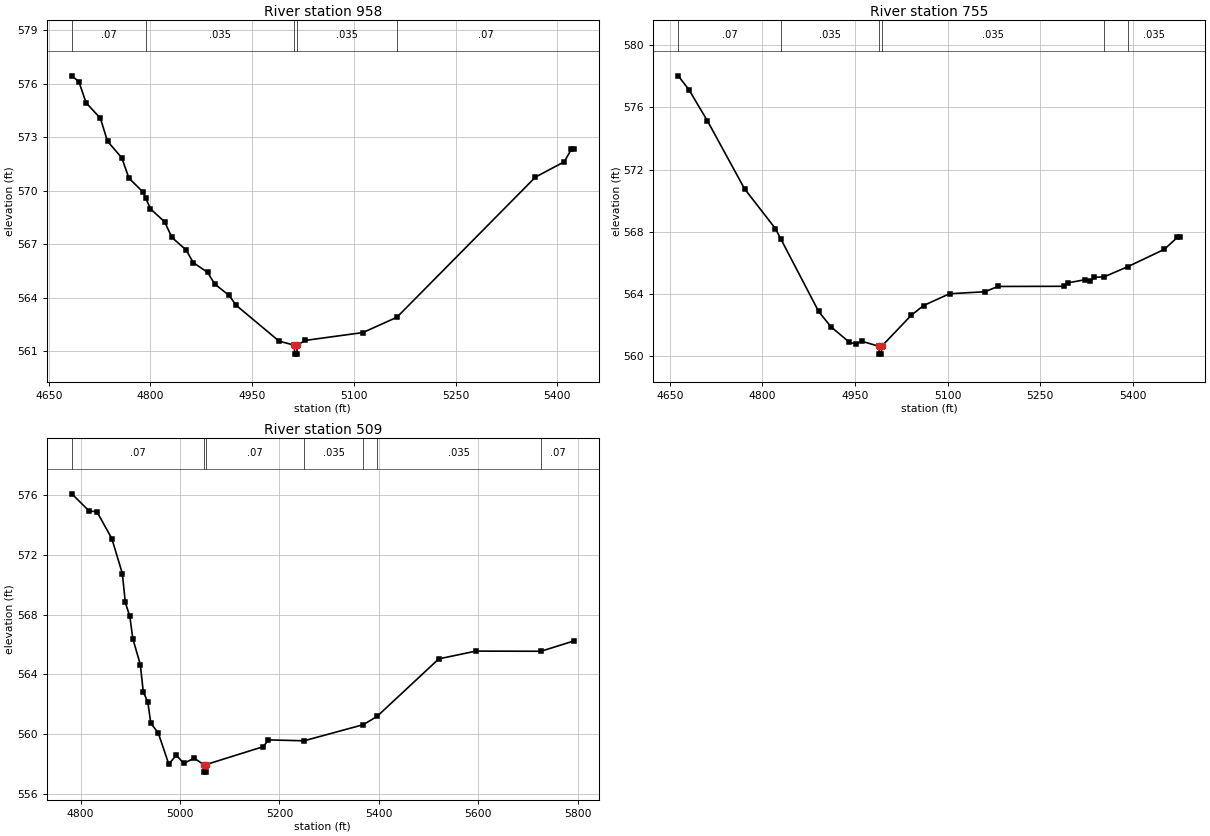
Type RM Length L Ch R = 1,958,203,203,203
BEGIN DESCRIPTION:
YOUNGS CREEK TRIBUTARY B 1.0
END DESCRIPTION:
XS GIS Cut Line= 3
      2259875.01     13766525.00      2259575.00     13766625.00
      2259275.00     13766925.00
#Sta/Elev= 30
  4684.0  576.44  4694.5  576.11  4705.1  574.93  4726.2  574.06  4736.7  572.77
  4757.8  571.84  4768.3  570.70  4789.4  569.91  4793.0  569.59  4800.0  568.98
  4821.0  568.25  4831.6  567.38  4852.7  566.67  4863.2  565.96  4884.3  565.42
  4894.8  564.76  4915.9  564.13  4926.4  563.57  4989.7  561.56  5012.4  561.33
  5012.6  560.83  5016.1  560.83  5016.4  561.33  5028.5  561.60  5113.4  562.04
  5163.6  562.90  5367.9  570.76  5410.4  571.62  5421.0  572.33  5424.5  572.33
#Mann=5,-1,0
  4684.0    0.07       0  4793.0   0.035       0  5012.4   0.035       0
  5016.4   0.035       0  5163.6    0.07       0
Bank Sta=5012.4,5016.4
Exp/Cntr=0.3,0.1

Type RM Length L Ch R = 1,755,246,246,246
BEGIN DESCRIPTION:
J21808
END DESCRIPTION:
XS GIS Cut Line= 3
      2259822.36     13766461.51      2259400.23     13766465.59
      2259151.43     13766767.41
#Sta/Elev= 30
  4663.7  578.04  4681.1  577.14  4711.1  575.13  4771.1  570.76  4821.1  568.20
  4830.3  567.50  4891.1  562.86  4911.1  561.87  4941.1  560.87  4951.1  560.77
  4961.1  560.94  4989.1  560.61  4989.3  560.11  4992.8  560.11  4993.1  560.61
  5041.1  562.61  5061.1  563.24  5103.2  564.00  5160.6  564.13  5181.4  564.47
  5288.3  564.48  5294.8  564.70  5323.4  564.91  5331.3  564.81  5337.8  565.06
  5353.7  565.09  5391.7  565.74  5451.1  566.86  5472.2  567.63  5477.0  567.63
#Mann=6,-1,0
  4663.7    0.07       0  4830.3   0.035       0  4989.1   0.035       0
  4993.1   0.035       0  5353.7    0.07       0  5391.7   0.035       0
Bank Sta=4989.1,4993.1
Exp/Cntr=0.3,0.1

Type RM Length L Ch R = 1,509,0,0,0
BEGIN DESCRIPTION:
J21807
END DESCRIPTION:
XS GIS Cut Line= 4
      2259814.24     13766396.25      2259577.66     13766241.25
      2259257.46     13766247.37      2259123.35     13766631.44
#Sta/Elev= 30
  4782.2  576.10  4817.5  574.94  4832.6  574.91  4862.8  573.10  4883.9  570.76
  4889.9  568.82  4899.0  567.88  4905.0  566.39  4920.1  564.66  4926.0  562.83
  4935.2  562.14  4941.1  560.73  4956.2  560.07  4977.3  557.99  4992.4  558.58
  5007.5  558.04  5028.6  558.38  5047.7  557.95  5047.9  557.45  5051.4  557.45
  5051.7  557.95  5167.7  559.16  5177.7  559.61  5249.4  559.55  5368.6  560.63
  5396.1  561.18  5520.5  565.04  5594.9  565.56  5726.0  565.55  5792.1  566.24
#Mann=7,-1,0
  4782.2    0.07       0  5047.7    0.05       0  5051.7    0.07       0
  5249.4   0.035       0  5368.6    0.07       0  5396.1   0.035       0
  5726.0    0.07       0
Bank Sta=5047.7,5051.7
Exp/Cntr=0.3,0.1

Chan Stop Cuts=-1