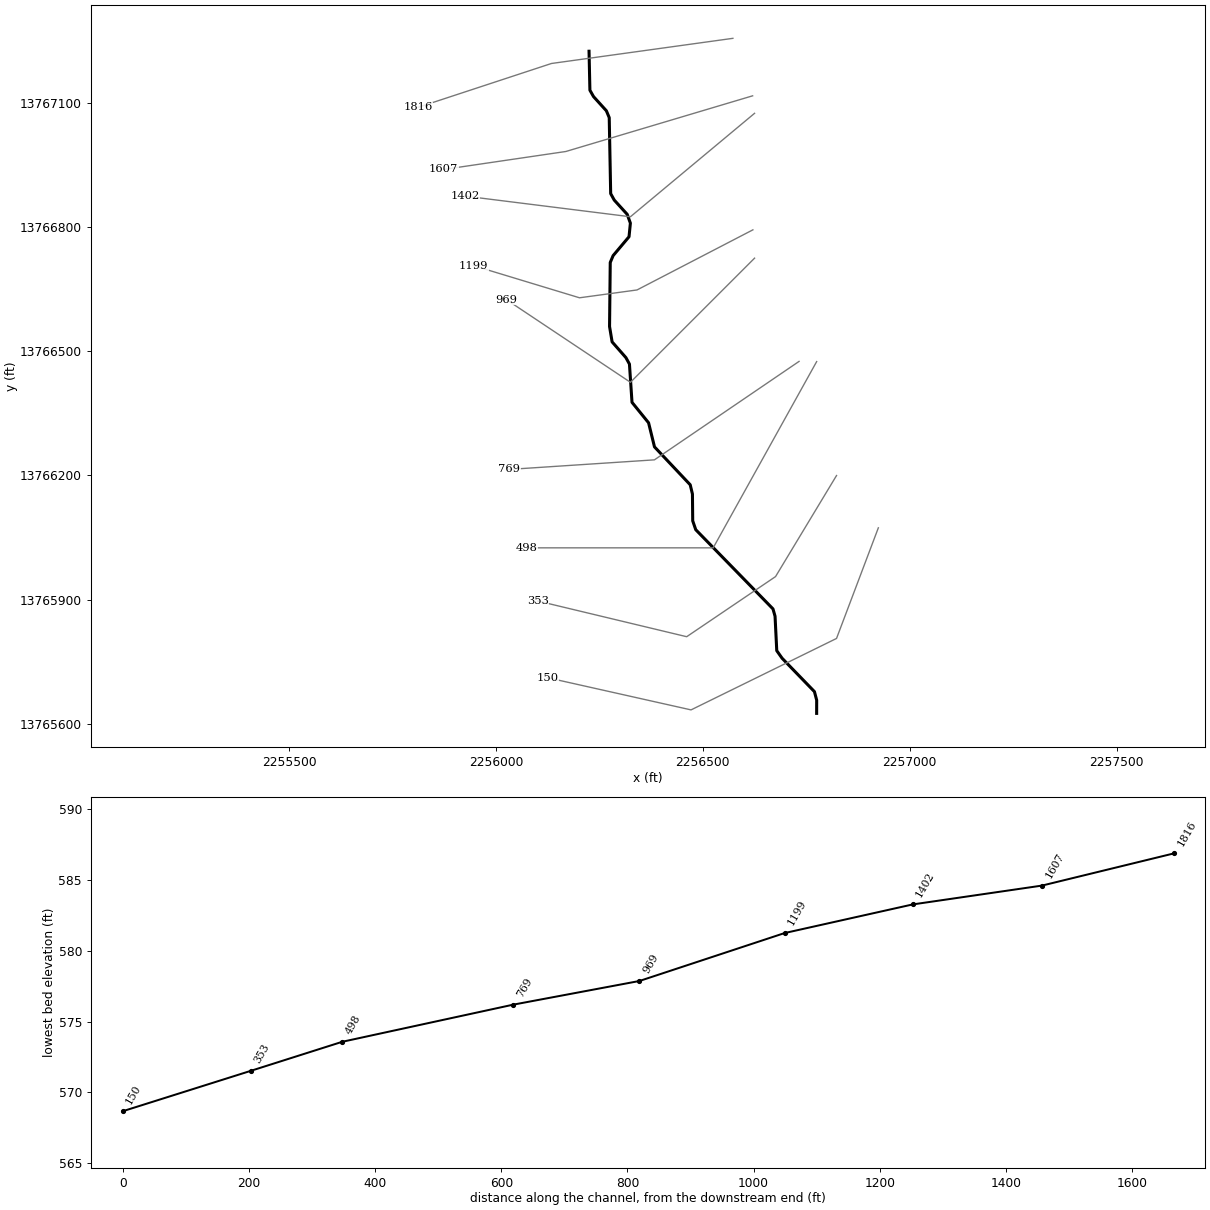
--- YOUNGS CREEK TRIBUTARY E.prj (project) ---

Proj Title=YOUNGS CREEK TRIBUTARY E Base Level Engineering
Current Plan=p01
Default Exp/Contr=0.3,0.1
English Units
Geom File=g01
Flow File=f01
Plan File=p01
BEGIN DESCRIPTION:
YOUNGS CREEK TRIBUTARY E
END DESCRIPTION:

--- YOUNGS CREEK TRIBUTARY E.p01 (plan) ---

Plan Title=Multiple Run
Short Identifier=Multiple
Geom File=g01
Flow File=f01
Subcritical Flow
K Sum by GR= 0
Std Step Tol= 0.01
Critical Tol= 0.01
Num of Std Step Trials= 20
Max Error Tol= 0.3
Flow Tol Ratio= 0.001
Split Flow NTrial= 30
Split Flow Tol= 0.02
Split Flow Ratio= 0.02
Log Output Level= 0
Friction Slope Method= 1
Unsteady Friction Slope Method= 2
Unsteady Bridges Friction Slope Method= 1
Parabolic Critical Depth
Global Vel Dist=  1 , 1 , 1
Global Log Level= 0
CheckData=True
Encroach Param= -1, 0, 0, 0
BEGIN DESCRIPTION:
Multiple Run
END DESCRIPTION:

--- YOUNGS CREEK TRIBUTARY E.f01 (steady flow) ---

Flow Title=Multiple
Number of Profiles=7
Profile Names=10-year,25-year,50-year,1pct_min,100-year,1pct_plu,500-year
River Rch & RM= YOUNGS CREEK TRI,Reach-1,1816
     230     348     447     280     558    1113     856
Boundary for River Rch & Prof#=YOUNGS CREEK TRI,Reach-1,1
Up Type=0
Dn Type=3
Dn Slope=0.005
Boundary for River Rch & Prof#=YOUNGS CREEK TRI,Reach-1,2
Up Type=0
Dn Type=3
Dn Slope=0.005
Boundary for River Rch & Prof#=YOUNGS CREEK TRI,Reach-1,3
Up Type=0
Dn Type=3
Dn Slope=0.005
Boundary for River Rch & Prof#=YOUNGS CREEK TRI,Reach-1,4
Up Type=0
Dn Type=3
Dn Slope=0.005
Boundary for River Rch & Prof#=YOUNGS CREEK TRI,Reach-1,5
Up Type=0
Dn Type=3
Dn Slope=0.005
Boundary for River Rch & Prof#=YOUNGS CREEK TRI,Reach-1,6
Up Type=0
Dn Type=3
Dn Slope=0.005
Boundary for River Rch & Prof#=YOUNGS CREEK TRI,Reach-1,7
Up Type=0
Dn Type=3
Dn Slope=0.005

--- YOUNGS CREEK TRIBUTARY E.g01 (geometry) ---

Geom Title=Existing Conditions

River Reach=YOUNGS CREEK TRI,Reach-1
Reach XY= 30
      2256225.00     13767225.00      2256227.10     13767130.87
      2256235.86     13767115.36      2256266.90     13767081.07
      2256273.80     13767064.50      2256277.29     13766880.93
      2256285.91     13766865.33      2256317.19     13766830.92
      2256324.91     13766809.61      2256321.63     13766776.74
      2256283.19     13766731.07      2256276.24     13766714.50
      2256274.57     13766559.82      2256280.74     13766522.66
      2256314.11     13766484.63      2256322.64     13766469.02
      2256328.83     13766376.58      2256368.86     13766327.17
      2256383.16     13766268.95      2256469.46     13766177.42
      2256474.86     13766154.94      2256475.53     13766090.22
      2256482.86     13766068.83      2256669.48     13765877.43
      2256674.47     13765859.78      2256678.61     13765776.50
      2256691.46     13765758.25      2256769.67     13765677.51
      2256775.07     13765656.88      2256775.00     13765625.00

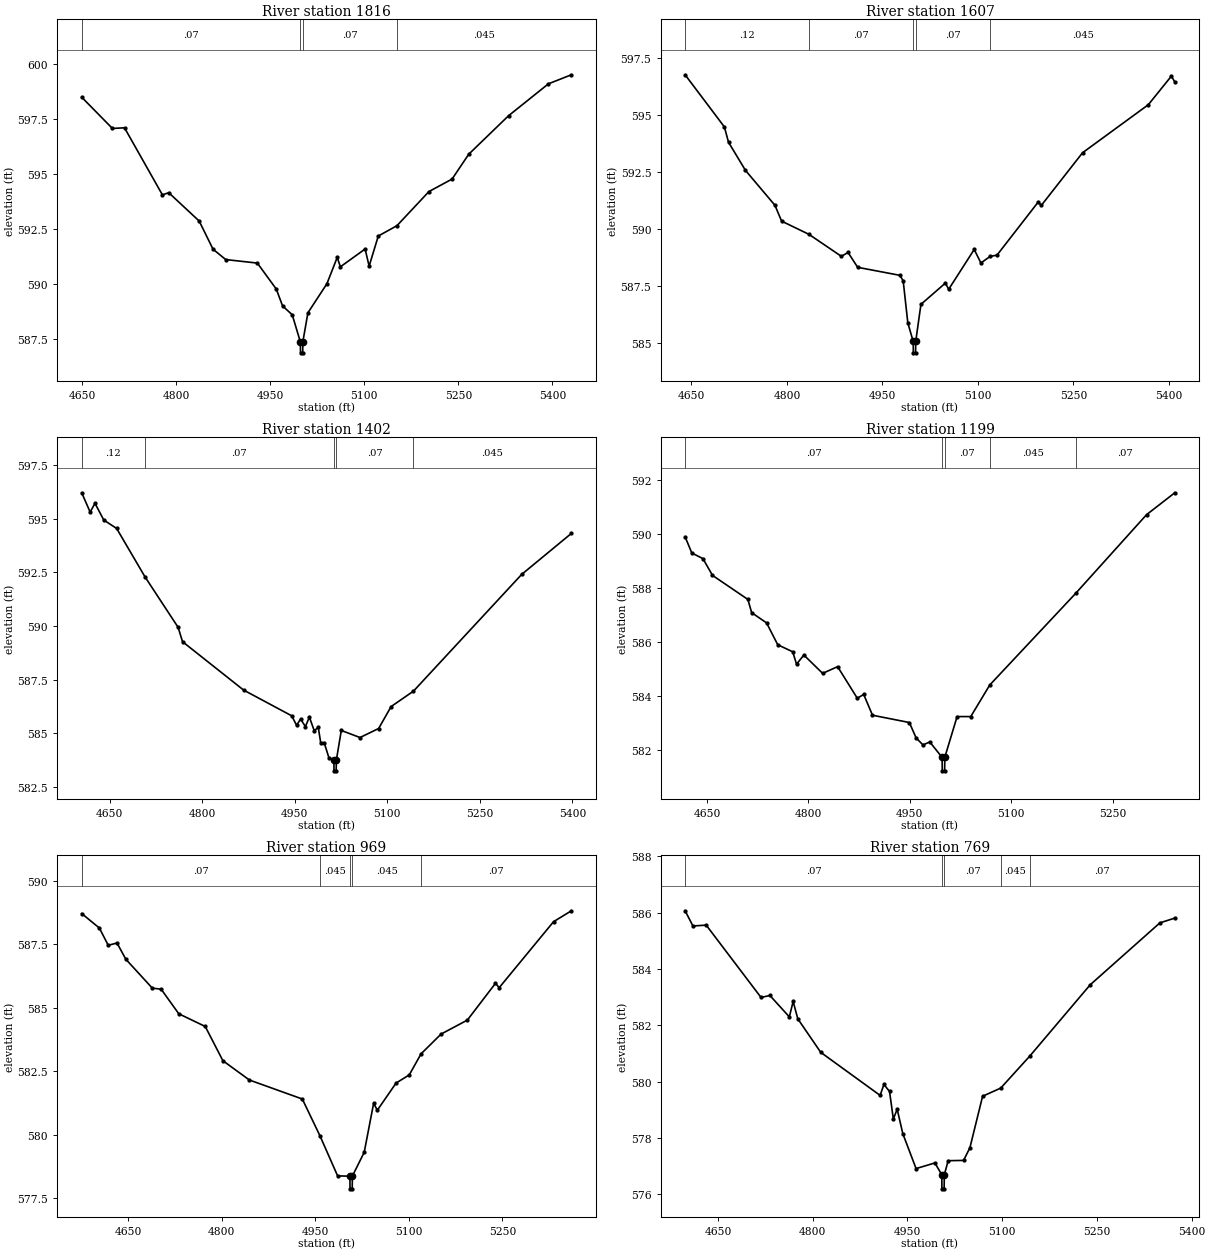
Type RM Length L Ch R = 1,1816,209,209,209
BEGIN DESCRIPTION:
J21818
END DESCRIPTION:
XS GIS Cut Line= 3
      2256572.61     13767256.16      2256134.23     13767195.40
      2255812.26     13767089.52
#Sta/Elev= 30
  4648.9  598.48  4697.9  597.06  4717.2  597.09  4777.7  594.04  4787.8  594.14
  4836.4  592.85  4858.5  591.57  4878.7  591.10  4929.2  590.94  4959.4  589.76
  4969.5  588.99  4984.9  588.59  4997.8  587.36  4998.1  586.86  5001.6  586.86
  5001.8  587.36  5009.9  588.68  5040.2  590.00  5056.7  591.20  5061.7  590.77
  5101.2  591.58  5107.6  590.80  5122.2  592.17  5152.0  592.64  5203.0  594.19
  5240.0  594.76  5266.6  595.89  5330.2  597.64  5393.8  599.09  5430.4  599.50
#Mann=4,-1,0
  4648.9    0.07       0  4997.8    0.05       0  5001.8    0.07       0
  5152.0   0.045       0
Bank Sta=4997.8,5001.8
Exp/Cntr=0.3,0.1

Type RM Length L Ch R = 1,1607,205,205,205
BEGIN DESCRIPTION:
J21817
END DESCRIPTION:
XS GIS Cut Line= 3
      2256620.32     13767117.27      2256168.95     13766982.73
      2255873.82     13766939.32
#Sta/Elev= 30
  4640.0  596.75  4701.7  594.47  4708.2  593.80  4734.8  592.57  4781.2  591.04
  4791.6  590.35  4834.7  589.77  4885.5  588.81  4896.0  588.98  4911.1  588.33
  4977.4  587.98  4982.6  587.74  4989.9  585.90  4998.3  585.09  4998.6  584.59
  5002.1  584.59  5002.3  585.09  5010.5  586.71  5048.9  587.64  5054.1  587.37
  5094.2  589.11  5104.7  588.52  5119.4  588.81  5129.9  588.86  5194.6  591.18
  5199.7  591.04  5264.4  593.34  5367.7  595.44  5403.9  596.69  5409.3  596.44
#Mann=5,-1,0
  4640.0    0.12       0  4834.7    0.07       0  4998.3    0.05       0
  5002.3    0.07       0  5119.4   0.045       0
Bank Sta=4998.3,5002.3
Exp/Cntr=0.3,0.1

Type RM Length L Ch R = 1,1402,203,203,203
BEGIN DESCRIPTION:
YOUNGS CREEK TRIBUTARY E 3.0
END DESCRIPTION:
XS GIS Cut Line= 3
      2256625.00     13767075.00      2256325.00     13766825.00
      2255925.03     13766875.00
#Sta/Elev= 30
  4604.9  596.20  4618.6  595.30  4626.4  595.71  4640.7  594.93  4661.5  594.54
  4707.4  592.29  4761.1  589.94  4768.3  589.27  4867.2  587.02  4945.3  585.82
  4953.1  585.38  4959.6  585.67  4967.4  585.32  4973.9  585.76  4981.7  585.13
  4988.3  585.28  4992.2  584.57  4997.9  584.57  5005.5  583.87  5013.6  583.76
  5013.8  583.26  5017.3  583.26  5017.6  583.76  5025.6  585.14  5055.9  584.81
  5086.1  585.23  5106.3  586.25  5142.6  586.97  5317.9  592.40  5398.5  594.31
#Mann=5,-1,0
  4604.9    0.12       0  4707.4    0.07       0  5013.6    0.05       0
  5017.6    0.07       0  5142.6   0.045       0
Bank Sta=5013.6,5017.6
Exp/Cntr=0.3,0.1

Type RM Length L Ch R = 1,1199,230,230,230
BEGIN DESCRIPTION:
J21816
END DESCRIPTION:
XS GIS Cut Line= 4
      2256620.96     13766793.43      2256340.95     13766648.16
      2256202.00     13766629.21      2255945.14     13766707.11
#Sta/Elev= 30
  4617.8  589.91  4627.7  589.31  4644.2  589.10  4658.3  588.48  4710.6  587.59
  4716.2  587.10  4738.3  586.72  4754.8  585.91  4776.9  585.65  4782.6  585.19
  4793.4  585.53  4821.2  584.85  4843.3  585.10  4872.4  583.93  4881.9  584.07
  4894.9  583.30  4949.4  583.03  4959.4  582.46  4969.5  582.20  4979.6  582.31
  4997.8  581.74  4998.1  581.24  5001.6  581.24  5001.8  581.74  5020.0  583.25
  5040.2  583.25  5068.3  584.42  5195.2  587.81  5300.2  590.73  5341.9  591.54
#Mann=5,-1,0
  4617.8    0.07       0  4997.8    0.05       0  5001.8    0.07       0
  5068.3   0.045       0  5195.2    0.07       0
Bank Sta=4997.8,5001.8
Exp/Cntr=0.3,0.1

Type RM Length L Ch R = 1,969,200,200,200
BEGIN DESCRIPTION:
YOUNGS CREEK TRIBUTARY E 2.0
END DESCRIPTION:
XS GIS Cut Line= 3
      2256625.02     13766725.02      2256325.00     13766425.00
      2256024.96     13766625.03
#Sta/Elev= 30
  4575.7  588.71  4604.0  588.14  4618.2  587.46  4632.3  587.55  4646.4  586.91
  4688.9  585.77  4703.0  585.73  4731.3  584.76  4773.7  584.26  4802.0  582.91
  4844.4  582.15  4929.3  581.40  4957.4  579.96  4985.9  578.37  5005.5  578.36
  5005.8  577.86  5009.3  577.86  5009.5  578.36  5028.5  579.30  5043.6  581.23
  5049.6  580.96  5079.6  582.03  5100.7  582.35  5119.6  583.18  5151.7  583.96
  5193.8  584.51  5238.9  585.96  5244.9  585.79  5332.0  588.39  5360.6  588.82
#Mann=5,-1,0
  4575.7    0.07       0  4957.4   0.045       0  5005.5   0.045       0
  5009.5   0.045       0  5119.6    0.07       0
Bank Sta=5005.5,5009.5
Exp/Cntr=0.3,0.1

Type RM Length L Ch R = 1,769,271,271,271
BEGIN DESCRIPTION:
J21815
END DESCRIPTION:
XS GIS Cut Line= 3
      2256732.49     13766475.50      2256383.05     13766237.63
      2256031.43     13766214.47
#Sta/Elev= 30
  4598.1  586.07  4610.5  585.53  4631.5  585.56  4718.3  582.99  4732.3  583.06
  4763.1  582.30  4769.1  582.85  4776.5  582.23  4812.8  581.04  4906.8  579.51
  4912.8  579.90  4921.7  579.65  4927.7  578.67  4933.8  579.02  4942.7  578.15
  4963.7  576.91  4993.5  577.11  5004.4  576.69  5004.6  576.19  5008.1  576.19
  5008.4  576.69  5014.5  577.19  5038.9  577.20  5048.9  577.65  5069.0  579.48
  5097.7  579.77  5143.8  580.91  5239.3  583.44  5349.6  585.64  5373.2  585.81
#Mann=5,-1,0
  4598.1    0.07       0  5004.4    0.05       0  5008.4    0.07       0
  5097.7   0.045       0  5143.8    0.07       0
Bank Sta=5004.4,5008.4
Exp/Cntr=0.3,0.1

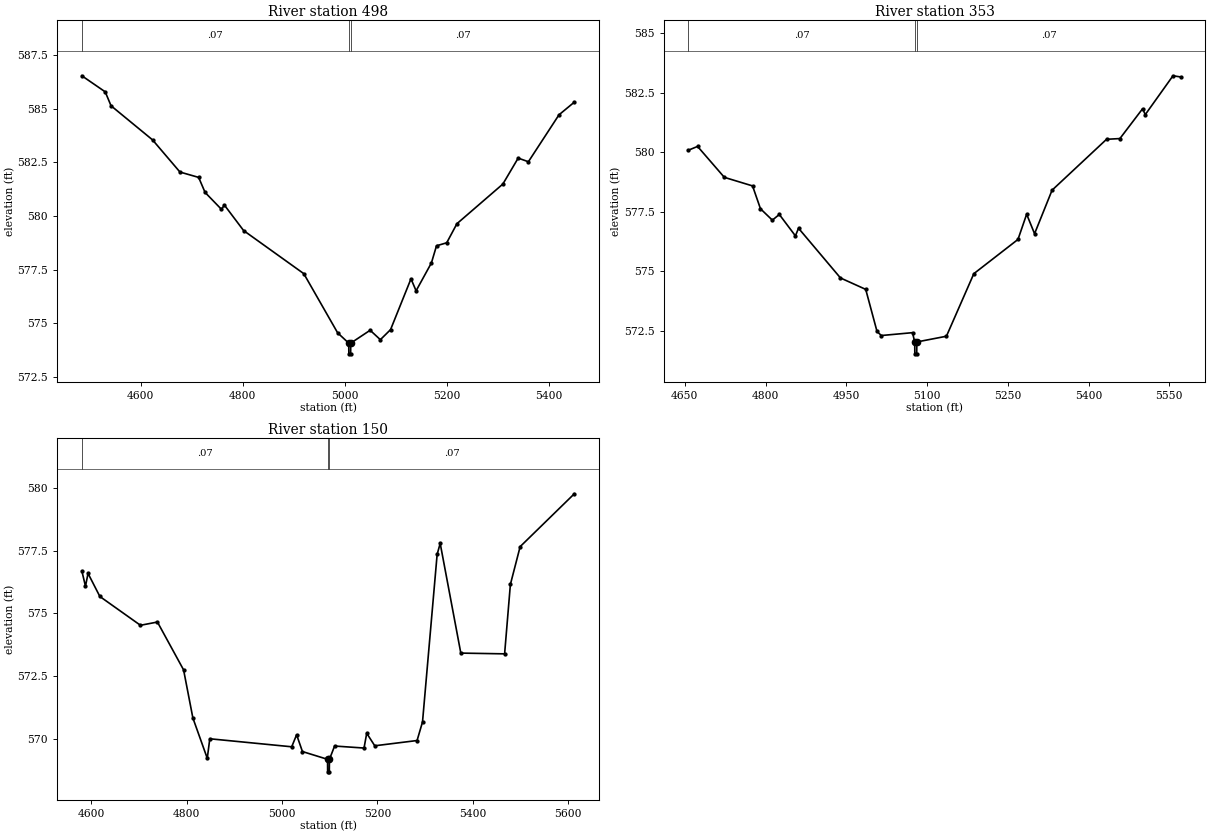
Type RM Length L Ch R = 1,498,145,145,145
BEGIN DESCRIPTION:
YOUNGS CREEK TRIBUTARY E 1.0
END DESCRIPTION:
XS GIS Cut Line= 3
      2256775.02     13766475.04      2256525.00     13766025.00
      2256075.03     13766025.00
#Sta/Elev= 30
  4484.8  586.54  4530.6  585.79  4542.0  585.14  4623.3  583.55  4677.0  582.05
  4713.6  581.80  4726.2  581.10  4758.3  580.31  4764.0  580.51  4801.7  579.32
  4919.6  577.31  4985.9  574.55  5007.6  574.07  5007.9  573.57  5011.4  573.57
  5011.6  574.07  5049.6  574.67  5069.6  574.23  5089.6  574.70  5129.6  577.07
  5139.6  576.51  5169.6  577.81  5179.6  578.61  5199.6  578.75  5219.6  579.64
  5309.6  581.49  5339.6  582.70  5359.6  582.53  5419.6  584.72  5449.6  585.31
#Mann=3,-1,0
  4484.8    0.07       0  5007.6    0.05       0  5011.6    0.07       0
Bank Sta=5007.6,5011.6
Exp/Cntr=0.3,0.1

Type RM Length L Ch R = 1,353,203,203,203
BEGIN DESCRIPTION:
J21814
END DESCRIPTION:
XS GIS Cut Line= 4
      2256823.05     13766199.74      2256675.68     13765955.53
      2256460.95     13765810.26      2256100.93     13765896.58
#Sta/Elev= 30
  4656.6  580.08  4673.8  580.24  4723.5  578.94  4775.9  578.58  4790.6  577.62
  4812.7  577.14  4825.6  577.38  4855.5  576.48  4861.3  576.80  4939.2  574.71
  4986.1  574.23  5007.1  572.46  5015.1  572.29  5073.0  572.41  5077.1  572.02
  5077.3  571.52  5080.8  571.52  5081.1  572.02  5136.0  572.26  5186.9  574.89
  5268.9  576.33  5285.0  577.39  5299.7  576.57  5332.2  578.40  5433.4  580.54
  5458.2  580.57  5500.2  581.82  5505.4  581.58  5556.8  583.21  5571.3  583.16
#Mann=3,-1,0
  4656.6    0.07       0  5077.1    0.05       0  5081.1    0.07       0
Bank Sta=5077.1,5081.1
Exp/Cntr=0.3,0.1

Type RM Length L Ch R = 1,150,0,0,0
BEGIN DESCRIPTION:
J21813
END DESCRIPTION:
XS GIS Cut Line= 4
      2256924.10     13766073.40      2256823.05     13765806.05
      2256471.47     13765633.42      2256124.08     13765711.32
#Sta/Elev= 30
  4579.9  576.69  4587.5  576.08  4592.9  576.59  4617.7  575.67  4702.9  574.52
  4738.5  574.65  4793.4  572.74  4812.9  570.82  4843.1  569.21  4848.4  569.99
  5020.3  569.67  5030.6  570.15  5042.8  569.48  5095.5  569.17  5095.7  568.67
  5099.2  568.67  5099.5  569.17  5110.3  569.70  5172.1  569.62  5177.7  570.21
  5194.6  569.71  5283.4  569.92  5294.8  570.66  5325.5  577.35  5331.9  577.79
  5375.2  573.41  5467.1  573.38  5479.2  576.15  5499.7  577.66  5613.4  579.77
#Mann=3,-1,0
  4579.9    0.07       0  5095.5    0.05       0  5099.5    0.07       0
Bank Sta=5095.5,5099.5
Exp/Cntr=0.3,0.1

Chan Stop Cuts=-1