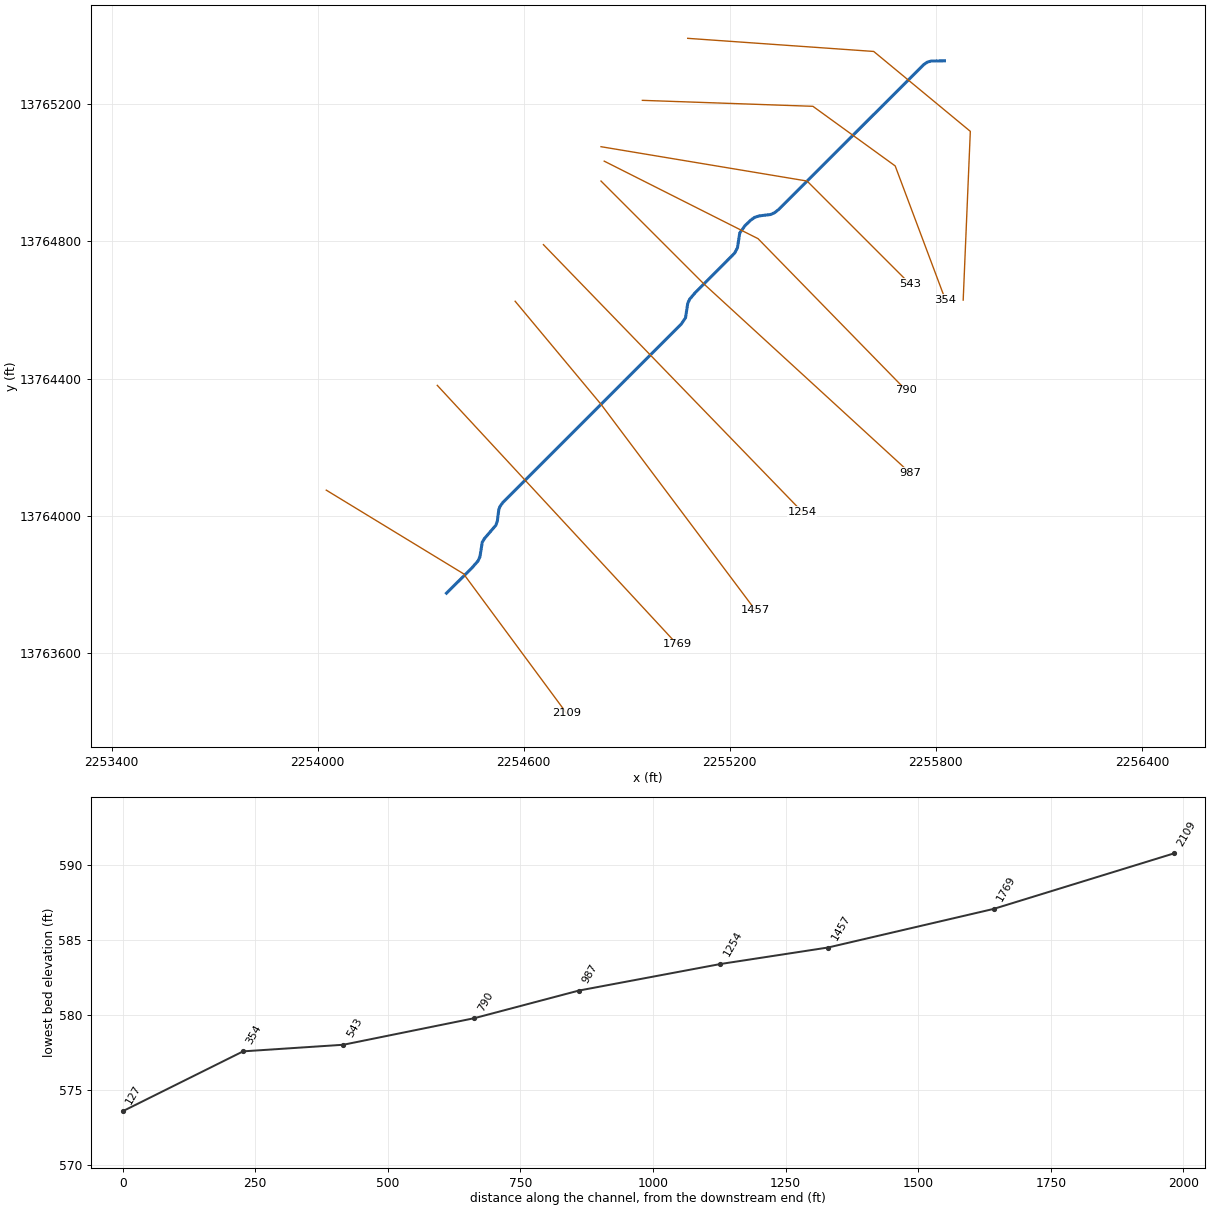
--- YOUNGS CREEK TRIBUTARY G.prj (project) ---

Proj Title=YOUNGS CREEK TRIBUTARY G Base Level Engineering
Current Plan=p01
Default Exp/Contr=0.3,0.1
English Units
Geom File=g01
Flow File=f01
Plan File=p01
BEGIN DESCRIPTION:
YOUNGS CREEK TRIBUTARY G
END DESCRIPTION:

--- YOUNGS CREEK TRIBUTARY G.p01 (plan) ---

Plan Title=Multiple Run
Short Identifier=Multiple
Geom File=g01
Flow File=f01
Subcritical Flow
K Sum by GR= 0
Std Step Tol= 0.01
Critical Tol= 0.01
Num of Std Step Trials= 20
Max Error Tol= 0.3
Flow Tol Ratio= 0.001
Split Flow NTrial= 30
Split Flow Tol= 0.02
Split Flow Ratio= 0.02
Log Output Level= 0
Friction Slope Method= 1
Unsteady Friction Slope Method= 2
Unsteady Bridges Friction Slope Method= 1
Parabolic Critical Depth
Global Vel Dist=  1 , 1 , 1
Global Log Level= 0
CheckData=True
Encroach Param= -1, 0, 0, 0
BEGIN DESCRIPTION:
Multiple Run
END DESCRIPTION:

--- YOUNGS CREEK TRIBUTARY G.f01 (steady flow) ---

Flow Title=Multiple
Number of Profiles=7
Profile Names=10-year,25-year,50-year,1pct_min,100-year,1pct_plu,500-year
River Rch & RM= YOUNGS CREEK TRI,Reach-1,2109
     170     251     317     196     391     780     583
Boundary for River Rch & Prof#=YOUNGS CREEK TRI,Reach-1,1
Up Type=0
Dn Type=3
Dn Slope=0.005
Boundary for River Rch & Prof#=YOUNGS CREEK TRI,Reach-1,2
Up Type=0
Dn Type=3
Dn Slope=0.005
Boundary for River Rch & Prof#=YOUNGS CREEK TRI,Reach-1,3
Up Type=0
Dn Type=3
Dn Slope=0.005
Boundary for River Rch & Prof#=YOUNGS CREEK TRI,Reach-1,4
Up Type=0
Dn Type=3
Dn Slope=0.005
Boundary for River Rch & Prof#=YOUNGS CREEK TRI,Reach-1,5
Up Type=0
Dn Type=3
Dn Slope=0.005
Boundary for River Rch & Prof#=YOUNGS CREEK TRI,Reach-1,6
Up Type=0
Dn Type=3
Dn Slope=0.005
Boundary for River Rch & Prof#=YOUNGS CREEK TRI,Reach-1,7
Up Type=0
Dn Type=3
Dn Slope=0.005

--- YOUNGS CREEK TRIBUTARY G.g01 (geometry) ---

Geom Title=Existing Conditions

River Reach=YOUNGS CREEK TRI,Reach-1
Reach XY= 30
      2254375.00     13763775.00      2254448.80     13763848.14
      2254466.91     13763868.92      2254472.52     13763881.03
      2254479.18     13763923.27      2254486.09     13763934.55
      2254518.90     13763972.81      2254523.30     13763985.70
      2254527.50     13764018.96      2254530.83     13764027.30
      2254538.62     13764038.21      2255058.35     13764558.33
      2255071.02     13764576.65      2255077.54     13764618.95
      2255083.16     13764631.05      2255098.02     13764648.46
      2255214.21     13764765.34      2255222.45     13764781.09
      2255228.89     13764823.57      2255244.63     13764845.47
      2255261.44     13764861.51      2255272.46     13764869.25
      2255285.49     13764873.51      2255318.91     13764877.55
      2255331.03     13764883.17      2255341.66     13764891.66
      2255765.21     13765314.49      2255776.36     13765321.73
      2255786.84     13765324.41      2255825.00     13765325.00

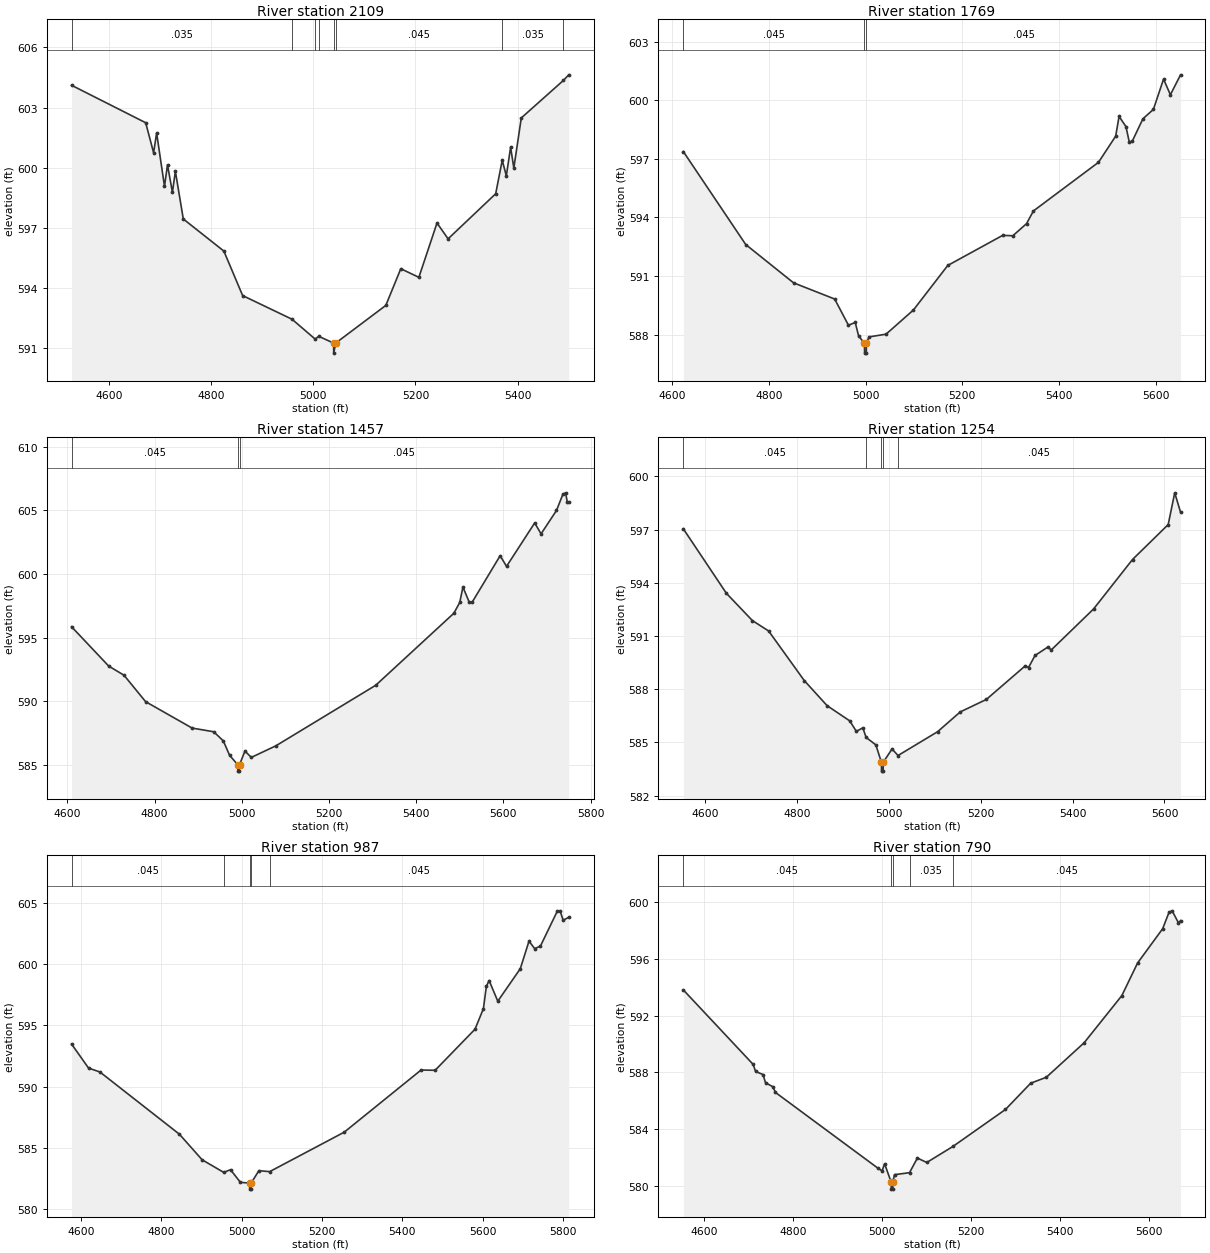
Type RM Length L Ch R = 1,2109,340,340,340
BEGIN DESCRIPTION:
YOUNGS CREEK TRIBUTARY G 4.0
END DESCRIPTION:
XS GIS Cut Line= 3
      2254025.02     13764074.99      2254424.65     13763831.50
      2254725.01     13763424.99
#Sta/Elev= 30
  4526.8  604.11  4672.0  602.24  4687.5  600.74  4693.4  601.73  4708.8  599.07
  4714.7  600.14  4724.3  598.77  4730.1  599.82  4745.6  597.44  4825.0  595.84
  4861.8  593.62  4958.5  592.44  5003.8  591.45  5010.7  591.59  5039.9  591.25
  5040.1  590.75  5043.9  591.25  5142.1  593.13  5171.4  594.96  5206.8  594.53
  5242.3  597.24  5264.0  596.45  5357.2  598.70  5370.0  600.37  5378.0  599.59
  5386.4  601.02  5392.7  599.98  5407.3  602.48  5489.7  604.35  5500.2  604.63
#Mann=8,-1,0
  4526.8   0.035       0  4958.5   0.045       0  5003.8   0.035       0
  5010.7   0.045       0  5039.9   0.045       0  5043.9   0.045       0
  5370.0   0.035       0  5489.7   0.063       0
Bank Sta=5039.9,5043.9
Exp/Cntr=0.3,0.1

Type RM Length L Ch R = 1,1769,312,312,312
BEGIN DESCRIPTION:
J21823
END DESCRIPTION:
XS GIS Cut Line= 2
      2254348.26     13764380.11      2255046.15     13763626.67
#Sta/Elev= 30
  4623.7  597.37  4752.6  592.61  4851.3  590.65  4936.3  589.82  4964.7  588.48
  4978.8  588.62  4985.7  587.93  4997.8  587.55  4998.1  587.05  5001.6  587.05
  5001.8  587.55  5007.2  587.88  5042.4  588.02  5099.0  589.26  5169.9  591.54
  5283.3  593.08  5304.3  593.06  5332.6  593.68  5346.8  594.33  5481.2  596.82
  5516.7  598.16  5523.7  599.17  5537.9  598.65  5544.7  597.87  5550.7  597.89
  5573.0  599.05  5594.6  599.53  5615.6  601.08  5629.7  600.28  5650.7  601.30
#Mann=3,-1,0
  4623.7   0.045       0  4997.8   0.045       0  5001.8   0.045       0
Bank Sta=4997.8,5001.8
Exp/Cntr=0.3,0.1

Type RM Length L Ch R = 1,1457,203,203,203
BEGIN DESCRIPTION:
YOUNGS CREEK TRIBUTARY G 3.0
END DESCRIPTION:
XS GIS Cut Line= 3
      2254575.01     13764624.99      2254825.00     13764325.00
      2255275.00     13763725.00
#Sta/Elev= 30
  4609.5  595.85  4694.8  592.75  4729.9  592.03  4779.4  589.95  4886.1  587.87
  4935.6  587.58  4957.7  586.86  4972.0  585.73  4990.8  584.98  4991.1  584.48
  4994.6  584.48  4994.8  584.98  5007.3  586.06  5021.9  585.56  5078.1  586.47
  5307.3  591.24  5486.5  596.91  5500.0  597.76  5507.3  598.97  5521.9  597.77
  5528.1  597.76  5592.7  601.44  5607.3  600.60  5671.9  604.02  5686.5  603.16
  5721.9  605.00  5736.5  606.27  5742.7  606.39  5746.9  605.63  5750.0  605.63
#Mann=3,-1,0
  4609.5   0.045       0  4990.8   0.045       0  4994.8   0.045       0
Bank Sta=4990.8,4994.8
Exp/Cntr=0.3,0.1

Type RM Length L Ch R = 1,1254,267,267,267
BEGIN DESCRIPTION:
J21822
END DESCRIPTION:
XS GIS Cut Line= 2
      2254657.32     13764789.80      2255410.38     13764012.45
#Sta/Elev= 30
  4552.7  597.04  4646.3  593.41  4702.9  591.87  4738.4  591.28  4816.1  588.48
  4865.7  587.07  4915.1  586.21  4929.3  585.62  4943.4  585.82  4950.6  585.28
  4971.7  584.86  4983.9  583.88  4984.1  583.38  4987.6  583.38  4987.9  583.88
  5007.0  584.63  5020.0  584.26  5106.0  585.60  5155.6  586.72  5212.2  587.42
  5297.1  589.32  5304.1  589.22  5318.2  589.90  5346.5  590.38  5353.5  590.21
  5445.6  592.52  5530.4  595.31  5608.1  597.28  5622.3  599.07  5635.0  597.98
#Mann=5,-1,0
  4552.7   0.045       0  4950.6   0.035       0  4983.9   0.035       0
  4987.9   0.035       0  5020.0   0.045       0
Bank Sta=4983.9,4987.9
Exp/Cntr=0.3,0.1

Type RM Length L Ch R = 1,987,197,197,197
BEGIN DESCRIPTION:
YOUNGS CREEK TRIBUTARY G 2.0
END DESCRIPTION:
XS GIS Cut Line= 3
      2254825.03     13764974.97      2255125.00     13764675.00
      2255725.02     13764124.98
#Sta/Elev= 30
  4576.0  593.48  4618.4  591.51  4646.7  591.19  4844.7  586.10  4901.2  584.01
  4955.0  582.98  4971.9  583.20  4996.7  582.16  5019.5  582.11  5019.8  581.61
  5023.3  581.61  5023.5  582.11  5042.5  583.12  5069.4  583.04  5255.2  586.27
  5446.4  591.35  5481.5  591.33  5580.8  594.69  5601.7  596.37  5609.1  598.20
  5615.9  598.67  5637.5  596.98  5693.6  599.64  5715.2  601.89  5729.4  601.28
  5743.6  601.48  5786.1  604.37  5792.9  604.34  5800.3  603.60  5814.2  603.84
#Mann=5,-1,0
  4576.0   0.045       0  4955.0   0.035       0  5019.5   0.035       0
  5023.5   0.035       0  5069.4   0.045       0
Bank Sta=5019.5,5023.5
Exp/Cntr=0.3,0.1

Type RM Length L Ch R = 1,790,247,247,247
BEGIN DESCRIPTION:
J21821
END DESCRIPTION:
XS GIS Cut Line= 3
      2254834.39     13765032.88      2255282.29     13764807.19
      2255712.88     13764366.19
#Sta/Elev= 30
  4553.2  593.82  4710.1  588.57  4715.7  588.07  4732.4  587.85  4738.0  587.27
  4754.7  586.99  4760.3  586.59  4990.6  581.25  5000.1  581.06  5005.7  581.56
  5020.4  580.27  5020.7  579.77  5024.2  579.77  5024.4  580.27  5028.0  580.79
  5061.7  580.93  5079.4  581.96  5100.6  581.65  5159.8  582.79  5277.5  585.39
  5334.1  587.24  5369.3  587.66  5454.2  590.09  5539.1  593.42  5574.5  595.72
  5630.9  598.14  5645.1  599.29  5652.2  599.40  5666.4  598.55  5671.1  598.71
#Mann=5,-1,0
  4553.2   0.045       0  5020.4   0.045       0  5024.4   0.045       0
  5061.7   0.035       0  5159.8   0.045       0
Bank Sta=5020.4,5024.4
Exp/Cntr=0.3,0.1

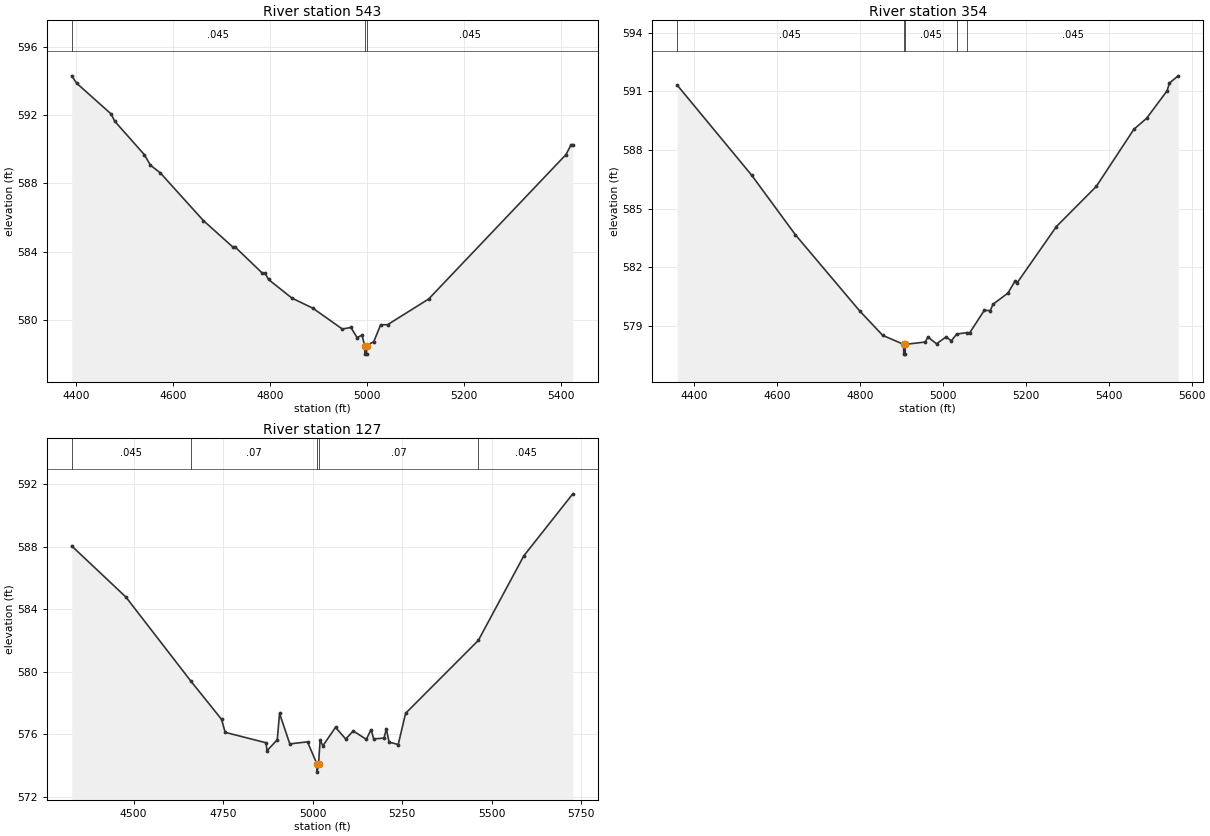
Type RM Length L Ch R = 1,543,189,189,189
BEGIN DESCRIPTION:
YOUNGS CREEK TRIBUTARY G 1.0
END DESCRIPTION:
XS GIS Cut Line= 3
      2254825.00     13765075.00      2255425.00     13764975.00
      2255724.97     13764675.03
#Sta/Elev= 30
  4391.7  594.29  4401.8  593.86  4472.8  592.06  4480.4  591.63  4541.2  589.68
  4553.9  589.06  4574.2  588.61  4662.9  585.82  4723.7  584.27  4728.8  584.26
  4784.5  582.74  4789.6  582.76  4797.2  582.37  4845.4  581.28  4888.5  580.69
  4949.3  579.47  4967.0  579.56  4979.7  578.97  4989.8  579.11  4995.4  578.50
  4995.7  578.00  4999.2  578.00  4999.4  578.50  5014.1  578.73  5028.3  579.72
  5042.4  579.72  5127.3  581.23  5410.1  589.68  5420.7  590.26  5424.2  590.26
#Mann=3,-1,0
  4391.7   0.045       0  4995.4   0.045       0  4999.4   0.045       0
Bank Sta=4995.4,4999.4
Exp/Cntr=0.3,0.1

Type RM Length L Ch R = 1,354,227,227,227
BEGIN DESCRIPTION:
J21820
END DESCRIPTION:
XS GIS Cut Line= 4
      2254945.46     13765209.97      2255442.01     13765192.61
      2255681.60     13765019.00      2255827.44     13764630.08
#Sta/Elev= 30
  4359.5  591.33  4539.1  586.72  4644.6  583.67  4799.3  579.78  4855.3  578.52
  4905.6  578.06  4905.9  577.56  4909.4  577.56  4909.6  578.06  4957.9  578.18
  4964.0  578.44  4984.9  578.09  5008.1  578.44  5020.6  578.24  5033.7  578.59
  5058.4  578.66  5064.6  578.64  5100.1  579.80  5114.8  579.79  5121.0  580.11
  5157.0  580.68  5174.3  581.30  5179.7  581.22  5274.0  584.09  5370.1  586.14
  5460.9  589.07  5491.2  589.62  5541.0  591.04  5546.4  591.43  5567.6  591.80
#Mann=5,-1,0
  4359.5   0.045       0  4905.6   0.045       0  4909.6   0.045       0
  5033.7    0.07       0  5058.4   0.045       0
Bank Sta=4905.6,4909.6
Exp/Cntr=0.3,0.1

Type RM Length L Ch R = 1,127,0,0,0
BEGIN DESCRIPTION:
J21819
END DESCRIPTION:
XS GIS Cut Line= 4
      2255077.46     13765390.53      2255619.10     13765352.33
      2255900.35     13765119.69      2255879.58     13764628.31
#Sta/Elev= 30
  4327.0  588.06  4478.3  584.79  4660.2  579.39  4745.6  576.95  4755.6  576.12
  4870.0  575.45  4872.4  574.94  4901.1  575.64  4907.6  577.33  4936.2  575.38
  4985.7  575.51  5012.4  574.07  5012.6  573.57  5016.4  574.07  5020.9  575.61
  5028.7  575.26  5063.9  576.44  5092.5  575.69  5113.4  576.21  5149.9  575.67
  5163.2  576.29  5170.7  575.70  5199.4  575.75  5205.8  576.33  5213.7  575.49
  5239.1  575.34  5259.7  577.34  5462.9  582.01  5590.0  587.43  5726.8  591.40
#Mann=5,-1,0
  4327.0   0.045       0  4660.2    0.07       0  5012.4    0.05       0
  5016.4    0.07       0  5462.9   0.045       0
Bank Sta=5012.4,5016.4
Exp/Cntr=0.3,0.1

Chan Stop Cuts=-1