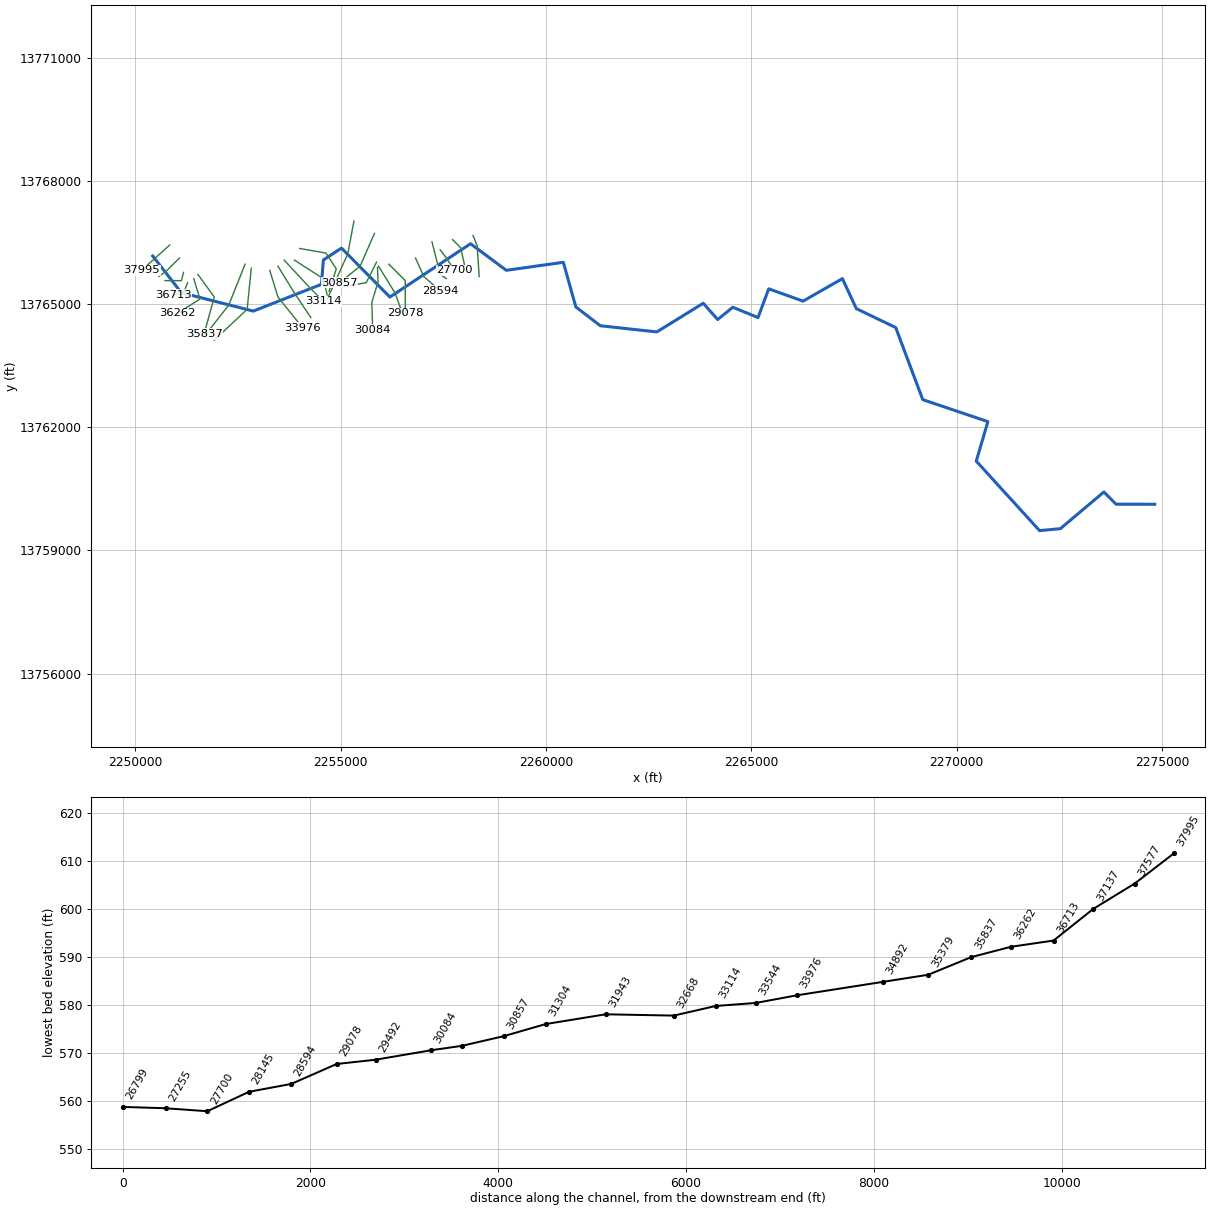
--- YOUNGS CREEK.prj (project) ---

Proj Title=YOUNGS CREEK Base Level Engineering
Current Plan=p01
Default Exp/Contr=0.3,0.1
English Units
Geom File=g01
Flow File=f01
Plan File=p01
Y Axis Title=Elevation
X Axis Title(PF)=Main Channel Distance
X Axis Title(XS)=Station
BEGIN DESCRIPTION:
YOUNGS CREEK
END DESCRIPTION:
DSS Export Rating Curves= 0
DSS Export Rating Curve Sorted= 0
DSS Export Volume Flow Curves= 0
DXF OffsetX= 0
DXF OffsetY= 0
DXF ScaleX= 1
DXF ScaleY= 10

--- YOUNGS CREEK.p01 (plan) ---

Plan Title=Multiple Run
Program Version=4.10
Short Identifier=Multiple
Geom File=g01
Flow File=f01
Subcritical Flow
K Sum by GR= 0
Std Step Tol= 0.01
Critical Tol= 0.01
Num of Std Step Trials= 20
Max Error Tol= 0.3
Flow Tol Ratio= 0.001
Split Flow NTrial= 30
Split Flow Tol= 0.02
Split Flow Ratio= 0.02
Log Output Level= 0
Friction Slope Method= 1
Unsteady Friction Slope Method= 2
Unsteady Bridges Friction Slope Method= 1
Parabolic Critical Depth
Global Vel Dist= 1 , 1 , 1
Global Log Level= 0
CheckData=True
Encroach Param=-1 ,0,0, 0
BEGIN DESCRIPTION:
Multiple Run
END DESCRIPTION:
Computation Interval=1HOUR
Output Interval=1HOUR
Run HTab= 0
Run UNet= 0
Run PostProcess= 0
Run WQNet= 0
UNET Theta= 1
UNET Theta Warmup= 1
UNET ZTol= 0.02
UNET ZSATol= 0.05
UNET MxIter= 20
UNET MaxInSteps= 0
UNET DtIC= 0
UNET DtMin= 0
UNET MaxCRTS= 20
UNET WFStab= 2
UNET SFStab= 1
UNET WFX= 1
UNET SFX= 1
UNET DSS MLevel= 4
UNET DZMax Abort= 100
UNET Convert EG Bridges= 0
UNET Use Existing IB Tables=-1
UNET Froude Reduction=False
UNET Froude Limit= 1
UNET Froude Power= 10
UNET Time Slicing=0,0, 5
UNET Junction Losses=0
Instantaneous Interval=1HOUR
Write IC File= 0
Write IC File at Sim End=0
Echo Input=False
Echo Parameters=False
Echo Output=False
Write Detailed= 0
WQ AD Non Conservative
WQ ULTIMATE=-1
WQ Max Comp Step=1HOUR
WQ Output Interval=15MIN
WQ Output Selected Increments= 0
WQ Output face flow=0
WQ Output face velocity=0
WQ Output face area=0
WQ Output face dispersion=0
WQ Output cell volume=0
WQ Output cell surface area=0
WQ Output cell continuity=0
WQ Output cumulative cell continuity=0
WQ Output face conc=0
WQ Output face dconc_dx=0
WQ Output face courant=0
WQ Output face peclet=0
WQ Output face adv mass=0
WQ Output face disp mass=0
WQ Output cell mass=0
WQ Output cell source sink temp=0
WQ Output cell source sink nsm=0
WQ Output MaxMinRange=-1
WQ Daily Max Min Mean=-1
WQ Daily Range=0
WQ Daily Time=0
WQ Create Restart=0
WQ Fixed Restart=0
WQ System Summary=0
WQ Use Fixed Temperature=0
Sorting and Armoring Iterations= 10
XS Update Threshold= 0.02
Hydraulics Update Threshold= 0.02
Energy Slope Method= 1
Volume Change Method= 0
XS Weighting Method= 0
Number of US Weighted Cross Sections= 1
Number of DS Weighted Cross Sections= 1
Upstream XS Weight=0.25
Main XS Weight=0.5
Downstream XS Weight=0.25
Number of DS XS's Weighted with US Boundary= 1
Upstream Boundary Weight= 1
Weight of XSs Associated with US Boundary= 0
Number of US XS's Weighted with DS Boundary= 1
Downstream Boundary Weight= 0.5
Weight of XSs Associated with DS Boundary= 0.5
Sediment Output Level= 4
Mass or Volume Output= 0
Output Increment Type= 1
Profile and TS Output Increment= 10
XS Output Flag= 0
XS Output Increment= 10
Disregard all LS=0
Disregard all Conn=0
Disregard all Breaches=0
Disregard all Pumps=0

--- YOUNGS CREEK.f01 (steady flow) ---

Flow Title=Multiple
Program Version=4.10
Number of Profiles= 7
Profile Names=10-year,25-year,50-year,1pct_min,100-year,1pct_plu,500-year
River Rch & RM=YOUNGS CREEK,Reach-1         ,37995
     534     854    1141     738    1473    2940    2430
River Rch & RM=YOUNGS CREEK,Reach-1         ,35837
     806    1323    1797    1181    2357    4703    1797
River Rch & RM=YOUNGS CREEK,Reach-1         ,35379
    1195    1984    2716    1794    3580    7143    6163
River Rch & RM=YOUNGS CREEK,Reach-1         ,31304
    1221    2023    2764    1822    3636    7255    6233
River Rch & RM=YOUNGS CREEK,Reach-1         ,30084
    1298    2158    2954    1951    3894    7769    6702
River Rch & RM=YOUNGS CREEK,Reach-1         ,28594
    1447    2420    3325    2204    4398    8776    7626
River Rch & RM=YOUNGS CREEK,Reach-1         ,26323
    1575    2642    3639    2416    4821    9619    8387
River Rch & RM=YOUNGS CREEK,Reach-1         ,24885
    1635    2744    3781    2511    5011    9998    8724
River Rch & RM=YOUNGS CREEK,Reach-1         ,21714
    2812    4823    6743    4538    9054   18064   16177
River Rch & RM=YOUNGS CREEK,Reach-1         ,18010
    2804    4795    6690    4492    8962   17881   15941
River Rch & RM=YOUNGS CREEK,Reach-1         ,14427
    3285    5649    7913    5330   10635   21220   19046
River Rch & RM=YOUNGS CREEK,Reach-1         ,8697
    3773    6510    9137    6166   12302   24546   22103
Boundary for River Rch & Prof#=YOUNGS CREEK,Reach-1         , 1
Up Type= 0
Dn Type= 3
Dn Slope=0.008
Boundary for River Rch & Prof#=YOUNGS CREEK,Reach-1         , 2
Up Type= 0
Dn Type= 3
Dn Slope=0.008
Boundary for River Rch & Prof#=YOUNGS CREEK,Reach-1         , 3
Up Type= 0
Dn Type= 3
Dn Slope=0.008
Boundary for River Rch & Prof#=YOUNGS CREEK,Reach-1         , 4
Up Type= 0
Dn Type= 3
Dn Slope=0.008
Boundary for River Rch & Prof#=YOUNGS CREEK,Reach-1         , 5
Up Type= 0
Dn Type= 3
Dn Slope=0.008
Boundary for River Rch & Prof#=YOUNGS CREEK,Reach-1         , 6
Up Type= 0
Dn Type= 3
Dn Slope=0.008
Boundary for River Rch & Prof#=YOUNGS CREEK,Reach-1         , 7
Up Type= 0
Dn Type= 3
Dn Slope=0.008
DSS Import GetInterval= 0
DSS Import GetPeak= 0
DSS Import FillOption= 0

--- YOUNGS CREEK.g01 (geometry) ---

Geom Title=Existing Conditions
Program Version=4.10

River Reach=YOUNGS CREEK    ,Reach-1
Reach XY= 30
        2250425.       13766175.      2251122.53     13765280.45
      2252875.11     13764832.31      2254535.05     13765485.63
       2254580.4     13766077.43      2255021.97     13766367.21
      2256200.12      13765174.7      2258164.49      13766473.8
      2259035.27     13765825.96      2260423.52     13766021.39
      2260728.35      13764933.1        2261325.       13764475.
      2262699.88     13764324.71      2263830.85     13765022.96
      2264180.65     13764626.96      2264549.88      13764925.3
      2265164.74     13764675.98        2265425.       13765375.
      2266259.98     13765075.32      2267219.07     13765622.76
      2267558.29     13764891.63      2268517.19     13764431.19
        2269175.       13762675.       2270761.5     13762138.68
      2270478.12     13761176.63      2272018.94     13759483.14
       2272527.3     13759530.83      2273585.76      13760424.3
      2273880.96     13760127.14        2274825.       13760125.

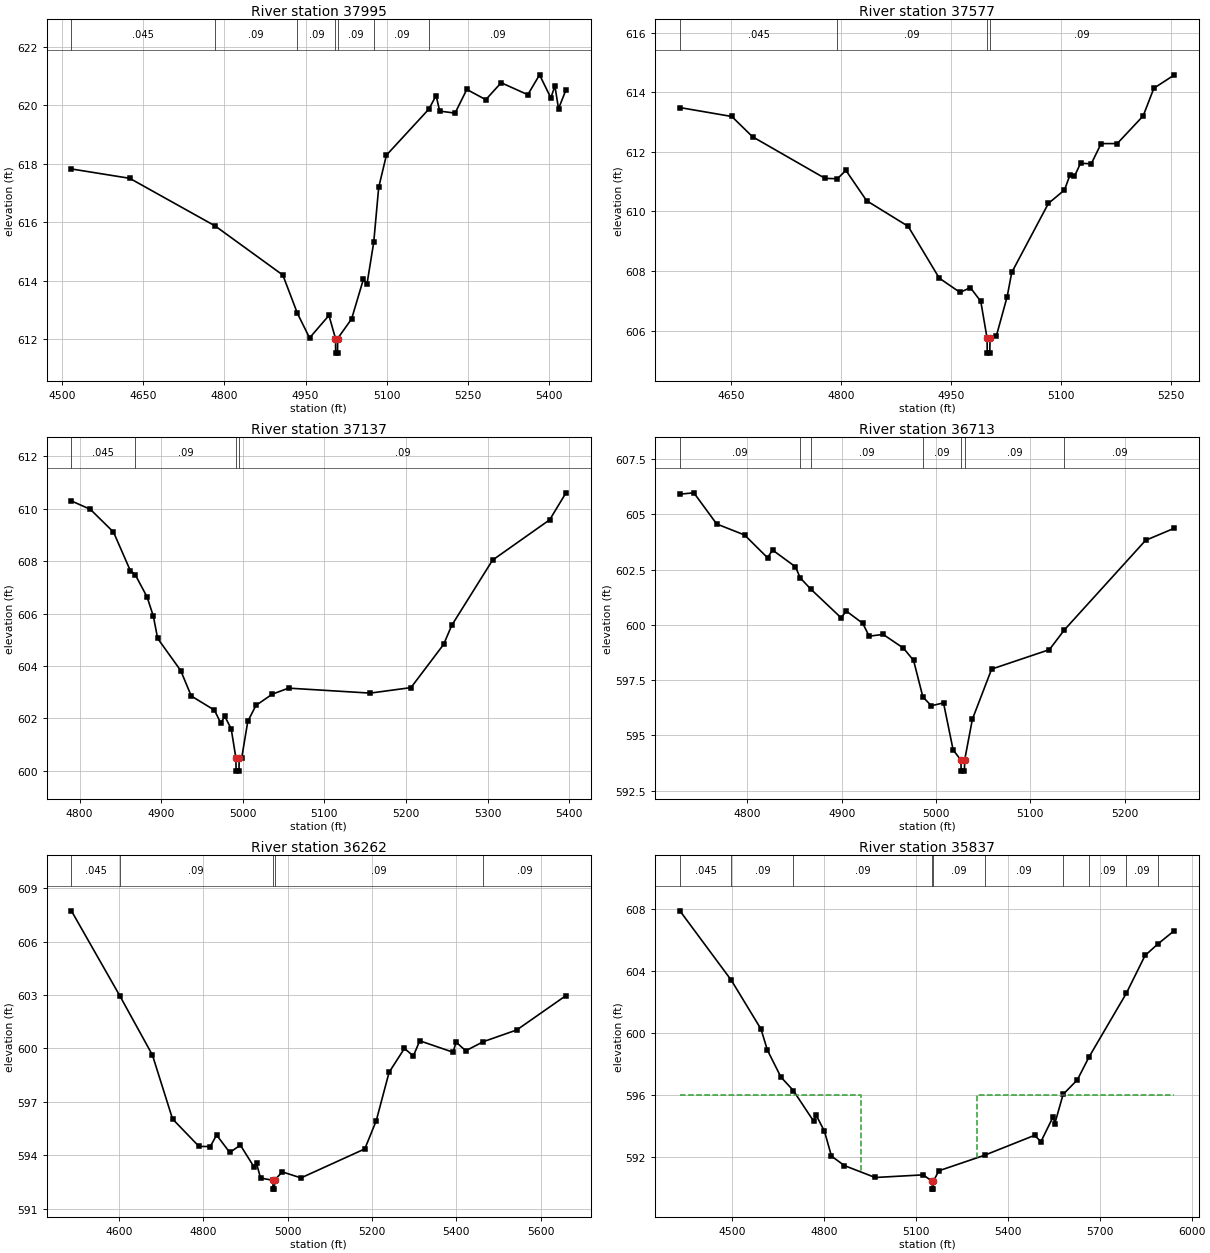
Type RM Length L Ch R = 1 ,37995   ,418,418,418
BEGIN DESCRIPTION:
H21810
END DESCRIPTION:
XS GIS Cut Line= 2
       2250839.2     13766442.94       2250159.9     13765830.68
#Sta/Elev= 30
    4517  617.82  4624.8   617.5  4782.8  615.87    4908  614.19  4934.9  612.88
  4957.4  612.04  4993.2  612.81  5005.3  612.02  5005.6  611.52  5009.1  611.52
  5009.3  612.02  5035.1  612.69  5056.8  614.04  5063.5  613.88    5076  615.31
  5085.2  617.19  5099.4  618.29  5178.1  619.87  5191.3  620.33    5198   619.8
  5226.4  619.73  5248.1  620.54  5283.2  620.19  5311.6  620.77  5360.9  620.36
  5382.6  621.04  5403.5  620.25    5411  620.66  5417.7  619.88  5431.5  620.53
#Mann= 7 ,-1 , 0
    4517    .045       0  4782.8     .09       0  4934.9     .09       0
  5005.3     .05       0  5009.3     .09       0    5076     .09       0
  5178.1     .09       0
Bank Sta=5005.3,5009.3
XS Rating Curve= 0 ,0
Exp/Cntr=0.3,0.1

Type RM Length L Ch R = 1 ,37577   ,440,440,440
BEGIN DESCRIPTION:
YOUNGS CREEK 65.0
END DESCRIPTION:
XS GIS Cut Line= 3
      2251075.03     13766125.03        2250775.       13765825.
      2250575.01     13765675.01
#Sta/Elev= 30
  4580.5  613.49  4651.3  613.19  4679.5  612.51  4778.5  611.11  4795.3   611.1
  4806.8  611.38  4835.1  610.36  4891.7   609.5  4934.1  607.76  4962.4  607.28
  4976.5  607.44  4990.7  606.98  4999.3  605.74  4999.5  605.24    5003  605.24
  5003.3  605.74  5012.1  605.83  5026.7  607.14  5032.9  607.95  5082.9  610.27
  5104.8  610.72  5112.1  611.21  5118.4  611.18  5126.7  611.62  5141.3   611.6
  5154.8  612.28  5176.7  612.28  5212.1  613.21  5226.7  614.14  5254.8  614.59
#Mann= 4 ,-1 , 0
  4580.5    .045       0  4795.3     .09       0  4999.3     .05       0
  5003.3     .09       0
Bank Sta=4999.3,5003.3
XS Rating Curve= 0 ,0
Exp/Cntr=0.3,0.1

Type RM Length L Ch R = 1 ,37137   ,424,424,424
BEGIN DESCRIPTION:
YOUNGS CREEK 64.0
END DESCRIPTION:
XS GIS Cut Line= 3
      2251175.01     13765775.02        2251125.       13765575.
      2250724.98       13765575.
#Sta/Elev= 30
  4789.9   610.3  4813.1  609.98  4841.5  609.11  4862.1  607.64    4868  607.49
  4882.7  606.63  4890.4  605.89  4895.6  605.05  4923.9  603.82  4936.8  602.85
  4965.2  602.31  4972.9  601.82    4978  602.07  4985.8  601.59  4991.5  600.48
  4991.8  599.98  4995.3  599.98  4995.5  600.48  4998.6  600.48  5006.1  601.88
  5016.1  602.49  5036.1  602.92  5056.1  603.15  5156.1  602.96  5206.1  603.17
  5246.1  604.82  5256.1  605.55  5306.1  608.04  5376.1  609.58  5396.1  610.61
#Mann= 4 ,-1 , 0
  4789.9    .045       0    4868     .09       0  4991.5     .05       0
  4995.5     .09       0
Bank Sta=4991.5,4995.5
XS Rating Curve= 0 ,0
Exp/Cntr=0.3,0.1

Type RM Length L Ch R = 1 ,36713   ,451,451,451
BEGIN DESCRIPTION:
YOUNGS CREEK 63.0
END DESCRIPTION:
XS GIS Cut Line= 3
      2251274.98     13765524.96        2251175.       13765275.
      2250924.97     13765224.99
#Sta/Elev= 30
  4728.5  605.92  4743.3  605.98  4767.5  604.57  4797.1  604.07  4821.4  603.04
  4826.7  603.39    4851  602.63    4856  602.13    4867  601.63  4899.4  600.32
  4904.8  600.63  4922.3  600.07  4929.1  599.49  4943.9  599.57  4965.4  598.95
  4976.2  598.39    4986  596.74    4995  596.34  5007.9  596.47  5018.1  594.34
  5026.3  593.88  5026.6  593.38  5030.1  593.38  5030.3  593.88  5038.5  595.73
  5058.9     598  5120.1  598.88  5136.1  599.78  5222.1  603.83  5252.7  604.38
#Mann= 7 ,-1 , 0
  4728.5     .09       0    4856     .09       0    4867     .09       0
    4986     .09       0  5026.3     .05       0  5030.3     .09       0
  5136.1     .09       0
Bank Sta=5026.3,5030.3
XS Rating Curve= 0 ,0
Exp/Cntr=0.3,0.1

Type RM Length L Ch R = 1 ,36262   ,425,425,425
BEGIN DESCRIPTION:
YOUNGS CREEK 62.0
END DESCRIPTION:
XS GIS Cut Line= 3
        2251425.     13765625.01        2251575.       13765125.
      2251025.04     13764775.02
#Sta/Elev= 30
  4486.5  607.73  4601.1  602.97  4678.8  599.63  4726.6  596.04  4789.3   594.5
  4816.2  594.49    4831  595.14  4862.4  594.16  4887.6  594.57  4920.6  593.32
  4925.9  593.55  4935.4  592.72  4964.8   592.6    4965   592.1  4968.5   592.1
  4968.8   592.6  4986.8  593.07  5031.4  592.73  5182.9  594.36    5210  595.94
  5240.5  598.66  5276.9     600  5298.1  599.58  5313.3  600.43  5392.1  599.79
  5399.7  600.35  5422.5  599.87    5464  600.38  5543.6  601.04  5660.4  602.97
#Mann= 5 ,-1 , 0
  4486.5    .045       0  4601.1     .09       0  4964.8     .05       0
  4968.8     .09       0    5464     .09       0
Bank Sta=4964.8,4968.8
XS Rating Curve= 0 ,0
Exp/Cntr=0.3,0.1

Type RM Length L Ch R = 1 ,35837   ,458,458,458
BEGIN DESCRIPTION:
YOUNGS CREEK 61.0
END DESCRIPTION:
XS GIS Cut Line= 3
      2251525.01     13765724.99        2251925.       13765175.
      2251675.01     13764275.04
#Sta/Elev= 30
  4329.9  607.89  4497.8  603.41  4594.6  600.26  4615.4  598.91  4659.5  597.17
    4700   596.3  4766.1  594.33  4774.6  594.71  4801.7  593.67  4824.5  592.07
  4866.6  591.46  4967.1  590.69  5124.1  590.86  5153.3  590.44  5153.5  589.94
    5157  589.94  5157.3  590.44  5174.5  591.12  5324.8  592.13  5487.4  593.41
  5508.1     593  5548.1  594.61  5553.3  594.16  5580.5  596.05    5627  596.99
    5665  598.46  5786.5  602.56    5848  605.01  5889.6  605.75    5944  606.62
#Mann= 10 ,-1 , 0
  4329.9    .045       0  4497.8     .09       0    4700     .09       0
  5153.3     .05       0  5157.3     .09       0  5324.8     .09       0
  5580.5     .09       0    5665     .09       0  5786.5     .09       0
  5889.6     .09       0
#XS Ineff= 2 , 0
       0    4920     596    5300       0     596
Permanent Ineff=
       F       F
Bank Sta=5153.3,5157.3
XS Rating Curve= 0 ,0
Exp/Cntr=0.3,0.1

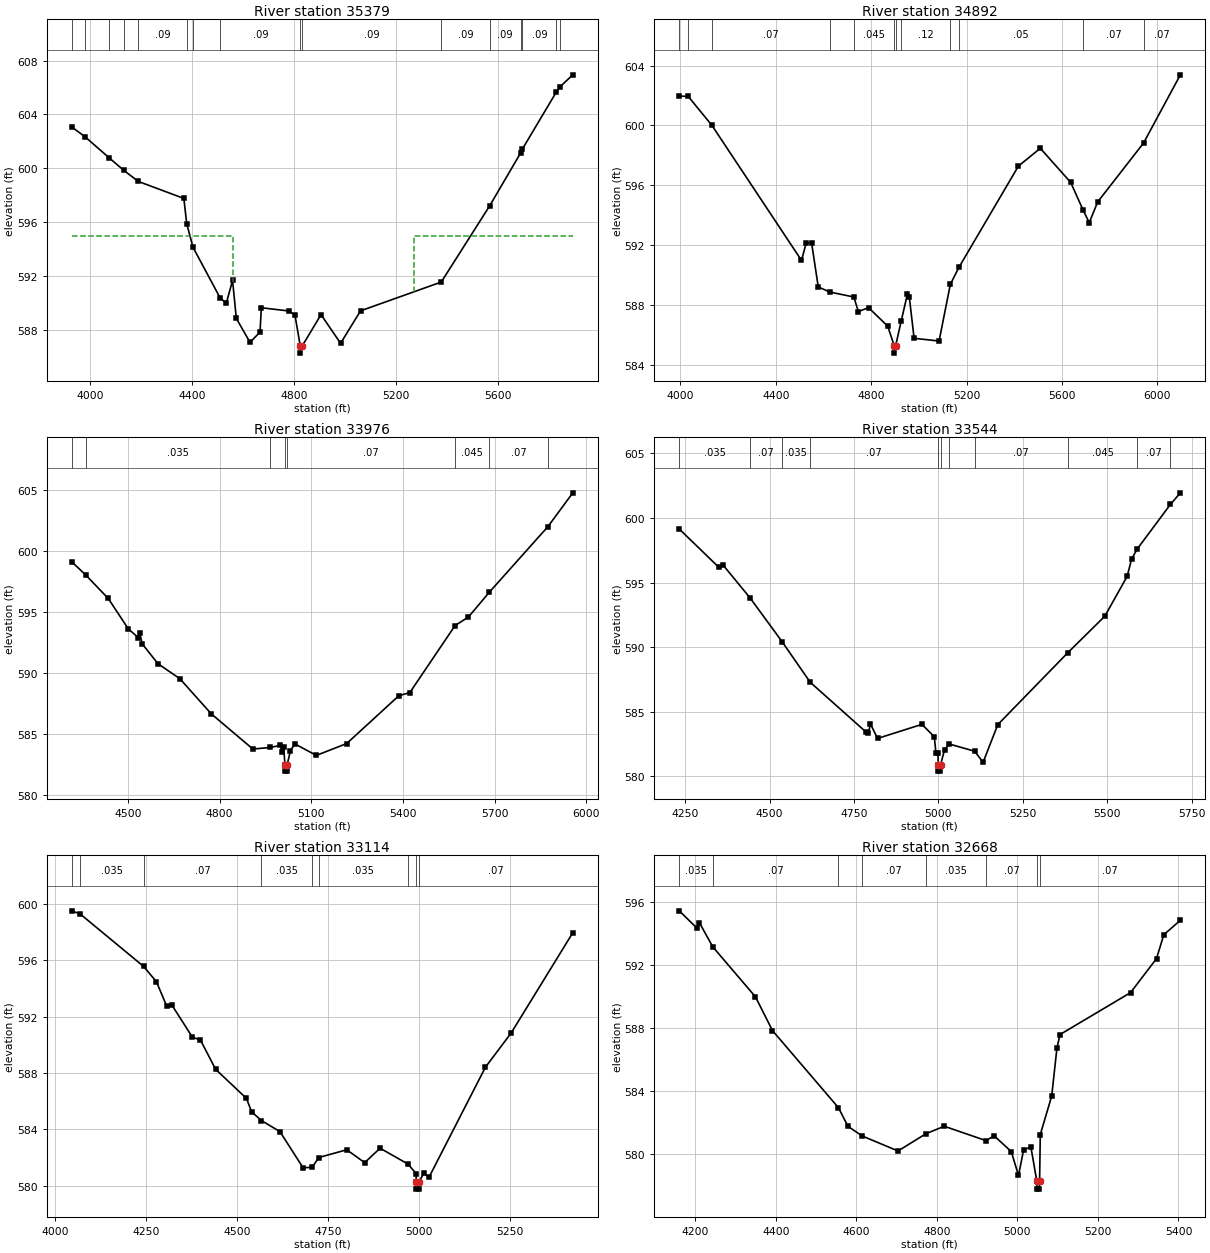
Type RM Length L Ch R = 1 ,35379   ,487,487,487
BEGIN DESCRIPTION:
YOUNGS CREEK 60.0
END DESCRIPTION:
XS GIS Cut Line= 3
      2252674.99     13765974.98        2252275.       13764975.
      2251725.02     13764275.03
#Sta/Elev= 30
  3928.1  603.07  3980.9  602.33  4075.4  600.77  4132.8  599.84  4189.7  599.02
  4368.3  597.76  4379.6  595.88  4404.3  594.13  4511.6  590.34  4535.3     590
  4559.5  591.67  4574.3  588.85  4628.1  587.07  4667.2  587.83  4672.6  589.64
  4780.3   589.4  4804.5   589.1  4825.6  586.77  4826.1  586.27  4831.9  586.77
  4906.8  589.13  4983.6     587    5062  589.41  5378.9  591.55  5569.2  597.22
  5690.8  601.15  5697.4  601.43  5830.2  605.65  5844.3  606.04  5895.3  606.94
#Mann= 16 ,-1 , 0
  3928.1     .09       0  3980.9     .09       0  4075.4     .09       0
  4132.8     .09       0  4189.7     .09       0  4379.6    .063       0
  4404.3     .09       0  4511.6     .09       0  4825.6     .05       0
  4831.9     .09       0  5378.9     .09       0  5569.2     .09       0
  5690.8     .09       0  5697.4     .09       0  5830.2     .09       0
  5844.3     .09       0
#XS Ineff= 2 , 0
       0    4560     595    5270       0     595
Permanent Ineff=
       F       F
Bank Sta=4825.6,4831.9
XS Rating Curve= 0 ,0
Exp/Cntr=0.3,0.1

Type RM Length L Ch R = 1 ,34892   ,916,916,916
BEGIN DESCRIPTION:
YOUNGS CREEK 59.0
END DESCRIPTION:
XS GIS Cut Line= 3
        2252825.     13765874.99        2252725.       13764875.
      2251924.98     13764124.98
#Sta/Elev= 30
    3995  601.96  4032.4  601.94  4131.6  600.01  4507.5  590.98  4527.6  592.15
  4550.2  592.13  4577.9   589.2  4627.7  588.86    4727  588.53  4746.2  587.56
  4788.9  587.82  4869.3  586.58  4896.3  585.28  4896.8  584.78  4902.7  585.28
  4925.4   586.9  4952.2  588.75  4959.8  588.53  4979.9  585.77  5084.7  585.59
  5131.9  589.38  5167.8  590.51  5417.4  597.28  5509.2  598.47  5636.7  596.19
  5688.7  594.34  5714.4   593.5    5750  594.89  5942.1  598.82  6096.6  603.38
#Mann= 12 ,-1 , 0
    3995     .07       0  4032.4     .07       0  4131.6     .07       0
  4627.7    .063       0    4727    .045       0  4896.3     .05       0
  4902.7    .045       0  4925.4     .12       0  5131.9    .045       0
  5167.8     .05       0  5688.7     .07       0  5942.1     .07       0
Bank Sta=4896.3,4902.7
XS Rating Curve= 0 ,0
Exp/Cntr=0.3,0.1

Type RM Length L Ch R = 1 ,33976   ,432,432,432
BEGIN DESCRIPTION:
YOUNGS CREEK 57.0
END DESCRIPTION:
XS GIS Cut Line= 3
        2253275.     13765824.98        2253475.       13765175.
      2254074.98     13764425.02
#Sta/Elev= 30
  4315.6  599.14  4362.1  598.04  4435.2  596.13  4500.6  593.65  4533.3  592.92
  4538.6  593.33  4545.8  592.43  4598.1  590.78  4669.4  589.56  4772.7  586.67
  4908.7  583.79  4965.6  583.92  4998.9  584.09  5002.9  583.52  5009.3  583.93
  5013.9  582.48  5014.4  581.98  5020.2  581.98  5020.7  582.48  5031.7  583.67
  5046.1  584.21  5116.5  583.27  5215.8  584.24    5387  588.17  5422.3  588.41
  5570.6  593.91  5614.4  594.61    5683  596.65  5874.6  602.02  5956.1  604.79
#Mann= 8 ,-1 , 0
  4315.6    .045       0  4362.1    .035       0  4965.6     .07       0
  5013.9     .05       0  5020.7     .07       0  5570.6    .045       0
    5683     .07       0  5874.6    .035       0
Bank Sta=5013.9,5020.7
XS Rating Curve= 0 ,0
Exp/Cntr=0.3,0.1

Type RM Length L Ch R = 1 ,33544   ,430,430,430
BEGIN DESCRIPTION:
YOUNGS CREEK 56.0
END DESCRIPTION:
XS GIS Cut Line= 3
      2253475.01     13765924.98        2253875.       13765275.
        2254275.       13764675.
#Sta/Elev= 30
  4232.5  599.15  4349.9  596.18    4362  596.37  4442.1  593.82  4537.6  590.41
  4620.3  587.29  4784.3  583.47  4792.8  583.34  4798.6  584.07  4819.9  582.94
  4951.3  584.03    4988  583.07  4992.8   581.8  4998.7   581.8  4999.8  580.91
  5000.3  580.41  5006.1  580.41  5006.6  580.91  5018.2  582.06  5032.2  582.51
  5107.5  581.95  5132.4  581.09    5176  584.01  5383.6  589.58    5493   592.4
  5559.1  595.48  5572.6  596.85  5589.8  597.63  5687.5  601.06  5716.8  601.95
#Mann= 11 ,-1 , 0
  4232.5    .035       0  4442.1     .07       0  4537.6    .035       0
  4620.3     .07       0  4999.8     .05       0  5006.6     .07       0
  5032.2    .035       0  5107.5     .07       0  5383.6    .045       0
  5589.8     .07       0  5687.5    .035       0
Bank Sta=4999.8,5006.6
XS Rating Curve= 0 ,0
Exp/Cntr=0.3,0.1

Type RM Length L Ch R = 1 ,33114   ,446,446,446
BEGIN DESCRIPTION:
YOUNGS CREEK 55.0
END DESCRIPTION:
XS GIS Cut Line= 3
      2253624.98     13766075.02        2254275.       13765375.
      2254574.97     13765075.03
#Sta/Elev= 30
  4044.7   599.5  4067.8  599.28  4242.5  595.56    4278  594.47  4306.4  592.73
  4320.5  592.82  4377.2  590.53  4398.7  590.36  4440.7  588.27  4525.8   586.2
  4539.9  585.25    4567  584.63  4617.9  583.85  4681.7  581.28  4706.9  581.32
  4724.6  582.01  4801.8  582.56  4851.2  581.65  4893.7  582.67  4970.2  581.55
  4992.9  580.87  4993.1  580.27  4993.6  579.77  4999.5  579.77    5000  580.27
  5014.1  580.88  5028.3  580.61  5183.8  588.42  5254.5  590.84  5424.2  597.95
#Mann= 9 ,-1 , 0
  4044.7    .045       0  4067.8    .035       0  4242.5     .07       0
    4567    .035       0  4706.9     .07       0  4724.6    .035       0
  4970.2     .07       0  4993.1     .05       0    5000     .07       0
Bank Sta=4993.1,5000
XS Rating Curve= 0 ,0
Exp/Cntr=0.3,0.1

Type RM Length L Ch R = 1 ,32668   ,725,725,725
BEGIN DESCRIPTION:
YOUNGS CREEK 54.0
END DESCRIPTION:
XS GIS Cut Line= 3
      2253874.96     13766075.03        2254575.       13765625.
      2254674.99     13765225.02
#Sta/Elev= 30
  4160.2  595.43  4204.2  594.33  4210.1  594.68  4243.6  593.14  4349.5  589.97
  4391.7  587.83  4555.4  582.94  4579.3  581.75  4614.8  581.14  4703.5  580.19
  4773.1  581.29  4818.4  581.76  4921.7  580.85  4942.5  581.15  4984.8  580.15
  5002.7  578.64  5015.6  580.28  5033.6  580.43  5048.2  578.27  5048.7  577.77
  5054.6  577.77  5055.1  578.27  5056.8  581.23  5085.2  583.68  5098.1  586.71
  5105.8  587.58    5281  590.24  5345.5   592.4  5363.5  593.91  5404.7  594.83
#Mann= 8 ,-1 , 0
  4160.2    .035       0  4243.6     .07       0  4555.4    .035       0
  4614.8     .07       0  4773.1    .035       0  4921.7     .07       0
  5048.2     .05       0  5055.1     .07       0
Bank Sta=5048.2,5055.1
XS Rating Curve= 0 ,0
Exp/Cntr=0.3,0.1

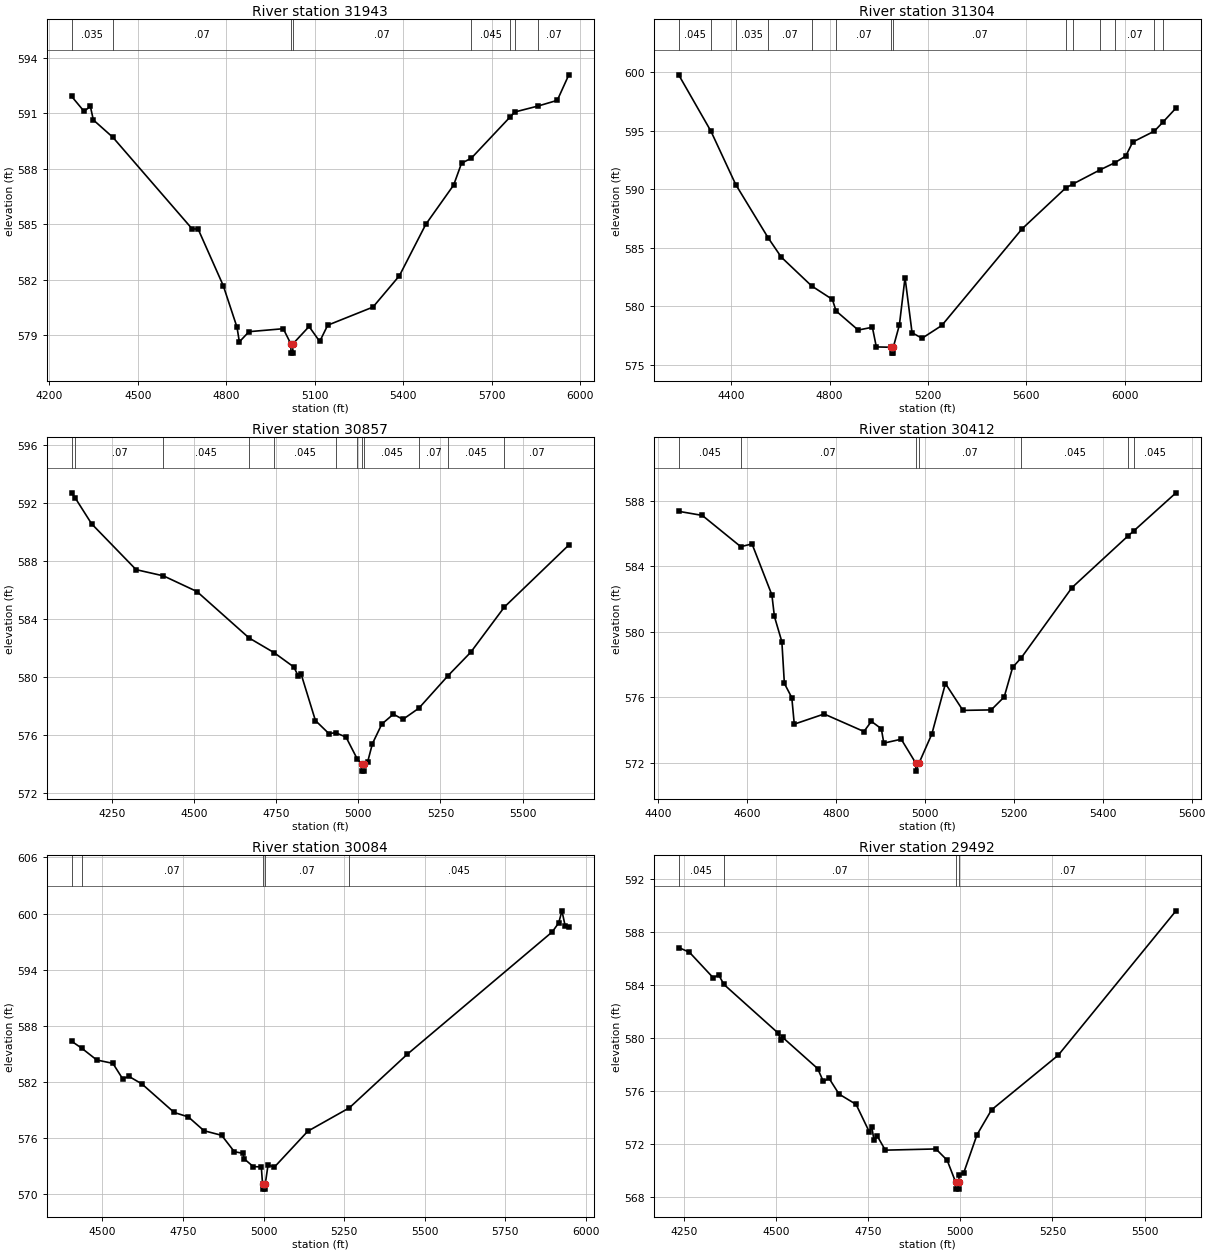
Type RM Length L Ch R = 1 ,31943   ,639,639,639
BEGIN DESCRIPTION:
J21806
END DESCRIPTION:
XS GIS Cut Line= 4
      2254002.08     13766357.88      2254642.06     13766246.77
      2254895.38     13765860.13      2254717.61      13765313.5
#Sta/Elev= 30
  4275.1  591.93  4317.4  591.12    4339  591.38  4349.1  590.65  4415.4  589.71
  4684.1  584.76  4704.4  584.75  4789.7  581.69  4836.3  579.44  4844.3  578.65
  4876.9   579.2  4993.2  579.36  5018.9  578.54  5019.4  578.04  5025.4  578.04
  5025.9  578.54  5080.7  579.48  5116.8  578.67  5143.9  579.55  5297.4  580.53
  5386.9  582.22  5476.4     585  5571.1  587.13  5597.8  588.31  5630.8  588.58
  5763.1  590.82  5778.4  591.08  5856.7   591.4  5922.5  591.71  5961.7  593.09
#Mann= 8 ,-1 , 0
  4275.1    .035       0  4415.4     .07       0  5018.9     .05       0
  5025.9     .07       0  5630.8    .045       0  5763.1     .07       0
  5778.4    .045       0  5856.7     .07       0
Bank Sta=5018.9,5025.9
XS Rating Curve= 0 ,0
Exp/Cntr=0.3,0.1

Type RM Length L Ch R = 1 ,31304   ,447,447,447
BEGIN DESCRIPTION:
YOUNGS CREEK 53.0
END DESCRIPTION:
XS GIS Cut Line= 3
      2255325.01     13767025.03        2255175.       13766225.
      2254674.99     13765124.98
#Sta/Elev= 30
    4186  599.78  4317.3  594.96    4418  590.41  4550.1  585.85  4603.2  584.21
  4726.6  581.75  4810.9   580.6  4826.1  579.61    4916  577.98  4973.7  578.22
  4989.8  576.54  5051.1  576.51  5051.6  576.01  5058.2  576.01  5058.7  576.51
  5083.5  578.41  5106.5  582.46  5135.1  577.75  5175.7  577.28  5255.9  578.37
  5582.2  586.62  5760.1  590.12  5791.5  590.48  5901.1  591.68  5958.5  592.26
    6004  592.84  6032.5  594.04  6120.4  594.97  6156.2  595.76  6208.3  596.94
#Mann= 14 ,-1 , 0
    4186    .045       0  4317.3     .07       0    4418    .035       0
  4550.1     .07       0  4726.6    .045       0  4826.1     .07       0
  5051.1     .05       0  5058.7     .07       0  5760.1    .045       0
  5791.5     .07       0  5901.1    .045       0  5958.5     .07       0
  6120.4    .045       0  6156.2    .035       0
Bank Sta=5051.1,5058.7
XS Rating Curve= 0 ,0
Exp/Cntr=0.3,0.1

Type RM Length L Ch R = 1 ,30857   ,445,445,445
BEGIN DESCRIPTION:
YOUNGS CREEK 52.0
END DESCRIPTION:
XS GIS Cut Line= 3
      2255825.01     13766725.03        2255475.       13765925.
      2254974.97     13765524.97
#Sta/Elev= 30
    4127  592.69  4138.4  592.33  4188.2  590.55  4323.5  587.39  4406.9  586.96
  4508.7  585.88  4667.2  582.68  4743.7  581.66  4803.8  580.67  4816.6  580.07
  4825.6   580.2  4869.3  576.98  4910.2  576.08  4930.6  576.14  4962.4  575.84
  4996.8  574.32    5010  573.99  5010.5  573.49  5017.2  573.49  5017.7  573.99
  5028.3  574.13  5042.7  575.38  5071.5  576.74  5106.7  577.42  5135.5  577.06
  5184.1  577.83  5273.2  580.08    5342  581.69  5444.4  584.81  5640.6  589.09
#Mann= 12 ,-1 , 0
    4127    .045       0  4138.4     .07       0  4406.9    .045       0
  4667.2     .07       0  4743.7    .045       0  4930.6     .07       0
  4996.8    .045       0    5010    .045       0  5017.7    .045       0
  5184.1     .07       0  5273.2    .045       0  5444.4     .07       0
Bank Sta=5010,5017.7
XS Rating Curve= 0 ,0
Exp/Cntr=0.3,0.1

Type RM Length L Ch R = 1 ,30412   ,328,328,328
BEGIN DESCRIPTION:
YOUNGS CREEK 51.0
END DESCRIPTION:
XS GIS Cut Line= 3
      2255874.99     13766024.99        2255625.       13765525.
      2255075.02       13765425.
#Sta/Elev= 30
  4446.8  587.35  4499.9   587.1  4586.4  585.19  4611.7  585.36  4656.4  582.24
    4662  580.93  4678.8  579.38  4684.4  576.84  4701.1  575.97  4706.7  574.35
  4773.8  574.97  4863.3   573.9    4880  574.52  4902.4  574.07    4908  573.19
  4947.1  573.43  4979.6  571.98  4980.1  571.48  4987.3  571.98    5016  573.75
  5046.5  576.83  5085.8  575.19  5149.4  575.22  5178.6  576.01  5197.6  577.82
  5216.9   578.4    5331  582.69  5457.9  585.87  5470.6  586.17  5564.8  588.48
#Mann= 7 ,-1 , 0
  4446.8    .045       0  4586.4     .07       0  4979.6     .05       0
  4987.3     .07       0  5216.9    .045       0  5457.9     .07       0
  5470.6    .045       0
Bank Sta=4979.6,4987.3
XS Rating Curve= 0 ,0
Exp/Cntr=0.3,0.1

Type RM Length L Ch R = 1 ,30084   ,592,592,592
BEGIN DESCRIPTION:
H21809
END DESCRIPTION:
XS GIS Cut Line= 4
      2255898.72     13765893.24      2255912.13     13765540.13
      2255760.17     13765044.01      2255782.51     13764373.62
#Sta/Elev= 30
  4404.2  586.37  4436.6   585.6  4482.5  584.36  4532.5     584  4562.6  582.36
  4582.6   582.6  4622.6   581.8  4722.7  578.75  4766.5  578.28  4815.2   576.8
    4870  576.31  4909.3  574.56  4935.5  574.39  4940.8  573.77  4968.3  572.96
    4993  572.94    4997  571.06  4997.5  570.56  5004.6  570.56  5005.1  571.06
  5013.9  573.14  5033.8  572.92  5137.3  576.75  5266.3  579.25  5445.5  584.96
  5895.8  598.05  5915.8  599.01  5925.8   600.3  5935.8  598.69  5947.2  598.62
#Mann= 5 ,-1 , 0
  4404.2    .045       0  4436.6     .07       0    4997     .05       0
  5005.1     .07       0  5266.3    .045       0
Bank Sta=4997,5005.1
XS Rating Curve= 0 ,0
Exp/Cntr=0.3,0.1

Type RM Length L Ch R = 1 ,29492   ,414,414,414
BEGIN DESCRIPTION:
YOUNGS CREEK 50.0
END DESCRIPTION:
XS GIS Cut Line= 3
      2255924.99     13765925.01        2256325.       13765275.
      2256525.01     13764724.97
#Sta/Elev= 30
  4236.5  586.81  4265.5  586.46  4330.5  584.52  4344.8  584.76  4359.1  584.03
  4506.6  580.35  4512.8  579.81  4518.7  580.03  4613.4  577.68  4628.8  576.71
  4644.2  576.95  4671.3  575.76  4717.6  574.98  4753.2  572.92  4760.1  573.27
    4766  572.31  4775.5  572.57  4796.8  571.53  4934.1  571.62  4964.5  570.77
  4987.9  569.09  4988.4  568.59  4995.7  568.59  4996.2  569.09  4996.8  569.66
  5009.7  569.84  5045.6   572.7  5084.9  574.57  5265.7  578.69    5585  589.58
#Mann= 4 ,-1 , 0
  4236.5    .045       0  4359.1     .07       0  4987.9     .05       0
  4996.2     .07       0
Bank Sta=4987.9,4996.2
XS Rating Curve= 0 ,0
Exp/Cntr=0.3,0.1

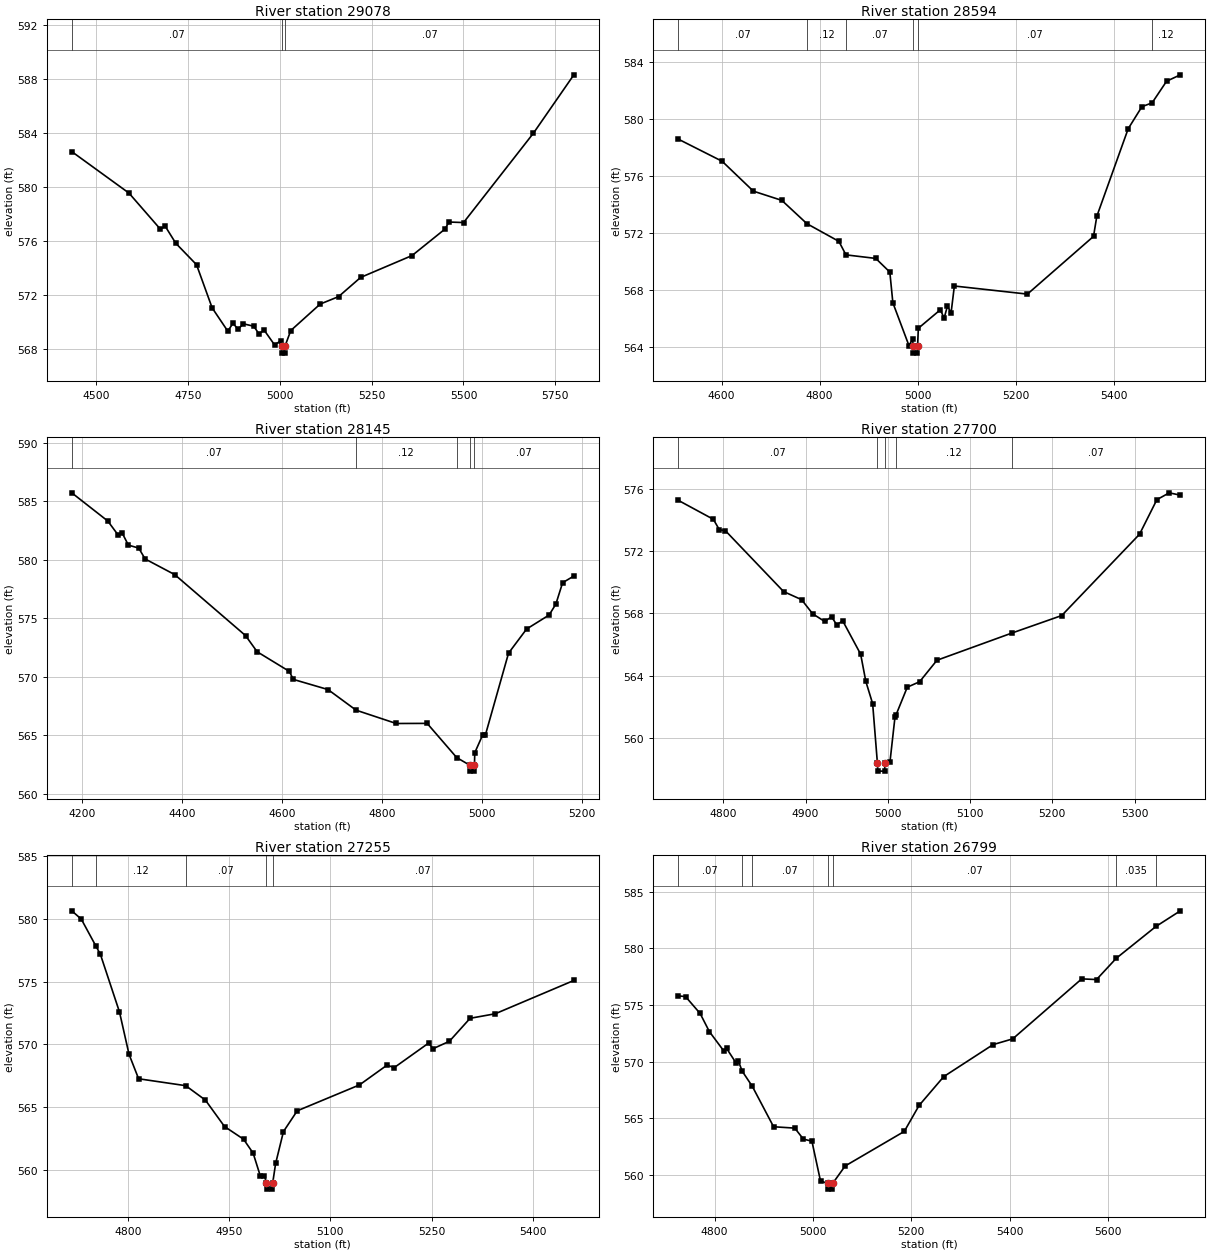
Type RM Length L Ch R = 1 ,29078   ,484,484,484
BEGIN DESCRIPTION:
YOUNGS CREEK 49.0
END DESCRIPTION:
XS GIS Cut Line= 3
      2256174.99     13765975.01        2256575.       13765575.
        2256575.     13764774.99
#Sta/Elev= 30
  4434.6  582.61  4590.2  579.54    4675  576.89  4689.2  577.07  4717.5  575.83
    4774  574.24  4816.4  571.05  4858.9  569.33    4873   569.9  4887.2  569.47
  4901.3  569.87  4929.6  569.69  4943.7  569.13  4957.9   569.4  4986.2  568.31
  5002.8  568.61  5006.1   568.2  5006.6   567.7  5013.9   567.7  5014.4   568.2
  5030.3  569.37  5110.3  571.33  5160.3  571.88  5220.3   573.3  5360.3  574.92
  5450.3  576.89  5460.3   577.4  5500.3  577.36  5690.3  583.97  5800.3  588.29
#Mann= 3 ,-1 , 0
  4434.6     .07       0  5006.1     .05       0  5014.4     .07       0
Bank Sta=5006.1,5014.4
XS Rating Curve= 0 ,0
Exp/Cntr=0.3,0.1

Type RM Length L Ch R = 1 ,28594   ,449,449,449
BEGIN DESCRIPTION:
YOUNGS CREEK 48.0
END DESCRIPTION:
XS GIS Cut Line= 3
      2256825.01     13766124.97        2257025.       13765675.
      2257424.99     13765325.01
#Sta/Elev= 30
  4511.7   578.6  4601.3  577.04  4664.9  574.94    4723  574.29  4774.2  572.65
  4839.3  571.41  4853.7  570.46  4914.5  570.21  4943.2  569.25  4949.4  567.09
  4982.2  564.08  4989.7  564.53  4990.8  564.05  4991.3  563.55  4999.2  563.55
  4999.7  564.05  5001.4   565.3  5046.3   566.6  5053.9  566.01  5060.6  566.84
  5068.2   566.4  5074.8  568.27  5223.8   567.7  5358.6  571.76  5365.3  573.17
  5429.3  579.33  5457.3  580.88  5478.1  581.15  5507.6  582.67  5535.6  583.12
#Mann= 6 ,-1 , 0
  4511.7     .07       0  4774.2     .12       0  4853.7     .07       0
  4990.8     .05       0  4999.7     .07       0  5478.1     .12       0
Bank Sta=4990.8,4999.7
XS Rating Curve= 0 ,0
Exp/Cntr=0.3,0.1

Type RM Length L Ch R = 1 ,28145   ,445,445,445
BEGIN DESCRIPTION:
YOUNGS CREEK 47.0
END DESCRIPTION:
XS GIS Cut Line= 3
      2257225.01     13766524.95        2257425.       13765725.
      2257574.96     13765625.03
#Sta/Elev= 30
  4179.6   585.7  4251.7  583.29  4272.3   582.1  4280.1   582.3  4292.9  581.23
  4313.6  580.98  4326.4  580.05  4385.7  578.71  4527.4   573.5  4550.6  572.12
  4615.1  570.44  4622.8  569.76  4692.4  568.89  4748.5  567.13  4828.9  565.99
  4890.8     566  4949.9  563.08  4976.4  562.42  4976.9  561.92    4985  561.92
  4985.5  562.42  4986.1  563.49  5001.6  564.98  5007.2  564.98  5053.7     572
  5089.8  574.06  5134.9  575.26  5148.4  576.19  5161.9  578.02  5184.4  578.59
#Mann= 5 ,-1 , 0
  4179.6     .07       0  4748.5     .12       0  4949.9     .07       0
  4976.4     .05       0  4985.5     .07       0
Bank Sta=4976.4,4985.5
XS Rating Curve= 0 ,0
Exp/Cntr=0.3,0.1

Type RM Length L Ch R = 1 ,27700   ,445,445,445
BEGIN DESCRIPTION:
YOUNGS CREEK 46.0
END DESCRIPTION:
XS GIS Cut Line= 3
      2257425.02     13766324.97        2257575.       13766125.
      2257774.99     13765825.02
#Sta/Elev= 30
  4745.2  575.26  4787.9  574.04  4795.2  573.37  4802.5  573.31  4873.3   569.4
  4895.2  568.88  4908.7  567.97  4923.3  567.48  4931.6  567.78  4937.9  567.27
  4945.2  567.52    4967  565.38  4973.3  563.63  4981.6   562.2  4987.4  558.37
  4987.9  557.87  4996.1  557.87  4996.6  558.37  5002.7  558.48  5008.7  561.32
  5009.8  561.45  5023.7  563.26  5038.7  563.61  5059.8  564.99  5151.1  566.74
  5211.5  567.86  5306.1  573.08  5327.2   575.3  5342.2  575.74  5355.7  575.59
#Mann= 5 ,-1 , 0
  4745.2     .07       0  4987.4     .05       0  4996.6     .07       0
  5009.8     .12       0  5151.1     .07       0
Bank Sta=4987.4,4996.6
XS Rating Curve= 0 ,0
Exp/Cntr=0.3,0.1

Type RM Length L Ch R = 1 ,27255   ,456,456,456
BEGIN DESCRIPTION:
YOUNGS CREEK 45.0
END DESCRIPTION:
XS GIS Cut Line= 3
      2257725.01     13766574.99        2257925.       13766375.
        2258025.       13765925.
#Sta/Elev= 30
  4716.9  580.63    4731  579.97  4752.4  577.85  4759.3  577.17  4787.6  572.58
  4801.7  569.22  4815.9  567.27  4885.7  566.72  4914.9  565.57  4943.2  563.47
  4971.4  562.46  4985.6  561.35  4996.2  559.54  5002.3  559.54  5005.3  558.99
  5005.8  558.49  5014.1  558.49  5014.6  558.99  5018.9  560.53  5030.5  563.07
  5050.9  564.72  5143.1  566.78  5184.1  568.36  5194.4  568.15  5245.6  570.11
    5252  569.66  5276.3  570.25    5307  572.08  5344.2  572.44  5460.7  575.09
#Mann= 5 ,-1 , 0
  4716.9     .07       0  4752.4     .12       0  4885.7     .07       0
  5005.3     .05       0  5014.6     .07       0
Bank Sta=5005.3,5014.6
XS Rating Curve= 0 ,0
Exp/Cntr=0.3,0.1

Type RM Length L Ch R = 1 ,26799   ,476,476,476
BEGIN DESCRIPTION:
YOUNGS CREEK 44.0
END DESCRIPTION:
XS GIS Cut Line= 3
      2258224.99     13766675.03        2258325.       13766425.
        2258375.     13765674.95
#Sta/Elev= 30
  4726.2  575.81    4741  575.75  4770.7  574.26  4789.5  572.66  4819.1  570.94
  4824.5  571.18  4843.4  569.92  4848.7  570.04  4856.3  569.17    4877  567.82
  4920.1  564.27  4963.2  564.15  4980.7  563.18    4998     563  5015.5  559.49
  5030.9  559.27  5031.4  558.77  5039.7  558.77  5040.2  559.27  5065.6  560.81
  5185.9  563.86    5216  566.15  5266.1  568.69  5366.3  571.51  5406.4  572.02
  5546.7  577.31  5576.8  577.25  5616.8  579.12  5697.6  581.93  5747.2  583.31
#Mann= 7 ,-1 , 0
  4726.2     .07       0  4856.3     .12       0    4877     .07       0
  5030.9     .05       0  5040.2     .07       0  5616.8    .035       0
  5697.6     .07       0
Bank Sta=5030.9,5040.2
XS Rating Curve= 0 ,0
Exp/Cntr=0.3,0.1