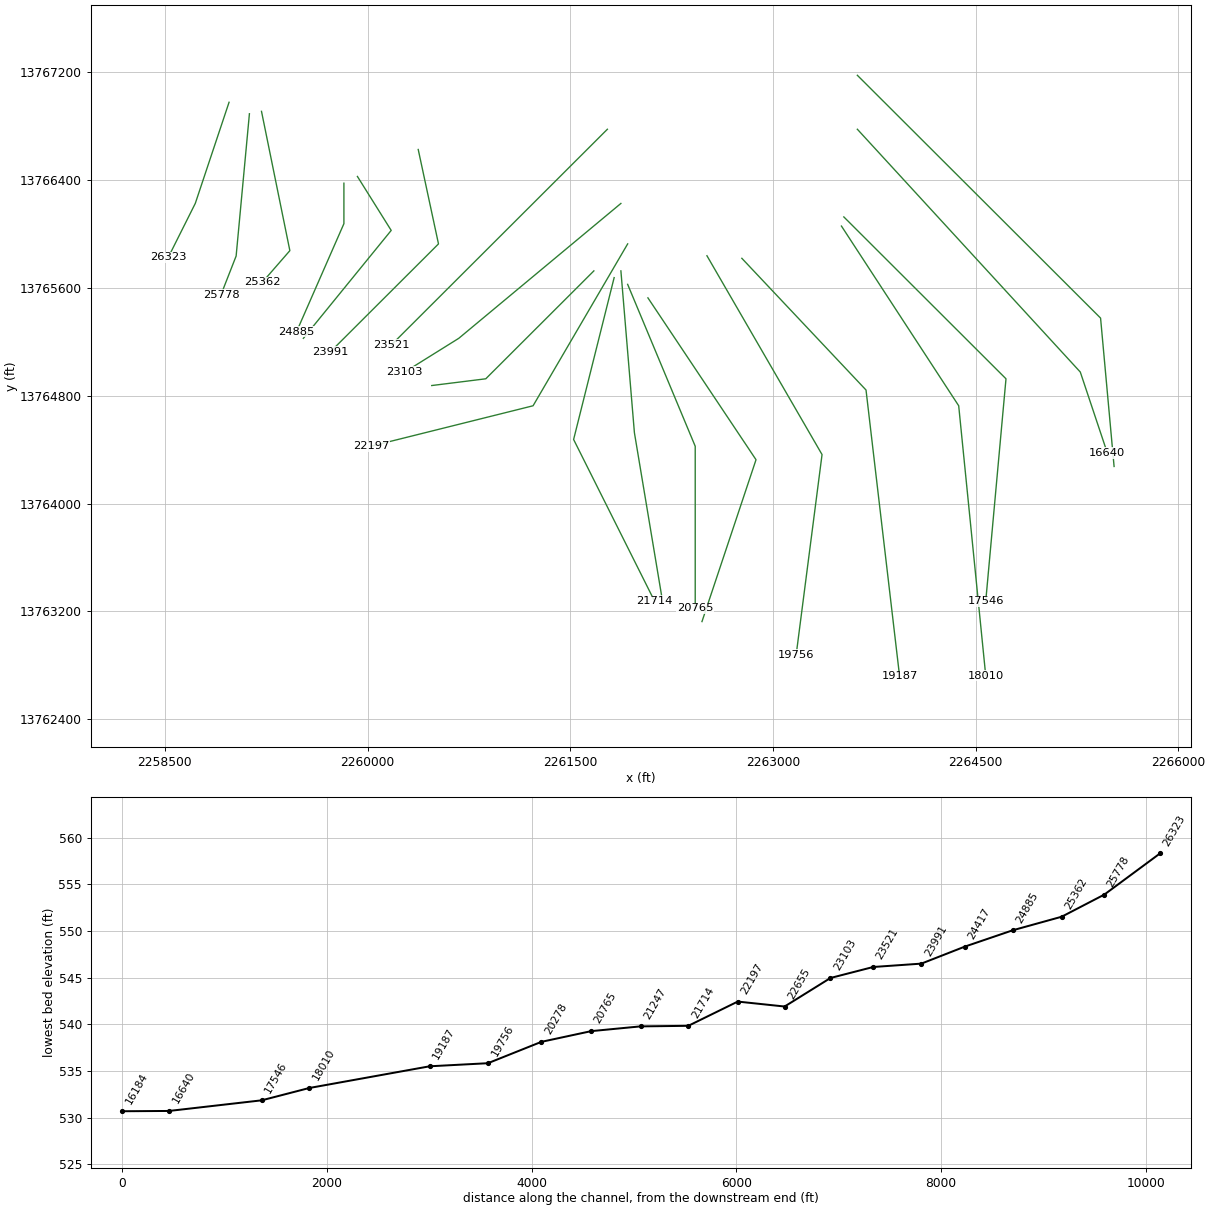
HEC-RAS study YOUNGS CREEK.prj: YOUNGS CREEK Base Level Engineering

--- YOUNGS CREEK.g01 (geometry) --- (continued)

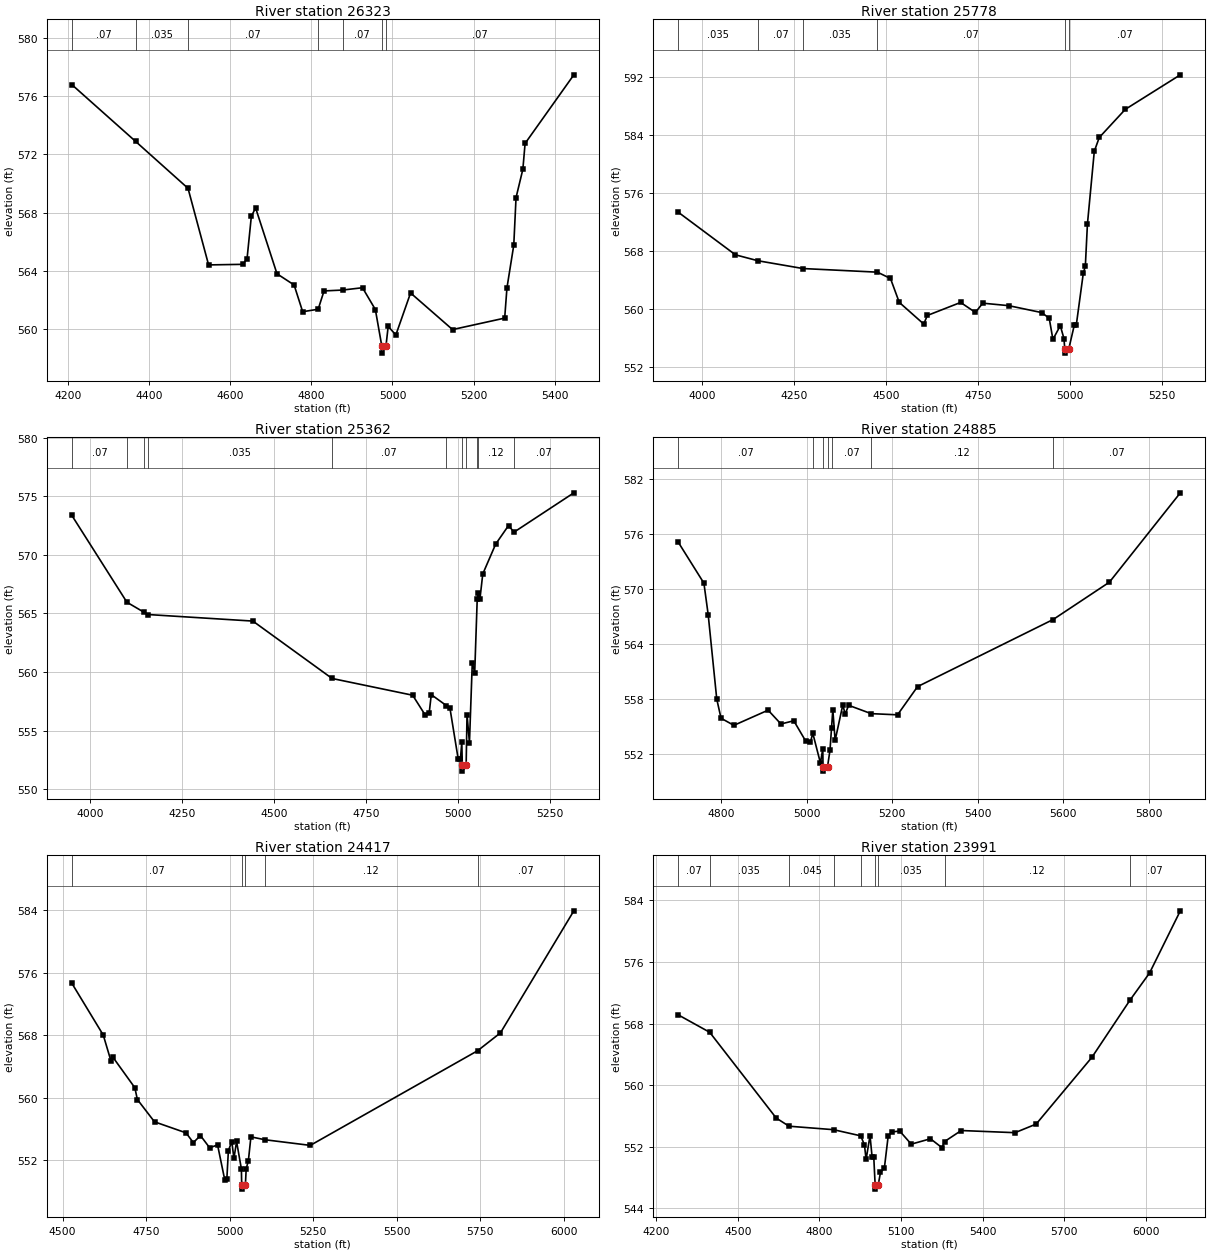
Type RM Length L Ch R = 1 ,26323   ,545,545,545
BEGIN DESCRIPTION:
YOUNGS CREEK 43.0
END DESCRIPTION:
XS GIS Cut Line= 3
      2258974.99     13766974.96        2258725.       13766225.
      2258525.02     13765825.03
#Sta/Elev= 30
  4209.5  576.81  4366.8   572.9  4496.1  569.67  4546.8   564.4  4631.1  564.44
  4641.6  564.83  4652.2  567.75  4662.7  568.32  4715.4  563.79  4757.6  563.02
  4778.7  561.18  4816.9  561.35  4831.4  562.61  4877.1  562.67  4926.2  562.83
  4957.9  561.33  4973.7  558.83  4974.2  558.33  4984.1  558.83  4989.5  560.17
  5008.4  559.58  5044.7  562.47  5148.2  559.95  5276.7  560.74  5282.3  562.82
  5299.1  565.76  5304.7  569.03  5321.5  570.98    5327  572.76  5447.2  577.48
#Mann= 7 ,-1 , 0
  4209.5     .07       0  4366.8    .035       0  4496.1     .07       0
  4816.9    .035       0  4877.1     .07       0  4973.7     .05       0
  4984.1     .07       0
Bank Sta=4973.7,4984.1
XS Rating Curve= 0 ,0
Exp/Cntr=0.3,0.1

Type RM Length L Ch R = 1 ,25778   ,416,416,416
BEGIN DESCRIPTION:
YOUNGS CREEK 42.0
END DESCRIPTION:
XS GIS Cut Line= 3
      2259125.71      13766889.9      2259027.38     13765835.12
      2258915.84     13765549.58
#Sta/Elev= 30
  3934.1  573.32  4089.7  567.45  4151.1  566.63  4273.5  565.56  4476.1  565.06
  4511.5  564.19  4535.4   560.9  4601.9  557.92  4611.9   559.1  4702.3  560.89
  4742.5  559.52  4762.6  560.79  4832.9  560.45  4923.3  559.49  4943.4   558.7
  4953.4   555.8  4973.5  557.69  4983.5  555.91  4985.7  554.41  4986.2  553.91
  4996.2  554.41  5011.7  557.79  5017.1  557.81  5036.2  564.96  5041.6  565.86
  5047.3  571.68    5066  581.71  5079.5  583.61  5150.2  587.48    5300  592.24
#Mann= 6 ,-1 , 0
  3934.1    .035       0  4151.1     .07       0  4273.5    .035       0
  4476.1     .07       0  4985.7     .05       0  4996.2     .07       0
Bank Sta=4985.7,4996.2
XS Rating Curve= 0 ,0
Exp/Cntr=0.3,0.1

Type RM Length L Ch R = 1 ,25362   ,477,477,477
BEGIN DESCRIPTION:
YOUNGS CREEK 41.0
END DESCRIPTION:
XS GIS Cut Line= 3
      2259215.09     13766907.83        2259425.       13765875.
      2259220.45     13765639.47
#Sta/Elev= 30
    3950  573.38    4100  565.96  4146.7   565.1  4157.1  564.91  4442.7  564.35
  4658.2  559.45  4877.4  558.02  4912.1   556.3  4922.3  556.48    4928  558.07
  4969.4  557.13  4978.6  556.96  5001.4  552.55  5007.3  552.55  5011.1  554.02
  5012.4  552.04  5012.9  551.54  5022.9  552.04  5025.3  556.37  5031.9  553.97
  5039.6   560.8  5046.2  559.95    5053   566.2  5055.4  566.76  5060.4  566.23
  5068.1  568.37  5103.2  570.92  5138.3  572.51    5153  571.94  5315.9   575.3
#Mann= 11 ,-1 , 0
    3950     .07       0    4100    .035       0  4146.7     .07       0
  4157.1    .035       0  4658.2     .07       0  4969.4     .12       0
  5012.4     .05       0  5022.9     .12       0    5053     .07       0
  5055.4     .12       0    5153     .07       0
Bank Sta=5012.4,5022.9
XS Rating Curve= 0 ,0
Exp/Cntr=0.3,0.1

Type RM Length L Ch R = 1 ,24885   ,468,468,468
BEGIN DESCRIPTION:
YOUNGS CREEK 40.0
END DESCRIPTION:
XS GIS Cut Line= 3
        2259825.     13766374.98        2259825.       13766075.
        2259475.     13765274.99
#Sta/Elev= 30
    4700   575.1    4760  570.62    4770  567.18    4790  557.96    4800  555.87
    4830  555.09    4910  556.75    4940  555.24    4970  555.59  4997.5   553.4
  5008.9  553.24  5014.4  554.23  5032.3  550.97  5037.8  552.55  5038.3  550.59
  5038.8  550.09  5048.9  550.59  5054.6  552.37  5058.3  554.85  5061.2   556.8
  5066.6  553.44  5084.6  557.34    5090  556.31  5098.2  557.28  5150.8  556.37
  5212.4  556.24  5259.2  559.32    5576  566.65  5707.5  570.73  5873.2  580.49
#Mann= 7 ,-1 , 0
    4700     .07       0  5014.4     .12       0  5038.3     .05       0
  5048.9     .12       0  5058.3     .07       0  5150.8     .12       0
    5576     .07       0
Bank Sta=5038.3,5048.9
XS Rating Curve= 0 ,0
Exp/Cntr=0.3,0.1

Type RM Length L Ch R = 1 ,24417   ,426,426,426
BEGIN DESCRIPTION:
YOUNGS CREEK 39.0
END DESCRIPTION:
XS GIS Cut Line= 3
      2259925.01     13766424.98        2260175.       13766025.
      2259524.97     13765224.97
#Sta/Elev= 30
  4527.5  574.66  4621.8  568.02  4644.8  564.71  4650.7  565.19  4716.2   561.3
  4723.8  559.79  4775.1  556.94  4869.5  555.53  4891.3  554.28  4912.5  555.19
  4940.2  553.62  4963.8  553.99  4985.6  549.46  4991.5  549.59  4996.2  553.27
  5006.4   554.4  5012.8  552.27  5020.7  554.43  5035.1  550.92    5036  548.84
  5036.5  548.34    5047  548.84  5049.5  550.97  5055.9  551.93  5063.6  555.02
  5105.6  554.65  5241.3  553.93  5741.9  566.02  5810.2   568.3    6030   583.9
#Mann= 5 ,-1 , 0
  4527.5     .07       0    5036     .05       0    5047     .07       0
  5105.6     .12       0  5741.9     .07       0
Bank Sta=5036,5047
XS Rating Curve= 0 ,0
Exp/Cntr=0.3,0.1

Type RM Length L Ch R = 1 ,23991   ,470,470,470
BEGIN DESCRIPTION:
YOUNGS CREEK 38.0
END DESCRIPTION:
XS GIS Cut Line= 3
      2260375.01     13766624.97        2260525.       13765925.
      2259725.02     13765125.02
#Sta/Elev= 30
  4280.3  569.14    4396  566.88  4640.8  555.74  4687.9  554.68  4851.7  554.23
  4951.7  553.43  4965.5  552.24  4971.4  550.36  4985.9  553.45  4993.6  550.67
  4999.7  550.67  5004.8  547.01  5005.3  546.51  5015.8  547.01  5024.4  548.69
  5038.6  549.22  5052.7   553.4  5066.9  553.94  5095.2  554.05  5137.6  552.35
  5208.3  553.05  5250.7  551.89  5260.2  552.69  5321.4  554.12  5519.4  553.84
  5597.2  554.96  5802.3  563.63  5942.9  571.08  6014.4  574.58  6127.5  582.65
#Mann= 9 ,-1 , 0
  4280.3     .07       0    4396    .035       0  4687.9    .045       0
  4851.7     .07       0  4951.7    .035       0  5004.8    .035       0
  5015.8    .035       0  5260.2     .12       0  5942.9     .07       0
Bank Sta=5004.8,5015.8
XS Rating Curve= 0 ,0
Exp/Cntr=0.3,0.1

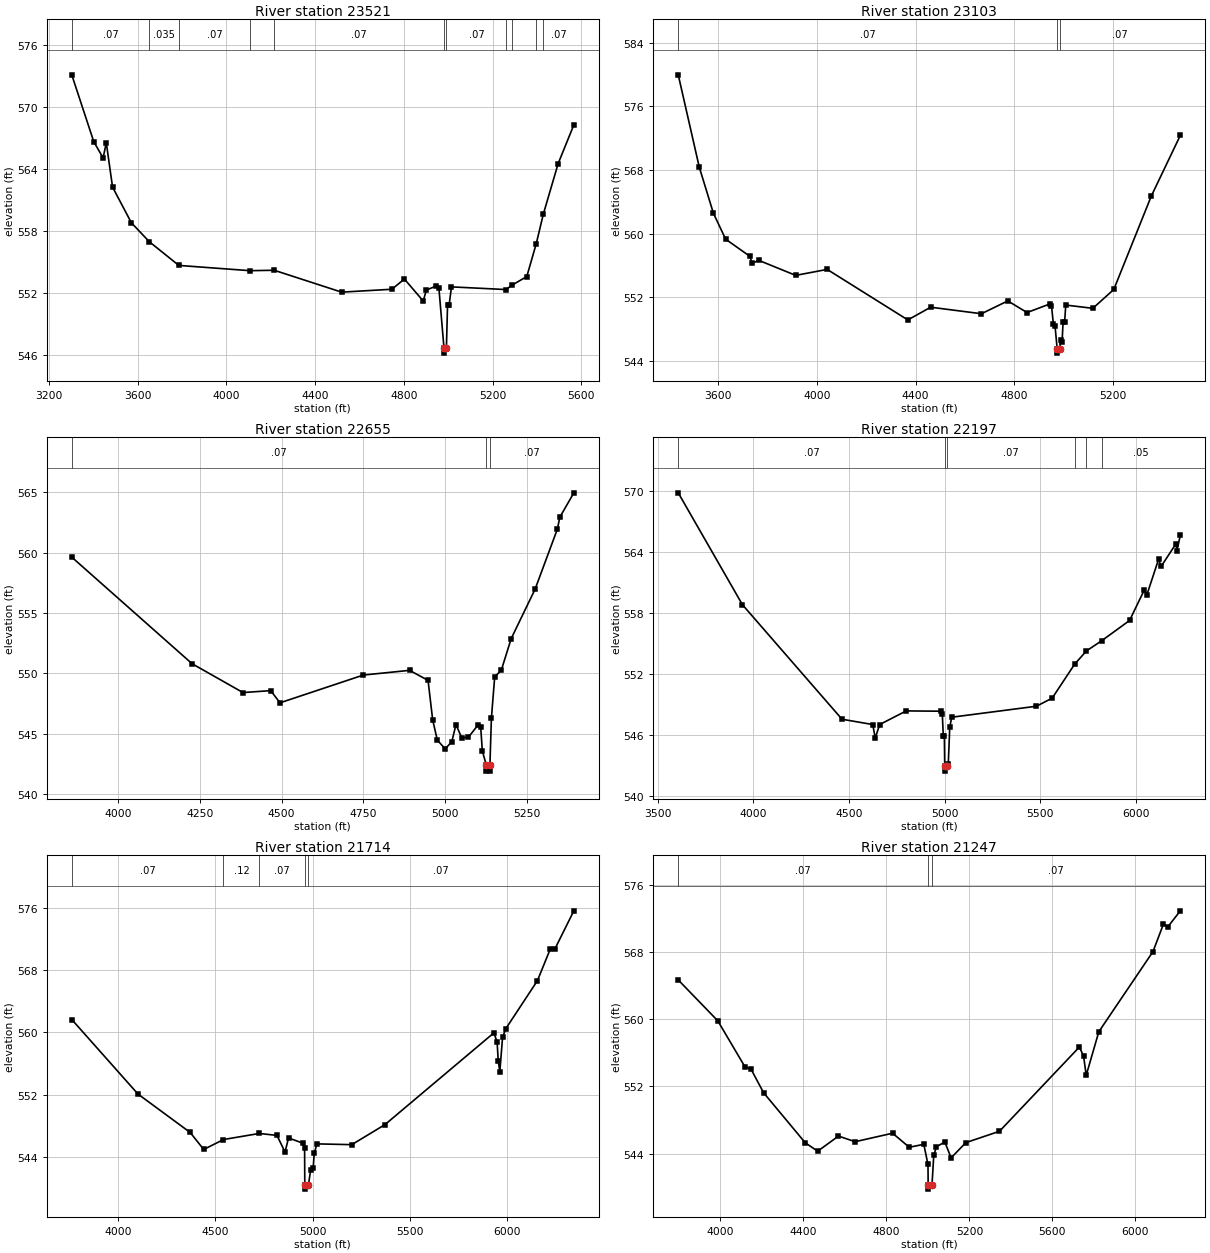
Type RM Length L Ch R = 1 ,23521   ,418,418,418
BEGIN DESCRIPTION:
YOUNGS CREEK 37.0
END DESCRIPTION:
XS GIS Cut Line= 3
      2261774.98     13766774.98        2260575.       13765575.
      2260175.01     13765175.01
#Sta/Elev= 30
  3303.2  573.12  3402.2  566.65  3444.6  565.06  3458.7  566.55    3487  562.24
  3571.9  558.78  3652.5  556.95  3785.7  554.65    4106  554.14  4215.6  554.18
  4519.4  552.06  4745.7  552.34  4802.2  553.33  4887.1   551.2  4901.2  552.26
  4943.7  552.64  4957.8  552.44  4980.6  546.65  4981.1  546.15  4991.6  546.65
  4996.7  550.81  5003.8  550.81  5014.4  552.57  5261.3  552.31    5285  552.71
  5353.8  553.57  5396.5  556.76  5428.5  559.63  5495.2  564.52  5565.9  568.27
#Mann= 11 ,-1 , 0
  3303.2     .07       0  3652.5    .035       0  3785.7     .07       0
    4106    .035       0  4215.6     .07       0  4980.6     .05       0
  4991.6     .07       0  5261.3     .12       0    5285     .07       0
  5396.5     .12       0  5428.5     .07       0
Bank Sta=4980.6,4991.6
XS Rating Curve= 0 ,0
Exp/Cntr=0.3,0.1

Type RM Length L Ch R = 1 ,23103   ,448,448,448
BEGIN DESCRIPTION:
YOUNGS CREEK 36.0
END DESCRIPTION:
XS GIS Cut Line= 3
      2261874.98     13766224.98        2260675.       13765225.
      2260275.02     13764975.01
#Sta/Elev= 30
  3438.5  579.94  3523.7  568.34    3581  562.54  3630.5  559.29  3729.4  557.12
  3737.2  556.25  3764.6  556.63  3914.3  554.74  4041.8  555.49  4368.5  549.14
    4461  550.74  4666.6  549.92  4773.4  551.53  4851.5  550.07  4943.9  551.15
  4950.4  550.94  4958.2  548.59  4964.7  548.41  4973.5  545.47    4974  544.97
  4984.5  545.47  4986.9  546.58  4993.4  546.43  4997.3  548.82  5003.5  548.82
  5008.2  551.01  5117.9   550.6  5202.8  552.97  5354.9  564.72  5472.2  572.33
#Mann= 3 ,-1 , 0
  3438.5     .07       0  4973.5     .05       0  4984.5     .07       0
Bank Sta=4973.5,4984.5
XS Rating Curve= 0 ,0
Exp/Cntr=0.3,0.1

Type RM Length L Ch R = 1 ,22655   ,458,458,458
BEGIN DESCRIPTION:
YOUNGS CREEK 35.0
END DESCRIPTION:
XS GIS Cut Line= 3
        2261675.       13765725.        2260875.       13764925.
      2260474.98       13764875.
#Sta/Elev= 30
  3858.8  559.64  4226.5  550.81  4382.1  548.42  4466.9  548.58  4495.2  547.57
  4749.8  549.87  4891.2  550.26  4947.7  549.43  4961.9  546.15    4976  544.48
  5000.2  543.75  5020.4  544.36    5033  545.76  5050.6  544.68  5070.8  544.71
    5101  545.75  5108.6  545.56  5113.6  543.59  5125.7  542.41  5126.2  541.91
  5136.3  541.91  5136.8  542.41  5141.3  546.29  5151.4  549.72  5171.6  550.27
  5201.8  552.89  5274.9  556.99  5342.9  561.96  5350.5  562.95  5393.3  564.97
#Mann= 3 ,-1 , 0
  3858.8     .07       0  5125.7     .05       0  5136.8     .07       0
Bank Sta=5125.7,5136.8
XS Rating Curve= 0 ,0
Exp/Cntr=0.3,0.1

Type RM Length L Ch R = 1 ,22197   ,483,483,483
BEGIN DESCRIPTION:
YOUNGS CREEK 34.0
END DESCRIPTION:
XS GIS Cut Line= 3
      2261925.02     13765925.04        2261225.       13764725.
      2260025.02     13764425.01
#Sta/Elev= 30
  3606.9   569.8  3942.7   558.8  4463.6  547.54  4624.5  547.02  4637.3  545.68
  4660.5  547.02  4799.4  548.36  4982.5  548.33  4988.3  548.01  4993.3  545.91
  4998.8  545.91  5000.9  542.94  5001.4  542.44    5012  542.94  5019.4  543.13
  5027.1  546.75  5037.4  547.74  5480.7  548.82  5563.1  549.62  5680.6  552.96
  5742.3  554.26    5822  555.26  5967.7  557.25    6045  560.26  6057.9  559.75
  6119.7  563.28  6132.6  562.56  6209.9  564.78  6215.1  564.08  6233.1  565.63
#Mann= 6 ,-1 , 0
  3606.9     .07       0  5000.9     .05       0    5012     .07       0
  5680.6     .05       0  5742.3     .07       0    5822     .05       0
Bank Sta=5000.9,5012
XS Rating Curve= 0 ,0
Exp/Cntr=0.3,0.1

Type RM Length L Ch R = 1 ,21714   ,467,467,467
BEGIN DESCRIPTION:
YOUNGS CREEK 33.0
END DESCRIPTION:
XS GIS Cut Line= 3
      2261824.99     13765674.96        2261525.       13764475.
      2262124.99     13763275.03
#Sta/Elev= 30
  3763.1  561.66  4103.2  552.07  4371.2  547.13  4440.8  544.94  4542.3  546.22
  4726.1     547    4817  546.75  4858.3   544.6  4876.3  546.43  4948.5  545.76
  4958.8   545.1  4959.8  540.34  4960.3  539.84  4978.3  540.34  4989.7  542.26
  5002.8  542.55  5008.4  544.46  5022.3  545.66  5201.2  545.56  5371.7  548.14
  5930.8  559.94  5947.5  558.78  5953.1  556.38  5961.5  554.95  5975.5  559.36
  5992.2  560.48  6154.4  566.65  6221.4  570.78  6243.8  570.71  6341.6  575.64
#Mann= 5 ,-1 , 0
  3763.1     .07       0  4542.3     .12       0  4726.1     .07       0
  4959.8     .05       0  4978.3     .07       0
Bank Sta=4959.8,4978.3
XS Rating Curve= 0 ,0
Exp/Cntr=0.3,0.1

Type RM Length L Ch R = 1 ,21247   ,482,482,482
BEGIN DESCRIPTION:
YOUNGS CREEK 32.0
END DESCRIPTION:
XS GIS Cut Line= 3
        2261875.     13765724.95        2261975.       13764525.
      2262175.01     13763324.96
#Sta/Elev= 30
  3796.3  564.66  3986.9   559.8  4117.4  554.35  4147.5  554.04  4207.7  551.25
  4408.4   545.3  4468.6  544.29  4568.9  546.09  4649.2  545.42  4829.8  546.43
  4910.1  544.76  4980.3  545.11  5000.4  542.71  5001.3  540.28  5001.8  539.78
  5019.8  540.28  5028.3  543.79    5041  544.81  5081.5  545.39  5111.9   543.5
  5182.9  545.31  5345.1  546.66  5730.3  556.68  5750.6  555.61  5763.3  553.32
  5824.1   558.5  6085.2  568.03  6135.9  571.32  6156.1  570.95    6217  572.88
#Mann= 3 ,-1 , 0
  3796.3     .07       0  5001.3     .05       0  5019.8     .07       0
Bank Sta=5001.3,5019.8
XS Rating Curve= 0 ,0
Exp/Cntr=0.3,0.1

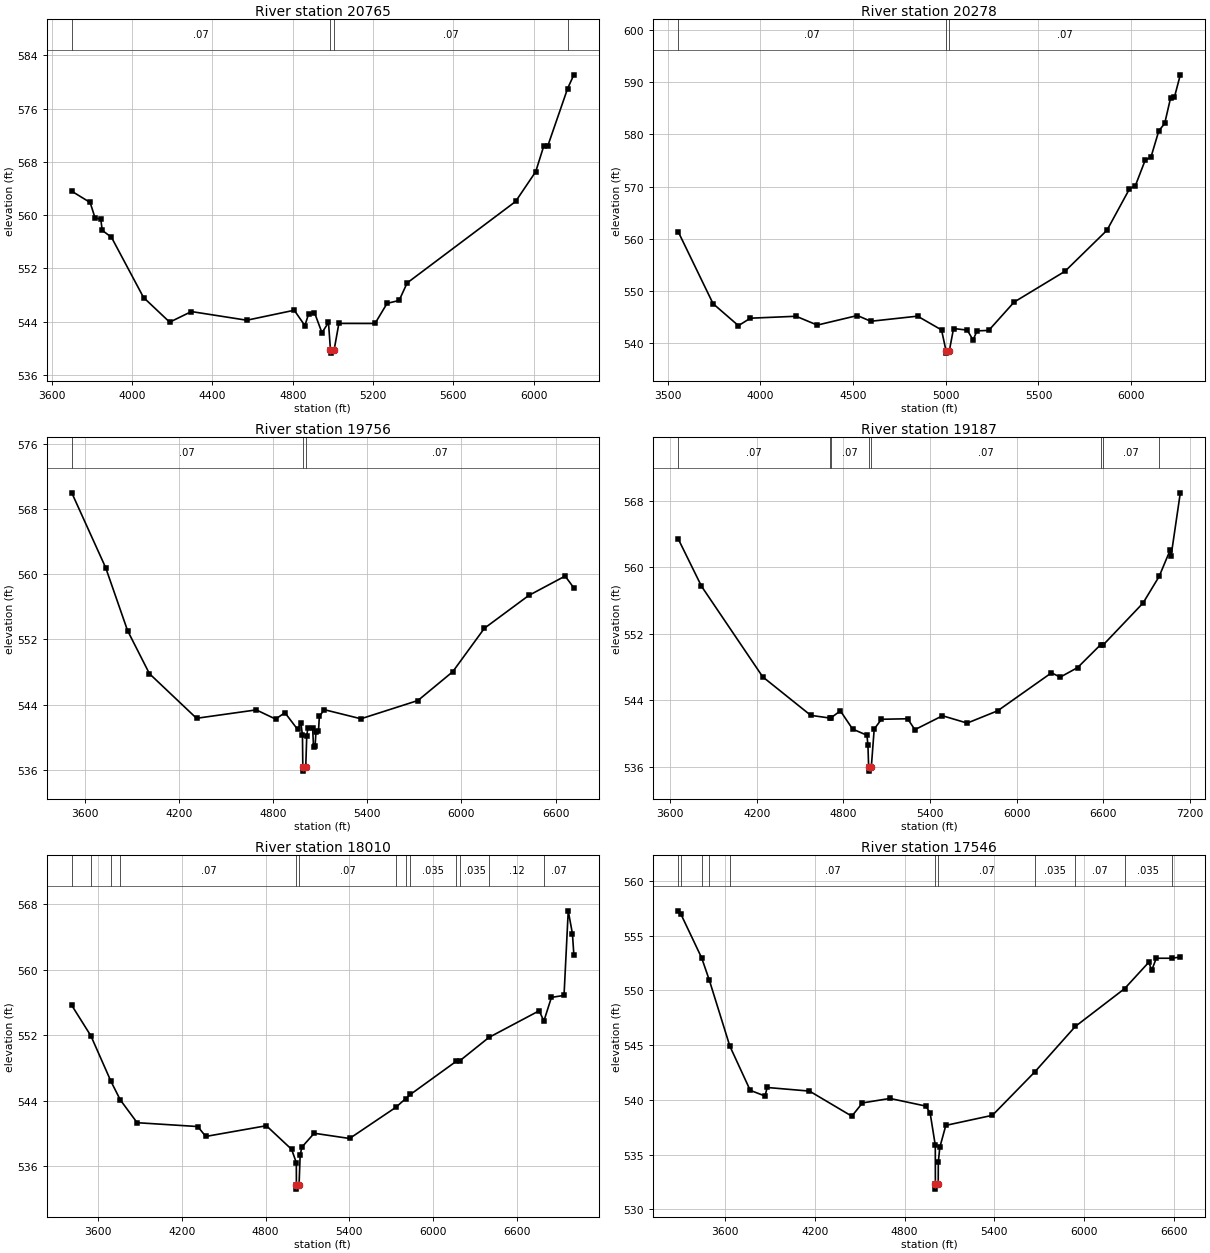
Type RM Length L Ch R = 1 ,20765   ,487,487,487
BEGIN DESCRIPTION:
YOUNGS CREEK 31.0
END DESCRIPTION:
XS GIS Cut Line= 3
        2261925.       13765625.        2262425.       13764425.
        2262425.       13763225.
#Sta/Elev= 30
  3699.6  563.58  3791.1  561.89    3815  559.62  3844.2  559.34  3851.3  557.71
  3897.3  556.66  4057.1  547.62  4187.1  543.92  4295.4  545.51  4571.1  544.21
  4807.3  545.71  4860.4   543.4  4878.8  545.15  4908.1  545.36  4945.4  542.33
  4977.9  543.87  4987.6  539.77  4988.1  539.27  5006.1  539.77  5029.6  543.73
  5209.6  543.72  5269.6  546.74  5329.6  547.18  5369.6  549.81  5909.6  562.04
  6009.6  566.51  6049.6  570.35  6069.6  570.36  6168.5     579  6199.6  581.06
#Mann= 4 ,-1 , 0
  3699.6     .07       0  4987.6     .05       0  5006.1     .07       0
  6168.5    .035       0
Bank Sta=4987.6,5006.1
XS Rating Curve= 0 ,0
Exp/Cntr=0.3,0.1

Type RM Length L Ch R = 1 ,20278   ,522,522,522
BEGIN DESCRIPTION:
YOUNGS CREEK 30.0
END DESCRIPTION:
XS GIS Cut Line= 3
        2262075.       13765525.        2262875.       13764325.
      2262475.01     13763125.03
#Sta/Elev= 30
  3557.7  561.36  3745.5  547.59  3882.2  543.38  3946.8  544.81  4193.2  545.18
  4307.4  543.49  4523.7  545.32  4595.8  544.22  4848.2   545.2  4977.4  542.56
  5001.2  538.62  5001.7  538.12  5019.7  538.62  5042.1  542.83  5115.9  542.53
  5147.5  540.64  5168.6  542.38  5231.8  542.47  5368.9   547.9  5642.9  553.79
  5869.5  561.66  5990.8  569.58  6022.4  570.18  6075.1  575.04  6106.7  575.67
  6148.9   580.7  6180.5   582.1  6212.1  586.96  6233.2  587.16  6264.8  591.42
#Mann= 3 ,-1 , 0
  3557.7     .07       0  5001.2     .05       0  5019.7     .07       0
Bank Sta=5001.2,5019.7
XS Rating Curve= 0 ,0
Exp/Cntr=0.3,0.1

Type RM Length L Ch R = 1 ,19756   ,569,569,569
BEGIN DESCRIPTION:
H21808
END DESCRIPTION:
XS GIS Cut Line= 3
      2262511.83     13765837.22      2263363.65     13764363.29
      2263172.25     13762879.95
#Sta/Elev= 30
  3517.9  569.96  3734.1  560.77  3873.3  553.06  4012.6  547.78  4312.6  542.31
  4693.1  543.34  4816.5  542.21  4875.4     543  4955.8  540.96  4977.3  541.72
  4987.3  540.21  4989.6  536.33  4990.1  535.83  5008.2  536.33  5014.6  540.14
  5021.9  541.15    5052  541.15  5057.7  538.84  5067.7  538.88  5073.5  540.68
  5089.3  540.74    5095  542.53  5125.9  543.37  5359.7  542.25  5722.7  544.49
  5944.5  548.02  6146.2  553.35  6428.5  557.37  6660.4  559.75  6715.9   558.3
#Mann= 3 ,-1 , 0
  3517.9     .07       0  4989.6     .05       0  5008.2     .07       0
Bank Sta=4989.6,5008.2
XS Rating Curve= 0 ,0
Exp/Cntr=0.3,0.1

Type RM Length L Ch R = 1 ,19187   ,1177,1177,1177
BEGIN DESCRIPTION:
YOUNGS CREEK 29.0
END DESCRIPTION:
XS GIS Cut Line= 3
      2262770.24     13765818.07      2263689.05     13764841.83
      2263937.72     13762718.56
#Sta/Elev= 30
  3656.4  563.39  3817.5  557.71    4242  546.82  4574.6   542.2  4709.1  541.87
  4712.9  541.88  4779.7  542.74  4864.6  540.55  4963.8  539.81  4970.6  538.62
  4975.5     536    4976   535.5  4994.1     536    5014  540.55  5064.3  541.73
  5245.5  541.79  5295.9  540.48  5487.2  542.15  5658.3  541.27  5869.8  542.75
  6242.3  547.31  6302.7  546.79  6423.5  547.94  6582.9  550.69  6597.4   550.6
  6876.6  555.69  6988.2  558.89  7065.6   562.1  7070.7  561.33  7134.8  568.93
#Mann= 8 ,-1 , 0
  3656.4     .07       0  4709.1    .035       0  4712.9     .07       0
  4975.5     .05       0  4994.1     .07       0  6582.9    .035       0
  6597.4     .07       0  6988.2    .035       0
Bank Sta=4975.5,4994.1
XS Rating Curve= 0 ,0
Exp/Cntr=0.3,0.1

Type RM Length L Ch R = 1 ,18010   ,464,464,464
BEGIN DESCRIPTION:
YOUNGS CREEK 28.0
END DESCRIPTION:
XS GIS Cut Line= 3
      2263507.21     13766057.31        2264375.       13764725.
        2264575.     13762724.98
#Sta/Elev= 30
    3410  555.63  3547.3   551.9  3691.4  546.33  3757.8  544.08  3878.7  541.29
  4313.3  540.82  4370.7  539.61  4805.4  540.92  4986.5  538.03  5020.1   536.4
  5020.7  533.67  5021.2  533.17  5039.7  533.67  5047.7  537.35  5060.3  538.31
  5148.2     540    5402  539.36    5732  543.15  5804.3  544.23  5837.6  544.74
  6167.9  548.81  6193.9  548.88  6400.8  551.71  6761.2  554.97  6795.3  553.72
  6849.2  556.61  6939.6  556.85  6969.8  567.19  6999.9  564.39    7010  561.83
#Mann= 13 ,-1 , 0
    3410    .035       0  3547.3     .07       0  3691.4    .035       0
  3757.8     .07       0  5020.7     .05       0  5039.7     .07       0
    5732    .035       0  5804.3     .07       0  5837.6    .035       0
  6167.9     .07       0  6193.9    .035       0  6400.8     .12       0
  6795.3     .07       0
Bank Sta=5020.7,5039.7
XS Rating Curve= 0 ,0
Exp/Cntr=0.3,0.1

Type RM Length L Ch R = 1 ,17546   ,906,906,906
BEGIN DESCRIPTION:
YOUNGS CREEK 27.0
END DESCRIPTION:
XS GIS Cut Line= 3
      2263525.01     13766124.99        2264725.       13764925.
        2264575.     13763275.05
#Sta/Elev= 30
  3288.3  557.26  3305.7  556.97  3445.2  552.95  3496.4  550.91  3632.9  544.91
  3769.1  540.87  3868.1  540.35  3882.3  541.13  4165.1   540.8  4447.9  538.51
  4518.7  539.72  4702.5  540.13  4942.9  539.43  4971.2  538.78  5005.4  535.85
    5006  532.35  5006.5  531.85    5025  532.35  5025.5  534.31  5035.5  535.66
  5075.7  537.67    5387  538.59    5670  542.55  5940.5   546.7  6269.6  550.15
  6431.3  552.56  6451.4  551.84  6481.5  552.93  6583.8  552.93  6642.1  553.04
#Mann= 11 ,-1 , 0
  3288.3     .07       0  3305.7    .035       0  3445.2     .07       0
  3496.4    .035       0  3632.9     .07       0    5006     .05       0
    5025     .07       0    5670    .035       0  5940.5     .07       0
  6269.6    .035       0  6583.8     .12       0
Bank Sta=5006,5025
XS Rating Curve= 0 ,0
Exp/Cntr=0.3,0.1

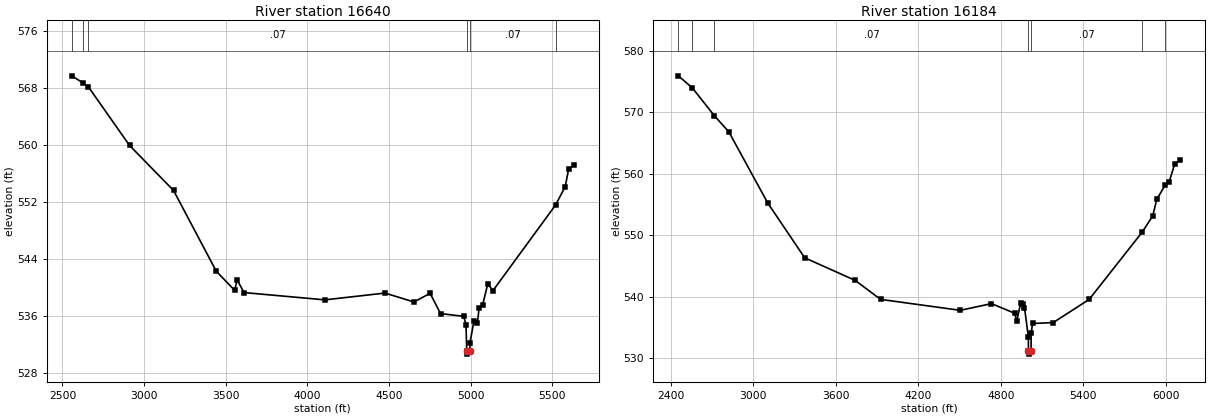
Type RM Length L Ch R = 1 ,16640   ,456,456,456
BEGIN DESCRIPTION:
YOUNGS CREEK 26.0
END DESCRIPTION:
XS GIS Cut Line= 3
      2263624.99     13766775.01        2265275.       13764975.
        2265475.     13764374.99
#Sta/Elev= 30
  2556.9  569.68  2623.6  568.72  2658.2  568.15  2910.5  559.94    3180  553.63
  3441.5  542.33  3554.9  539.62  3569.1  541.12  3611.6  539.33  4106.8  538.31
  4474.9  539.26  4651.9  538.01  4751.2  539.22  4814.7  536.39  4956.5     536
  4970.7  534.85  4975.4  531.21  4975.9  530.71  4994.4  531.21  4995.3  532.29
  5019.8  535.41  5040.9  535.11  5051.4  537.22  5072.5  537.59  5104.1  540.54
  5135.8   539.6  5519.3  551.59  5578.5  554.18  5599.6  556.67  5631.2  557.14
#Mann= 6 ,-1 , 0
  2556.9     .07       0  2623.6    .035       0  2658.2     .07       0
  4975.4     .05       0  4994.4     .07       0  5519.3    .035       0
Bank Sta=4975.4,4994.4
XS Rating Curve= 0 ,0
Exp/Cntr=0.3,0.1

Type RM Length L Ch R = 1 ,16184   ,456,456,456
BEGIN DESCRIPTION:
YOUNGS CREEK 25.0
END DESCRIPTION:
XS GIS Cut Line= 3
      2263624.99     13767175.01        2265425.       13765375.
        2265525.     13764275.04
#Sta/Elev= 30
  2454.4  575.92  2556.1  573.98    2718  569.41  2822.1  566.82    3105  555.25
  3373.7  546.34  3741.3  542.66  3925.2  539.58    4505   537.8  4731.3  538.89
    4901  537.32  4915.1     536  4943.4  538.95  4957.6  538.82  4971.7  538.24
    5000  533.42  5000.4  531.18  5000.9  530.68  5019.7  531.18  5020.1  534.06
  5030.1  535.66  5180.7  535.81  5441.8  539.57  5825.8  550.47  5903.7  553.13
  5933.8  555.86  5995.8   558.2  6024.2  558.74  6064.4  561.65  6104.5  562.21
#Mann= 7 ,-1 , 0
  2454.4     .07       0  2556.1    .035       0    2718     .07       0
  5000.4     .05       0  5019.7     .07       0  5825.8    .035       0
  5995.8     .07       0
Bank Sta=5000.4,5019.7
XS Rating Curve= 0 ,0
Exp/Cntr=0.3,0.1