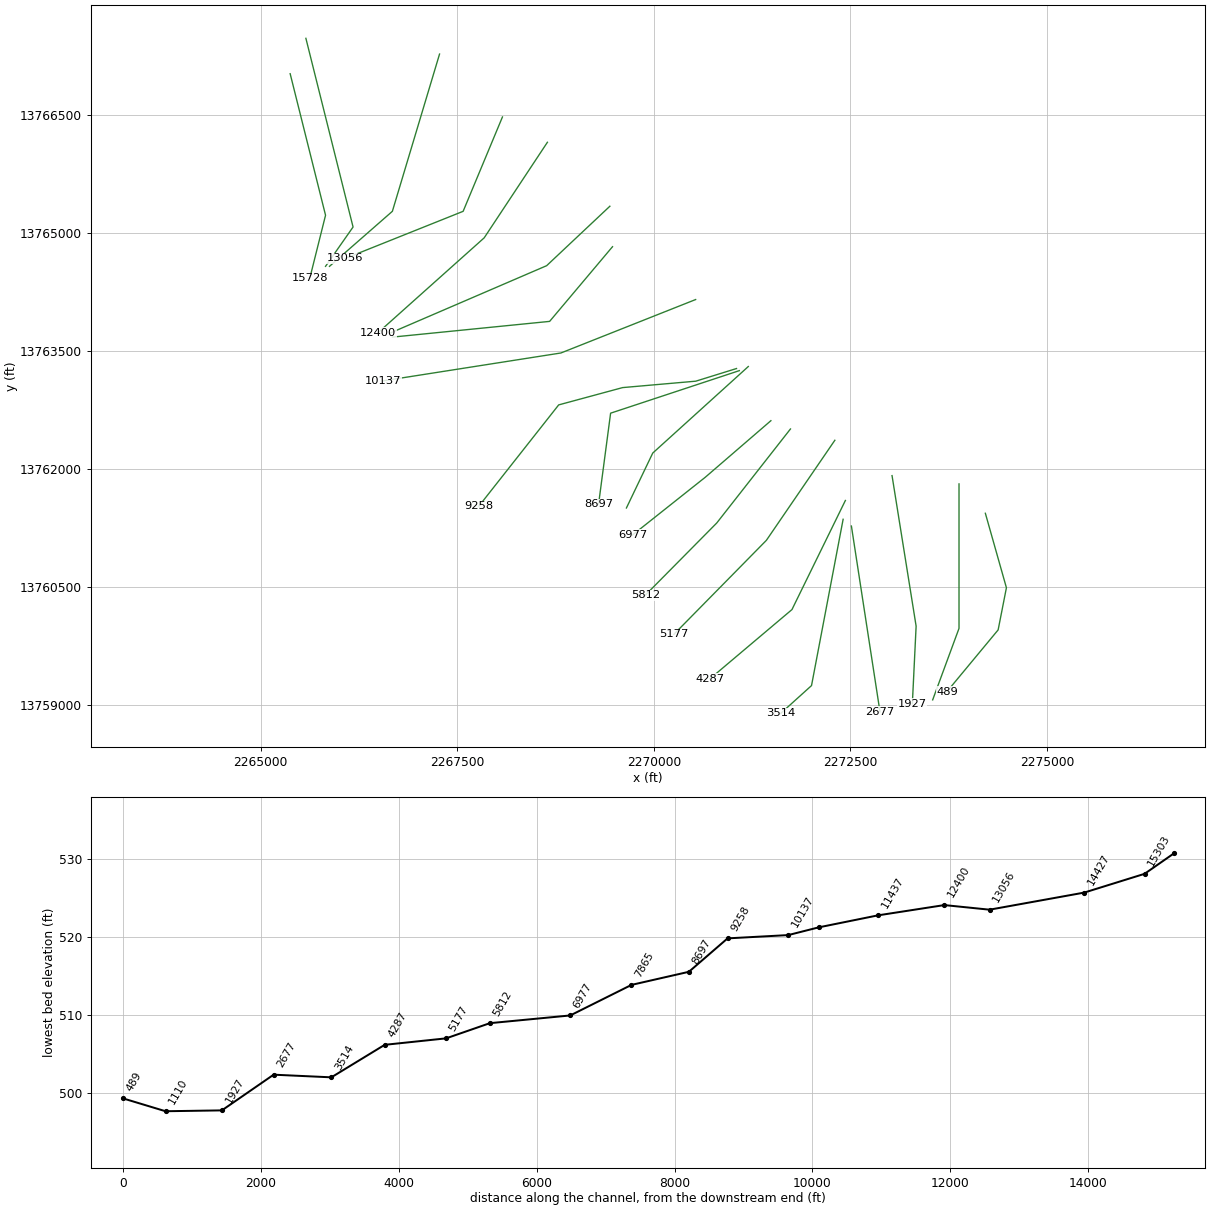
HEC-RAS study YOUNGS CREEK.prj: YOUNGS CREEK Base Level Engineering

--- YOUNGS CREEK.g01 (geometry) --- (continued)

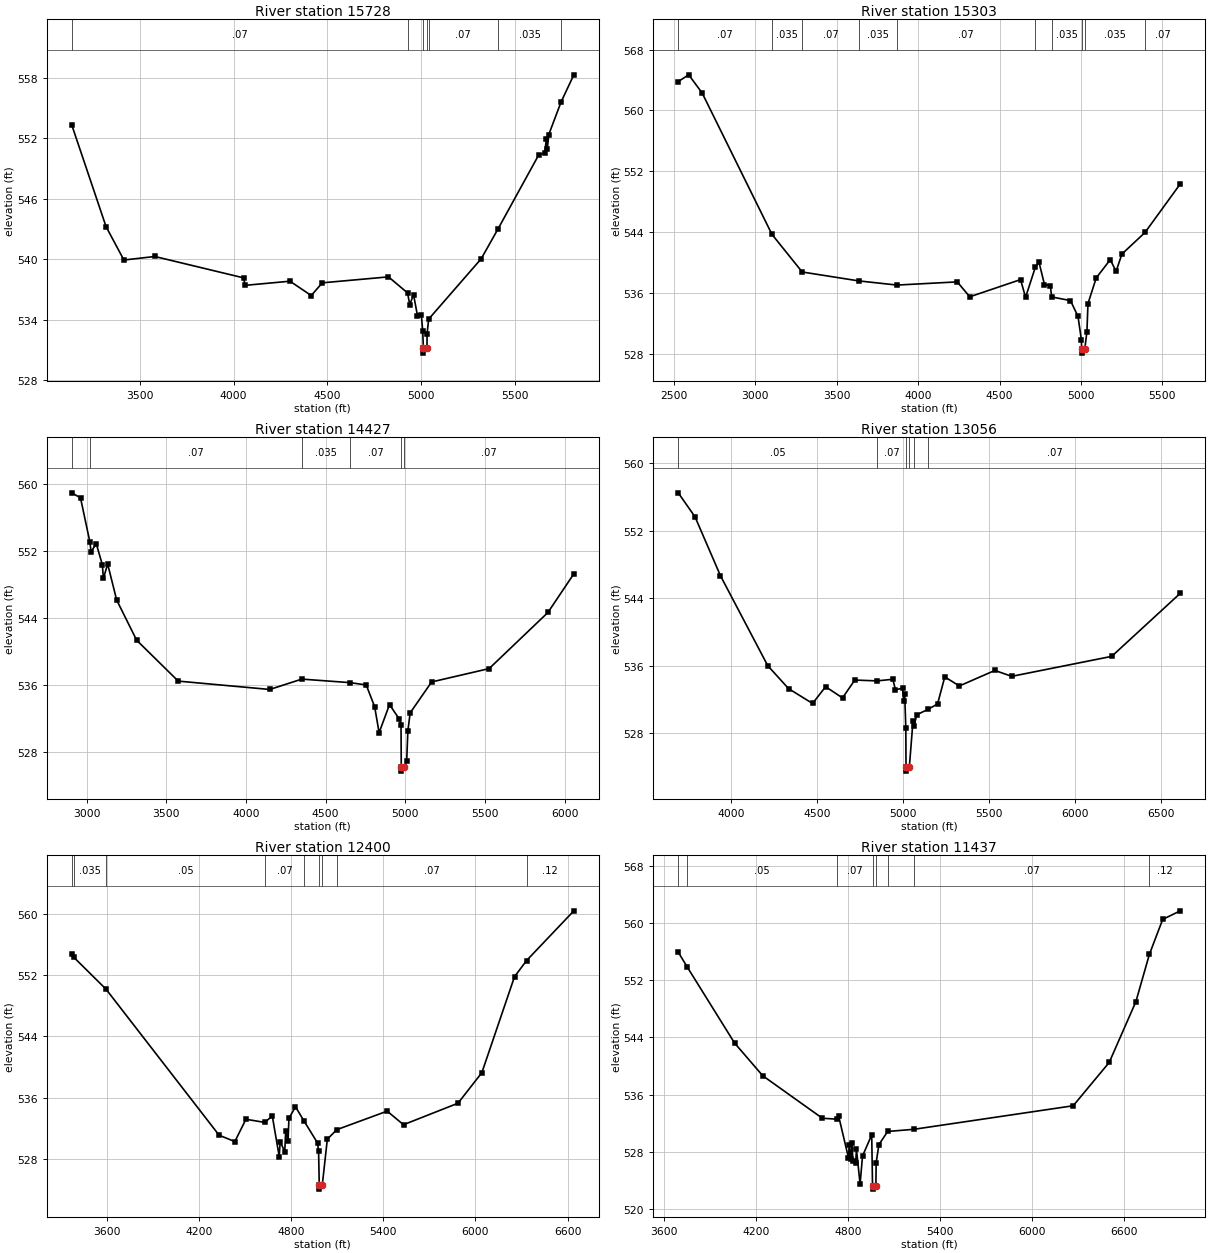
Type RM Length L Ch R = 1 ,15728   ,425,425,425
BEGIN DESCRIPTION:
YOUNGS CREEK 24.0
END DESCRIPTION:
XS GIS Cut Line= 3
        2265375.       13767025.        2265825.       13765225.
      2265625.01     13764425.02
#Sta/Elev= 30
  3136.3  553.32  3319.3  543.24  3414.6  539.93  3579.5  540.28  4053.7  538.16
  4061.4  537.42  4301.1  537.83  4414.5  536.41  4473.7  537.67  4826.8  538.26
  4928.7  536.67  4940.2  535.52  4960.8  536.49  4981.4  534.43    5002   534.5
  5009.7  532.89    5013   531.2  5013.5   530.7  5032.3   531.2  5032.9  532.62
  5041.3  534.07  5321.6  540.05  5411.2     543  5628.2  550.33  5661.7  550.58
  5669.4  551.95  5674.6  550.93  5682.3  552.36  5748.6  555.62  5816.3  558.29
#Mann= 7 ,-1 , 0
  3136.3     .07       0  4928.7     .12       0    5013     .05       0
  5032.3     .12       0  5041.3     .07       0  5411.2    .035       0
  5748.6     .07       0
Bank Sta=5013,5032.3
XS Rating Curve= 0 ,0
Exp/Cntr=0.3,0.1

Type RM Length L Ch R = 1 ,15303   ,876,876,876
BEGIN DESCRIPTION:
YOUNGS CREEK 23.0
END DESCRIPTION:
XS GIS Cut Line= 3
        2265575.     13767475.01        2266175.       13765075.
        2265825.       13764575.
#Sta/Elev= 30
    2526   563.8  2590.4  564.68  2672.9  562.29  3101.6   543.7  3287.5  538.75
  3634.4  537.58  3869.7  537.03  4239.7  537.45    4317  535.49  4628.8  537.75
  4659.7  535.42  4719.2  539.35  4742.2  540.04  4775.7   537.1  4811.8  536.96
    4820  535.47  4935.5  534.99  4981.8   532.9  5002.9  529.78  5003.7  528.58
  5004.2  528.08  5023.1  528.58  5036.5   530.9    5043  534.59  5093.6  537.97
  5179.9  540.37  5215.7  538.83  5251.4  541.11  5393.5  543.95  5610.2  550.34
#Mann= 10 ,-1 , 0
    2526     .07       0  3101.6    .035       0  3287.5     .07       0
  3634.4    .035       0  3869.7     .07       0  4719.2     .12       0
    4820    .035       0  5003.7    .035       0  5023.1    .035       0
  5393.5     .07       0
Bank Sta=5003.7,5023.1
XS Rating Curve= 0 ,0
Exp/Cntr=0.3,0.1

Type RM Length L Ch R = 1 ,14427   ,1371,1371,1371
BEGIN DESCRIPTION:
YOUNGS CREEK 22.0
END DESCRIPTION:
XS GIS Cut Line= 3
      2267274.99     13767274.96        2266675.       13765275.
      2265875.03     13764575.02
#Sta/Elev= 30
  2906.7     559  2961.5   558.4  3020.6  553.09  3027.6  551.97  3060.7  552.89
  3098.9  550.37    3105  548.74    3132  550.47  3188.5  546.16  3313.8  541.35
  3574.8  536.45  4149.1  535.45  4350.4  536.69  4651.9  536.27  4754.6  535.99
  4807.7  533.38  4835.5  530.27  4900.8  533.64  4963.4  531.87    4973  531.23
  4974.6  526.17  4975.1  525.67    4994  526.17  5008.5  526.85  5016.1   530.5
  5030.3  532.64  5165.1  536.35  5526.2  537.95    5895  544.67  6057.7   549.3
#Mann= 6 ,-1 , 0
  2906.7    .035       0  3020.6     .07       0  4350.4    .035       0
  4651.9     .07       0  4974.6     .05       0    4994     .07       0
Bank Sta=4974.6,4994
XS Rating Curve= 0 ,0
Exp/Cntr=0.3,0.1

Type RM Length L Ch R = 1 ,13056   ,656,656,656
BEGIN DESCRIPTION:
YOUNGS CREEK 21.0
END DESCRIPTION:
XS GIS Cut Line= 3
      2268075.02     13766475.04        2267575.       13765275.
      2266074.99       13764675.
#Sta/Elev= 30
  3694.3  556.51  3791.8  553.66  3939.7  546.66  4214.3  535.99  4335.1  533.27
  4474.3  531.51  4550.2   533.5  4648.2  532.17  4719.7  534.29    4848  534.19
  4940.2  534.38  4955.9  533.13    4997  533.33  5003.8  531.82  5009.2  532.64
  5015.9  528.59    5017  523.98  5017.5  523.48  5036.4  523.98  5057.6  529.43
  5061.5  528.78  5080.5  530.18  5146.8  530.83  5200.3  531.46  5242.1  534.66
  5326.9  533.59  5532.9  535.43  5631.1  534.73  6211.4   537.1  6609.9  544.59
#Mann= 6 ,-1 , 0
  3694.3     .05       0    4848     .07       0    5017     .05       0
  5036.4     .07       0  5061.5     .12       0  5146.8     .07       0
Bank Sta=5017,5036.4
XS Rating Curve= 0 ,0
Exp/Cntr=0.3,0.1

Type RM Length L Ch R = 1 ,12400   ,963,963,963
BEGIN DESCRIPTION:
YOUNGS CREEK 20.0
END DESCRIPTION:
XS GIS Cut Line= 3
      2268646.66     13766152.97      2267842.74     13764937.53
      2266493.29     13763731.64
#Sta/Elev= 30
  3373.8  554.77  3385.7  554.33  3596.8  550.14  4332.5   531.1  4434.8  530.27
  4507.1  533.18  4629.9  532.77  4678.5  533.62  4723.7  528.32  4729.7  530.26
  4759.8  528.95  4765.8  531.67  4780.9  530.35  4786.9  533.31  4829.6  534.81
    4887  532.89  4973.1  530.09  4979.8  529.04  4984.3  524.57  4984.8  524.07
  5003.7  524.57  5036.7  530.58    5098  531.82  5426.2  534.24  5532.4  532.47
  5886.8  535.27  6042.3  539.26  6254.7  551.77  6332.9  553.87  6640.8  560.36
#Mann= 9 ,-1 , 0
  3373.8    .045       0  3385.7    .035       0  3596.8     .05       0
  4629.9     .07       0    4887     .12       0  4984.3     .05       0
  5003.7     .12       0    5098     .07       0  6332.9     .12       0
Bank Sta=4984.3,5003.7
XS Rating Curve= 0 ,0
Exp/Cntr=0.3,0.1

Type RM Length L Ch R = 1 ,11437   ,859,859,859
BEGIN DESCRIPTION:
YOUNGS CREEK 19.0
END DESCRIPTION:
XS GIS Cut Line= 3
      2269441.06     13765339.51      2268637.11     13764583.42
      2266638.39     13763722.72
#Sta/Elev= 30
  3690.6  555.95  3749.6  553.86  4058.8  543.21  4242.9  538.63  4632.1  532.68
  4728.4  532.55  4738.1  533.01  4802.4  527.17  4807.9  528.96  4818.3  526.92
    4826  529.19  4831.4  526.64  4849.5  526.44  4854.9  528.32  4878.5  523.46
  4894.5  527.39  4954.5  530.35  4959.8  523.25  4960.3  522.75  4981.7  523.25
  4983.5  526.45  5001.6  528.99  5058.8  530.83  5229.7  531.13  6270.6  534.43
  6505.9   540.5  6680.1  549.01  6768.2  555.63  6855.3  560.54  6970.4  561.74
#Mann= 8 ,-1 , 0
  3690.6    .045       0  3749.6     .05       0  4728.4     .07       0
  4959.8     .05       0  4981.7     .07       0  5058.8     .12       0
  5229.7     .07       0  6768.2     .12       0
Bank Sta=4959.8,4981.7
XS Rating Curve= 0 ,0
Exp/Cntr=0.3,0.1

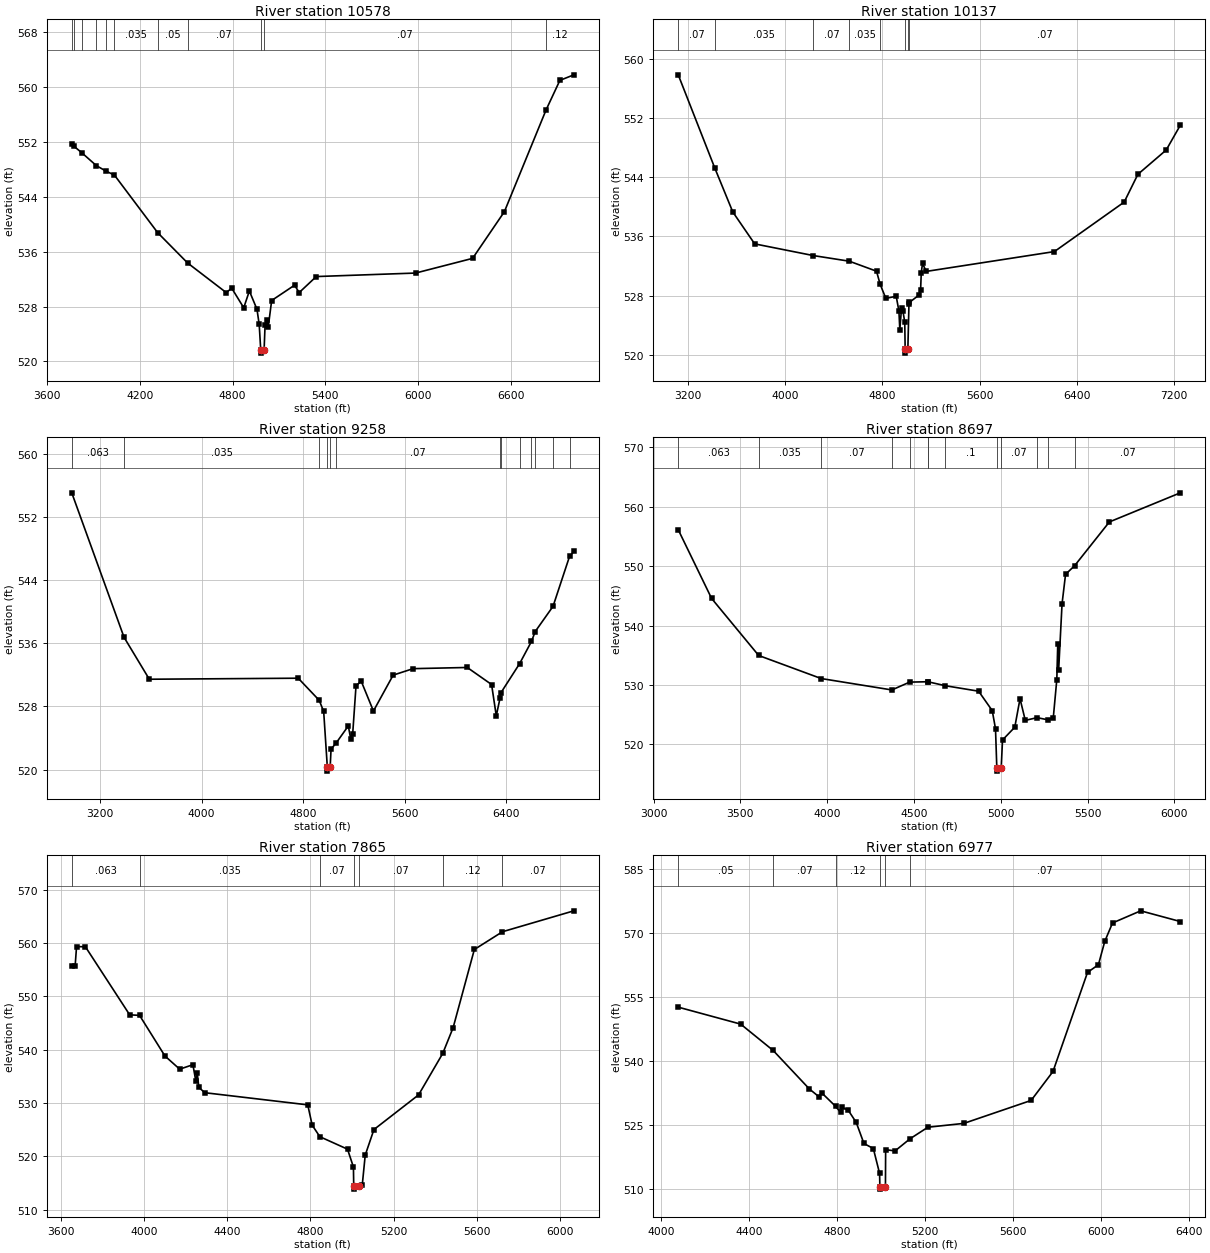
Type RM Length L Ch R = 1 ,10578   ,441,441,441
BEGIN DESCRIPTION:
YOUNGS CREEK 18.0
END DESCRIPTION:
XS GIS Cut Line= 3
        2269475.       13764825.        2268675.       13763875.
      2266674.95       13763675.
#Sta/Elev= 30
  3758.1  551.75  3771.8  551.37  3824.1  550.39  3917.7  548.53  3979.6  547.74
  4034.6  547.15  4314.8  538.76  4508.3  534.35  4758.8  530.03    4794  530.68
    4872  527.82  4908.4  530.27  4957.8  527.59  4972.1  525.39  4981.9  521.71
  4982.4  521.21  5003.9  521.71  5010.1  525.25  5020.2  526.03  5030.2  524.95
  5052.8  528.88  5201.1  531.11  5231.2  530.04  5341.8  532.37    5985  532.88
  6354.3  535.02  6560.3  541.83  6830.1  556.65  6919.6  560.96  7010.1  561.77
#Mann= 11 ,-1 , 0
  3758.1     .05       0  3771.8    .035       0  3824.1     .05       0
  3917.7    .035       0  3979.6     .05       0  4034.6    .035       0
  4314.8     .05       0  4508.3     .07       0  4981.9     .05       0
  5003.9     .07       0  6830.1     .12       0
Bank Sta=4981.9,5003.9
XS Rating Curve= 0 ,0
Exp/Cntr=0.3,0.1

Type RM Length L Ch R = 1 ,10137   ,879,879,879
BEGIN DESCRIPTION:
YOUNGS CREEK 17.0
END DESCRIPTION:
XS GIS Cut Line= 3
      2270532.07     13764152.72      2268818.95     13763473.21
       2266560.3      13763119.1
#Sta/Elev= 30
  3121.3  557.82  3420.4  545.29    3570  539.29    3750  534.98  4232.4   533.4
  4528.2  532.64    4752  531.29  4781.8  529.52  4828.7  527.62    4914   527.9
  4936.2  525.91  4943.7  523.38  4957.8  526.35  4968.8  525.94  4984.2  524.42
  4987.6  520.72  4988.1  520.22  5009.7  520.72  5018.9  526.88  5023.2  527.08
  5099.8  528.05  5114.6  528.78  5120.1  531.09  5130.2  532.34  5160.6  531.26
    6215  533.94    6789  540.63  6901.6  544.38  7134.4  547.66  7250.5  551.01
#Mann= 8 ,-1 , 0
  3121.3     .07       0  3420.4    .035       0  4232.4     .07       0
  4528.2    .035       0  4781.8     .07       0  4987.6     .05       0
  5009.7     .07       0  5023.2     .07       0
Bank Sta=4987.6,5009.7
XS Rating Curve= 0 ,0
Exp/Cntr=0.3,0.1

Type RM Length L Ch R = 1 ,9258    ,561,561,561
BEGIN DESCRIPTION:
YOUNGS CREEK 16.0
END DESCRIPTION:
XS GIS Cut Line= 5
      2271051.68     13763275.24      2270533.83     13763114.53
      2269603.75     13763032.96      2268790.24     13762812.83
      2267775.01     13761525.01
#Sta/Elev= 30
  2976.3  555.08  3388.3  536.77  3587.6  531.45  4761.7  531.58    4927  528.78
  4962.4  527.37  4991.2   520.3  4991.7   519.8  5013.5   520.3  5020.6  522.59
  5059.2  523.33  5156.6  525.53    5176  523.85  5191.3  524.56  5217.5  530.64
  5258.9  531.18  5354.7  527.42  5510.2  531.97  5667.3  532.79  6094.4  532.94
  6286.2  530.78  6323.2  526.82  6352.5  529.03  6356.9  529.66    6507  533.42
  6600.9  536.25  6630.4   537.5  6770.7  540.69  6901.1  547.03  6934.8  547.65
#Mann= 13 ,-1 , 0
  2976.3    .063       0  3388.3    .035       0    4927    .063       0
  4991.2     .05       0  5013.5    .063       0  5059.2     .07       0
  6352.5      .1       0  6356.9     .07       0    6507      .1       0
  6600.9     .07       0  6630.4    .045       0  6770.7     .07       0
  6901.1    .045       0
Bank Sta=4991.2,5013.5
XS Rating Curve= 0 ,0
Exp/Cntr=0.3,0.1

Type RM Length L Ch R = 1 ,8697    ,832,832,832
BEGIN DESCRIPTION:
H21807
END DESCRIPTION:
XS GIS Cut Line= 3
      2271087.42     13763248.46      2269450.62     13762707.56
      2269297.53      13761549.8
#Sta/Elev= 30
  3142.1  556.13  3334.2  544.57  3605.4  534.97  3965.3  531.09  4372.4  529.17
  4475.1  530.49  4577.8  530.55  4581.4  530.54  4680.5  529.88  4872.1  528.96
  4950.6  525.69  4969.4  522.64    4977  516.01  4977.5  515.51  5002.2  516.01
  5009.8  520.75  5080.4   522.9  5110.6   527.7  5140.9  524.05  5208.9  524.51
  5270.2  524.15  5302.3  524.52  5322.5  530.92    5328  536.97    5333  532.47
  5352.7  543.68  5372.9  548.63  5424.6  550.06  5625.1  557.44  6033.8  562.34
#Mann= 13 ,-1 , 0
  3142.1    .063       0  3605.4    .035       0  3965.3     .07       0
  4372.4    .035       0  4475.1     .07       0  4577.8      .1       0
  4581.4    .035       0  4680.5      .1       0    4977     .05       0
  5002.2     .07       0  5208.9     .07       0  5270.2      .1       0
  5424.6     .07       0
Bank Sta=4977,5002.2
XS Rating Curve= 0 ,0
Exp/Cntr=0.3,0.1

Type RM Length L Ch R = 1 ,7865    ,888,888,888
BEGIN DESCRIPTION:
H21806
END DESCRIPTION:
XS GIS Cut Line= 3
      2271202.03     13763300.92      2269986.58     13762200.31
      2269651.62     13761501.67
#Sta/Elev= 30
  3652.7  555.65  3668.9  555.67  3675.7   559.3  3718.3  559.27  3931.2  546.51
  3978.7  546.41  4100.8  538.79  4171.8  536.32  4235.3  537.16  4249.5  534.04
  4256.3  535.54  4263.7  532.92  4292.1  531.91  4787.5  529.63  4808.9  525.82
  4845.7  523.66  4978.8  521.32  5007.2  517.97  5008.7  514.33  5009.2  513.83
    5034  514.33  5049.7  514.61  5063.9   520.2  5105.8     525  5320.5   531.5
  5436.7  539.27  5486.8  544.12  5588.7  558.76    5724  562.09  6067.2  566.01
#Mann= 7 ,-1 , 0
  3652.7    .063       0  3978.7    .035       0  4845.7     .07       0
  5008.7     .05       0    5034     .07       0  5436.7     .12       0
    5724     .07       0
Bank Sta=5008.7,5034
XS Rating Curve= 0 ,0
Exp/Cntr=0.3,0.1

Type RM Length L Ch R = 1 ,6977    ,1165,1165,1165
BEGIN DESCRIPTION:
H21805
END DESCRIPTION:
XS GIS Cut Line= 3
      2271489.19     13762611.86      2270656.53     13761894.05
      2269729.07     13761157.82
#Sta/Elev= 30
  4077.8  552.62  4361.8  548.64  4509.6  542.45  4674.4  533.41  4717.1  531.62
  4730.4  532.51    4794  529.31  4815.9  527.93  4822.7  529.12  4851.1  528.41
  4887.2  525.58  4922.4  520.62  4965.1  519.44  4993.6  513.59  4994.9  510.41
  4995.4  509.91  5020.2  510.41  5021.1  519.17  5063.9  518.88  5132.1  521.73
  5213.4  524.44  5376.8  525.34  5682.8  530.73  5782.2  537.52  5939.2  560.77
  5988.9  562.59  6017.7  568.05  6052.9  572.38  6181.1  575.23  6361.3  572.72
#Mann= 6 ,-1 , 0
  4077.8     .05       0  4509.6     .07       0    4794     .12       0
  4994.9     .05       0  5020.2     .12       0  5132.1     .07       0
Bank Sta=4994.9,5020.2
XS Rating Curve= 0 ,0
Exp/Cntr=0.3,0.1

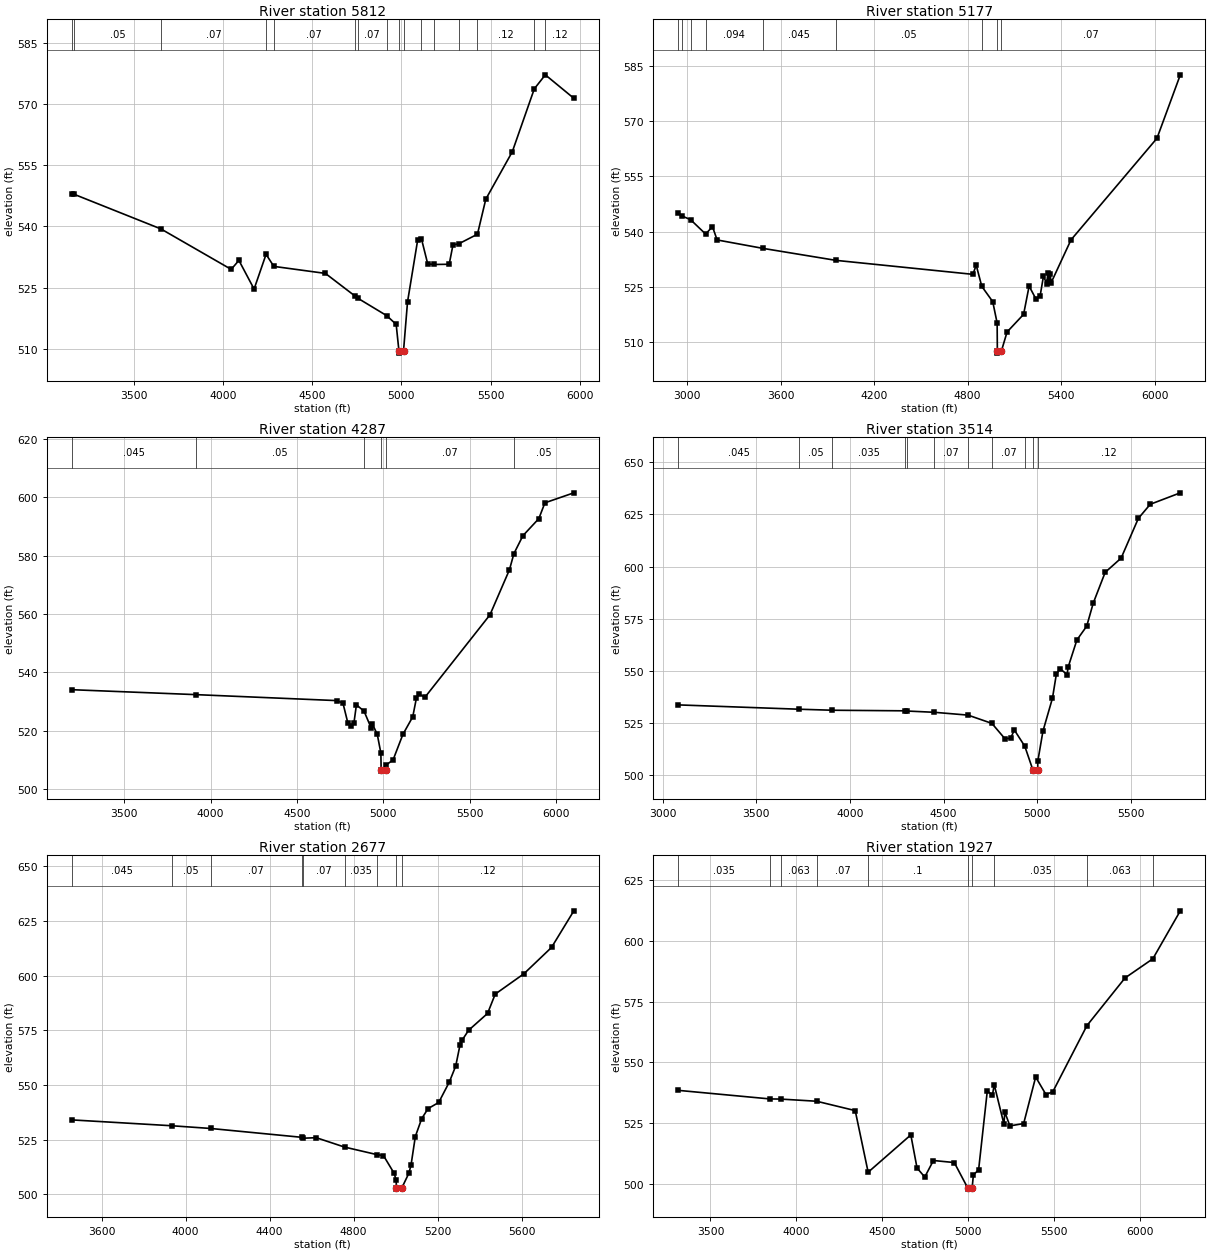
Type RM Length L Ch R = 1 ,5812    ,635,635,635
BEGIN DESCRIPTION:
H21804
END DESCRIPTION:
XS GIS Cut Line= 3
      2271738.04     13762506.59      2270800.09     13761310.23
      2269890.88     13760391.46
#Sta/Elev= 30
  3154.1  547.99  3164.9  547.93  3653.7  539.39  4047.2  529.47  4090.5  531.67
  4175.5  524.64  4242.6  533.16  4286.2   530.2  4575.1  528.48    4739  522.99
    4756  522.41  4918.3  518.12  4971.5  515.98  4987.1  509.42  4987.6  508.92
  5012.6  509.42  5035.1  521.48  5091.7   536.6  5112.9     537  5148.3  530.81
    5184  530.67  5268.5  530.72  5289.7  535.47  5322.1  535.74  5426.9   538.1
  5473.6  546.69  5622.1  558.33  5745.4  573.77  5807.1   577.2  5966.9  571.44
#Mann= 16 ,-1 , 0
  3154.1    .035       0  3164.9     .05       0  3653.7     .07       0
  4242.6     .12       0  4286.2     .07       0    4739     .12       0
    4756     .07       0  4918.3     .12       0  4987.1     .05       0
  5012.6     .12       0  5112.9     .07       0    5184     .12       0
  5322.1     .07       0  5426.9     .12       0  5745.4     .07       0
  5807.1     .12       0
Bank Sta=4987.1,5012.6
XS Rating Curve= 0 ,0
Exp/Cntr=0.3,0.1

Type RM Length L Ch R = 1 ,5177    ,890,890,890
BEGIN DESCRIPTION:
H21803
END DESCRIPTION:
XS GIS Cut Line= 3
      2272302.69     13762363.01      2271431.76     13761090.11
      2270254.58     13759893.79
#Sta/Elev= 30
  2943.7  545.01  2965.2   544.3    3023  543.25  3119.6  539.33  3163.2  541.38
    3193  537.74    3487  535.45  3955.3  532.19  4833.8  528.39  4855.1  530.88
    4891  525.11  4961.1  520.97  4989.4  515.15  4990.8  507.47  4991.3  506.97
  5016.3  507.47  5053.1  512.72  5159.1  517.51  5194.5  525.19  5236.9  521.79
  5265.1  522.52  5286.4  527.85  5307.6  525.89  5314.7  528.69  5321.7  526.33
  5328.8  528.54  5335.9  526.12  5463.1  537.76  6014.7  565.38  6164.4  582.63
#Mann= 9 ,-1 , 0
  2943.7    .125       0  2965.2    .094       0    3023    .125       0
  3119.6    .094       0    3487    .045       0  3955.3     .05       0
    4891     .07       0  4990.8     .05       0  5016.3     .07       0
Bank Sta=4990.8,5016.3
XS Rating Curve= 0 ,0
Exp/Cntr=0.3,0.1

Type RM Length L Ch R = 1 ,4287    ,773,773,773
BEGIN DESCRIPTION:
H21802
END DESCRIPTION:
XS GIS Cut Line= 3
      2272436.68     13761597.36      2271757.16      13760209.6
       2270714.5     13759329.56
#Sta/Elev= 30
    3195  534.06  3913.2  532.37  4731.2  530.32  4766.6  529.44  4795.2   522.6
    4816  521.67  4830.3  522.72  4844.6  528.88    4889  526.68  4929.2  521.03
  4936.9  522.33  4965.5  518.73  4986.4  512.29  4987.8  506.64  4988.3  506.14
  5013.5  506.64    5015  508.15  5057.1     510  5113.8  518.72    5171  524.76
  5191.8  531.05  5206.1  532.64  5241.3  531.44  5618.3  559.71  5731.4  575.18
  5757.2  580.71  5809.4  586.86  5901.7  592.72  5936.9  598.13  6104.6  601.56
#Mann= 6 ,-1 , 0
    3195    .045       0  3913.2     .05       0    4889     .07       0
  4987.8     .05       0  5013.5     .07       0  5757.2     .05       0
Bank Sta=4987.8,5013.5
XS Rating Curve= 0 ,0
Exp/Cntr=0.3,0.1

Type RM Length L Ch R = 1 ,3514    ,837,837,837
BEGIN DESCRIPTION:
H21801
END DESCRIPTION:
XS GIS Cut Line= 3
      2272407.97     13761358.08        2272006.     13759242.96
      2271614.22      13758889.4
#Sta/Elev= 30
  3083.1  533.71    3727  531.64  3905.8  531.15    4295  530.87  4305.3  530.77
  4450.9  530.16  4630.5  528.81  4757.7  524.85  4826.8  517.56  4857.4   517.7
  4877.7  521.69  4933.5  513.88  4976.9  502.47  4977.4  501.97  5002.6  502.47
  5002.7  506.63  5030.4  521.13  5081.3  536.97  5101.7  548.32    5122  551.07
  5159.4  548.22  5164.5  551.68  5211.6  564.82    5264  571.43  5299.1  582.54
  5362.6  597.23  5447.8  604.06  5539.8   623.1  5603.3  629.85  5763.8  635.34
#Mann= 11 ,-1 , 0
  3083.1    .045       0    3727     .05       0  3905.8    .035       0
    4295     .05       0  4305.3    .035       0  4450.9     .07       0
  4630.5     .05       0  4757.7     .07       0  4933.5     .12       0
  4976.9     .05       0  5002.6     .12       0
Bank Sta=4976.9,5002.6
XS Rating Curve= 0 ,0
Exp/Cntr=0.3,0.1

Type RM Length L Ch R = 1 ,2677    ,750,750,750
BEGIN DESCRIPTION:
H21800
END DESCRIPTION:
XS GIS Cut Line= 2
      2272513.25     13761271.95      2272876.79     13758908.95
#Sta/Elev= 30
  3458.3  533.99  3933.3  531.32  4119.3  530.07  4553.7  526.02  4558.1   525.6
  4622.3  525.85    4757  521.56  4912.4  518.08  4942.5  517.67  4993.1  509.59
  5003.2  506.39  5003.9  502.81  5004.4  502.31  5029.7  502.81  5063.9  509.67
    5074  513.45  5094.3  526.39  5124.6  534.57    5155  539.16  5205.6  541.96
  5256.2  551.34  5286.5   558.6  5306.7  568.14  5316.9  570.46  5348.2  575.02
  5438.3  582.72  5474.7  591.55  5611.3  600.86  5742.8  612.91  5849.1  629.66
#Mann= 9 ,-1 , 0
  3458.3    .045       0  3933.3     .05       0  4119.3     .07       0
  4553.7    .035       0  4558.1     .07       0    4757    .035       0
  4912.4     .07       0  5003.9     .05       0  5029.7     .12       0
Bank Sta=5003.9,5029.7
XS Rating Curve= 0 ,0
Exp/Cntr=0.3,0.1

Type RM Length L Ch R = 1 ,1927    ,817,817,817
BEGIN DESCRIPTION:
H21799
END DESCRIPTION:
XS GIS Cut Line= 3
      2273030.06     13761913.23      2273336.33     13759999.05
      2273288.47     13759013.23
#Sta/Elev= 30
  3312.3  538.45  3845.6  534.92  3910.1  534.85  4118.8  533.96  4343.5   530.1
  4418.9   504.7  4667.5  520.08  4703.7  506.46  4748.6   502.7  4799.2  509.53
  4920.7  508.69  4998.9  498.23  4999.4  497.73  5024.8  498.23  5032.1  503.59
  5062.5  505.67  5113.1  538.19    5143  536.49  5153.5  540.78  5210.1  524.53
  5215.1   529.5  5244.8   523.8    5325  524.76    5395  543.95  5455.1   536.7
  5495.2  537.92  5693.7  565.14  5915.7  584.79  6077.8  592.69  6237.8  612.46
#Mann= 10 ,-1 , 0
  3312.3    .035       0  3845.6    .045       0  3910.1    .063       0
  4118.8     .07       0  4418.9      .1       0  4998.9     .05       0
  5024.8      .1       0  5153.5    .035       0  5693.7    .063       0
  6077.8     .07       0
Bank Sta=4998.9,5024.8
XS Rating Curve= 0 ,0
Exp/Cntr=0.3,0.1

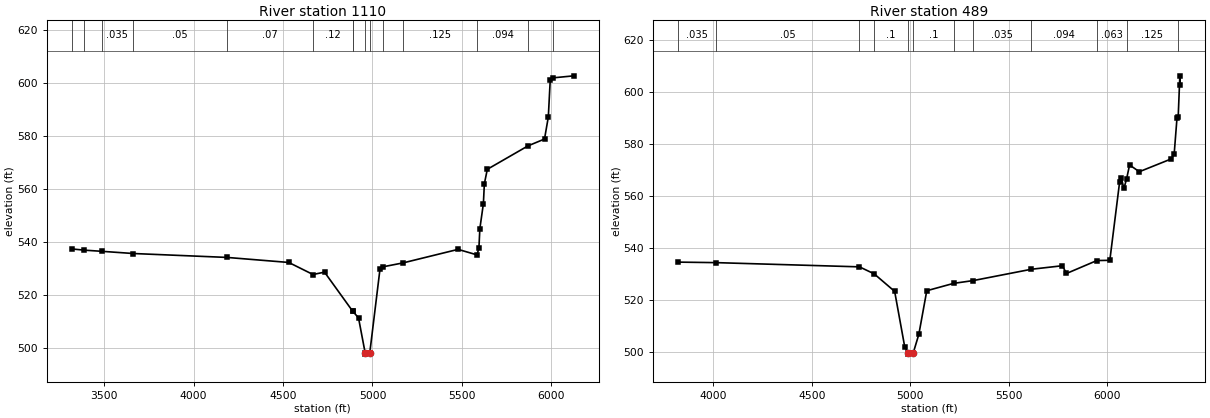
Type RM Length L Ch R = 1 ,1110    ,621,621,621
BEGIN DESCRIPTION:
H21798
END DESCRIPTION:
XS GIS Cut Line= 3
      2273881.86     13761807.94      2273881.86     13759970.33
      2273546.87     13759061.08
#Sta/Elev= 30
    3319  537.35  3387.8  536.89  3486.2  536.45  3662.3  535.62  4186.6  534.14
  4531.9  532.24  4667.5  527.69  4731.9  528.58  4888.7  513.88  4890.3  513.76
  4921.9  511.32  4958.9  498.12  4959.4  497.62  4984.9  498.12  5041.9  529.72
  5061.2  530.63  5171.4  532.08  5478.4  537.18  5584.2   535.1  5594.9  537.66
  5600.2  545.01    5620  554.47  5625.3  561.93  5641.9  567.42  5869.3  576.27
  5961.6  578.85  5982.9  587.16  5993.5  601.02  6008.5  601.95  6125.6  602.72
#Mann= 15 ,-1 , 0
    3319    .063       0  3387.8     .05       0  3486.2    .035       0
  3662.3     .05       0  4186.6     .07       0  4667.5     .12       0
  4888.7      .1       0  4890.3     .12       0  4958.9     .05       0
  4984.9     .12       0  5061.2    .035       0  5171.4    .125       0
  5584.2    .094       0  5869.3    .125       0  6008.5    .094       0
Bank Sta=4958.9,4984.9
XS Rating Curve= 0 ,0
Exp/Cntr=0.3,0.1

Type RM Length L Ch R = 1 ,489     ,0,0,0
BEGIN DESCRIPTION:
H21797
END DESCRIPTION:
XS GIS Cut Line= 4
      2274216.85     13761434.61      2274484.81     13760487.15
      2274379.54     13759951.19      2273729.34     13759167.14
#Sta/Elev= 30
  3822.3  534.65  4014.9  534.45  4742.4  532.83    4817  530.15  4921.2   523.4
  4972.2  502.14  4989.7  499.78  4990.2  499.28  5015.7  499.78    5044  506.89
  5084.3  523.65  5220.6  526.48  5321.5  527.57    5615   531.9  5772.9  533.26
  5793.7  530.28  5947.9  535.25  6013.8  535.34  6063.3  565.34  6071.1  567.16
  6085.4     563  6098.7  566.56  6114.1  571.99  6163.6   569.4  6326.3  574.34
  6340.7  576.37    6355   590.2  6360.9  590.31  6369.3  606.26  6371.7  602.55
#Mann= 12 ,-1 , 0
  3822.3    .035       0  4014.9     .05       0  4742.4    .035       0
    4817      .1       0  4989.7     .05       0  5015.7      .1       0
  5220.6    .094       0  5321.5    .035       0    5615    .094       0
  5947.9    .063       0  6098.7    .125       0  6360.9    .094       0
Bank Sta=4989.7,5015.7
XS Rating Curve= 0 ,0
Exp/Cntr=0.3,0.1

Chan Stop Cuts=-1
Use User Specified Reach Order=0
Composite Channel Slope=5