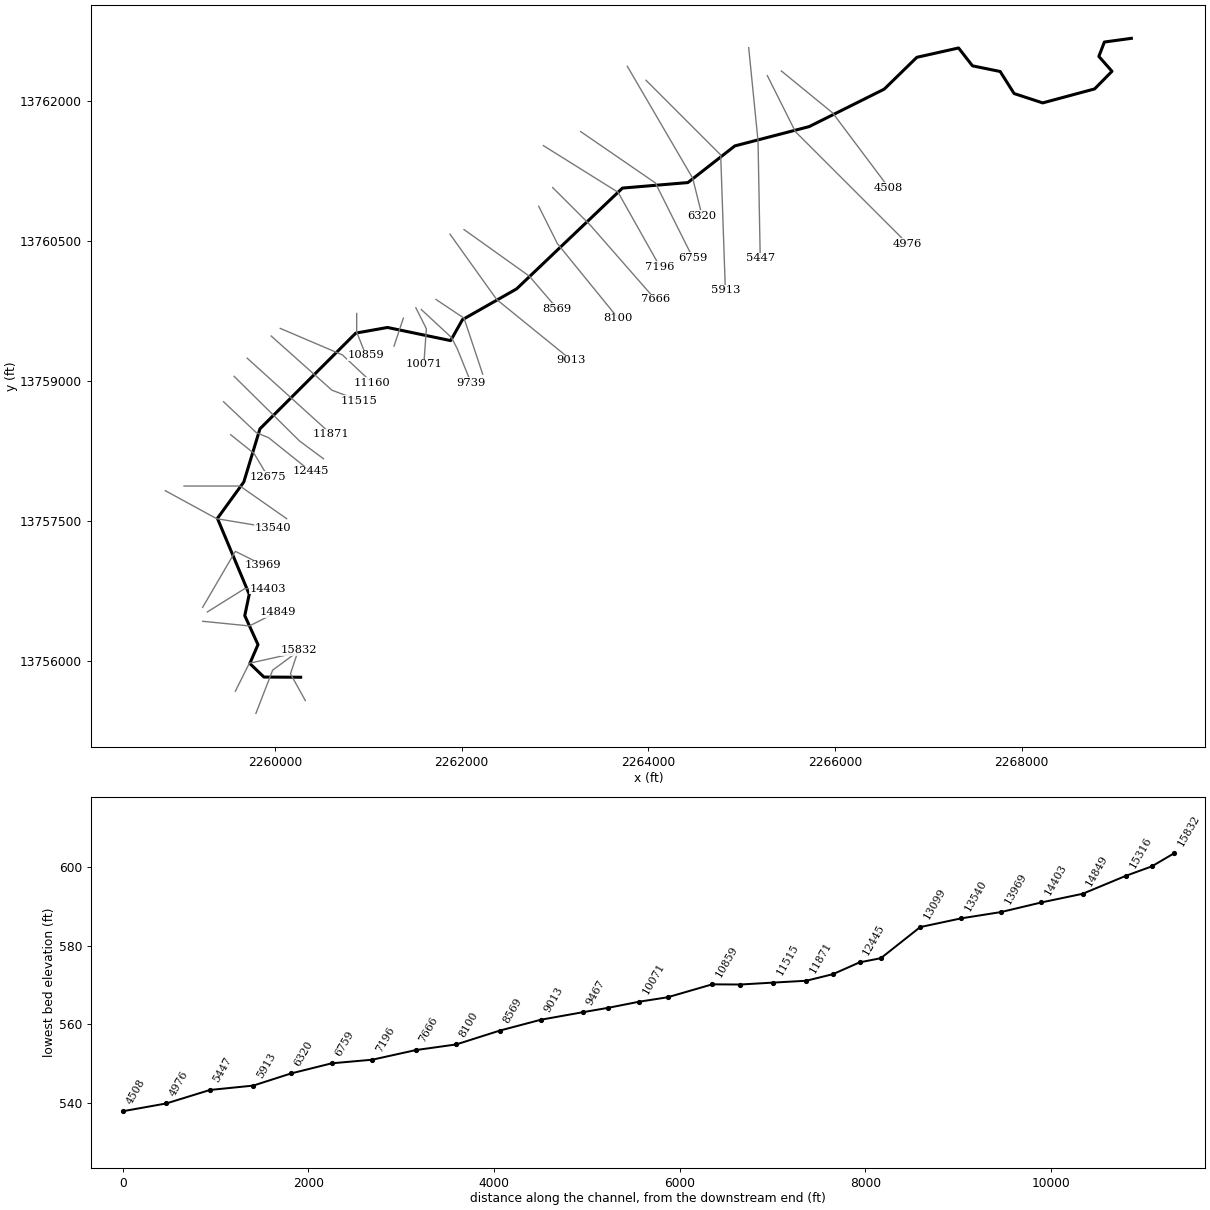
--- YOUNGS TRIBUTARY 1.prj (project) ---

Proj Title=YOUNGS TRIBUTARY 1 Base Level Engineering
Current Plan=p01
Default Exp/Contr=0.3,0.1
English Units
Geom File=g01
Flow File=f01
Plan File=p01
Y Axis Title=Elevation
X Axis Title(PF)=Main Channel Distance
X Axis Title(XS)=Station
BEGIN DESCRIPTION:
YOUNGS TRIBUTARY 1
END DESCRIPTION:
DSS Export Rating Curves= 0
DSS Export Rating Curve Sorted= 0
DSS Export Volume Flow Curves= 0
DXF OffsetX= 0
DXF OffsetY= 0
DXF ScaleX= 1
DXF ScaleY= 10

--- YOUNGS TRIBUTARY 1.p01 (plan) ---

Plan Title=Multiple Run
Short Identifier=Multiple
Geom File=g01
Flow File=f01
Subcritical Flow
K Sum by GR= 0
Std Step Tol= 0.01
Critical Tol= 0.01
Num of Std Step Trials= 20
Max Error Tol= 0.3
Flow Tol Ratio= 0.001
Split Flow NTrial= 30
Split Flow Tol= 0.02
Split Flow Ratio= 0.02
Log Output Level= 0
Friction Slope Method= 1
Unsteady Friction Slope Method= 2
Unsteady Bridges Friction Slope Method= 1
Parabolic Critical Depth
Global Vel Dist=  1 , 1 , 1
Global Log Level= 0
CheckData=True
Encroach Param= -1, 0, 0, 0
BEGIN DESCRIPTION:
Multiple Run
END DESCRIPTION:

--- YOUNGS TRIBUTARY 1.f01 (steady flow) ---

Flow Title=Multiple
Number of Profiles=7
Profile Names=10-year,25-year,50-year,1pct_min,100-year,1pct_plu,500-year
River Rch & RM= YOUNGS TRIBUTARY,Reach-1,15832
     420     663     878     564    1126    2247    1831
River Rch & RM= YOUNGS TRIBUTARY,Reach-1,13099
     611     984    1320     858    1712    3415    2846
River Rch & RM= YOUNGS TRIBUTARY,Reach-1,9013
     855    1397    1891    1237    2468    4924    4165
River Rch & RM= YOUNGS TRIBUTARY,Reach-1,2191
    1071    1770    2413    1589    3170    6325    5420
River Rch & RM= YOUNGS TRIBUTARY,Reach-1,461
    1193    1981    2711    1791    3574    7131    6153
Boundary for River Rch & Prof#=YOUNGS TRIBUTARY,Reach-1,1
Up Type=0
Dn Type=3
Dn Slope=0.005
Boundary for River Rch & Prof#=YOUNGS TRIBUTARY,Reach-1,2
Up Type=0
Dn Type=3
Dn Slope=0.005
Boundary for River Rch & Prof#=YOUNGS TRIBUTARY,Reach-1,3
Up Type=0
Dn Type=3
Dn Slope=0.005
Boundary for River Rch & Prof#=YOUNGS TRIBUTARY,Reach-1,4
Up Type=0
Dn Type=3
Dn Slope=0.005
Boundary for River Rch & Prof#=YOUNGS TRIBUTARY,Reach-1,5
Up Type=0
Dn Type=3
Dn Slope=0.005
Boundary for River Rch & Prof#=YOUNGS TRIBUTARY,Reach-1,6
Up Type=0
Dn Type=3
Dn Slope=0.005
Boundary for River Rch & Prof#=YOUNGS TRIBUTARY,Reach-1,7
Up Type=0
Dn Type=3
Dn Slope=0.005

--- YOUNGS TRIBUTARY 1.g01 (geometry) ---

Geom Title=Existing Conditions
Program Version=4.10

River Reach=YOUNGS TRIBUTARY,Reach-1
Reach XY= 30
        2260275.       13755825.      2259880.85     13755827.06
       2259730.4     13755972.57      2259817.67      13756174.9
      2259676.09     13756485.54       2259723.9     13756714.45
      2259383.04     13757528.31       2259665.7     13757918.33
      2259838.64     13758488.34       2260865.2     13759514.52
       2261204.9     13759575.09        2261882.     13759434.16
       2262008.3     13759658.62      2262588.21     13759988.62
      2263722.55     13761069.54      2264423.54     13761128.54
      2264926.47     13761521.45      2265723.42     13761728.83
      2266527.43     13762130.52      2266876.46     13762471.46
      2267323.72     13762571.63       2267472.7     13762380.11
      2267769.39     13762319.41      2267918.66     13762083.02
       2268224.9     13761982.78      2268781.21     13762132.76
      2268967.41     13762321.67      2268826.61     13762481.04
      2268885.76     13762635.44        2269175.       13762675.

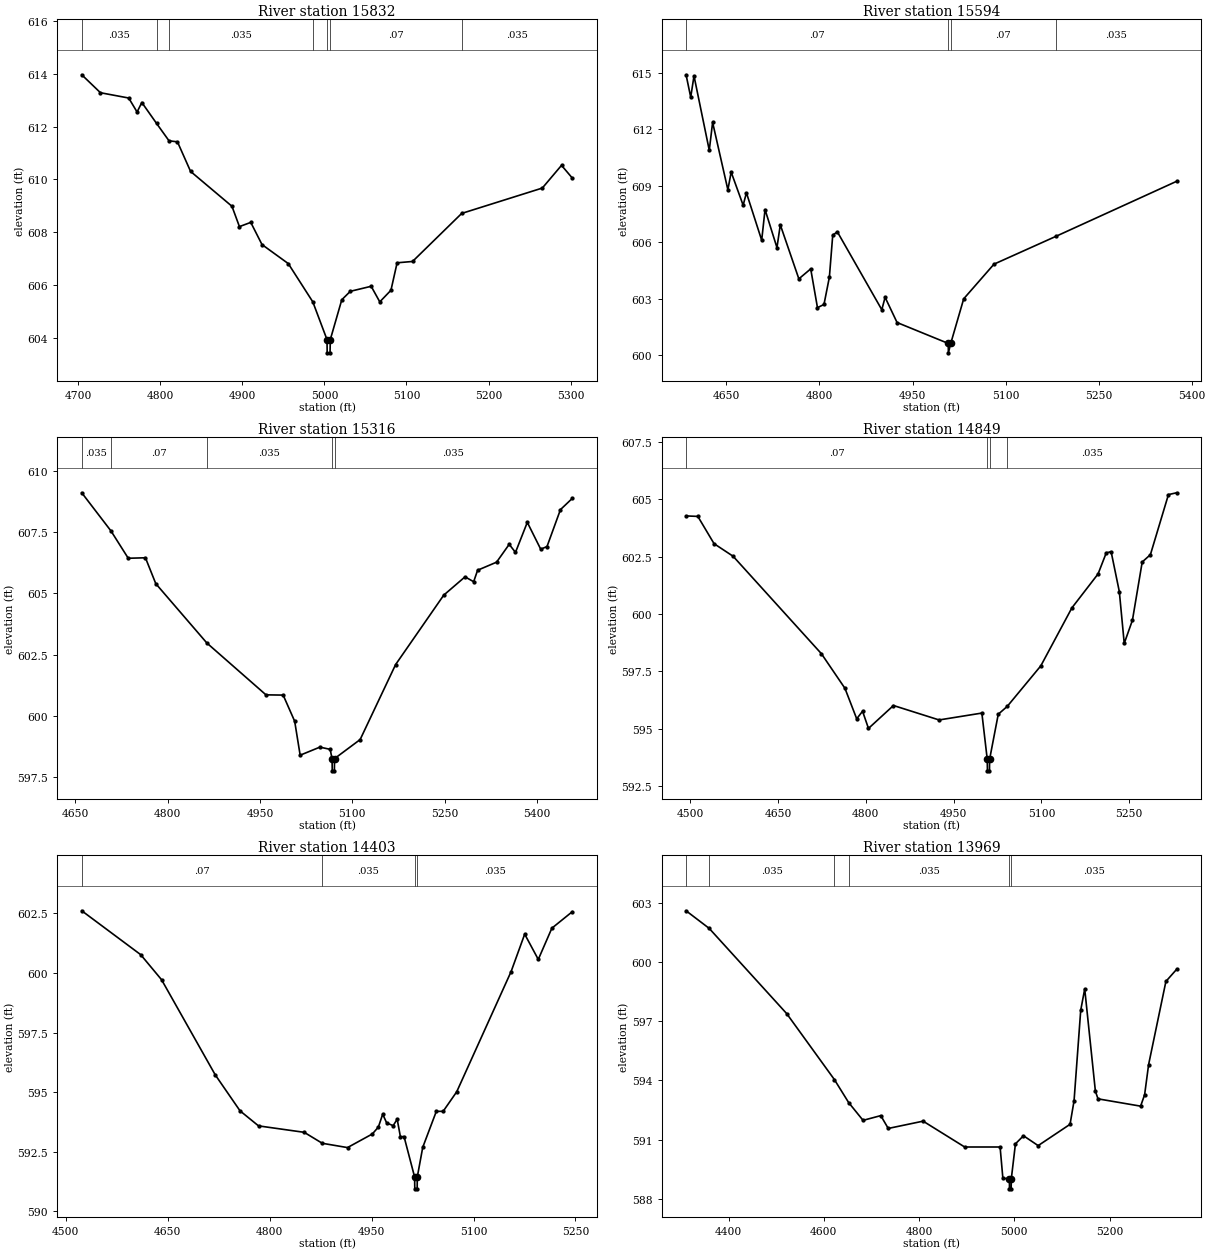
Type RM Length L Ch R = 1 ,15832   ,238,238,238
BEGIN DESCRIPTION:
YOUNGS TRIBUTARY 1 30.0
END DESCRIPTION:
XS GIS Cut Line= 3
      2260324.98     13755575.03      2260165.44     13755862.09
      2260250.57     13756117.46
#Sta/Elev= 30
  4704.4  613.96  4727.2  613.28  4761.6  613.08  4771.8  612.55  4777.6  612.91
  4795.5  612.12  4810.7  611.46    4821  611.42    4837   610.3  4887.4  608.98
  4896.5  608.21  4910.3  608.37    4924  607.53    4956  606.81  4985.9  605.36
  5003.2  603.93  5003.4  603.43  5006.9  603.43  5007.2  603.93  5021.2  605.44
  5031.6  605.76    5057  605.95  5067.5  605.36  5081.1   605.8  5088.6  606.84
  5107.4  606.89  5167.3  608.71  5265.5  609.67  5288.9  610.53    5302  610.05
#Mann= 7 ,-1 , 0
  4704.4    .035       0  4795.5     .07       0  4810.7    .035       0
  4985.9     .07       0  5003.2     .05       0  5007.2     .07       0
  5167.3    .035       0
Bank Sta=5003.2,5007.2
XS Rating Curve= 0 ,0
Exp/Cntr=0.3,0.1

Type RM Length L Ch R = 1 ,15594   ,278,278,278
BEGIN DESCRIPTION:
J21835
END DESCRIPTION:
XS GIS Cut Line= 3
      2259795.52     13755437.64      2259974.65     13755901.03
      2260211.07     13756075.44
#Sta/Elev= 30
    4585   614.9  4592.5  613.71  4597.8  614.84  4622.4  610.89  4627.8  612.37
  4652.4  608.79  4657.7  609.73    4677  607.97  4682.3  608.63  4706.9  606.11
  4712.3  607.74  4731.5  605.72  4736.9  606.93  4766.8  604.06  4785.9  604.59
  4796.8  602.53  4807.3   602.7    4816  604.15  4821.4  606.38  4828.8  606.56
  4900.5  602.42  4905.8  603.08  4925.1  601.74  5007.6  600.63  5007.8  600.13
  5011.6  600.63  5032.5     603  5081.3  604.84  5180.6  606.31  5375.6  609.24
#Mann= 4 ,-1 , 0
    4585     .07       0  5007.6     .05       0  5011.6     .07       0
  5180.6    .035       0
Bank Sta=5007.6,5011.6
XS Rating Curve= 0 ,0
Exp/Cntr=0.3,0.1

Type RM Length L Ch R = 1 ,15316   ,467,467,467
BEGIN DESCRIPTION:
YOUNGS TRIBUTARY 1 29.0
END DESCRIPTION:
XS GIS Cut Line= 3
      2259574.99     13755674.99        2259725.       13755975.
        2260175.       13756075.
#Sta/Elev= 30
  4660.7  609.12  4708.1  607.56  4736.2  606.44  4764.1  606.46  4780.9   605.4
  4863.9  602.97  4959.8  600.85  4987.7  600.84  5006.4  599.77  5015.3  598.38
  5047.3  598.71    5064  598.62  5067.1  598.24  5067.4  597.74  5070.9  597.74
  5071.1  598.24  5112.7  599.02  5170.3  602.09  5248.4  604.93    5283  605.68
    5297  605.48  5303.4  605.95  5334.2  606.28  5354.7  607.01  5364.9  606.68
  5384.1  607.91  5405.9  606.81  5416.1  606.92  5437.9  608.43  5457.1  608.89
#Mann= 5 ,-1 , 0
  4660.7    .035       0  4708.1     .07       0  4863.9    .035       0
  5067.1    .035       0  5071.1    .035       0
Bank Sta=5067.1,5071.1
XS Rating Curve= 0 ,0
Exp/Cntr=0.3,0.1

Type RM Length L Ch R = 1 ,14849   ,446,446,446
BEGIN DESCRIPTION:
YOUNGS TRIBUTARY 1 28.0
END DESCRIPTION:
XS GIS Cut Line= 3
      2259224.96       13756425.        2259725.       13756375.
      2260024.96     13756524.98
#Sta/Elev= 30
  4492.9  604.28    4513  604.26  4540.7  603.07  4573.3  602.52  4724.1  598.27
  4764.3  596.76  4784.4  595.43  4794.4  595.76  4804.5  595.01  4847.2  596.01
  4925.1  595.38  4998.2  595.68  5007.4  593.66  5007.7  593.16  5011.2  593.16
  5011.4  593.66  5026.2  595.63  5041.5  595.97  5098.9  597.74    5152  600.27
  5196.7  601.75  5210.7  602.67    5219  602.72    5233  600.98  5241.4  598.72
  5255.4  599.73  5272.1  602.27  5286.1  602.59  5316.9  605.21  5330.8  605.29
#Mann= 4 ,-1 , 0
  4492.9     .07       0  5007.4     .05       0  5011.4     .07       0
  5041.5    .035       0
Bank Sta=5007.4,5011.4
XS Rating Curve= 0 ,0
Exp/Cntr=0.3,0.1

Type RM Length L Ch R = 1 ,14403   ,434,434,434
BEGIN DESCRIPTION:
YOUNGS TRIBUTARY 1 27.0
END DESCRIPTION:
XS GIS Cut Line= 3
      2259274.97     13756524.98        2259675.       13756775.
      2259924.96       13756775.
#Sta/Elev= 30
  4523.6  602.61  4610.3  600.77    4641  599.72    4720  595.73  4756.5  594.22
  4783.7  593.59  4850.9  593.32  4877.5  592.86  4914.6  592.68  4951.1  593.25
    4960  593.54  4966.4  594.08  4972.3  593.71  4981.8   593.6  4987.7  593.87
  4992.4  593.14  4997.8  593.14  5013.3  591.45  5013.6  590.95  5017.1  590.95
  5017.3  591.45  5025.3  592.69  5045.3   594.2  5055.3   594.2  5075.3  595.02
  5155.3  600.06  5175.3  601.63  5195.3  600.57  5215.3  601.88  5245.3  602.57
#Mann= 4 ,-1 , 0
  4523.6     .07       0  4877.5    .035       0  5013.3    .035       0
  5017.3    .035       0
Bank Sta=5013.3,5017.3
XS Rating Curve= 0 ,0
Exp/Cntr=0.3,0.1

Type RM Length L Ch R = 1 ,13969   ,429,429,429
BEGIN DESCRIPTION:
YOUNGS TRIBUTARY 1 26.0
END DESCRIPTION:
XS GIS Cut Line= 3
      2259224.99     13756574.98        2259575.       13757175.
      2259875.04     13757024.98
#Sta/Elev= 30
  4310.7   602.6  4359.2  601.71    4522  597.39  4622.1  594.05  4652.2  592.88
  4682.4  591.98  4719.6  592.22  4735.3  591.57  4808.5  591.94  4895.8  590.63
  4970.2  590.63    4976  589.05  4989.7  589.01  4989.9  588.51  4993.4  588.51
  4993.7  589.01  5002.4  590.79  5019.3   591.2  5050.1   590.7  5117.1  591.78
  5125.5  592.97  5139.5  597.56  5147.9  598.64  5170.3  593.46  5175.8  593.07
  5265.3   592.7  5273.7  593.28  5282.1  594.81  5318.4  599.02  5340.8  599.63
#Mann= 6 ,-1 , 0
  4310.7     .07       0  4359.2    .035       0  4622.1     .07       0
  4652.2    .035       0  4989.7    .035       0  4993.7    .035       0
Bank Sta=4989.7,4993.7
XS Rating Curve= 0 ,0
Exp/Cntr=0.3,0.1

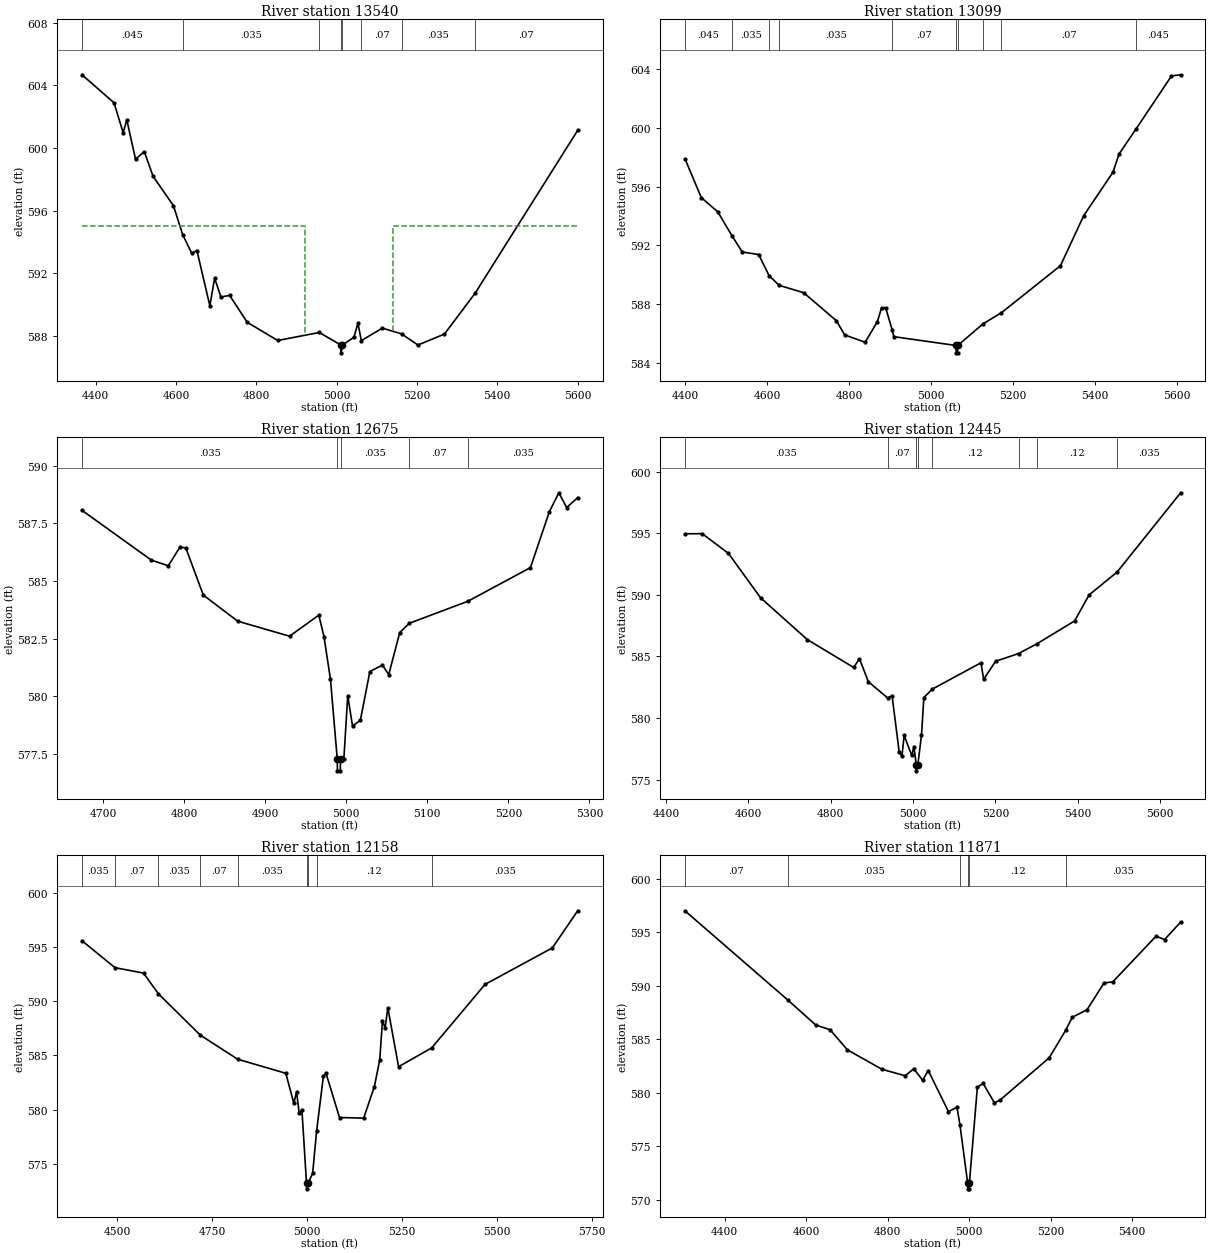
Type RM Length L Ch R = 1 ,13540   ,441,441,441
BEGIN DESCRIPTION:
YOUNGS TRIBUTARY 1 25.0
END DESCRIPTION:
XS GIS Cut Line= 3
      2258825.03     13757824.98        2259375.       13757525.
      2259974.96     13757425.01
#Sta/Elev= 30
  4365.7  604.68  4445.4  602.89  4468.2  600.98  4477.2   601.8    4499  599.29
  4520.9  599.77  4542.7  598.19  4593.5  596.31  4616.3  594.47    4639  593.27
  4651.9  593.45  4684.1  589.92    4696  591.68  4711.7  590.48  4733.5  590.58
  4777.2  588.86  4853.1   587.7  4956.8  588.21  5010.4  587.41  5010.7  586.91
  5014.4  587.41  5042.9   587.9    5053   588.8  5061.4  587.69  5113.8  588.49
  5161.7  588.12  5202.5  587.41  5268.4  588.11  5344.6  590.71  5600.4  601.13
#Mann= 8 ,-1 , 0
  4365.7    .045       0  4616.3    .035       0  4956.8     .12       0
  5010.4     .05       0  5014.4     .12       0  5061.4     .07       0
  5161.7    .035       0  5344.6     .07       0
#XS Ineff= 2 , 0
       0    4920     595    5140       0     595
Permanent Ineff=
       F       F
Bank Sta=5010.4,5014.4
XS Rating Curve= 0 ,0
Exp/Cntr=0.3,0.1

Type RM Length L Ch R = 1 ,13099   ,424,424,424
BEGIN DESCRIPTION:
YOUNGS TRIBUTARY 1 24.0
END DESCRIPTION:
XS GIS Cut Line= 3
      2259025.05       13757875.        2259625.       13757875.
      2260125.01     13757524.99
#Sta/Elev= 30
  4399.7   597.9  4439.7  595.25  4479.7  594.29  4514.3  592.67  4539.7  591.55
  4579.7  591.38  4605.4  589.93  4630.1  589.28  4689.7  588.78  4769.7  586.87
  4789.7  585.91  4839.7  585.41  4869.7  586.82  4879.7  587.75  4889.7  587.76
  4905.6  586.27  4909.7  585.79  5061.7  585.19    5062  584.69  5065.5  584.69
  5065.7  585.19  5127.9  586.67  5172.5  587.42  5316.6  590.62  5373.3  594.02
  5444.8  596.98  5459.6  598.22  5501.8  599.95  5587.7  603.53    5610  603.61
#Mann= 10 ,-1 , 0
  4399.7    .045       0  4514.3    .035       0  4605.4    .045       0
  4630.1    .035       0  4905.6     .07       0  5061.7     .05       0
  5065.7     .07       0  5127.9    .035       0  5172.5     .07       0
  5501.8    .045       0
Bank Sta=5061.7,5065.7
XS Rating Curve= 0 ,0
Exp/Cntr=0.3,0.1

Type RM Length L Ch R = 1 ,12675   ,230,230,230
BEGIN DESCRIPTION:
YOUNGS TRIBUTARY 1 23.0
END DESCRIPTION:
XS GIS Cut Line= 3
      2259524.99     13758425.01        2259775.       13758225.
      2259924.99     13757975.01
#Sta/Elev= 30
  4673.9  588.06  4759.6   585.9  4780.4  585.66  4794.8  586.47    4802  586.43
  4823.6  584.39    4866  583.26    4930  582.61  4966.1  583.52  4972.5  582.59
  4980.5  580.74  4988.9  577.28  4989.1  576.78  4992.6  576.78  4992.9  577.28
    4997  577.28  5001.8  580.04  5007.7  578.72  5017.4  578.97  5029.1  581.08
  5044.6  581.36  5052.4  580.95    5066  582.77  5077.8  583.17  5149.9  584.12
  5227.3  585.58  5250.6     588  5262.3  588.82    5272  588.18  5285.6  588.61
#Mann= 5 ,-1 , 0
  4673.9    .035       0  4988.9    .035       0  4992.9    .035       0
  5077.8     .07       0  5149.9    .035       0
Bank Sta=4988.9,4992.9
XS Rating Curve= 0 ,0
Exp/Cntr=0.3,0.1

Type RM Length L Ch R = 1 ,12445   ,287,287,287
BEGIN DESCRIPTION:
J21834
END DESCRIPTION:
XS GIS Cut Line= 4
      2259448.97     13758778.56      2259799.43     13758447.57
      2259931.82     13758393.06      2260383.46     13758030.96
#Sta/Elev= 30
  4445.9  594.95    4488  594.96  4551.6  593.36  4629.6  589.76  4742.9  586.37
  4855.8   584.1  4869.9  584.81  4891.4  582.95  4938.8  581.61    4949  581.82
  4966.4  577.23    4973   576.9  4978.4  578.58  4996.9  576.96  5002.3  577.68
  5007.7  576.21  5007.9  575.71  5011.7  576.21  5020.5   578.6  5026.3  581.66
  5046.6  582.34  5164.9  584.48  5171.6  583.14  5200.4   584.6  5256.2  585.23
  5300.3  586.01  5392.5  587.88  5427.7  589.99  5495.8  591.85    5650  598.28
#Mann= 8 ,-1 , 0
  4445.9    .035       0  4938.8     .07       0  5007.7     .05       0
  5011.7     .07       0  5046.6     .12       0  5256.2     .07       0
  5300.3     .12       0  5495.8    .035       0
Bank Sta=5007.7,5011.7
XS Rating Curve= 0 ,0
Exp/Cntr=0.3,0.1

Type RM Length L Ch R = 1 ,12158   ,287,287,287
BEGIN DESCRIPTION:
J21833
END DESCRIPTION:
XS GIS Cut Line= 3
      2259561.92      13759051.1      2260262.79     13758358.01
      2260519.81      13758167.2
#Sta/Elev= 30
  4406.9  595.56  4493.7  593.08  4568.9  592.58    4608  590.68  4718.5  586.87
  4816.8  584.65  4943.8  583.35  4964.9  580.58    4972  581.66  4979.1  579.65
  4986.2  579.97  4998.3  573.21  4998.6  572.71  5002.3  573.21  5014.5  574.15
  5024.8  578.02  5042.8   583.1  5049.8  583.34  5085.2  579.28  5148.8  579.22
  5177.1  582.13  5191.2  584.59  5198.3  588.18  5205.4  587.53  5212.5  589.38
  5240.8  583.96    5328  585.69  5468.5  591.54  5645.8   594.9  5712.7  598.32
#Mann= 9 ,-1 , 0
  4406.9    .035       0  4493.7     .07       0    4608    .035       0
  4718.5     .07       0  4816.8    .035       0  4998.3    .035       0
  5002.3    .035       0  5024.8     .12       0    5328    .035       0
Bank Sta=4998.3,5002.3
XS Rating Curve= 0 ,0
Exp/Cntr=0.3,0.1

Type RM Length L Ch R = 1 ,11871   ,356,356,356
BEGIN DESCRIPTION:
J21832
END DESCRIPTION:
XS GIS Cut Line= 2
      2259702.09     13759245.79      2260604.36     13758429.08
#Sta/Elev= 30
  4302.4  597.01  4554.6  588.69  4623.6  586.34  4658.8   585.9  4701.3  584.02
  4786.5   582.2  4843.3   581.6  4864.2  582.26  4885.9  581.18  4899.8  582.09
  4949.4  578.25  4970.3  578.66  4977.7  576.99  4996.7  571.54    4997  571.04
  5000.5  571.04  5000.7  571.54  5020.4  580.54  5034.6  580.88  5062.3  579.07
  5076.4  579.34  5196.7  583.28  5237.1  585.84  5253.5  587.07  5289.4  587.76
  5331.4  590.27  5352.9  590.37    5459  594.64  5479.9  594.32  5519.4  595.95
#Mann= 6 ,-1 , 0
  4302.4     .07       0  4554.6    .035       0  4977.7     .12       0
  4996.7     .05       0  5000.7     .12       0  5237.1    .035       0
Bank Sta=4996.7,5000.7
XS Rating Curve= 0 ,0
Exp/Cntr=0.3,0.1

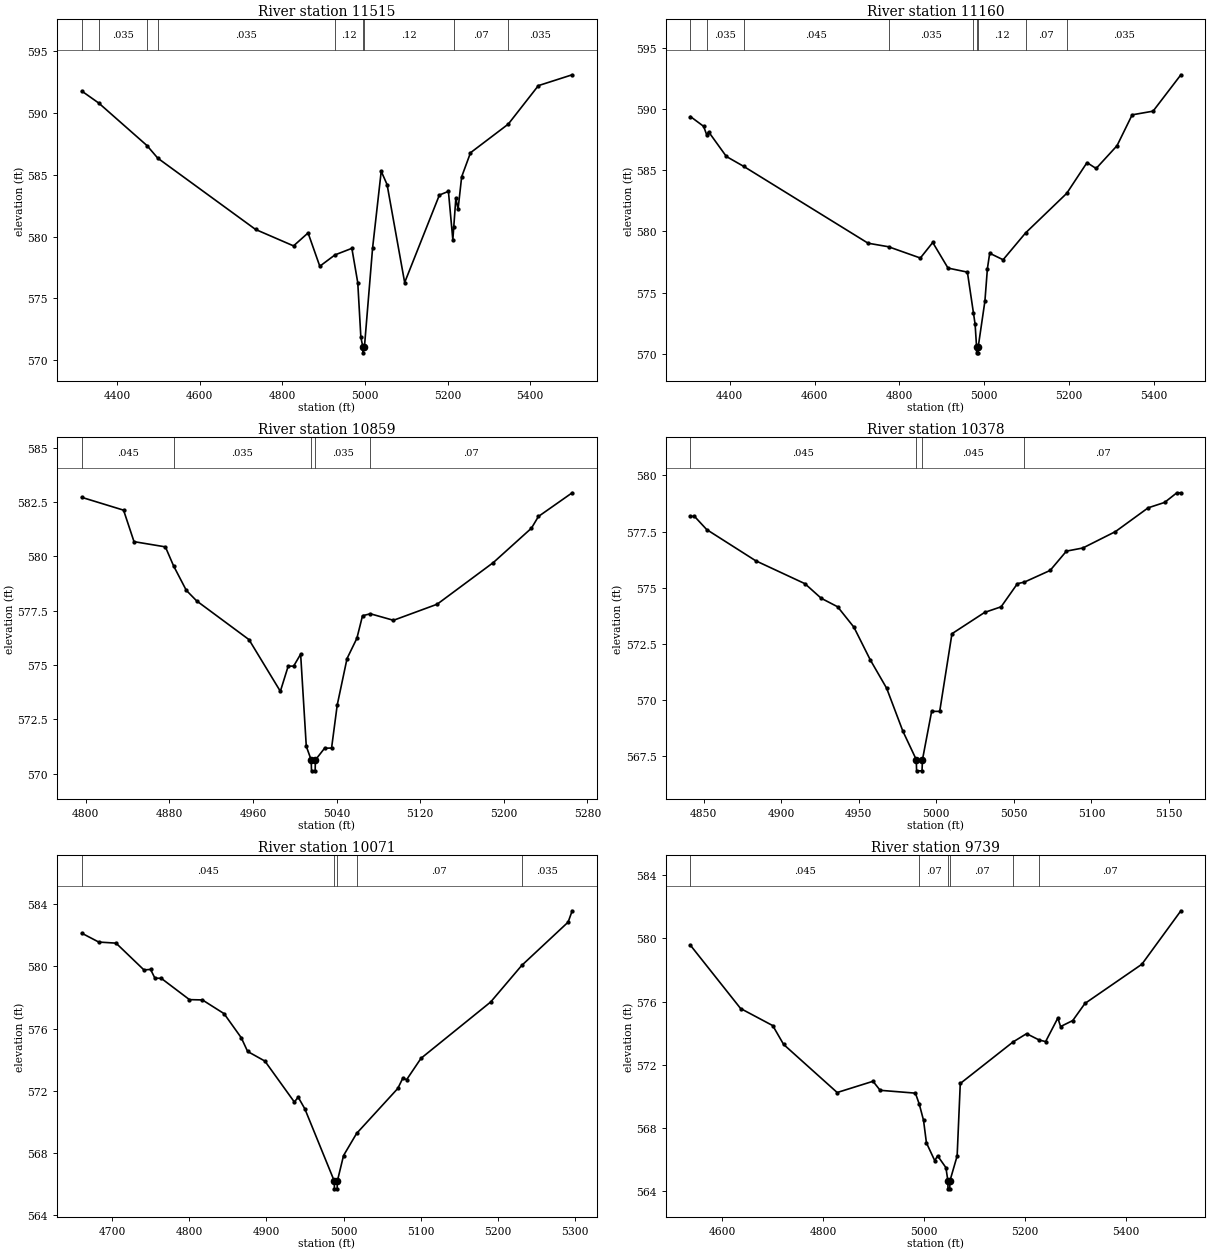
Type RM Length L Ch R = 1 ,11515   ,355,355,355
BEGIN DESCRIPTION:
J21831
END DESCRIPTION:
XS GIS Cut Line= 3
      2259959.04     13759483.35      2260609.34     13758903.14
      2260905.22     13758790.24
#Sta/Elev= 30
  4313.9  591.79    4355  590.82    4472  587.37  4498.1  586.35  4735.1  580.57
    4827  579.24  4862.2  580.29  4890.6  577.59  4927.4  578.51  4968.3  579.04
  4982.6  576.25  4990.1  571.83  4994.8  571.07    4995  570.57  4998.8  571.07
  5018.5  579.07  5039.4  585.29  5053.6  584.21  5096.2  576.27  5180.3  583.36
  5202.2  583.66  5212.9  579.74  5215.1  580.75  5220.2   583.1  5225.6  582.22
  5234.3  584.84  5255.7  586.79  5347.2  589.11  5420.1  592.23  5502.1  593.11
#Mann= 9 ,-1 , 0
  4313.9    .045       0    4355    .035       0    4472    .045       0
  4498.1    .035       0  4927.4     .12       0  4994.8     .05       0
  4998.8     .12       0  5215.1     .07       0  5347.2    .035       0
Bank Sta=4994.8,4998.8
XS Rating Curve= 0 ,0
Exp/Cntr=0.3,0.1

Type RM Length L Ch R = 1 ,11160   ,301,301,301
BEGIN DESCRIPTION:
J21830
END DESCRIPTION:
XS GIS Cut Line= 3
      2260056.43     13759565.08      2260722.26     13759280.84
      2261037.62     13758984.95
#Sta/Elev= 30
  4307.2  589.37  4338.3  588.57  4345.4  587.89  4350.1  588.12  4391.9  586.11
  4432.9   585.3    4726  579.03  4774.3  578.74  4849.3  577.82  4878.5  579.09
  4914.5     577  4960.2  576.67  4974.5  573.33  4978.4  572.42  4981.8  570.58
    4982  570.08  4985.5  570.08  4985.8  570.58  5001.5   574.3  5007.4  576.96
  5012.8  578.21  5044.4  577.68  5097.4  579.87  5194.4   583.1  5242.2  585.61
  5263.7  585.13    5313  586.99  5348.7  589.51    5398  589.81  5463.6  592.78
#Mann= 9 ,-1 , 0
  4307.2    .045       0  4345.4    .035       0  4432.9    .045       0
  4774.3    .035       0  4974.5     .12       0  4981.8     .05       0
  4985.8     .12       0  5097.4     .07       0  5194.4    .035       0
Bank Sta=4981.8,4985.8
XS Rating Curve= 0 ,0
Exp/Cntr=0.3,0.1

Type RM Length L Ch R = 1 ,10859   ,481,481,481
BEGIN DESCRIPTION:
YOUNGS TRIBUTARY 1 19.0
END DESCRIPTION:
XS GIS Cut Line= 3
        2260875.     13759724.97        2260875.       13759525.
      2260974.99     13759275.03
#Sta/Elev= 30
  4796.2  582.72  4836.2  582.13  4846.2  580.68  4876.2  580.44    4884  579.57
  4896.2  578.44  4906.2  577.95  4956.2  576.17  4986.2  573.79  4993.7  574.95
  4998.9  574.95  5005.6   575.5    5011  571.26  5015.7  570.63    5016  570.13
  5019.5  570.13  5019.7  570.63  5028.5  571.17  5035.2  571.18  5040.6  573.16
    5050   575.3  5059.4  576.23  5064.8  577.27  5072.3  577.36  5094.4  577.06
  5136.2   577.8    5190  579.72  5226.4   581.3  5233.1  581.84  5265.4  582.93
#Mann= 5 ,-1 , 0
  4796.2    .045       0    4884    .035       0  5015.7    .035       0
  5019.7    .035       0  5072.3     .07       0
Bank Sta=5015.7,5019.7
XS Rating Curve= 0 ,0
Exp/Cntr=0.3,0.1

Type RM Length L Ch R = 1 ,10378   ,307,307,307
BEGIN DESCRIPTION:
YOUNGS TRIBUTARY 1 18.0
END DESCRIPTION:
XS GIS Cut Line= 3
      2261374.99     13759674.98        2261325.       13759525.
        2261275.     13759375.01
#Sta/Elev= 30
  4841.5  578.18  4844.1  578.18    4852  577.59  4883.6   576.2  4915.3  575.18
  4925.8  574.53  4936.4  574.15  4946.9  573.24  4957.4  571.79    4968  570.52
  4978.5   568.6  4987.1  567.34  4987.3  566.84  4990.8  566.84  4991.1  567.34
    4997  569.49  5002.2  569.49  5010.1  572.95  5031.2   573.9  5041.8  574.15
  5052.3  575.18  5056.8  575.25  5073.4  575.77  5083.9  576.63  5094.5  576.77
  5115.5   577.5  5136.6  578.56  5147.2   578.8  5155.1  579.23  5157.7  579.23
#Mann= 4 ,-1 , 0
  4841.5    .045       0  4987.1    .045       0  4991.1    .045       0
  5056.8     .07       0
Bank Sta=4987.1,4991.1
XS Rating Curve= 0 ,0
Exp/Cntr=0.3,0.1

Type RM Length L Ch R = 1 ,10071   ,332,332,332
BEGIN DESCRIPTION:
J21829
END DESCRIPTION:
XS GIS Cut Line= 3
       2261508.8     13759787.03      2261621.72     13759561.19
      2261594.48     13759179.76
#Sta/Elev= 30
    4661  582.14    4683  581.57  4705.4   581.5  4741.5  579.78  4750.1  579.81
  4755.7  579.25  4763.9  579.24  4800.4  577.87  4817.2  577.85  4845.2  576.97
  4867.5  575.42  4875.7  574.54  4898.1  573.92  4936.2  571.29  4941.2   571.6
  4949.8  570.85  4987.9  566.21  4988.1  565.71  4991.6  565.71  4991.9  566.21
  4999.9  567.85  5016.8  569.27  5070.1  572.16  5076.5  572.81  5081.6  572.73
  5100.2   574.1  5190.4  577.72  5230.6  580.07  5290.6  582.85  5295.9  583.58
#Mann= 5 ,-1 , 0
    4661    .045       0  4987.9    .045       0  4991.9    .045       0
  5016.8     .07       0  5230.6    .035       0
Bank Sta=4987.9,4991.9
XS Rating Curve= 0 ,0
Exp/Cntr=0.3,0.1

Type RM Length L Ch R = 1 ,9739    ,272,272,272
BEGIN DESCRIPTION:
J21828
END DESCRIPTION:
XS GIS Cut Line= 4
      2261567.19     13759767.58      2261890.39     13759467.74
      2261952.69     13759347.04      2262100.32     13758981.85
#Sta/Elev= 30
  4537.7  579.56    4637  575.56  4700.6  574.48  4722.1  573.29  4828.1  570.25
    4899  570.96  4913.1  570.39  4982.9  570.21  4990.6  569.51    4999  568.49
  5004.7  567.07  5021.2  565.94  5026.8  566.25  5043.3   565.5  5047.2  564.66
  5047.4  564.16  5050.9  564.16  5051.2  564.66  5065.5  566.24  5071.7  570.82
  5176.3  573.45  5202.9  573.97  5227.8  573.57  5240.6  573.47  5264.8  574.96
  5270.2  574.42  5294.3   574.8  5318.4  575.88  5431.1  578.36  5508.3  581.74
#Mann= 6 ,-1 , 0
  4537.7    .045       0  4990.6     .07       0  5047.2     .05       0
  5051.2     .07       0  5176.3     .12       0  5227.8     .07       0
Bank Sta=5047.2,5051.2
XS Rating Curve= 0 ,0
Exp/Cntr=0.3,0.1

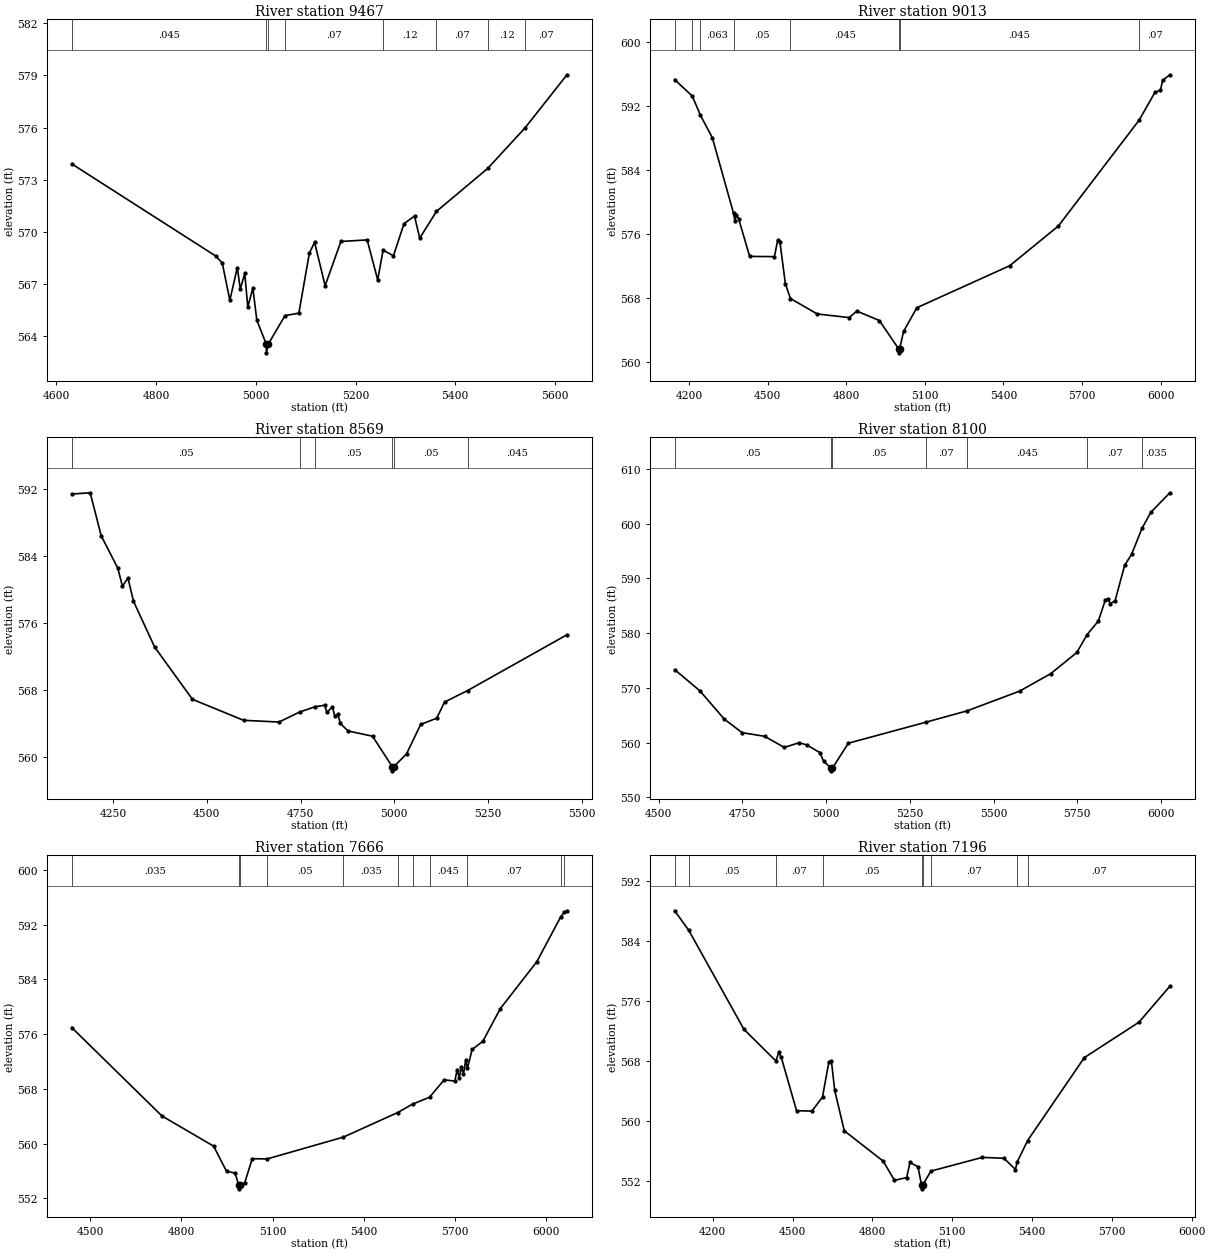
Type RM Length L Ch R = 1 ,9467    ,454,454,454
BEGIN DESCRIPTION:
YOUNGS TRIBUTARY 1 16.0
END DESCRIPTION:
XS GIS Cut Line= 3
      2261725.03     13759874.98        2262025.       13759675.
      2262225.01     13759074.98
#Sta/Elev= 30
    4631  573.91  4919.4  568.62  4932.9  568.21    4948  566.07    4963  567.95
    4969  566.72    4978  567.61    4984  565.68  4994.2  566.77  5002.1  564.93
  5021.1  563.55  5021.4  563.05  5025.1  563.55  5058.6  565.19  5086.4  565.33
  5107.5  568.78    5118   569.4  5139.1  566.91  5170.7  569.45  5223.4  569.54
  5244.5  567.24  5255.3  568.95  5276.1  568.63  5297.2  570.47  5318.3  570.91
  5328.8  569.64  5362.4  571.18  5465.2  573.65  5540.3  575.99    5624  579.03
#Mann= 8 ,-1 , 0
    4631    .045       0  5021.1    .045       0  5025.1    .045       0
  5058.6     .07       0  5255.3     .12       0  5362.4     .07       0
  5465.2     .12       0  5540.3     .07       0
Bank Sta=5021.1,5025.1
XS Rating Curve= 0 ,0
Exp/Cntr=0.3,0.1

Type RM Length L Ch R = 1 ,9013    ,444,444,444
BEGIN DESCRIPTION:
YOUNGS TRIBUTARY 1 15.0
END DESCRIPTION:
XS GIS Cut Line= 3
        2261875.       13760575.        2262375.       13759875.
      2263174.99       13759225.
#Sta/Elev= 30
  4144.5  595.29  4211.7  593.24  4242.7  590.85  4288.3  588.03  4369.2  578.59
  4374.3  577.63  4380.4  578.39    4389  577.86  4430.8  573.19  4525.5  573.16
  4537.7   575.2  4546.3  575.03  4567.2  569.76  4586.6  567.92  4688.9  565.99
  4810.6  565.54  4840.1  566.35  4926.1  565.17  4999.7  561.63  4999.9  561.13
  5003.7  561.63  5018.4   563.8  5069.2  566.77  5424.2  572.03  5609.6  576.99
  5918.1  590.23  5978.8  593.72  5999.6  593.96  6007.5   595.2  6035.5   595.9
#Mann= 8 ,-1 , 0
  4144.5    .063       0  4211.7     .05       0  4242.7    .063       0
  4369.2     .05       0  4586.6    .045       0  4999.7    .045       0
  5003.7    .045       0  5918.1     .07       0
Bank Sta=4999.7,5003.7
XS Rating Curve= 0 ,0
Exp/Cntr=0.3,0.1

Type RM Length L Ch R = 1 ,8569    ,469,469,469
BEGIN DESCRIPTION:
YOUNGS TRIBUTARY 1 14.0
END DESCRIPTION:
XS GIS Cut Line= 3
      2262024.96     13760625.03        2262725.       13760125.
      2263025.03     13759774.96
#Sta/Elev= 30
  4139.5  591.44  4188.7  591.59  4218.2  586.44  4262.4  582.58  4274.7  580.43
  4289.5   581.4  4304.2  578.63  4360.7  573.15  4461.5  566.91  4597.9   564.4
  4692.5  564.19  4748.2   565.4  4788.2  566.01  4814.2   566.2  4820.4  565.34
  4835.1  566.02  4841.2  564.88  4849.8   565.1    4856  564.03  4876.9  563.12
    4942   562.5  4994.7  558.86  4994.9  558.36  4998.8  558.86  5032.7  560.38
  5070.6  563.91  5113.4  564.65  5134.2  566.58  5195.9  567.96  5460.8  574.62
#Mann= 6 ,-1 , 0
  4139.5     .05       0  4748.2     .07       0  4788.2     .05       0
  4994.7     .05       0  4998.8     .05       0  5195.9    .045       0
Bank Sta=4994.7,4998.8
XS Rating Curve= 0 ,0
Exp/Cntr=0.3,0.1

Type RM Length L Ch R = 1 ,8100    ,434,434,434
BEGIN DESCRIPTION:
YOUNGS TRIBUTARY 1 13.0
END DESCRIPTION:
XS GIS Cut Line= 3
        2262825.     13760874.99        2263025.       13760475.
      2263675.01     13759674.99
#Sta/Elev= 30
  4548.2  573.34  4623.7  569.44  4696.3  564.29  4749.4  561.82  4816.5  561.15
  4875.2  559.12  4919.9  559.98  4942.3  559.58  4981.4  558.18  4992.6  556.62
  5014.9  555.34  5015.1  554.84  5019.1  555.34  5066.5  559.89  5296.9  563.71
  5420.8   565.8  5577.9  569.41  5670.6   572.6  5748.7  576.48  5778.5  579.68
  5812.8  582.23  5833.7   586.1  5841.6   586.3    5848  585.41  5862.4  585.88
  5891.1  592.37    5912  594.43    5943  599.15  5969.4  602.09  6026.2  605.65
#Mann= 7 ,-1 , 0
  4548.2     .05       0  5014.9     .05       0  5019.1     .05       0
  5296.9     .07       0  5420.8    .045       0  5778.5     .07       0
    5943    .035       0
Bank Sta=5014.9,5019.1
XS Rating Curve= 0 ,0
Exp/Cntr=0.3,0.1

Type RM Length L Ch R = 1 ,7666    ,470,470,470
BEGIN DESCRIPTION:
YOUNGS TRIBUTARY 1 12.0
END DESCRIPTION:
XS GIS Cut Line= 3
        2262975.       13761075.        2263375.       13760675.
        2264075.       13759875.
#Sta/Elev= 30
  4439.3  576.96  4736.3  564.04    4906  559.64  4948.4  555.97  4976.7  555.71
  4988.7  553.91    4989  553.41    4993  553.91  5008.3  554.31    5033  557.81
  5082.2  557.78  5332.7  560.96  5511.1  564.55  5560.9  565.79  5616.2  566.79
  5664.2  569.33  5699.3  569.14  5706.9  570.83  5713.5  569.66  5721.1  571.16
  5727.7  570.16  5735.3  572.26  5740.5  570.99  5756.2  573.77  5791.3  574.94
  5848.3  579.69  5968.8  586.57  6047.8  593.14  6059.4  593.76    6068  594.01
#Mann= 11 ,-1 , 0
  4439.3    .035       0  4988.7    .035       0    4993    .035       0
  5082.2     .05       0  5332.7    .035       0  5511.1    .045       0
  5560.9    .035       0  5616.2    .045       0  5740.5     .07       0
  6047.8     .05       0  6059.4     .07       0
Bank Sta=4988.7,4993
XS Rating Curve= 0 ,0
Exp/Cntr=0.3,0.1

Type RM Length L Ch R = 1 ,7196    ,437,437,437
BEGIN DESCRIPTION:
YOUNGS TRIBUTARY 1 11.0
END DESCRIPTION:
XS GIS Cut Line= 3
      2262875.01     13761524.99        2263675.       13761025.
      2264125.02     13760224.97
#Sta/Elev= 30
  4056.9  588.08  4109.7  585.48  4316.9  572.27  4437.5  568.02  4447.8  569.17
  4457.2  568.56    4515  561.39  4572.8  561.34  4612.5  563.21  4636.5  567.92
  4645.9  568.05  4658.3  564.13  4694.3  558.71  4840.5  554.66  4882.9   552.1
  4928.9  552.46  4941.3  554.48  4971.4  553.91  4984.6  551.46  4984.8  550.96
  4988.9  551.46  5020.1  553.33  5213.5  555.16  5294.5  555.04  5337.8  553.54
  5343.6  554.49  5383.5  557.41  5596.6  568.48  5801.8   573.2  5918.2  578.01
#Mann= 9 ,-1 , 0
  4056.9    .035       0  4109.7     .05       0  4437.5     .07       0
  4612.5     .05       0  4984.6     .05       0  4988.9     .05       0
  5020.1     .07       0  5343.6     .05       0  5383.5     .07       0
Bank Sta=4984.6,4988.9
XS Rating Curve= 0 ,0
Exp/Cntr=0.3,0.1

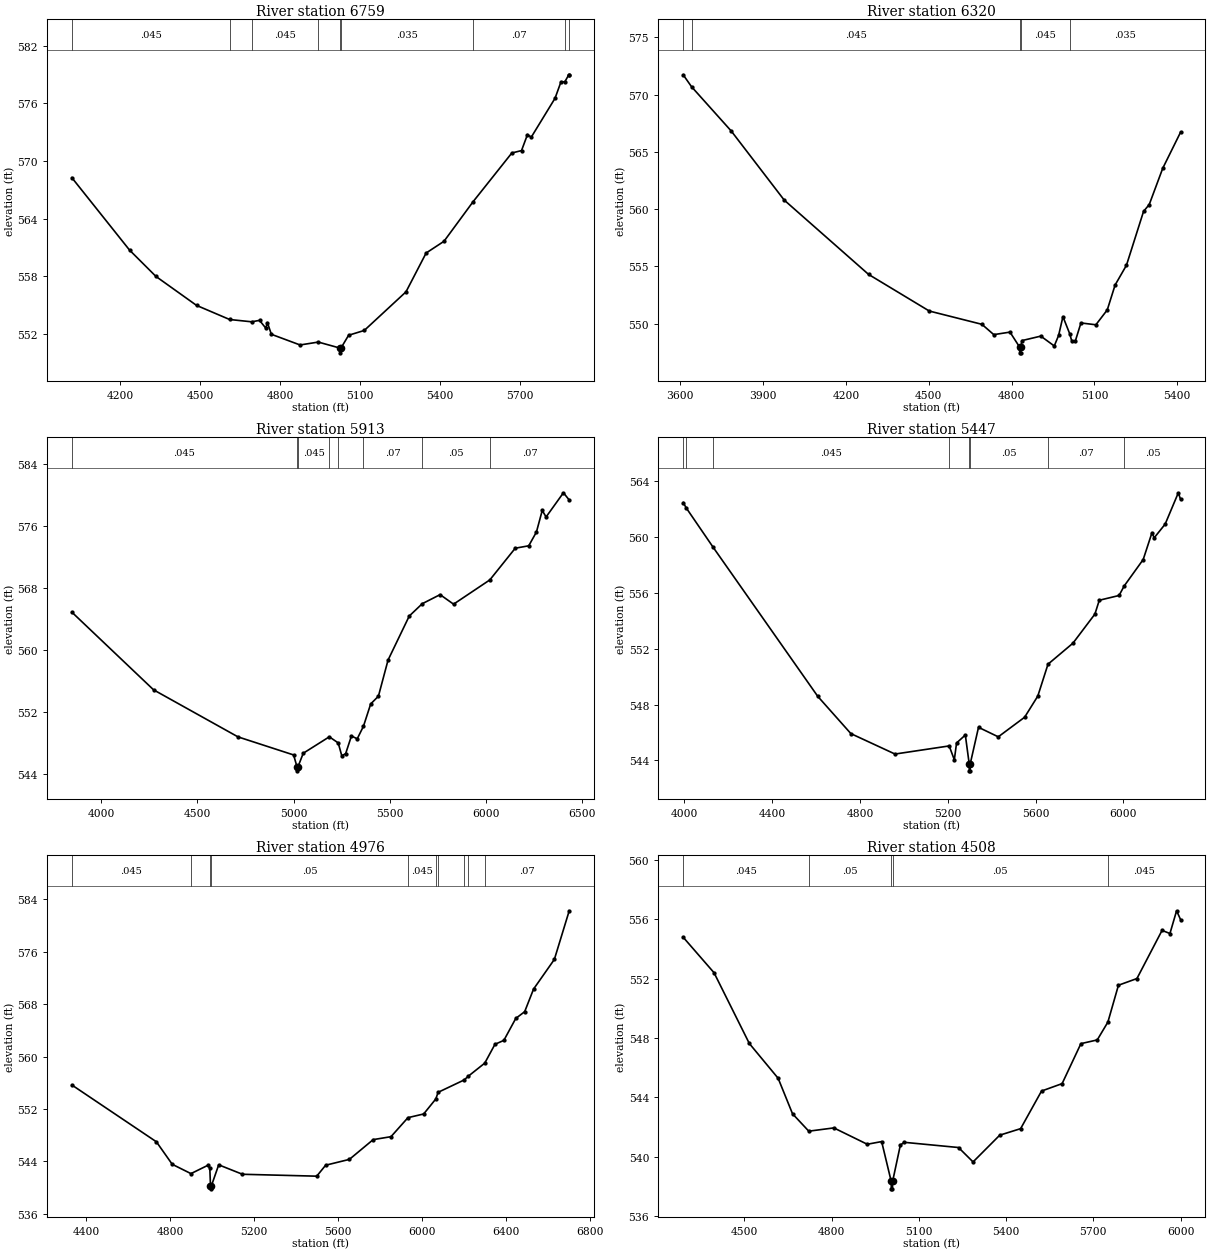
Type RM Length L Ch R = 1 ,6759    ,439,439,439
BEGIN DESCRIPTION:
YOUNGS TRIBUTARY 1 10.0
END DESCRIPTION:
XS GIS Cut Line= 3
      2263275.02     13761674.98        2264075.       13761125.
      2264474.99     13760325.02
#Sta/Elev= 30
  4019.4  568.27  4235.9  560.73  4334.9  557.99  4486.9  554.98    4611  553.51
  4693.7  553.27  4723.2  553.42  4746.7  552.61  4752.7  553.19  4767.6  551.97
  4875.2  550.86  4943.6  551.16  5024.3  550.54  5024.6  550.04  5028.7  550.54
  5057.3  551.87    5116  552.37  5272.5  556.39    5348  560.43    5415  561.65
  5524.1  565.77  5669.4  570.84  5705.7  571.09  5728.1  572.76  5742.1  572.48
  5831.5  576.54  5853.9  578.26    5868  578.24    5883  578.98  5884.6  578.98
#Mann= 9 ,-1 , 0
  4019.4    .045       0    4611     .05       0  4693.7    .045       0
  4943.6    .035       0  5024.3    .035       0  5028.7    .035       0
  5524.1     .07       0    5868     .05       0    5883     .07       0
Bank Sta=5024.3,5028.7
XS Rating Curve= 0 ,0
Exp/Cntr=0.3,0.1

Type RM Length L Ch R = 1 ,6320    ,407,407,407
BEGIN DESCRIPTION:
YOUNGS TRIBUTARY 1 9.0
END DESCRIPTION:
XS GIS Cut Line= 3
      2263774.98     13762375.03        2264475.       13761175.
        2264575.     13760774.99
#Sta/Elev= 30
  3610.4  571.74  3640.6   570.7  3784.5  566.83  3976.3   560.8  4281.9  554.31
  4501.9  551.11  4692.5  549.95  4735.5  549.05  4794.2  549.27  4829.1  547.96
  4829.5  547.46  4833.3  547.46  4833.6  547.96  4837.6  548.53  4905.8  548.92
  4954.6  548.06  4970.3  548.98    4986  550.62  5010.5  549.13  5017.7  548.51
  5030.6  548.47  5051.2  550.07  5105.3  549.91  5146.6  551.21  5174.9  553.38
  5216.1  555.11    5278  559.81  5298.6  560.41  5347.6  563.58    5412  566.72
#Mann= 5 ,-1 , 0
  3610.4    .035       0  3640.6    .045       0  4829.1    .045       0
  4833.6    .045       0  5010.5    .035       0
Bank Sta=4829.1,4833.6
XS Rating Curve= 0 ,0
Exp/Cntr=0.3,0.1

Type RM Length L Ch R = 1 ,5913    ,466,466,466
BEGIN DESCRIPTION:
YOUNGS TRIBUTARY 1 8.0
END DESCRIPTION:
XS GIS Cut Line= 3
      2263974.99     13762225.01        2264775.       13761425.
        2264825.     13759974.95
#Sta/Elev= 30
  3849.2  564.84  4273.5  554.82  4711.9  548.75  5000.6  546.42  5018.3  544.87
  5018.6  544.37  5022.9  544.87  5050.6  546.64    5186  548.76  5232.2  547.97
  5250.7  546.31  5270.8  546.59  5300.8  548.87  5330.8   548.5  5363.2  550.12
  5400.8     553  5440.9     554  5490.9  558.66    5601  564.34  5668.5  565.93
  5761.1   567.1  5831.1  565.87  6019.3     569  6151.3  573.09  6221.3   573.4
  6261.3  575.18  6291.4  577.96  6311.4  577.12  6401.4  580.24  6431.5  579.31
#Mann= 8 ,-1 , 0
  3849.2    .045       0  5018.3    .045       0  5022.9    .045       0
    5186     .05       0  5232.2    .035       0  5363.2     .07       0
  5668.5     .05       0  6019.3     .07       0
Bank Sta=5018.3,5022.9
XS Rating Curve= 0 ,0
Exp/Cntr=0.3,0.1

Type RM Length L Ch R = 1 ,5447    ,471,471,471
BEGIN DESCRIPTION:
YOUNGS TRIBUTARY 1 7.0
END DESCRIPTION:
XS GIS Cut Line= 3
        2265075.     13762575.02        2265175.       13761575.
      2265198.74     13760314.93
#Sta/Elev= 30
    3995  562.43  4009.7  562.03  4132.2  559.22  4608.1  548.58  4758.8  545.92
  4959.8  544.46  5206.5  545.04    5230  544.05  5240.1  545.25  5280.1  545.82
  5297.7  543.76  5298.1  543.26  5302.1  543.26  5302.4  543.76  5340.1  546.37
  5430.1  545.69  5550.1  547.09  5610.1   548.6  5656.6  550.88  5770.1  552.38
  5870.2  554.46  5890.2  555.45  5980.2  555.79    6004  556.48  6090.2  558.36
  6130.2  560.28  6140.2  559.91  6190.2  560.89  6250.2  563.13  6260.3  562.66
#Mann= 8 ,-1 , 0
    3995    .063       0  4009.7    .035       0  4132.2    .045       0
  5206.5     .05       0  5297.7    .045       0  5302.4     .05       0
  5656.6     .07       0    6004     .05       0
Bank Sta=5297.7,5302.4
XS Rating Curve= 0 ,0
Exp/Cntr=0.3,0.1

Type RM Length L Ch R = 1 ,4976    ,468,468,468
BEGIN DESCRIPTION:
YOUNGS TRIBUTARY 1 6.0
END DESCRIPTION:
XS GIS Cut Line= 3
      2265275.01     13762274.98        2265575.       13761675.
      2266774.97     13760475.03
#Sta/Elev= 30
    4333  555.66  4735.5     547  4810.9  543.57    4900  542.15  4981.4  543.43
  4989.8  542.95    4993  540.33  4993.4  539.83  4997.8  540.33  5032.1  543.49
  5145.2  542.05  5498.8  541.76  5541.2  543.43  5654.3  544.32  5767.5  547.33
  5852.3  547.78  5933.1  550.68  6007.9  551.24  6065.7  553.53  6076.6  554.54
  6200.9  556.43  6220.1  556.99  6298.7  558.99  6347.3  561.86  6389.7  562.46
  6446.3   565.8  6488.7  566.83  6531.1  570.28  6630.1   574.8  6700.8  582.21
#Mann= 10 ,-1 , 0
    4333    .045       0    4900     .05       0    4993     .05       0
  4997.8     .05       0  5933.1    .045       0  6065.7     .05       0
  6076.6    .045       0  6200.9     .07       0  6220.1    .045       0
  6298.7     .07       0
Bank Sta=4993,4997.8
XS Rating Curve= 0 ,0
Exp/Cntr=0.3,0.1

Type RM Length L Ch R = 1 ,4508    ,420,420,420
BEGIN DESCRIPTION:
YOUNGS TRIBUTARY 1 5.0
END DESCRIPTION:
XS GIS Cut Line= 3
      2265425.04     13762324.97        2265975.       13761875.
      2266575.01     13761074.99
#Sta/Elev= 30
  4289.4  554.78  4395.6  552.39  4516.9  547.63    4616  545.29  4665.5   542.9
  4721.4  541.73  4807.6  541.95  4922.5  540.85    4972  541.03  5004.9  538.35
  5005.2  537.85  5009.3  537.85  5009.7  538.35  5036.4   540.8    5050  540.98
  5236.4  540.63  5286.4  539.66  5378.1  541.46    5450   541.9  5521.9  544.43
  5592.7  544.93  5657.3  547.62  5713.5  547.87  5750.1  549.07  5786.4  551.55
    5850     552  5936.4  555.24  5963.5  555.03  5986.4  556.56    6000  555.97
#Mann= 5 ,-1 , 0
  4289.4    .045       0  4721.4     .05       0  5004.9     .05       0
  5009.7     .05       0  5750.1    .045       0
Bank Sta=5004.9,5009.7
XS Rating Curve= 0 ,0
Exp/Cntr=0.3,0.1