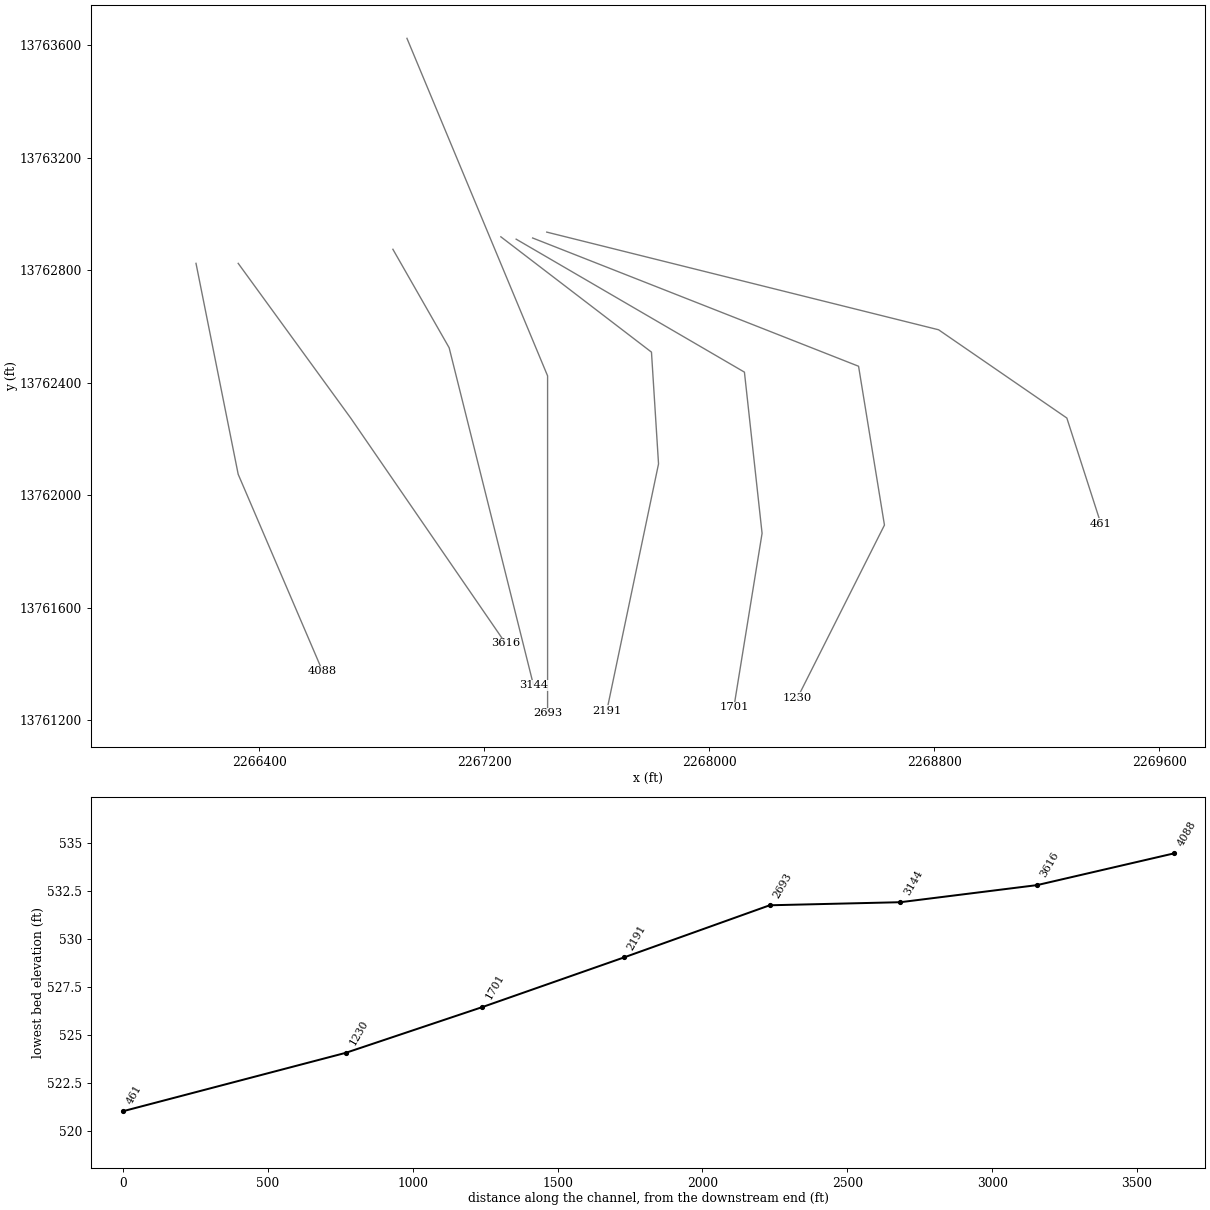
HEC-RAS study YOUNGS TRIBUTARY 1.prj: YOUNGS TRIBUTARY 1 Base Level Engineering

--- YOUNGS TRIBUTARY 1.g01 (geometry) --- (continued)

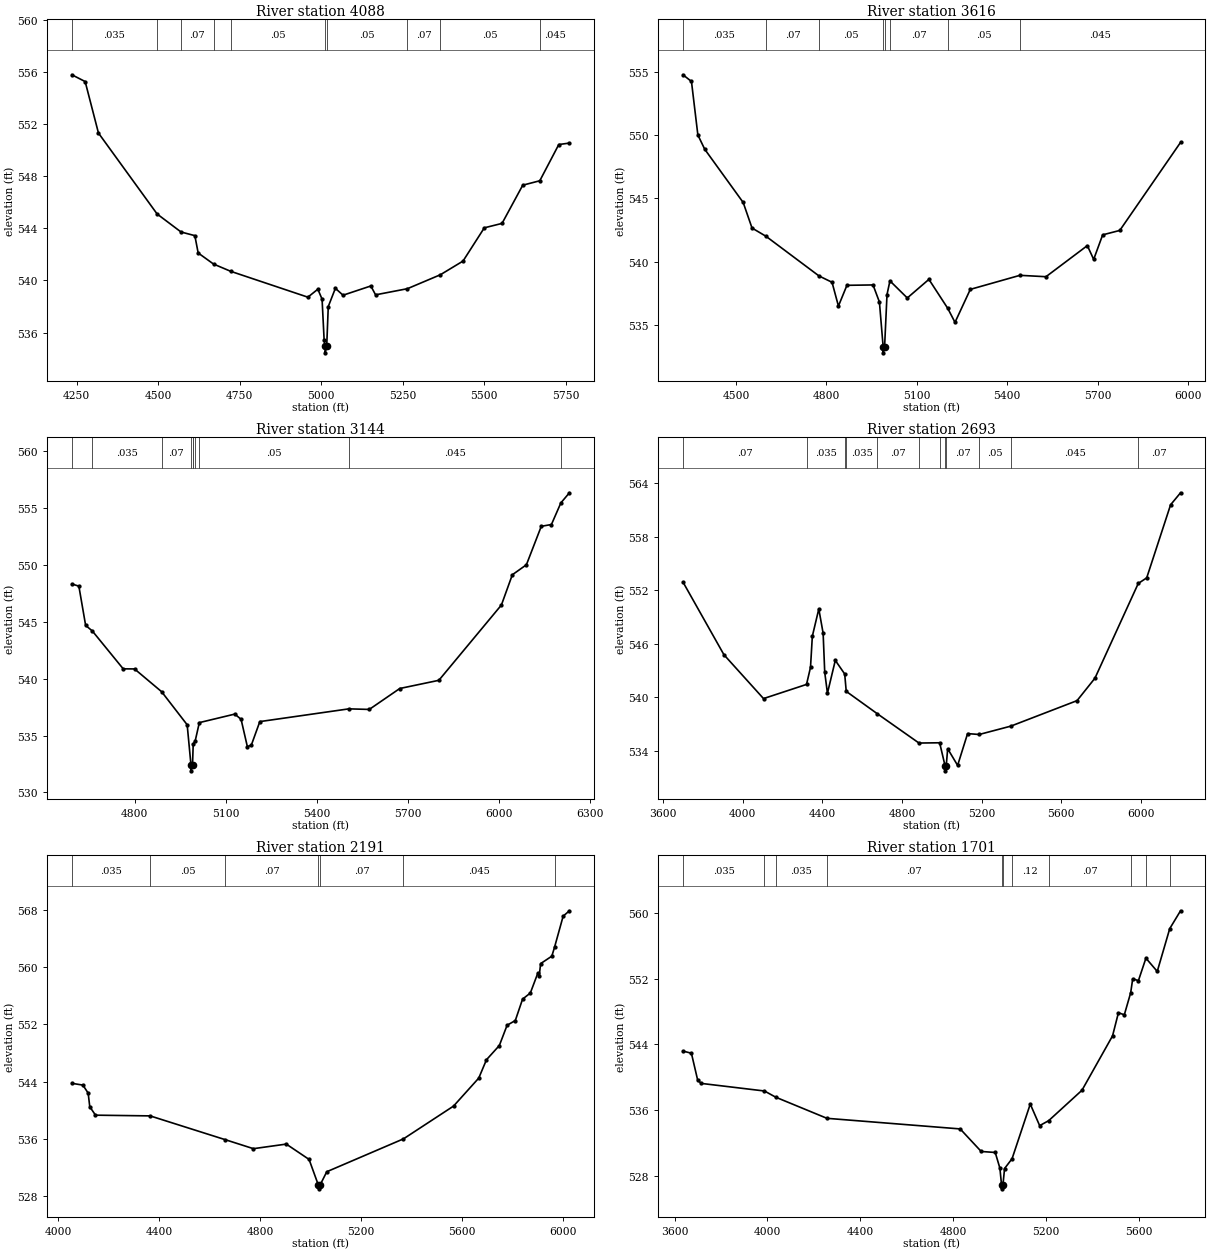
Type RM Length L Ch R = 1 ,4088    ,472,472,472
BEGIN DESCRIPTION:
YOUNGS TRIBUTARY 1 4.0
END DESCRIPTION:
XS GIS Cut Line= 3
        2266175.     13762824.99        2266325.       13762075.
      2266624.99     13761375.01
#Sta/Elev= 30
  4235.2  555.77    4276  555.25  4316.8   551.3  4496.8  545.09  4570.1  543.71
  4612.5  543.43  4622.7   542.1  4669.9  541.25  4722.9  540.69  4959.2  538.71
  4989.8  539.32  5002.8  538.56  5009.1  535.43  5012.1  534.94  5012.4  534.44
    5017  534.94  5021.8  537.99  5043.6  539.39  5067.1  538.86  5152.4  539.57
  5166.9  538.89  5264.5  539.36  5365.7  540.43  5435.2  541.48  5500.5  544.03
  5554.9  544.37  5618.4   547.3  5670.7  547.64    5729  550.42  5761.6  550.53
#Mann= 10 ,-1 , 0
  4235.2    .035       0  4496.8    .045       0  4570.1     .07       0
  4669.9    .045       0  4722.9     .05       0  5012.1     .05       0
    5017     .05       0  5264.5     .07       0  5365.7     .05       0
  5670.7    .045       0
Bank Sta=5012.1,5017
XS Rating Curve= 0 ,0
Exp/Cntr=0.3,0.1

Type RM Length L Ch R = 1 ,3616    ,472,472,472
BEGIN DESCRIPTION:
YOUNGS TRIBUTARY 1 3.0
END DESCRIPTION:
XS GIS Cut Line= 3
      2266325.01     13762824.99        2266725.       13762275.
      2267275.01     13761474.98
#Sta/Elev= 30
  4324.3  554.78  4352.5  554.25  4373.7  550.02  4396.5  548.89  4524.1  544.68
  4553.4  542.66  4599.6  542.01  4775.7  538.87  4818.9  538.37  4840.1  536.49
  4868.3  538.13  4954.9  538.16  4976.1  536.81  4988.4  533.29  4988.7  532.79
  4993.3  533.29  5001.3   537.4    5011  538.48  5068.6  537.13  5140.3   538.6
  5202.8  536.31  5226.9   535.2  5277.7  537.81  5442.4  538.92  5528.7  538.81
    5666  541.27    5687  540.18  5716.8  542.12  5773.6  542.47  5975.2  549.43
#Mann= 8 ,-1 , 0
  4324.3    .035       0  4599.6     .07       0  4775.7     .05       0
  4988.4     .05       0  4993.3     .05       0    5011     .07       0
  5202.8     .05       0  5442.4    .045       0
Bank Sta=4988.4,4993.3
XS Rating Curve= 0 ,0
Exp/Cntr=0.3,0.1

Type RM Length L Ch R = 1 ,3144    ,451,451,451
BEGIN DESCRIPTION:
YOUNGS TRIBUTARY 1 2.0
END DESCRIPTION:
XS GIS Cut Line= 3
      2266874.99     13762875.02        2267075.       13762525.
      2267375.01     13761324.97
#Sta/Elev= 30
  4592.6  548.33  4615.7  548.14    4638  544.69    4660   544.2  4761.8  540.87
  4799.2  540.86  4888.4  538.86  4972.7  535.95  4985.3   532.4  4985.7   531.9
  4990.3   532.4  4992.6  534.24  4999.4  534.56  5012.8  536.14  5129.7  536.89
  5150.4  536.43    5171  534.04  5183.9  534.14  5212.2  536.23  5505.6  537.35
    5573   537.3  5673.5  539.14  5802.3  539.86  6008.5  546.48  6044.5  549.14
  6090.9  550.02  6139.9   553.4  6173.4  553.56  6204.5  555.46  6232.7  556.35
#Mann= 10 ,-1 , 0
  4592.6    .063       0    4660    .035       0  4888.4     .07       0
  4985.3     .05       0  4990.3     .07       0  4992.6     .05       0
  4999.4     .07       0  5012.8     .05       0  5505.6    .045       0
  6204.5     .07       0
Bank Sta=4985.3,4990.3
XS Rating Curve= 0 ,0
Exp/Cntr=0.3,0.1

Type RM Length L Ch R = 1 ,2693    ,502,502,502
BEGIN DESCRIPTION:
YOUNGS TRIBUTARY 1 1.0
END DESCRIPTION:
XS GIS Cut Line= 3
      2266924.99     13763625.03        2267425.       13762425.
        2267425.     13761225.03
#Sta/Elev= 30
  3699.3  552.93  3905.2  544.77    4104  539.85  4320.1  541.44  4340.1  543.36
  4349.3  546.85  4381.8  549.91  4403.5  547.19  4411.6  542.79  4425.2  540.45
  4464.7  544.14  4511.9  542.61  4519.6  540.66  4674.4  538.17  4885.1  534.86
    4989  534.89  5016.8  532.24  5017.2  531.74  5021.8  532.24  5029.3  534.22
  5079.3  532.35  5129.3  535.92  5187.6  535.82  5346.9  536.76  5679.3  539.62
  5769.3  542.14  5986.8  552.77  6029.3   553.4  6149.3   561.6  6199.3  562.95
#Mann= 12 ,-1 , 0
  3699.3     .07       0  4320.1    .035       0  4511.9    .063       0
  4519.6    .035       0  4674.4     .07       0  4885.1     .05       0
    4989     .07       0  5016.8     .05       0  5021.8     .07       0
  5187.6     .05       0  5346.9    .045       0  5986.8     .07       0
Bank Sta=5016.8,5021.8
XS Rating Curve= 0 ,0
Exp/Cntr=0.3,0.1

Type RM Length L Ch R = 1 ,2191    ,490,490,490
BEGIN DESCRIPTION:
J21827
END DESCRIPTION:
XS GIS Cut Line= 4
      2267258.87     13762919.36      2267794.34     13762509.39
      2267819.44     13762111.96      2267635.37     13761233.45
#Sta/Elev= 30
    4054  543.77  4097.7  543.52  4118.6   542.4  4124.9   540.5  4147.6  539.32
  4363.8  539.22  4659.3  535.92  4772.9  534.64  4903.1  535.28  4993.3  533.14
  5030.3  529.53  5030.8  529.03  5036.4  529.53  5063.4  531.42    5367  536.01
  5565.4  540.59  5665.2   544.5  5695.7  547.06  5746.7  549.05  5777.4  551.88
  5809.9  552.54  5838.7  555.53  5869.4  556.38  5899.5   559.2  5904.6   558.8
  5910.2  560.49  5954.5  561.53  5965.3  562.78  5999.4  567.12  6024.2  567.87
#Mann= 7 ,-1 , 0
    4054    .035       0  4363.8     .05       0  4659.3     .07       0
  5030.3     .05       0  5036.4     .07       0    5367    .045       0
  5965.3     .07       0
Bank Sta=5030.3,5036.4
XS Rating Curve= 0 ,0
Exp/Cntr=0.3,0.1

Type RM Length L Ch R = 1 ,1701    ,471,471,471
BEGIN DESCRIPTION:
J21826
END DESCRIPTION:
XS GIS Cut Line= 4
      2267313.27     13762910.98      2268124.83     13762438.27
      2268187.58     13761865.14      2268087.18     13761245.98
#Sta/Elev= 30
  3636.2  543.18  3672.5  542.92  3699.8  539.62  3715.5  539.25  3987.2  538.33
  4036.2  537.57  4256.3  535.01  4830.2  533.72  4920.7  530.98  4981.1  530.86
  5001.2  528.95  5008.2  526.94  5008.7  526.44  5014.4  526.94  5021.3  528.91
  5053.6   530.1    5132  536.74  5172.4  534.12  5211.1  534.72  5354.7  538.42
  5486.4  545.03  5511.7  547.84  5537.1  547.59  5564.4  550.26  5573.3  551.97
  5597.8  551.74  5630.1  554.47  5678.9  552.86  5732.7  558.06  5779.2  560.23
#Mann= 11 ,-1 , 0
  3636.2    .035       0  3987.2     .05       0  4036.2    .035       0
  4256.3     .07       0  5008.2     .05       0  5014.4     .07       0
  5053.6     .12       0  5211.1     .07       0  5564.4    .045       0
  5630.1     .07       0  5732.7    .045       0
Bank Sta=5008.2,5014.4
XS Rating Curve= 0 ,0
Exp/Cntr=0.3,0.1

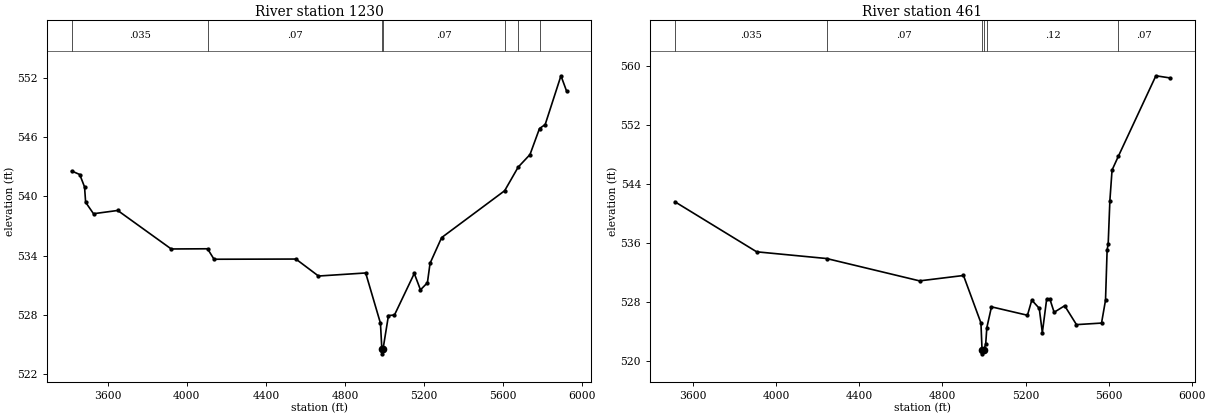
Type RM Length L Ch R = 1 ,1230    ,769,769,769
BEGIN DESCRIPTION:
J21825
END DESCRIPTION:
XS GIS Cut Line= 4
      2267371.84     13762915.17      2268530.63     13762459.19
      2268622.66     13761894.42      2268313.21      13761279.7
#Sta/Elev= 30
  3416.5  542.58  3457.7  542.22  3482.1  540.96  3487.5  539.41  3527.4  538.25
    3650  538.58  3920.9  534.68  4104.7   534.7  4137.6  533.64    4552  533.66
  4666.4  531.94  4905.3  532.25  4980.1  527.16  4987.1  524.56  4987.6  524.06
  4993.3  524.56  5020.6  527.94    5051  527.99  5151.3   532.2  5182.7  530.54
  5217.8  531.26  5231.2  533.23  5289.7  535.83  5608.9  540.58  5677.3  542.97
  5737.1  544.24  5785.3  546.88    5814  547.28  5893.9  552.22  5922.2  550.68
#Mann= 7 ,-1 , 0
  3416.5    .035       0  4104.7     .07       0  4987.1     .05       0
  4993.3     .07       0  5608.9    .045       0  5677.3     .07       0
  5785.3    .045       0
Bank Sta=4987.1,4993.3
XS Rating Curve= 0 ,0
Exp/Cntr=0.3,0.1

Type RM Length L Ch R = 1 ,461     ,0,0,0
BEGIN DESCRIPTION:
J21824
END DESCRIPTION:
XS GIS Cut Line= 4
      2267422.01      13762936.1       2268815.1     13762588.87
       2269271.1     13762275.11      2269391.96     13761900.03
#Sta/Elev= 30
  3511.8  541.63  3905.3  534.85    4242  533.94  4689.7  530.91  4901.3  531.64
  4985.3  525.21  4990.7  521.52  4991.2  521.02  4997.7  521.52  5008.1  522.29
  5013.7  524.57  5036.1  527.39  5209.3  526.25  5230.2   528.3  5266.1  527.19
    5281  523.89  5301.9  528.46  5316.8  528.48  5337.8  526.65  5388.5  527.54
  5445.3  524.98    5566  525.19  5585.2  528.29  5592.9  535.08  5598.1  535.95
  5606.2   541.8  5616.7  545.93  5646.7  547.78  5827.8  558.71  5895.1  558.42
#Mann= 6 ,-1 , 0
  3511.8    .035       0    4242     .07       0  4990.7     .05       0
  4997.7     .07       0  5013.7     .12       0  5646.7     .07       0
Bank Sta=4990.7,4997.7
XS Rating Curve= 0 ,0
Exp/Cntr=0.3,0.1

Chan Stop Cuts=-1
Use User Specified Reach Order=0
Composite Channel Slope=5