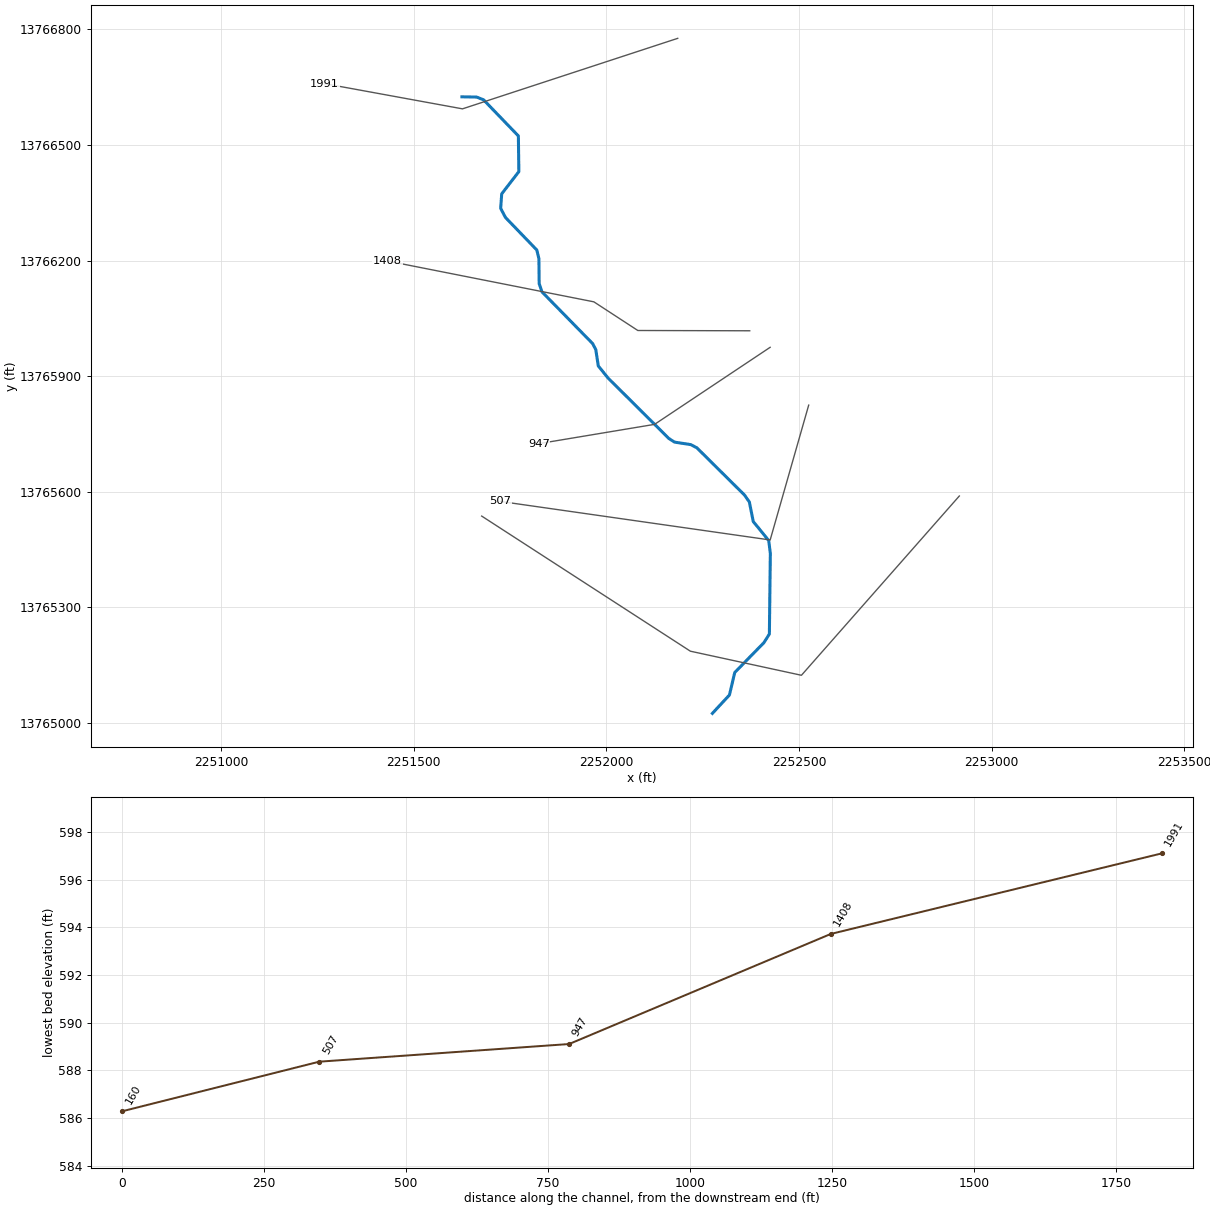
--- YOUNGS TRIBUTARY 10.prj (project) ---

Proj Title=YOUNGS TRIBUTARY 10 Base Level Engineering
Current Plan=p01
Default Exp/Contr=0.3,0.1
English Units
Geom File=g01
Flow File=f01
Plan File=p01
BEGIN DESCRIPTION:
YOUNGS TRIBUTARY 10
END DESCRIPTION:

--- YOUNGS TRIBUTARY 10.p01 (plan) ---

Plan Title=Multiple Run
Short Identifier=Multiple
Geom File=g01
Flow File=f01
Subcritical Flow
K Sum by GR= 0
Std Step Tol= 0.01
Critical Tol= 0.01
Num of Std Step Trials= 20
Max Error Tol= 0.3
Flow Tol Ratio= 0.001
Split Flow NTrial= 30
Split Flow Tol= 0.02
Split Flow Ratio= 0.02
Log Output Level= 0
Friction Slope Method= 1
Unsteady Friction Slope Method= 2
Unsteady Bridges Friction Slope Method= 1
Parabolic Critical Depth
Global Vel Dist=  1 , 1 , 1
Global Log Level= 0
CheckData=True
Encroach Param= -1, 0, 0, 0
BEGIN DESCRIPTION:
Multiple Run
END DESCRIPTION:

--- YOUNGS TRIBUTARY 10.f01 (steady flow) ---

Flow Title=Multiple
Number of Profiles=7
Profile Names=10-year,25-year,50-year,1pct_min,100-year,1pct_plu,500-year
River Rch & RM= YOUNGS TRIBUTARY,Reach-1,1991
     624    1000    1337     865    1725    3442    2844
Boundary for River Rch & Prof#=YOUNGS TRIBUTARY,Reach-1,1
Up Type=0
Dn Type=3
Dn Slope=0.005
Boundary for River Rch & Prof#=YOUNGS TRIBUTARY,Reach-1,2
Up Type=0
Dn Type=3
Dn Slope=0.005
Boundary for River Rch & Prof#=YOUNGS TRIBUTARY,Reach-1,3
Up Type=0
Dn Type=3
Dn Slope=0.005
Boundary for River Rch & Prof#=YOUNGS TRIBUTARY,Reach-1,4
Up Type=0
Dn Type=3
Dn Slope=0.005
Boundary for River Rch & Prof#=YOUNGS TRIBUTARY,Reach-1,5
Up Type=0
Dn Type=3
Dn Slope=0.005
Boundary for River Rch & Prof#=YOUNGS TRIBUTARY,Reach-1,6
Up Type=0
Dn Type=3
Dn Slope=0.005
Boundary for River Rch & Prof#=YOUNGS TRIBUTARY,Reach-1,7
Up Type=0
Dn Type=3
Dn Slope=0.005

--- YOUNGS TRIBUTARY 10.g01 (geometry) ---

Geom Title=Existing Conditions

River Reach=YOUNGS TRIBUTARY,Reach-1
Reach XY= 30
      2251625.00     13766625.00      2251663.17     13766624.41
      2251681.24     13766617.25      2251771.55     13766523.52
      2251772.81     13766430.97      2251728.34     13766373.25
      2251725.61     13766335.62      2251738.15     13766311.80
      2251819.46     13766227.42      2251824.86     13766204.94
      2251825.53     13766140.22      2251832.86     13766118.83
      2251964.22     13765984.68      2251972.46     13765968.95
      2251978.98     13765926.65      2252004.62     13765894.84
      2252161.79     13765738.63      2252176.65     13765728.98
      2252218.95     13765722.47      2252234.68     13765714.22
      2252358.36     13765591.68      2252371.06     13765573.37
      2252381.14     13765522.83      2252421.25     13765473.45
      2252425.44     13765440.18      2252422.94     13765230.86
      2252408.54     13765208.25      2252333.07     13765131.08
      2252319.30     13765072.65      2252275.00     13765025.00

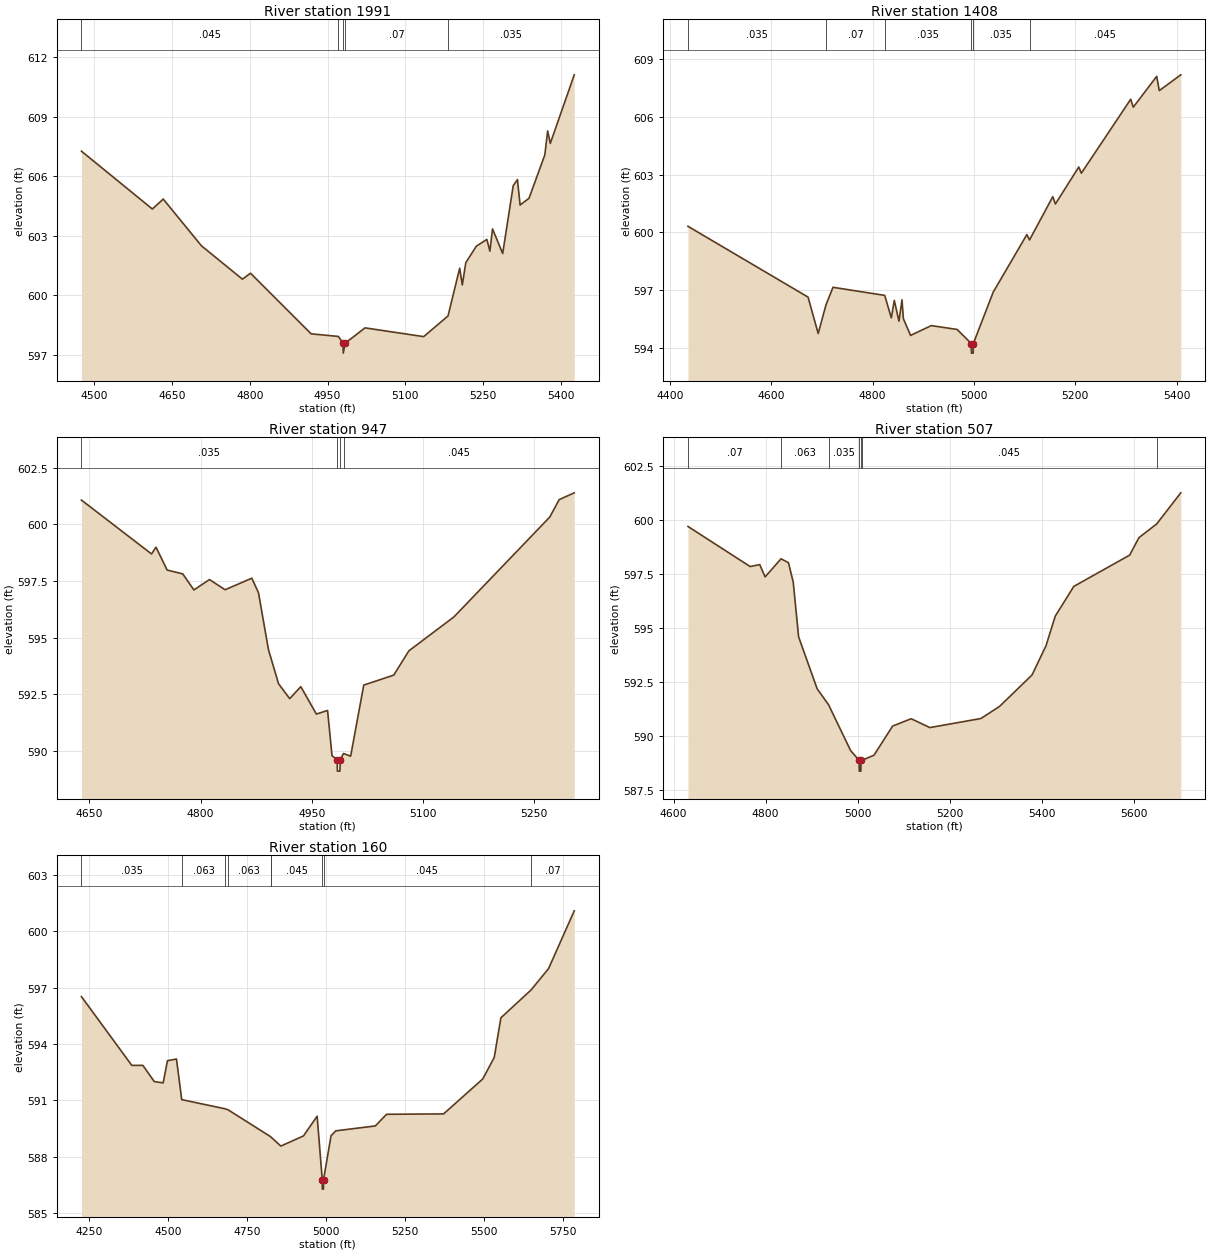
Type RM Length L Ch R = 1,1991,583,583,583
BEGIN DESCRIPTION:
YOUNGS TRIBUTARY 10 4.0
END DESCRIPTION:
XS GIS Cut Line= 3
      2252185.09     13766776.79      2251626.52     13766593.81
      2251269.12     13766659.14
#Sta/Elev= 30
  4475.0  607.26  4611.9  604.35  4632.9  604.85  4706.6  602.50  4785.7  600.82
  4801.3  601.12  4918.4  598.07  4970.8  597.94  4980.0  597.60  4980.3  597.10
  4984.0  597.60  5022.3  598.37  5135.5  597.93  5182.5  598.97  5205.0  601.37
  5210.1  600.53  5216.8  601.65  5237.1  602.48  5257.5  602.82  5263.3  602.23
  5268.4  603.35  5288.0  602.11  5308.3  605.52  5316.5  605.83  5321.6  604.55
  5338.8  604.89  5369.3  607.07  5374.8  608.28  5379.9  607.65  5426.1  611.10
#Mann=5,-1,0
  4475.0   0.045       0  4970.8    0.07       0  4980.0    0.05       0
  4984.0    0.07       0  5182.5   0.035       0
Bank Sta=4980,4984
Exp/Cntr=0.3,0.1

Type RM Length L Ch R = 1,1408,461,461,461
BEGIN DESCRIPTION:
YOUNGS TRIBUTARY 10 3.0
END DESCRIPTION:
XS GIS Cut Line= 4
      2252371.97     13766017.87      2252081.58     13766018.60
      2251967.46     13766092.99      2251431.96     13766198.94
#Sta/Elev= 30
  4435.6  600.31  4672.6  596.63  4692.6  594.74  4708.0  596.23  4721.8  597.14
  4823.9  596.72  4836.9  595.55  4842.8  596.46  4852.0  595.38  4858.0  596.49
  4860.7  595.51  4874.9  594.64  4915.7  595.15  4966.7  594.95  4994.8  594.22
  4995.0  593.72  4998.5  593.72  4998.8  594.22  5038.0  596.89  5104.4  599.88
  5109.6  599.60  5155.6  601.85  5160.7  601.47  5206.8  603.39  5211.9  603.07
  5309.3  606.91  5314.4  606.50  5360.6  608.10  5365.7  607.36  5408.1  608.18
#Mann=6,-1,0
  4435.6   0.035       0  4708.0    0.07       0  4823.9   0.035       0
  4994.8   0.035       0  4998.8   0.035       0  5109.6   0.045       0
Bank Sta=4994.8,4998.8
Exp/Cntr=0.3,0.1

Type RM Length L Ch R = 1,947,440,440,440
BEGIN DESCRIPTION:
YOUNGS TRIBUTARY 10 2.0
END DESCRIPTION:
XS GIS Cut Line= 3
      2252424.97     13765974.98      2252125.00     13765775.00
      2251824.95     13765724.99
#Sta/Elev= 30
  4639.2  601.07  4733.8  598.69  4739.8  598.99  4754.8  597.98  4775.9  597.81
  4790.9  597.10  4811.9  597.56  4833.0  597.11  4869.0  597.62  4878.0  596.98
  4891.5  594.46  4905.1  592.96  4920.1  592.30  4935.1  592.83  4956.1  591.62
  4971.2  591.78  4977.2  589.78  4984.2  589.60  4984.4  589.10  4987.9  589.10
  4988.2  589.60  4992.7  589.88  5002.3  589.76  5020.0  592.90  5060.5  593.34
  5080.8  594.41  5141.6  595.91  5270.9  600.32  5283.6  601.09  5303.9  601.39
#Mann=4,-1,0
  4639.2   0.035       0  4984.2   0.045       0  4988.2   0.035       0
  4992.7   0.045       0
Bank Sta=4984.2,4988.2
Exp/Cntr=0.3,0.1

Type RM Length L Ch R = 1,507,347,347,347
BEGIN DESCRIPTION:
YOUNGS TRIBUTARY 10 1.0
END DESCRIPTION:
XS GIS Cut Line= 3
      2252524.99     13765824.97      2252425.00     13765475.00
      2251724.98     13765575.00
#Sta/Elev= 30
  4631.1  599.71  4766.3  597.85  4787.1  597.94  4798.8  597.37  4833.4  598.21
  4849.5  598.03  4859.9  597.13  4871.6  594.59  4911.9  592.18  4936.7  591.44
  4984.7  589.31  5003.2  588.86  5003.4  588.36  5006.9  588.36  5007.2  588.86
  5009.0  588.86  5035.5  589.10  5075.9  590.45  5116.3  590.79  5156.7  590.38
  5267.8  590.80  5308.2  591.36  5378.9  592.82  5409.2  594.17  5429.4  595.55
  5469.8  596.93  5591.1  598.38  5611.3  599.19  5650.0  599.83  5702.2  601.27
#Mann=7,-1,0
  4631.1    0.07       0  4833.4   0.063       0  4936.7   0.035       0
  5003.2   0.035       0  5007.2   0.035       0  5009.0   0.045       0
  5650.0    0.07       0
Bank Sta=5003.2,5007.2
Exp/Cntr=0.3,0.1

Type RM Length L Ch R = 1,160,0,0,0
BEGIN DESCRIPTION:
J21836
END DESCRIPTION:
XS GIS Cut Line= 4
      2252915.87     13765589.14      2252506.15     13765123.86
      2252217.95     13765186.36      2251676.32     13765537.03
#Sta/Elev= 30
  4226.4  596.52  4385.9  592.86  4421.0  592.86  4457.0  592.00  4485.1  591.93
  4498.8  593.11  4527.3  593.20  4543.9  591.04  4681.7  590.55  4690.5  590.50
  4825.2  589.07  4825.6  589.06  4857.8  588.57  4929.4  589.11  4972.6  590.16
  4988.8  586.78  4989.0  586.28  4992.5  586.28  4992.8  586.78  5016.6  589.12
  5031.7  589.38  5156.7  589.64  5192.4  590.26  5372.9  590.28  5496.9  592.14
  5533.2  593.28  5554.3  595.39  5649.7  596.87  5705.3  598.01  5786.5  601.08
#Mann=9,-1,0
  4226.4   0.035       0  4543.9   0.063       0  4681.7    0.07       0
  4690.5   0.063       0  4825.2    0.07       0  4825.6   0.045       0
  4988.8   0.045       0  4992.8   0.045       0  5649.7    0.07       0
Bank Sta=4988.8,4992.8
Exp/Cntr=0.3,0.1

Chan Stop Cuts=-1