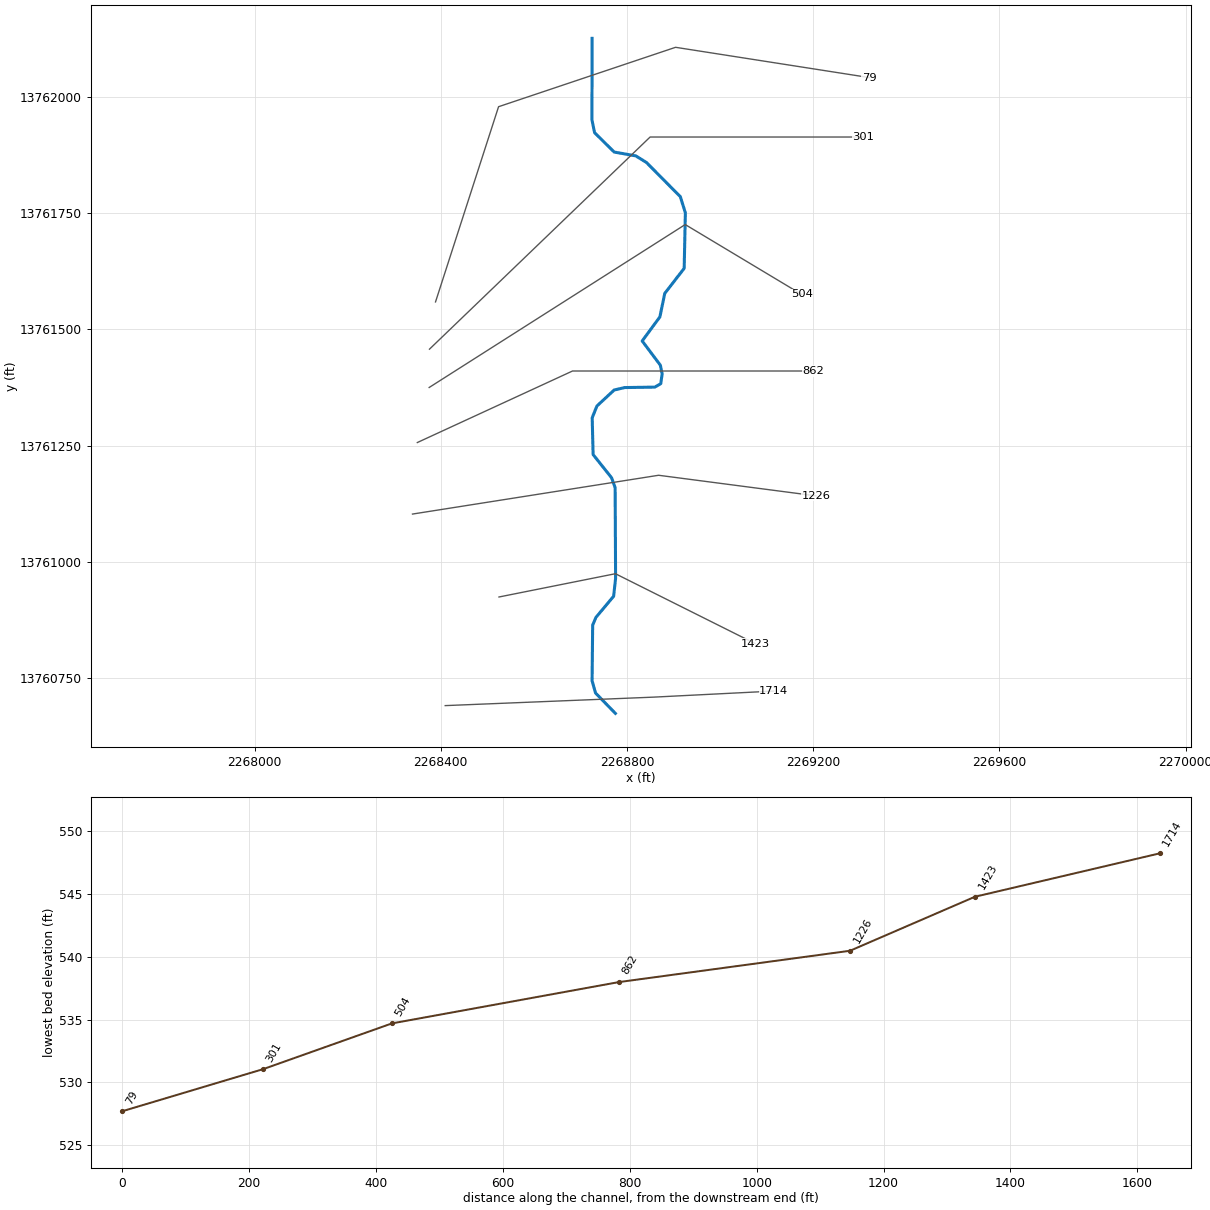
--- YOUNGS TRIBUTARY 1D.prj (project) ---

Proj Title=YOUNGS TRIBUTARY 1D Base Level Engineering
Current Plan=p01
Default Exp/Contr=0.3,0.1
English Units
Geom File=g01
Flow File=f01
Plan File=p01
BEGIN DESCRIPTION:
YOUNGS TRIBUTARY 1D
END DESCRIPTION:

--- YOUNGS TRIBUTARY 1D.p01 (plan) ---

Plan Title=Multiple Run
Short Identifier=Multiple
Geom File=g01
Flow File=f01
Subcritical Flow
K Sum by GR= 0
Std Step Tol= 0.01
Critical Tol= 0.01
Num of Std Step Trials= 20
Max Error Tol= 0.3
Flow Tol Ratio= 0.001
Split Flow NTrial= 30
Split Flow Tol= 0.02
Split Flow Ratio= 0.02
Log Output Level= 0
Friction Slope Method= 1
Unsteady Friction Slope Method= 2
Unsteady Bridges Friction Slope Method= 1
Parabolic Critical Depth
Global Vel Dist=  1 , 1 , 1
Global Log Level= 0
CheckData=True
Encroach Param= -1, 0, 0, 0
BEGIN DESCRIPTION:
Multiple Run
END DESCRIPTION:

--- YOUNGS TRIBUTARY 1D.f01 (steady flow) ---

Flow Title=Multiple
Number of Profiles=7
Profile Names=10-year,25-year,50-year,1pct_min,100-year,1pct_plu,500-year
River Rch & RM= YOUNGS TRIBUTARY,Reach-1,1714
     414     662     884     575    1146    2288    1903
Boundary for River Rch & Prof#=YOUNGS TRIBUTARY,Reach-1,1
Up Type=0
Dn Type=3
Dn Slope=0.005
Boundary for River Rch & Prof#=YOUNGS TRIBUTARY,Reach-1,2
Up Type=0
Dn Type=3
Dn Slope=0.005
Boundary for River Rch & Prof#=YOUNGS TRIBUTARY,Reach-1,3
Up Type=0
Dn Type=3
Dn Slope=0.005
Boundary for River Rch & Prof#=YOUNGS TRIBUTARY,Reach-1,4
Up Type=0
Dn Type=3
Dn Slope=0.005
Boundary for River Rch & Prof#=YOUNGS TRIBUTARY,Reach-1,5
Up Type=0
Dn Type=3
Dn Slope=0.005
Boundary for River Rch & Prof#=YOUNGS TRIBUTARY,Reach-1,6
Up Type=0
Dn Type=3
Dn Slope=0.005
Boundary for River Rch & Prof#=YOUNGS TRIBUTARY,Reach-1,7
Up Type=0
Dn Type=3
Dn Slope=0.005

--- YOUNGS TRIBUTARY 1D.g01 (geometry) ---

Geom Title=Existing Conditions

River Reach=YOUNGS TRIBUTARY,Reach-1
Reach XY= 30
      2268775.00     13760675.00      2268732.42     13760718.65
      2268724.96     13760745.00      2268726.20     13760864.49
      2268733.14     13760881.05      2268771.22     13760926.57
      2268775.45     13760964.81      2268774.48     13761159.78
      2268766.85     13761181.06      2268727.16     13761230.98
      2268725.19     13761309.92      2268735.29     13761335.16
      2268772.35     13761369.57      2268795.13     13761374.85
      2268859.66     13761375.81      2268872.46     13761383.17
      2268875.42     13761404.43      2268871.60     13761422.92
      2268832.58     13761474.97      2268870.58     13761526.64
      2268881.09     13761577.17      2268922.77     13761630.93
      2268925.32     13761750.12      2268914.54     13761784.82
      2268841.70     13761858.36      2268818.92     13761872.45
      2268772.43     13761880.74      2268730.35     13761922.30
      2268724.65     13761949.79      2268725.00     13762125.00

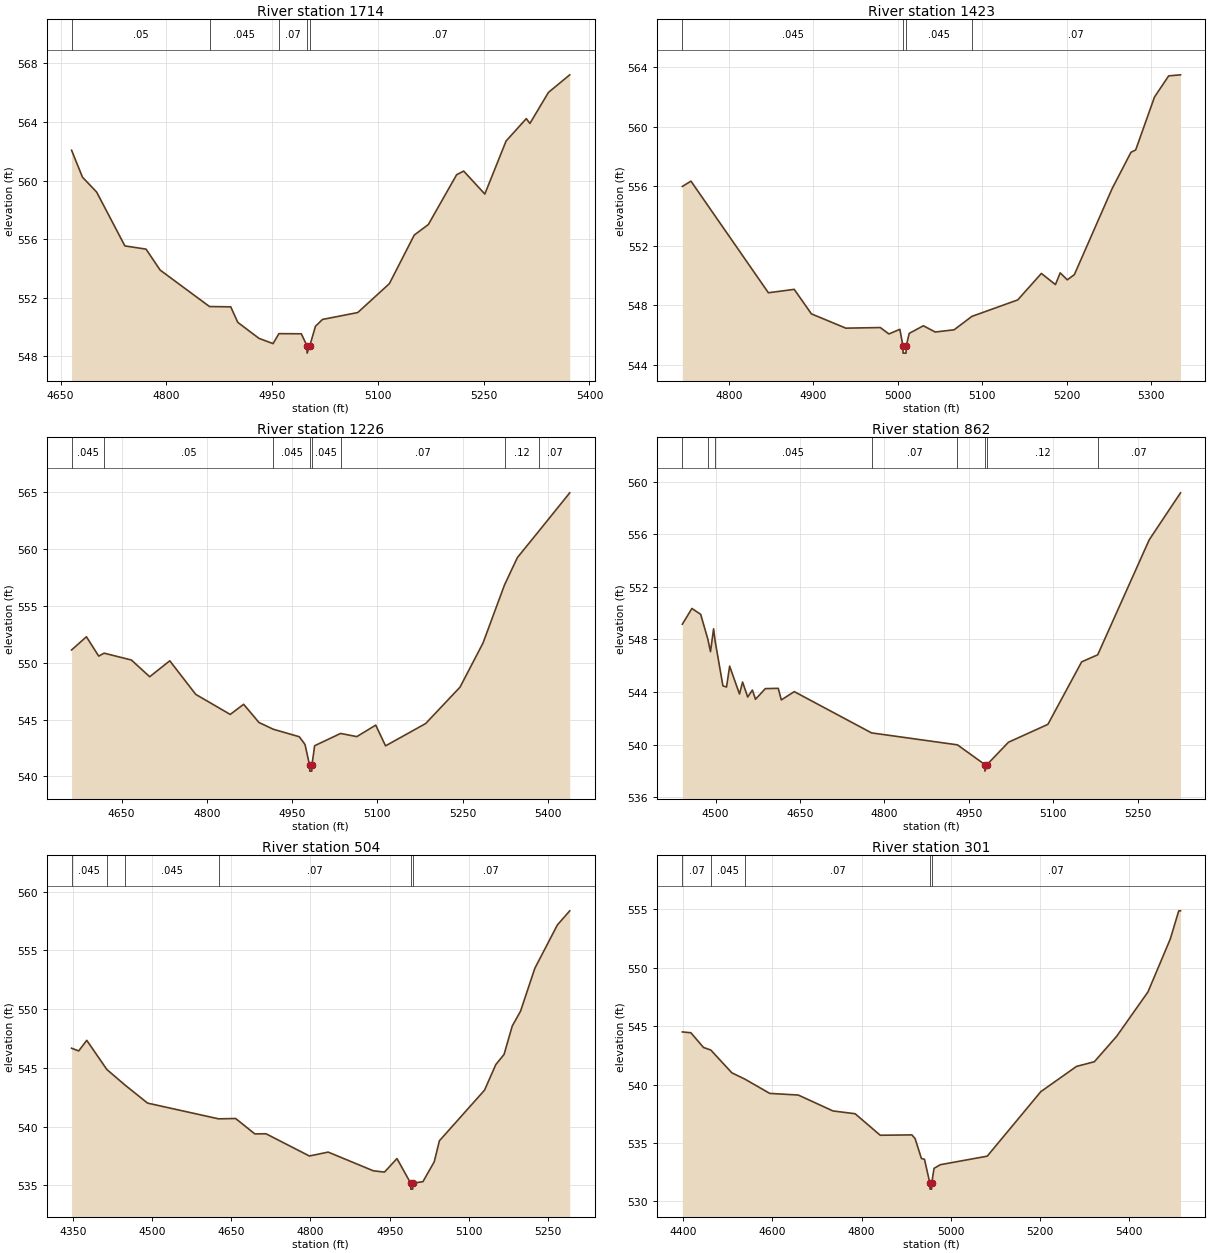
Type RM Length L Ch R = 1,1714,291,291,291
BEGIN DESCRIPTION:
J21841
END DESCRIPTION:
XS GIS Cut Line= 3
      2268409.51     13760691.67      2268857.41     13760709.90
      2269115.21     13760722.92
#Sta/Elev= 30
  4665.6  562.07  4681.1  560.23  4701.1  559.22  4741.2  555.54  4771.2  555.32
  4791.2  553.89  4861.2  551.40  4891.3  551.38  4901.3  550.32  4931.3  549.23
  4951.3  548.87  4959.6  549.55  4991.4  549.54  4999.4  548.72  4999.6  548.22
  5003.4  548.72  5011.4  550.05  5021.4  550.52  5071.4  550.99  5116.2  552.96
  5151.5  556.28  5171.5  557.00  5211.6  560.40  5221.6  560.65  5251.6  559.08
  5281.7  562.70  5310.4  564.23  5315.5  563.90  5341.8  566.02  5372.0  567.22
#Mann=5,-1,0
  4665.6    0.05       0  4861.2   0.045       0  4959.6    0.07       0
  4999.4    0.05       0  5003.4    0.07       0
Bank Sta=4999.4,5003.4
Exp/Cntr=0.3,0.1

Type RM Length L Ch R = 1,1423,197,197,197
BEGIN DESCRIPTION:
YOUNGS TRIBUTARY 1D 2.0
END DESCRIPTION:
XS GIS Cut Line= 3
      2268524.98     13760925.00      2268775.00     13760975.00
      2269075.02     13760824.99
#Sta/Elev= 30
  4744.6  555.98  4754.8  556.34  4846.6  548.83  4877.2  549.06  4897.6  547.41
  4938.4  546.45  4979.2  546.49  4989.4  546.06  5002.4  546.37  5006.0  545.27
  5006.2  544.77  5009.7  544.77  5010.0  545.27  5013.5  546.10  5030.3  546.61
  5044.3  546.19  5066.7  546.34  5087.7  547.24  5142.1  548.35  5170.1  550.13
  5186.8  549.38  5192.4  550.17  5200.8  549.70  5209.2  550.05  5253.9  555.83
  5276.3  558.28  5281.9  558.44  5304.2  562.00  5321.0  563.42  5335.0  563.49
#Mann=4,-1,0
  4744.6   0.045       0  5006.0   0.045       0  5010.0   0.045       0
  5087.7    0.07       0
Bank Sta=5006,5010
Exp/Cntr=0.3,0.1

Type RM Length L Ch R = 1,1226,364,364,364
BEGIN DESCRIPTION:
J21840
END DESCRIPTION:
XS GIS Cut Line= 3
      2268339.19     13761103.13      2268867.82     13761186.46
      2269206.38     13761142.19
#Sta/Elev= 30
  4561.9  551.11  4588.0  552.27  4609.7  550.57  4619.1  550.83  4667.1  550.23
  4699.4  548.76  4734.7  550.16  4780.4  547.21  4841.1  545.45  4864.7  546.34
  4891.7  544.74  4916.8  544.15  4962.6  543.49  4972.7  542.81  4980.8  540.97
  4981.1  540.47  4984.6  540.47  4984.8  540.97  4989.6  542.70  5035.3  543.78
  5063.8  543.50  5097.1  544.51  5114.4  542.69  5185.0  544.65  5245.5  547.85
  5285.8  551.71  5323.7  556.82  5346.3  559.22  5384.2  561.55  5438.5  564.91
#Mann=8,-1,0
  4561.9   0.045       0  4619.1    0.05       0  4916.8   0.045       0
  4980.8   0.045       0  4984.8   0.045       0  5035.3    0.07       0
  5323.7    0.12       0  5384.2    0.07       0
Bank Sta=4980.8,4984.8
Exp/Cntr=0.3,0.1

Type RM Length L Ch R = 1,862,358,358,358
BEGIN DESCRIPTION:
J21839
END DESCRIPTION:
XS GIS Cut Line= 3
      2268349.55     13761256.75      2268682.93     13761410.42
      2269200.54     13761410.42
#Sta/Elev= 30
  4441.0  549.16  4458.0  550.36  4473.6  549.91  4486.5  547.99  4491.0  547.07
  4496.5  548.81  4499.2  547.89  4513.1  544.47  4519.5  544.38  4525.0  545.97
  4542.5  543.85  4548.0  544.76  4557.1  543.62  4565.4  544.15  4570.9  543.45
  4588.4  544.26  4611.3  544.28  4616.8  543.40  4639.8  544.03  4777.0  540.89
  4929.6  539.98  4978.2  538.48  4978.4  537.98  4982.2  538.48  5020.2  540.18
  5090.2  541.54  5150.2  546.30  5178.6  546.83  5270.2  555.59  5325.7  559.16
#Mann=8,-1,0
  4441.0   0.045       0  4486.5    0.05       0  4499.2   0.045       0
  4777.0    0.07       0  4929.6    0.12       0  4978.2    0.05       0
  4982.2    0.12       0  5178.6    0.07       0
Bank Sta=4978.2,4982.2
Exp/Cntr=0.3,0.1

Type RM Length L Ch R = 1,504,203,203,203
BEGIN DESCRIPTION:
YOUNGS TRIBUTARY 1D 1.0
END DESCRIPTION:
XS GIS Cut Line= 3
      2268375.01     13761375.01      2268925.00     13761725.00
      2269175.04     13761574.98
#Sta/Elev= 30
  4347.5  546.68  4361.0  546.45  4376.3  547.35  4414.3  544.87  4448.6  543.55
  4491.4  542.01  4626.0  540.67  4658.2  540.70  4694.6  539.39  4715.8  539.40
  4797.9  537.51  4833.5  537.84  4919.0  536.25  4940.1  536.14  4963.8  537.29
  4989.8  535.19  4990.0  534.69  4993.5  534.69  4993.8  535.19  5013.0  535.33
  5034.4  537.02  5044.1  538.80  5129.6  543.11  5151.0  545.29  5166.6  546.15
  5182.1  548.57  5197.7  549.82  5224.9  553.48  5267.6  557.17  5291.0  558.37
#Mann=6,-1,0
  4347.5   0.045       0  4414.3    0.07       0  4448.6   0.045       0
  4626.0    0.07       0  4989.8    0.05       0  4993.8    0.07       0
Bank Sta=4989.8,4993.8
Exp/Cntr=0.3,0.1

Type RM Length L Ch R = 1,301,222,222,222
BEGIN DESCRIPTION:
J21838
END DESCRIPTION:
XS GIS Cut Line= 3
      2268375.65     13761457.31      2268849.59     13761913.02
      2269307.91     13761913.02
#Sta/Elev= 30
  4398.6  544.50  4417.7  544.43  4446.0  543.17  4462.4  542.95  4509.5  541.00
  4538.8  540.46  4594.4  539.24  4658.3  539.10  4735.9  537.74  4785.6  537.50
  4841.9  535.66  4912.7  535.69  4919.9  535.38  4934.1  533.67  4941.0  533.60
  4953.1  531.55  4953.4  531.05  4956.9  531.05  4957.1  531.55  4962.4  532.83
  4976.5  533.14  5081.5  533.87  5201.5  539.39  5281.5  541.55  5321.5  541.95
  5371.5  544.13  5441.5  547.92  5491.5  552.45  5510.5  554.86  5514.4  554.86
#Mann=5,-1,0
  4398.6    0.07       0  4462.4   0.045       0  4538.8    0.07       0
  4953.1    0.05       0  4957.1    0.07       0
Bank Sta=4953.1,4957.1
Exp/Cntr=0.3,0.1

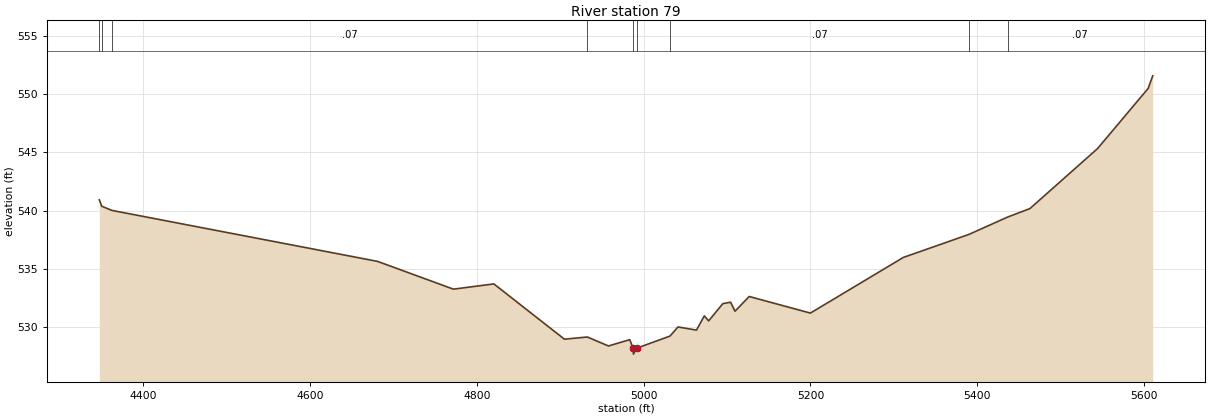
Type RM Length L Ch R = 1,79,0,0,0
BEGIN DESCRIPTION:
J21837
END DESCRIPTION:
XS GIS Cut Line= 4
      2268388.65     13761558.83      2268524.07     13761978.13
      2268904.28     13762105.73      2269320.46     13762040.70
#Sta/Elev= 30
  4347.5  540.93  4350.4  540.38  4362.7  540.02  4681.1  535.65  4772.0  533.27
  4820.5  533.72  4905.1  528.98  4932.5  529.17  4957.9  528.40  4983.4  528.94
  4987.5  528.20  4987.8  527.70  4991.5  528.20  5031.7  529.25  5041.2  530.03
  5063.4  529.76  5072.8  530.98  5078.0  530.55  5095.0  532.03  5104.3  532.15
  5109.6  531.38  5126.6  532.64  5200.0  531.22  5311.4  535.99  5389.9  537.96
  5436.4  539.45  5463.2  540.18  5544.2  545.32  5604.9  550.48  5610.4  551.56
#Mann=9,-1,0
  4347.5    0.07       0  4350.4   0.045       0  4362.7    0.07       0
  4932.5    0.12       0  4987.5    0.05       0  4991.5    0.12       0
  5031.7    0.07       0  5389.9    0.12       0  5436.4    0.07       0
Bank Sta=4987.5,4991.5
Exp/Cntr=0.3,0.1

Chan Stop Cuts=-1