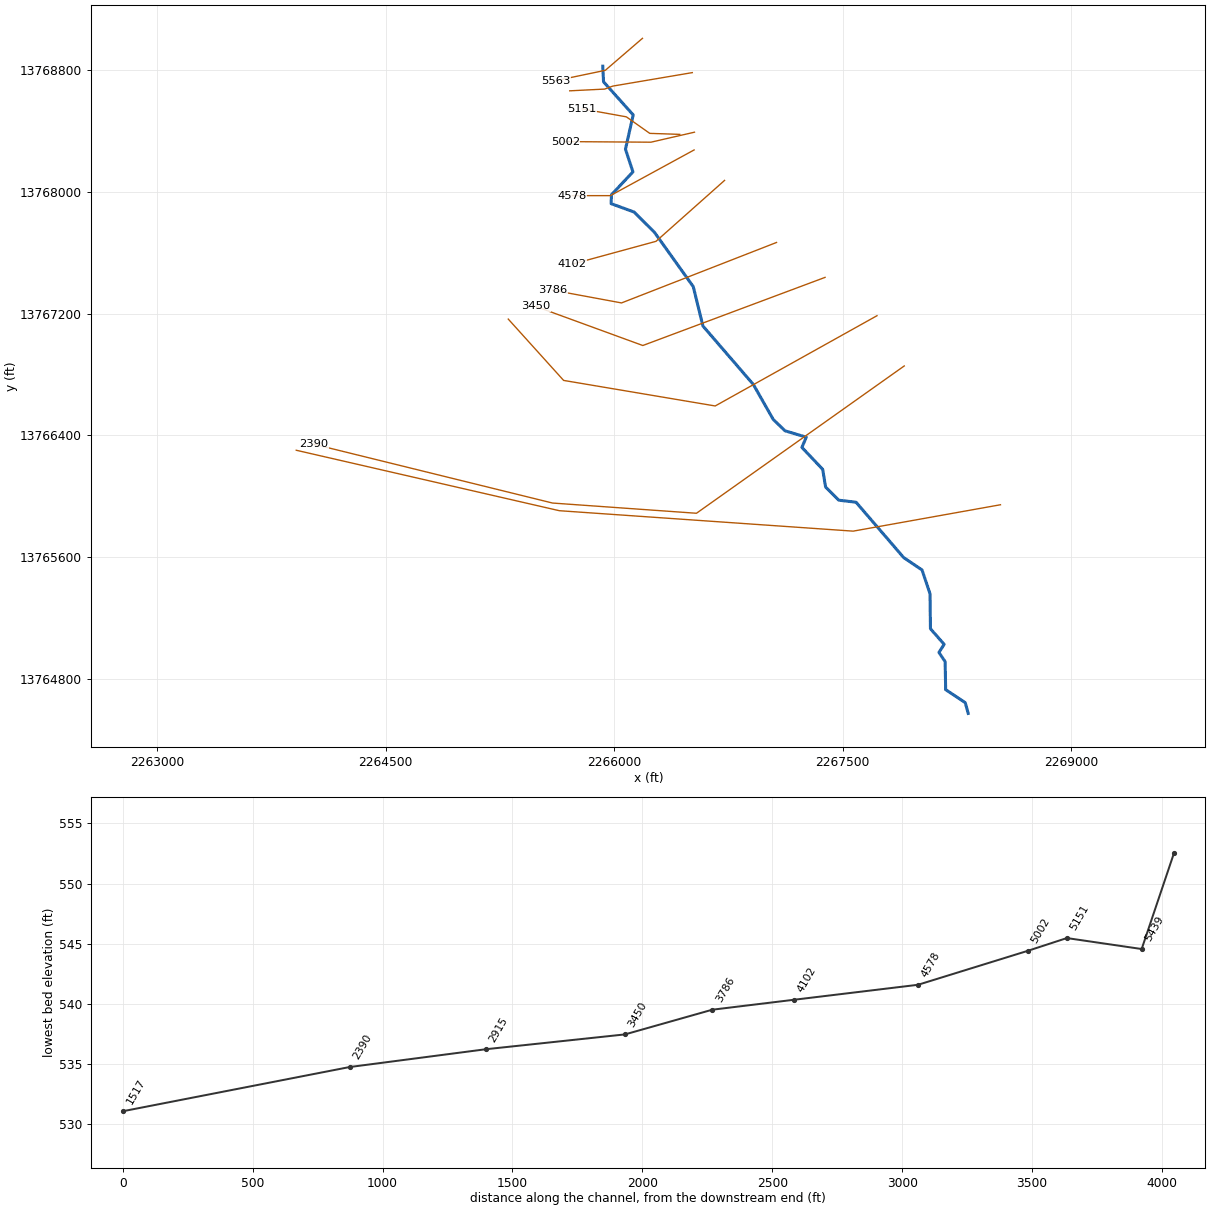
--- YOUNGS TRIBUTARY 2.prj (project) ---

Proj Title=YOUNGS TRIBUTARY 2 Base Level Engineering
Current Plan=p01
Default Exp/Contr=0.3,0.1
English Units
Geom File=g01
Flow File=f01
Plan File=p01
BEGIN DESCRIPTION:
YOUNGS TRIBUTARY 2
END DESCRIPTION:

--- YOUNGS TRIBUTARY 2.p01 (plan) ---

Plan Title=Multiple Run
Short Identifier=Multiple
Geom File=g01
Flow File=f01
Subcritical Flow
K Sum by GR= 0
Std Step Tol= 0.01
Critical Tol= 0.01
Num of Std Step Trials= 20
Max Error Tol= 0.3
Flow Tol Ratio= 0.001
Split Flow NTrial= 30
Split Flow Tol= 0.02
Split Flow Ratio= 0.02
Log Output Level= 0
Friction Slope Method= 1
Unsteady Friction Slope Method= 2
Unsteady Bridges Friction Slope Method= 1
Parabolic Critical Depth
Global Vel Dist=  1 , 1 , 1
Global Log Level= 0
CheckData=True
Encroach Param= -1, 0, 0, 0
BEGIN DESCRIPTION:
Multiple Run
END DESCRIPTION:

--- YOUNGS TRIBUTARY 2.f01 (steady flow) ---

Flow Title=Multiple
Number of Profiles=7
Profile Names=10-year,25-year,50-year,1pct_min,100-year,1pct_plu,500-year
River Rch & RM= YOUNGS TRIBUTARY,Reach-1,5563
     395     617     811     517    1032    2059    1651
River Rch & RM= YOUNGS TRIBUTARY,Reach-1,3450
     652    1048    1403     909    1814    3619    2998
River Rch & RM= YOUNGS TRIBUTARY,Reach-1,1517
    1262    2122    2929    1953    3897    7776    6837
Boundary for River Rch & Prof#=YOUNGS TRIBUTARY,Reach-1,1
Up Type=0
Dn Type=3
Dn Slope=0.005
Boundary for River Rch & Prof#=YOUNGS TRIBUTARY,Reach-1,2
Up Type=0
Dn Type=3
Dn Slope=0.005
Boundary for River Rch & Prof#=YOUNGS TRIBUTARY,Reach-1,3
Up Type=0
Dn Type=3
Dn Slope=0.005
Boundary for River Rch & Prof#=YOUNGS TRIBUTARY,Reach-1,4
Up Type=0
Dn Type=3
Dn Slope=0.005
Boundary for River Rch & Prof#=YOUNGS TRIBUTARY,Reach-1,5
Up Type=0
Dn Type=3
Dn Slope=0.005
Boundary for River Rch & Prof#=YOUNGS TRIBUTARY,Reach-1,6
Up Type=0
Dn Type=3
Dn Slope=0.005
Boundary for River Rch & Prof#=YOUNGS TRIBUTARY,Reach-1,7
Up Type=0
Dn Type=3
Dn Slope=0.005

--- YOUNGS TRIBUTARY 2.g01 (geometry) ---

Geom Title=Existing Conditions

River Reach=YOUNGS TRIBUTARY,Reach-1
Reach XY= 30
      2265925.00     13768825.00      2265930.35     13768722.50
      2266125.06     13768505.01      2266074.20     13768280.03
      2266123.38     13768131.03      2265982.45     13767981.03
      2265979.95     13767922.43      2266131.17     13767867.14
      2266264.22     13767734.68      2266519.48     13767377.43
      2266582.86     13767118.83      2266914.22     13766734.68
      2267044.77     13766504.87      2267122.56     13766430.52
      2267261.52     13766388.75      2267233.01     13766321.68
      2267369.48     13766177.43      2267388.31     13766061.66
      2267475.00     13765975.00      2267588.33     13765961.65
      2267901.28     13765598.12      2268021.84     13765516.66
      2268074.48     13765359.79      2268077.07     13765130.85
      2268166.99     13765028.33      2268132.81     13764975.10
      2268173.62     13764914.57      2268176.98     13764730.67
      2268305.44     13764645.63      2268325.00     13764575.00

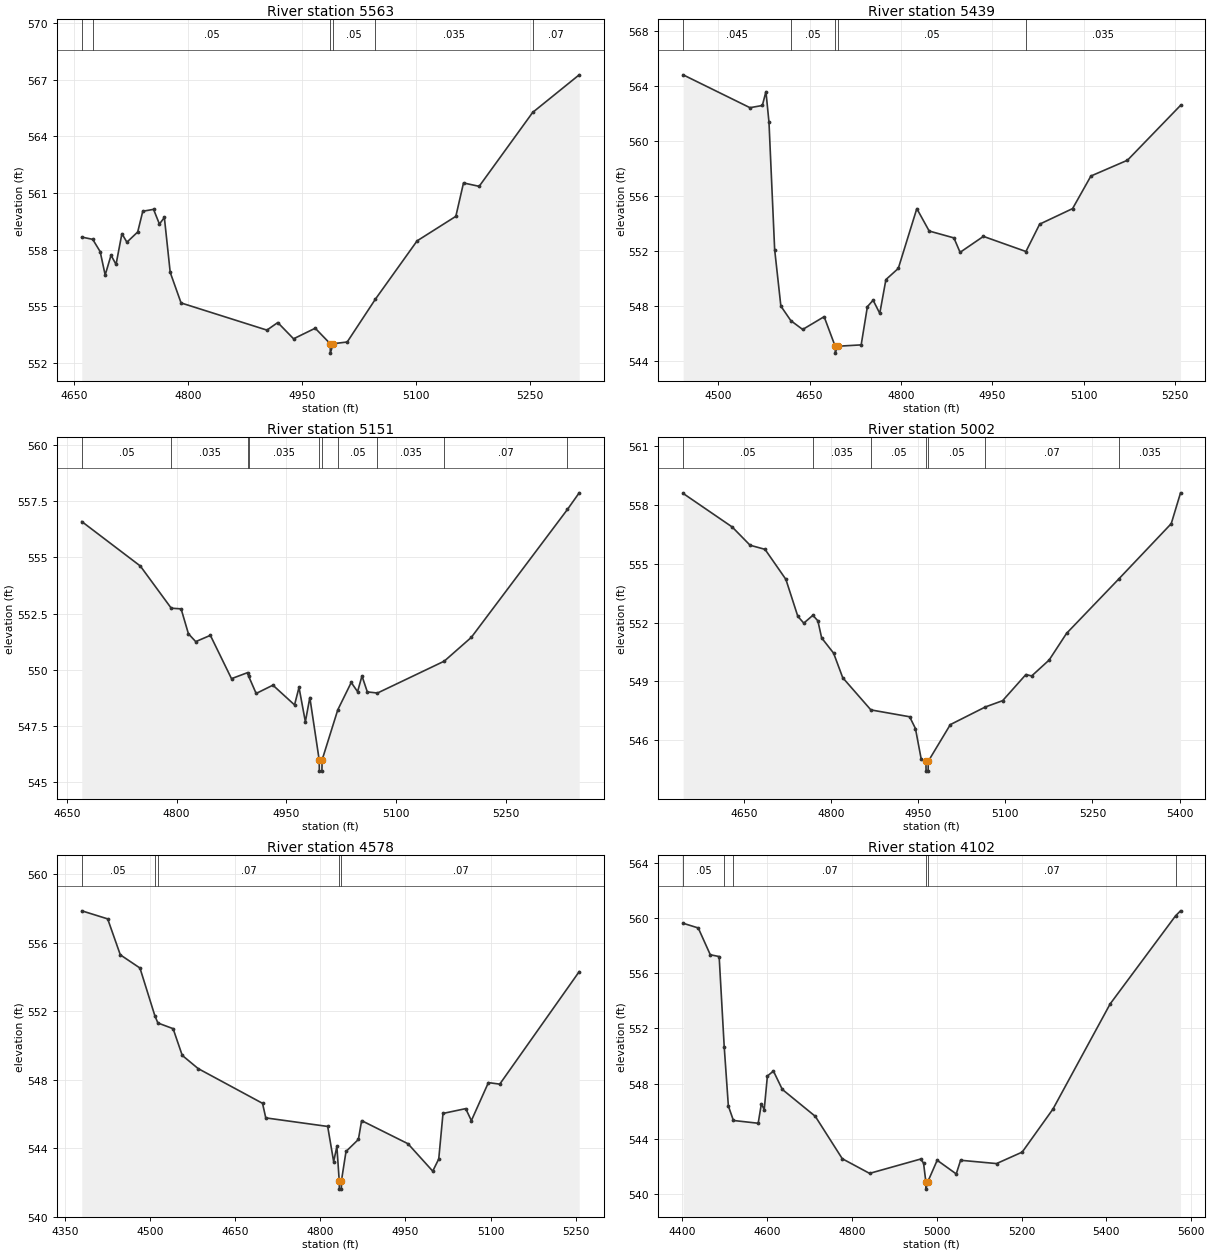
Type RM Length L Ch R = 1,5563,124,124,124
BEGIN DESCRIPTION:
YOUNGS TRIBUTARY 2 5.0
END DESCRIPTION:
XS GIS Cut Line= 3
      2266185.86     13769007.98      2265941.73     13768797.85
      2265616.05     13768729.93
#Sta/Elev= 30
  4660.4  558.66  4674.8  558.54  4684.6  557.89  4691.2  556.65  4698.9  557.70
  4705.5  557.21  4713.2  558.84  4719.8  558.39  4734.0  558.93  4740.7  560.03
  4754.9  560.13  4762.6  559.35  4769.1  559.70  4776.8  556.79  4791.1  555.17
  4904.1  553.73  4918.4  554.13  4939.2  553.27  4967.7  553.83  4987.4  553.01
  4987.6  552.51  4991.4  553.01  5009.8  553.10  5046.9  555.37  5101.8  558.46
  5152.8  559.76  5162.9  561.53  5183.5  561.35  5254.0  565.27  5315.2  567.26
#Mann=6,-1,0
  4660.4   0.045       0  4674.8    0.05       0  4987.4    0.05       0
  4991.4    0.05       0  5046.9   0.035       0  5254.0    0.07       0
Bank Sta=4987.4,4991.4
Exp/Cntr=0.3,0.1

Type RM Length L Ch R = 1,5439,288,288,288
BEGIN DESCRIPTION:
J21847
END DESCRIPTION:
XS GIS Cut Line= 4
      2266513.12     13768782.85      2265990.95     13768694.32
      2265937.81     13768674.74      2265708.06     13768663.25
#Sta/Elev= 30
  4442.5  564.81  4552.2  562.42  4572.5  562.58  4578.4  563.59  4583.4  561.36
  4592.7  552.10  4602.9  547.99  4619.3  546.93  4638.7  546.29  4673.9  547.22
  4692.0  545.07  4692.2  544.57  4696.0  545.07  4734.7  545.17  4744.9  547.95
  4754.3  548.42  4765.2  547.46  4775.3  549.92  4795.6  550.73  4826.0  555.08
  4846.3  553.45  4886.9  552.95  4897.0  551.90  4935.3  553.06  5005.1  551.96
  5027.6  553.95  5081.6  555.08  5111.7  557.45  5171.7  558.60  5258.8  562.59
#Mann=5,-1,0
  4442.5   0.045       0  4619.3    0.05       0  4692.0    0.05       0
  4696.0    0.05       0  5005.1   0.035       0
Bank Sta=4692,4696
Exp/Cntr=0.3,0.1

Type RM Length L Ch R = 1,5151,149,149,149
BEGIN DESCRIPTION:
J21846
END DESCRIPTION:
XS GIS Cut Line= 4
      2266430.74     13768377.41      2266233.85     13768383.85
      2266080.09     13768492.42      2265789.89     13768544.72
#Sta/Elev= 30
  4670.3  556.60  4750.3  554.62  4792.6  552.74  4806.1  552.71  4816.1  551.60
  4826.1  551.25  4846.1  551.53  4875.0  549.60  4897.1  549.87  4898.3  549.72
  4908.7  548.94  4931.6  549.31  4961.2  548.43  4967.3  549.21  4976.0  547.68
  4982.1  548.76  4994.9  545.98  4995.1  545.48  4998.6  545.48  4998.9  545.98
  5020.3  548.21  5038.7  549.43  5047.4  549.02  5053.4  549.72  5060.7  549.01
  5074.6  548.96  5165.9  550.38  5202.9  551.44  5334.3  557.14  5350.4  557.88
#Mann=10,-1,0
  4670.3    0.05       0  4792.6   0.035       0  4897.1    0.05       0
  4898.3   0.035       0  4994.9   0.035       0  4998.9   0.035       0
  5020.3    0.05       0  5074.6   0.035       0  5165.9    0.07       0
  5334.3   0.035       0
Bank Sta=4994.9,4998.9
Exp/Cntr=0.3,0.1

Type RM Length L Ch R = 1,5002,424,424,424
BEGIN DESCRIPTION:
YOUNGS TRIBUTARY 2 4.0
END DESCRIPTION:
XS GIS Cut Line= 3
      2266527.30     13768391.57      2266241.57     13768325.93
      2265678.95     13768329.78
#Sta/Elev= 30
  4545.8  558.58  4630.2  556.87  4661.0  555.94  4686.7  555.73  4722.6  554.20
  4743.1  552.32  4753.4  551.97  4769.0  552.37  4777.6  552.09  4784.1  551.22
  4804.7  550.44  4820.4  549.19  4868.8  547.55  4935.5  547.20  4945.5  546.60
  4955.5  545.03  4963.5  544.93  4963.8  544.43  4967.3  544.43  4967.5  544.93
  5005.5  546.80  5065.8  547.70  5095.5  548.02  5135.5  549.35  5145.5  549.28
  5175.5  550.09  5205.5  551.45  5295.3  554.22  5385.6  557.04  5401.6  558.61
#Mann=7,-1,0
  4545.8    0.05       0  4769.0   0.035       0  4868.8    0.05       0
  4963.5    0.05       0  4967.5    0.05       0  5065.8    0.07       0
  5295.3   0.035       0
Bank Sta=4963.5,4967.5
Exp/Cntr=0.3,0.1

Type RM Length L Ch R = 1,4578,476,476,476
BEGIN DESCRIPTION:
YOUNGS TRIBUTARY 2 3.0
END DESCRIPTION:
XS GIS Cut Line= 3
      2266525.01     13768275.00      2265975.00     13767975.00
      2265725.01     13767975.00
#Sta/Elev= 30
  4379.8  557.85  4425.4  557.38  4447.7  555.28  4482.3  554.51  4508.5  551.73
  4513.9  551.30  4540.7  550.97  4556.8  549.41  4584.8  548.64  4698.3  546.61
  4704.0  545.76  4813.1  545.26  4823.6  543.21  4829.3  544.09  4833.4  542.10
  4833.7  541.60  4837.2  541.60  4837.4  542.10  4845.4  543.80  4867.2  544.50
  4872.9  545.60  4954.6  544.25  4998.2  542.65  5008.8  543.36  5016.3  546.02
  5056.3  546.30  5066.3  545.60  5096.3  547.82  5116.3  547.73  5256.3  554.30
#Mann=5,-1,0
  4379.8    0.05       0  4508.5   0.035       0  4513.9    0.07       0
  4833.4    0.05       0  4837.4    0.07       0
Bank Sta=4833.4,4837.4
Exp/Cntr=0.3,0.1

Type RM Length L Ch R = 1,4102,316,316,316
BEGIN DESCRIPTION:
YOUNGS TRIBUTARY 2 2.0
END DESCRIPTION:
XS GIS Cut Line= 3
      2266725.01     13768075.01      2266275.00     13767675.00
      2265724.98     13767524.99
#Sta/Elev= 30
  4402.6  559.61  4438.2  559.27  4466.6  557.33  4487.5  557.20  4499.4  550.68
  4509.2  546.38  4521.1  545.33  4579.5  545.13  4587.0  546.54  4593.7  546.12
  4601.2  548.55  4615.4  548.91  4636.3  547.58  4714.1  545.63  4777.7  542.56
  4842.0  541.50  4962.5  542.54  4969.2  542.24  4974.7  540.86  4974.9  540.36
  4978.7  540.86  5001.3  542.45  5046.2  541.46  5056.5  542.45  5141.2  542.21
  5201.6  543.04  5274.2  546.16  5408.9  553.77  5563.1  560.15  5574.8  560.51
#Mann=6,-1,0
  4402.6    0.05       0  4499.4   0.035       0  4521.1    0.07       0
  4974.7    0.05       0  4978.7    0.07       0  5563.1   0.035       0
Bank Sta=4974.7,4978.7
Exp/Cntr=0.3,0.1

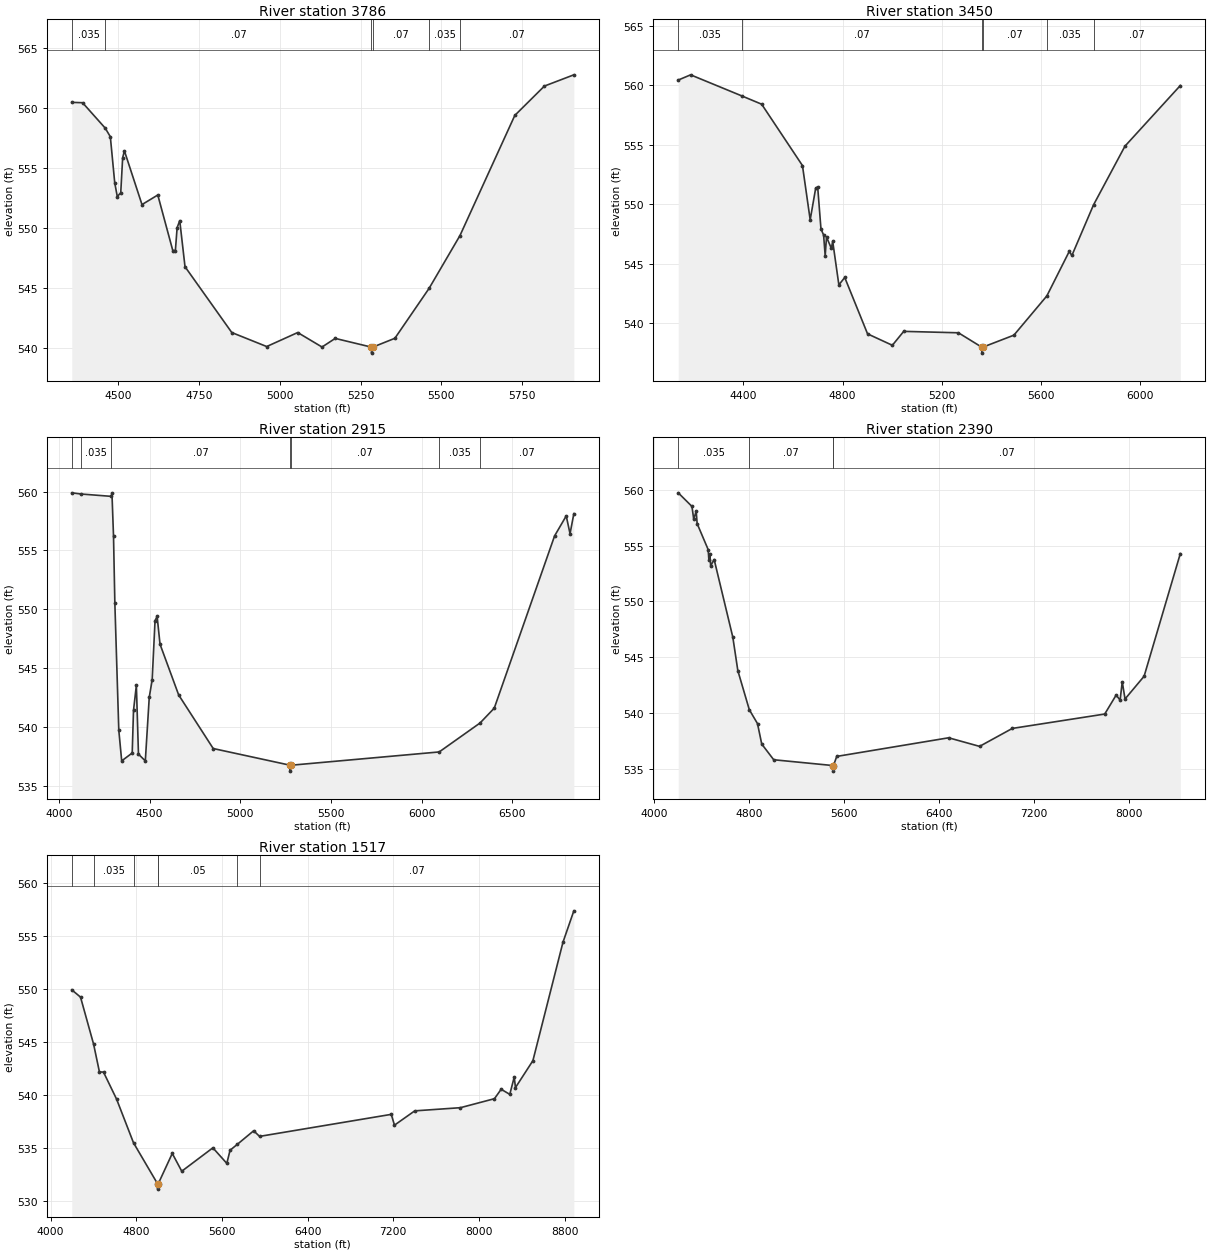
Type RM Length L Ch R = 1,3786,336,336,336
BEGIN DESCRIPTION:
J21845
END DESCRIPTION:
XS GIS Cut Line= 3
      2267066.14     13767667.43      2266048.39     13767270.39
      2265595.44     13767354.27
#Sta/Elev= 30
  4356.5  560.48  4389.9  560.45  4459.9  558.33  4475.8  557.61  4489.4  553.76
  4497.3  552.61  4508.0  552.93  4513.9  555.85  4519.3  556.43  4573.7  551.94
  4622.6  552.74  4669.0  548.10  4677.0  548.10  4682.4  550.01  4690.5  550.60
  4706.8  546.75  4851.5  541.25  4959.5  540.08  5055.4  541.25  5130.6  540.04
  5171.5  540.76  5283.6  540.03  5283.8  539.53  5287.6  540.03  5356.0  540.77
  5461.8  544.94  5557.3  549.35  5727.0  559.39  5818.5  561.84  5909.6  562.78
#Mann=6,-1,0
  4356.5   0.035       0  4459.9    0.07       0  5283.6    0.05       0
  5287.6    0.07       0  5461.8   0.035       0  5557.3    0.07       0
Bank Sta=5283.6,5287.6
Exp/Cntr=0.3,0.1

Type RM Length L Ch R = 1,3450,535,535,535
BEGIN DESCRIPTION:
J21844
END DESCRIPTION:
XS GIS Cut Line= 3
      2267384.95     13767438.18      2266188.19     13766990.79
      2265483.62     13767248.01
#Sta/Elev= 30
  4136.5  560.44  4186.4  560.88  4392.9  559.11  4473.4  558.41  4638.2  553.25
  4669.4  548.69  4691.6  551.35  4699.7  551.44  4712.9  547.93  4723.6  547.41
  4730.0  545.66  4735.3  547.24  4754.9  546.29  4760.3  546.88  4785.2  543.22
  4809.0  543.84  4901.1  539.10  5001.2  538.14  5047.2  539.31  5268.1  539.19
  5362.4  537.98  5362.6  537.48  5366.4  537.98  5492.1  538.99  5625.2  542.29
  5715.6  546.03  5726.3  545.69  5813.6  549.94  5940.6  554.88  6164.2  559.98
#Mann=6,-1,0
  4136.5   0.035       0  4392.9    0.07       0  5362.4    0.05       0
  5366.4    0.07       0  5625.2   0.035       0  5813.6    0.07       0
Bank Sta=5362.4,5366.4
Exp/Cntr=0.3,0.1

Type RM Length L Ch R = 1,2915,525,525,525
BEGIN DESCRIPTION:
J21843
END DESCRIPTION:
XS GIS Cut Line= 4
      2267726.05     13767186.53      2266663.52     13766593.75
      2265668.13     13766761.51      2265304.62     13767164.17
#Sta/Elev= 30
  4071.0  559.89  4121.8  559.79  4288.9  559.59  4292.6  559.86  4301.2  556.21
  4308.6  550.50  4330.3  539.73  4346.3  537.12  4404.3  537.79  4411.4  541.40
  4427.2  543.54  4438.8  537.69  4476.6  537.12  4498.3  542.53  4514.3  543.99
  4530.2  549.03  4541.7  549.39  4557.7  547.03  4660.5  542.72  4850.9  538.17
  5275.6  536.75  5275.8  536.25  5279.6  536.75  6097.2  537.88  6322.5  540.34
  6400.8  541.60  6733.4  556.23  6797.6  557.93  6818.6  556.42  6839.6  558.12
#Mann=7,-1,0
  4071.0    0.07       0  4121.8   0.035       0  4288.9    0.07       0
  5275.6    0.05       0  5279.6    0.07       0  6097.2   0.035       0
  6322.5    0.07       0
Bank Sta=5275.6,5279.6
Exp/Cntr=0.3,0.1

Type RM Length L Ch R = 1,2390,873,873,873
BEGIN DESCRIPTION:
YOUNGS TRIBUTARY 2 1.0
END DESCRIPTION:
XS GIS Cut Line= 4
      2267904.94     13766856.56      2266540.49     13765889.14
      2265595.43     13765956.25      2264029.81     13766342.06
#Sta/Elev= 30
  4203.7  559.73  4319.4  558.51  4334.2  557.37  4355.1  558.09  4363.0  556.97
  4456.0  554.64  4462.1  553.70  4470.8  554.21  4476.9  553.18  4506.5  553.75
  4663.9  546.78  4706.2  543.78  4802.8  540.28  4871.9  539.03  4907.6  537.20
  5008.5  535.79  5508.4  535.27  5508.7  534.77  5512.5  535.27  5539.8  536.09
  6483.3  537.76  6744.0  536.99  7019.9  538.60  7799.1  539.89  7895.3  541.59
  7928.7  541.14  7946.8  542.78  7970.2  541.24  8131.0  543.28  8436.2  554.28
#Mann=4,-1,0
  4203.7   0.035       0  4802.8    0.07       0  5508.4    0.05       0
  5512.5    0.07       0
Bank Sta=5508.4,5512.5
Exp/Cntr=0.3,0.1

Type RM Length L Ch R = 1,1517,0,0,0
BEGIN DESCRIPTION:
J21842
END DESCRIPTION:
XS GIS Cut Line= 4
      2268536.90     13765945.07      2267569.44     13765771.71
      2265640.17     13765905.92      2263912.20     13766302.96
#Sta/Elev= 30
  4197.1  549.92  4278.9  549.23  4401.2  544.78  4455.4  542.17  4493.6  542.15
  4615.6  539.60  4773.9  535.47  4998.7  531.60  4999.2  531.10  5004.6  531.60
  5135.9  534.47  5224.5  532.79  5515.2  535.00  5645.5  533.53  5675.6  534.77
  5742.3  535.32  5896.1  536.61  5951.3  536.08  7181.3  538.16  7211.5  537.14
  7400.7  538.49  7827.2  538.79  8145.3  539.64  8207.9  540.53  8288.5  540.05
  8330.0  541.68  8341.6  540.69  8504.4  543.23  8785.5  554.42  8886.9  557.38
#Mann=7,-1,0
  4197.1    0.05       0  4401.2   0.035       0  4773.9    0.05       0
  4998.7    0.05       0  5004.6    0.05       0  5742.3   0.035       0
  5951.3    0.07       0
Bank Sta=4998.7,5004.6
Exp/Cntr=0.3,0.1

Chan Stop Cuts=-1