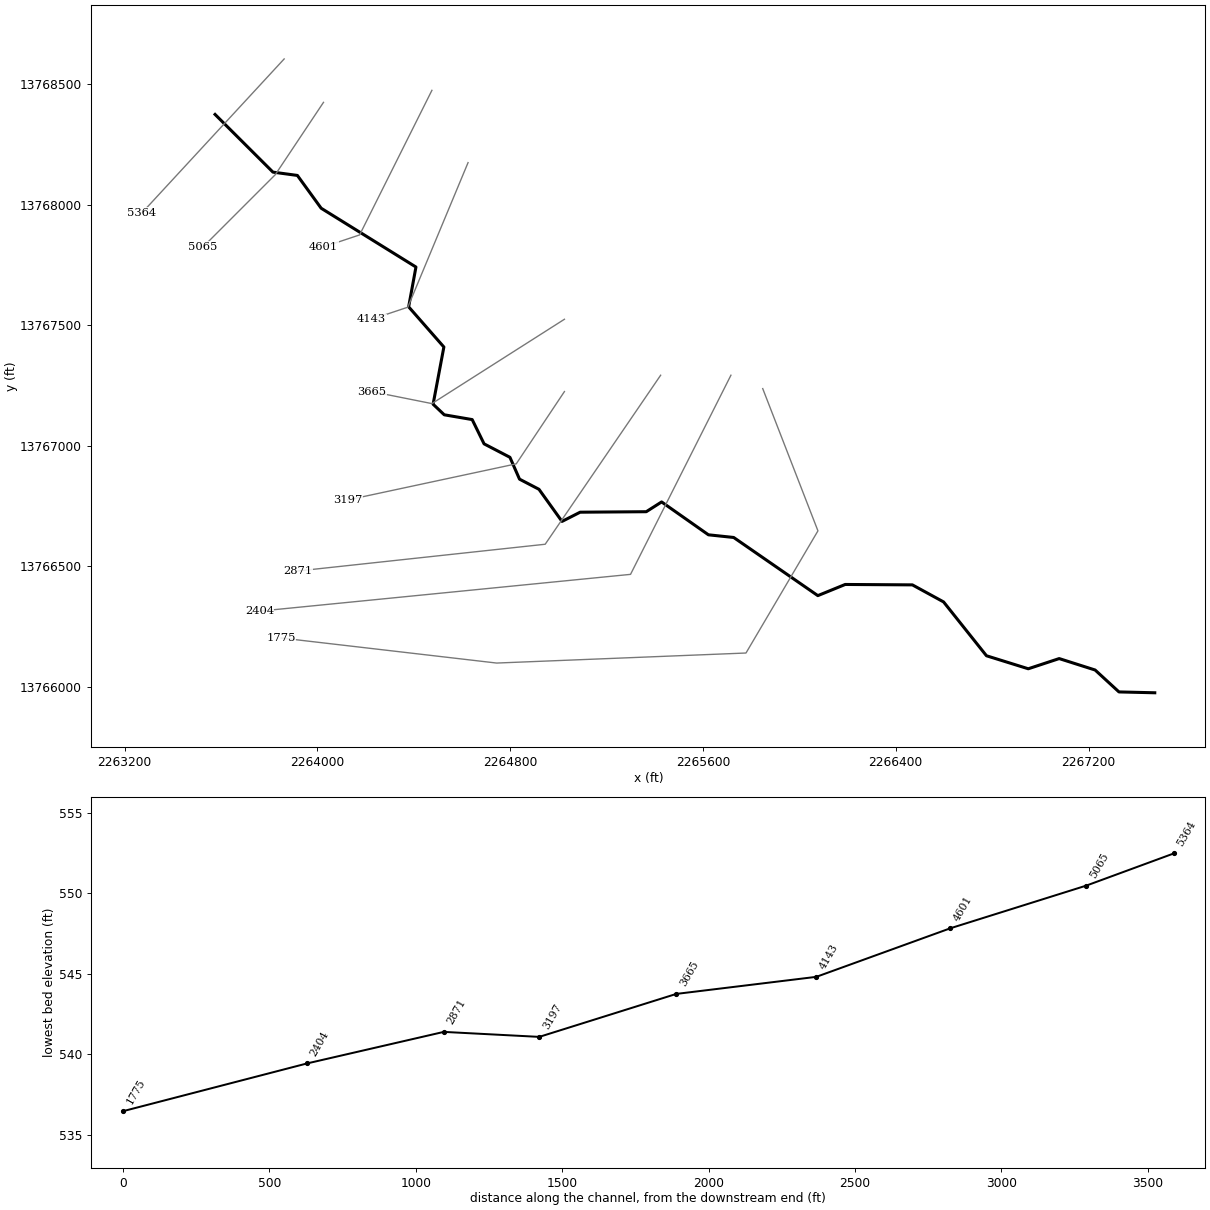
--- YOUNGS TRIBUTARY 3.prj (project) ---

Proj Title=YOUNGS TRIBUTARY 3 Base Level Engineering
Current Plan=p01
Default Exp/Contr=0.3,0.1
English Units
Geom File=g01
Flow File=f01
Plan File=p01
BEGIN DESCRIPTION:
YOUNGS TRIBUTARY 3
END DESCRIPTION:

--- YOUNGS TRIBUTARY 3.p01 (plan) ---

Plan Title=Multiple Run
Short Identifier=Multiple
Geom File=g01
Flow File=f01
Subcritical Flow
K Sum by GR= 0
Std Step Tol= 0.01
Critical Tol= 0.01
Num of Std Step Trials= 20
Max Error Tol= 0.3
Flow Tol Ratio= 0.001
Split Flow NTrial= 30
Split Flow Tol= 0.02
Split Flow Ratio= 0.02
Log Output Level= 0
Friction Slope Method= 1
Unsteady Friction Slope Method= 2
Unsteady Bridges Friction Slope Method= 1
Parabolic Critical Depth
Global Vel Dist=  1 , 1 , 1
Global Log Level= 0
CheckData=True
Encroach Param= -1, 0, 0, 0
BEGIN DESCRIPTION:
Multiple Run
END DESCRIPTION:

--- YOUNGS TRIBUTARY 3.f01 (steady flow) ---

Flow Title=Multiple
Number of Profiles=7
Profile Names=10-year,25-year,50-year,1pct_min,100-year,1pct_plu,500-year
River Rch & RM= YOUNGS TRIBUTARY,Reach-1,5364
     653    1059    1427     931    1858    3706    3115
Boundary for River Rch & Prof#=YOUNGS TRIBUTARY,Reach-1,1
Up Type=0
Dn Type=3
Dn Slope=0.005
Boundary for River Rch & Prof#=YOUNGS TRIBUTARY,Reach-1,2
Up Type=0
Dn Type=3
Dn Slope=0.005
Boundary for River Rch & Prof#=YOUNGS TRIBUTARY,Reach-1,3
Up Type=0
Dn Type=3
Dn Slope=0.005
Boundary for River Rch & Prof#=YOUNGS TRIBUTARY,Reach-1,4
Up Type=0
Dn Type=3
Dn Slope=0.005
Boundary for River Rch & Prof#=YOUNGS TRIBUTARY,Reach-1,5
Up Type=0
Dn Type=3
Dn Slope=0.005
Boundary for River Rch & Prof#=YOUNGS TRIBUTARY,Reach-1,6
Up Type=0
Dn Type=3
Dn Slope=0.005
Boundary for River Rch & Prof#=YOUNGS TRIBUTARY,Reach-1,7
Up Type=0
Dn Type=3
Dn Slope=0.005

--- YOUNGS TRIBUTARY 3.g01 (geometry) ---

Geom Title=Existing Conditions

River Reach=YOUNGS TRIBUTARY,Reach-1
Reach XY= 30
      2263575.00     13768375.00      2263815.25     13768135.53
      2263916.66     13768121.83      2264015.30     13767985.77
      2264408.72     13767741.74      2264378.46     13767576.50
      2264524.63     13767409.84      2264479.97     13767172.42
      2264526.22     13767128.53      2264642.13     13767108.69
      2264691.50     13767007.96      2264798.83     13766952.13
      2264838.56     13766861.48      2264919.35     13766819.36
      2265014.92     13766686.09      2265090.16     13766724.34
      2265364.56     13766726.38      2265428.32     13766766.96
      2265622.58     13766630.54      2265727.42     13766619.46
      2266076.64     13766378.14      2266190.21     13766424.46
      2266469.07     13766422.76      2266598.52     13766352.01
      2266776.48     13766128.61      2266950.00     13766074.61
      2267078.30     13766116.92      2267227.42     13766069.47
      2267326.45     13765978.51      2267475.00     13765975.00

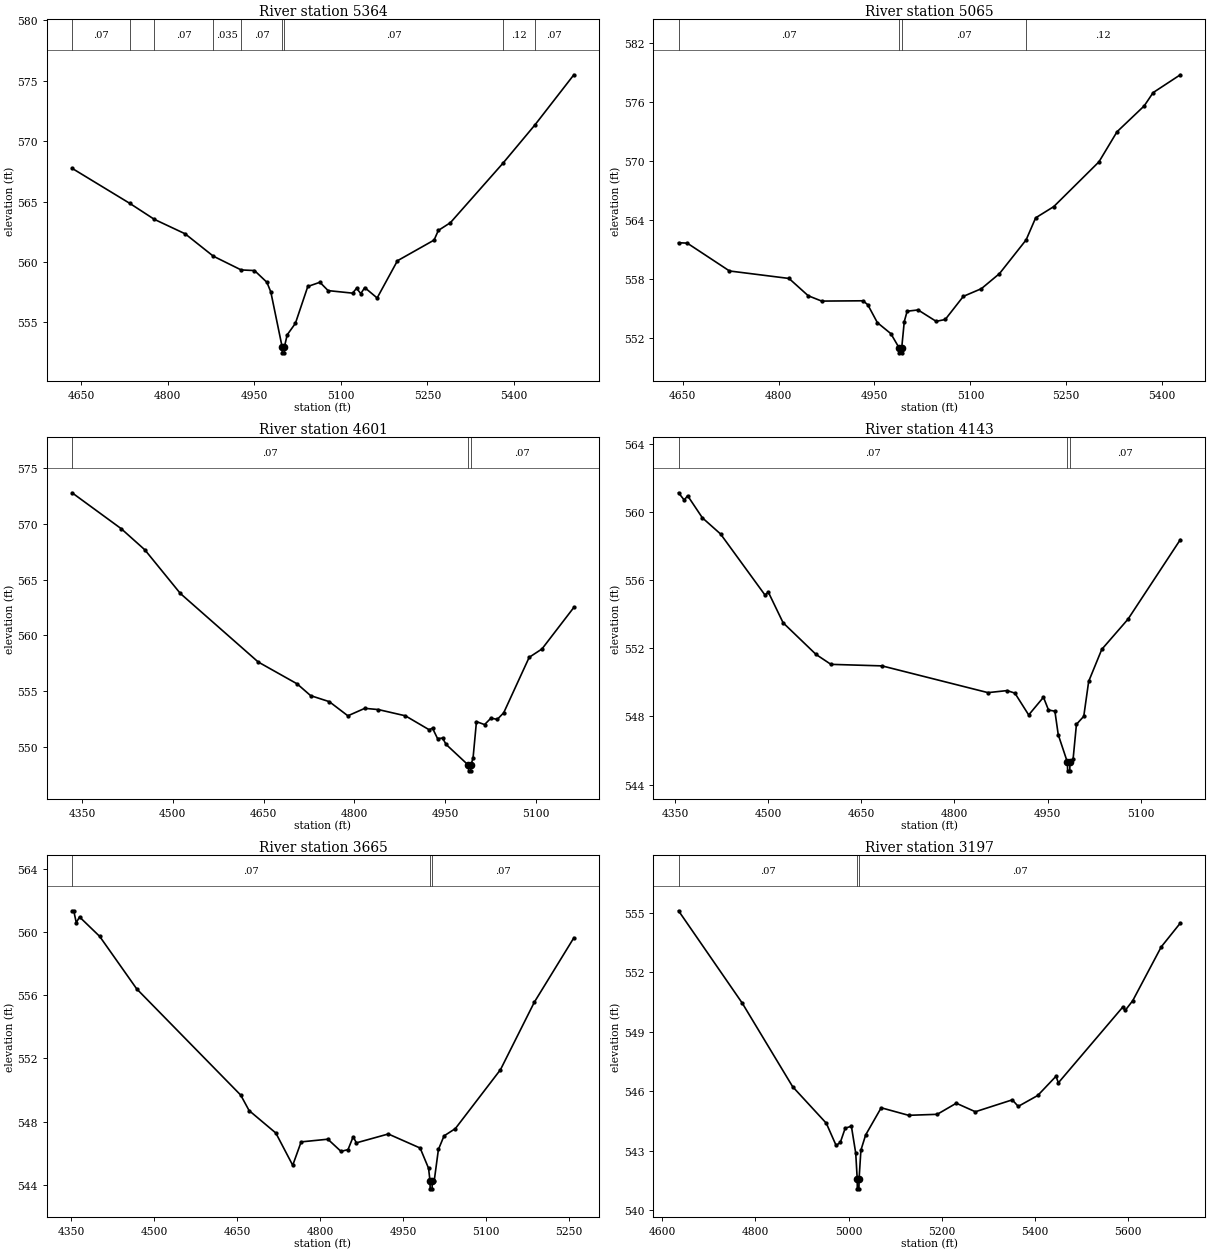
Type RM Length L Ch R = 1,5364,299,299,299
BEGIN DESCRIPTION:
J21851
END DESCRIPTION:
XS GIS Cut Line= 2
      2263861.79     13768605.26      2263271.53     13767966.39
#Sta/Elev= 30
  4634.1  567.75  4734.1  564.85  4776.6  563.53  4830.1  562.33  4878.9  560.48
  4927.2  559.34  4950.3  559.29  4971.8  558.32  4978.6  557.52  4998.2  552.98
  4998.4  552.48  5001.9  552.48  5002.2  552.98  5007.0  553.97  5021.2  554.92
  5042.7  557.97  5063.7  558.32  5077.9  557.63  5120.4  557.42  5127.2  557.82
  5134.6  557.38  5141.4  557.88  5162.9  557.02  5198.1  560.10  5261.6  561.81
  5269.0  562.61  5289.9  563.25  5380.6  568.15  5436.4  571.34  5503.9  575.49
#Mann=9,-1,0
  4634.1    0.07       0  4734.1   0.035       0  4776.6    0.07       0
  4878.9   0.035       0  4927.2    0.07       0  4998.2    0.05       0
  5002.2    0.07       0  5380.6    0.12       0  5436.4    0.07       0
Bank Sta=4998.2,5002.2
Exp/Cntr=0.3,0.1

Type RM Length L Ch R = 1,5065,464,464,464
BEGIN DESCRIPTION:
YOUNGS TRIBUTARY 3 6.0
END DESCRIPTION:
XS GIS Cut Line= 3
      2264025.02     13768425.04      2263825.00     13768125.00
      2263524.97     13767824.97
#Sta/Elev= 30
  4643.5  561.67  4657.1  561.63  4723.2  558.80  4816.3  558.04  4846.4  556.28
  4867.4  555.74  4932.0  555.77  4939.5  555.37  4954.5  553.55  4975.6  552.43
  4988.6  550.98  4988.8  550.48  4992.3  550.48  4992.6  550.98  4996.6  553.66
  5001.1  554.71  5018.2  554.84  5046.5  553.68  5060.7  553.87  5089.0  556.22
  5117.2  557.00  5145.5  558.53  5187.2  561.96  5202.1  564.20  5230.4  565.34
  5301.1  569.89  5329.4  572.95  5371.8  575.57  5385.9  576.93  5428.4  578.74
#Mann=4,-1,0
  4643.5    0.07       0  4988.6    0.05       0  4992.6    0.07       0
  5187.2    0.12       0
Bank Sta=4988.6,4992.6
Exp/Cntr=0.3,0.1

Type RM Length L Ch R = 1,4601,458,458,458
BEGIN DESCRIPTION:
YOUNGS TRIBUTARY 3 5.0
END DESCRIPTION:
XS GIS Cut Line= 3
      2264475.00     13768475.00      2264175.00     13767875.00
      2264025.03     13767825.01
#Sta/Elev= 30
  4333.5  572.79  4414.6  569.57  4453.7  567.67  4512.4  563.75  4641.0  557.60
  4705.2  555.64  4727.6  554.58  4758.4  554.04  4789.1  552.77  4817.0  553.44
  4839.4  553.33  4884.1  552.77  4923.3  551.52  4928.9  551.66  4937.2  550.73
  4945.6  550.77  4951.2  550.21  4988.3  548.33  4988.6  547.83  4992.1  547.83
  4992.3  548.33  4995.9  548.99  5001.5  552.25  5014.9  551.98  5025.4  552.56
  5035.9  552.45  5046.5  553.04  5088.6  558.02  5109.7  558.77  5162.4  562.50
#Mann=3,-1,0
  4333.5    0.07       0  4988.3    0.05       0  4992.3    0.07       0
Bank Sta=4988.3,4992.3
Exp/Cntr=0.3,0.1

Type RM Length L Ch R = 1,4143,478,478,478
BEGIN DESCRIPTION:
YOUNGS TRIBUTARY 3 4.0
END DESCRIPTION:
XS GIS Cut Line= 3
      2264624.99     13768174.99      2264375.00     13767575.00
      2264225.00     13767525.00
#Sta/Elev= 30
  4355.7  561.13  4364.9  560.70  4370.3  560.96  4394.1  559.66  4423.4  558.71
  4494.9  555.13  4500.3  555.30  4524.1  553.50  4577.2  551.64  4601.1  551.06
  4683.4  550.97  4854.0  549.40  4884.9  549.52  4897.4  549.37  4919.6  548.09
  4943.4  549.13  4951.5  548.38  4961.8  548.31  4967.2  546.93  4982.0  545.31
  4982.3  544.81  4985.8  544.81  4986.0  545.31  4991.1  545.49  4996.5  547.54
  5008.3  548.01  5016.2  550.06  5037.3  551.94  5079.5  553.71  5163.8  558.38
#Mann=3,-1,0
  4355.7    0.07       0  4982.0    0.05       0  4986.0    0.07       0
Bank Sta=4982,4986
Exp/Cntr=0.3,0.1

Type RM Length L Ch R = 1,3665,468,468,468
BEGIN DESCRIPTION:
YOUNGS TRIBUTARY 3 3.0
END DESCRIPTION:
XS GIS Cut Line= 3
      2265024.99     13767525.00      2264475.00     13767175.00
      2264224.96     13767225.01
#Sta/Elev= 30
  4351.5  561.34  4354.5  561.34  4359.1  560.59  4365.0  560.95  4401.4  559.72
  4468.3  556.40  4656.3  549.68  4671.5  548.70  4719.8  547.28  4750.3  545.24
  4765.5  546.72  4813.8  546.89  4837.5  546.12  4850.2  546.23  4859.5  547.04
  4865.4  546.66  4923.0  547.22  4980.6  546.33  4995.8  545.05  4998.4  544.25
  4998.7  543.75  5002.2  543.75  5002.4  544.25  5006.0  544.25  5013.6  546.24
  5023.8  547.10  5044.2  547.56  5125.8  551.29  5187.0  555.56  5258.4  559.63
#Mann=3,-1,0
  4351.5    0.07       0  4998.4    0.05       0  5002.4    0.07       0
Bank Sta=4998.4,5002.4
Exp/Cntr=0.3,0.1

Type RM Length L Ch R = 1,3197,326,326,326
BEGIN DESCRIPTION:
YOUNGS TRIBUTARY 3 2.0
END DESCRIPTION:
XS GIS Cut Line= 3
      2265024.99     13767224.99      2264825.00     13766925.00
      2264125.03     13766775.01
#Sta/Elev= 30
  4635.2  555.11  4771.9  550.45  4880.1  546.23  4952.2  544.39  4973.2  543.27
  4982.2  543.42  4992.7  544.14  5006.0  544.24  5015.3  542.88  5018.5  541.58
  5018.7  541.08  5022.2  541.08  5022.5  541.58  5026.4  543.03  5036.6  543.80
  5069.9  545.17  5128.7  544.79  5190.1  544.84  5231.0  545.40  5271.9  544.97
  5351.1  545.57  5363.9  545.24  5405.7  545.79  5444.9  546.76  5450.0  546.43
  5588.1  550.25  5593.2  550.08  5609.4  550.57  5670.7  553.29  5711.6  554.49
#Mann=3,-1,0
  4635.2    0.07       0  5018.5    0.05       0  5022.5    0.07       0
Bank Sta=5018.5,5022.5
Exp/Cntr=0.3,0.1

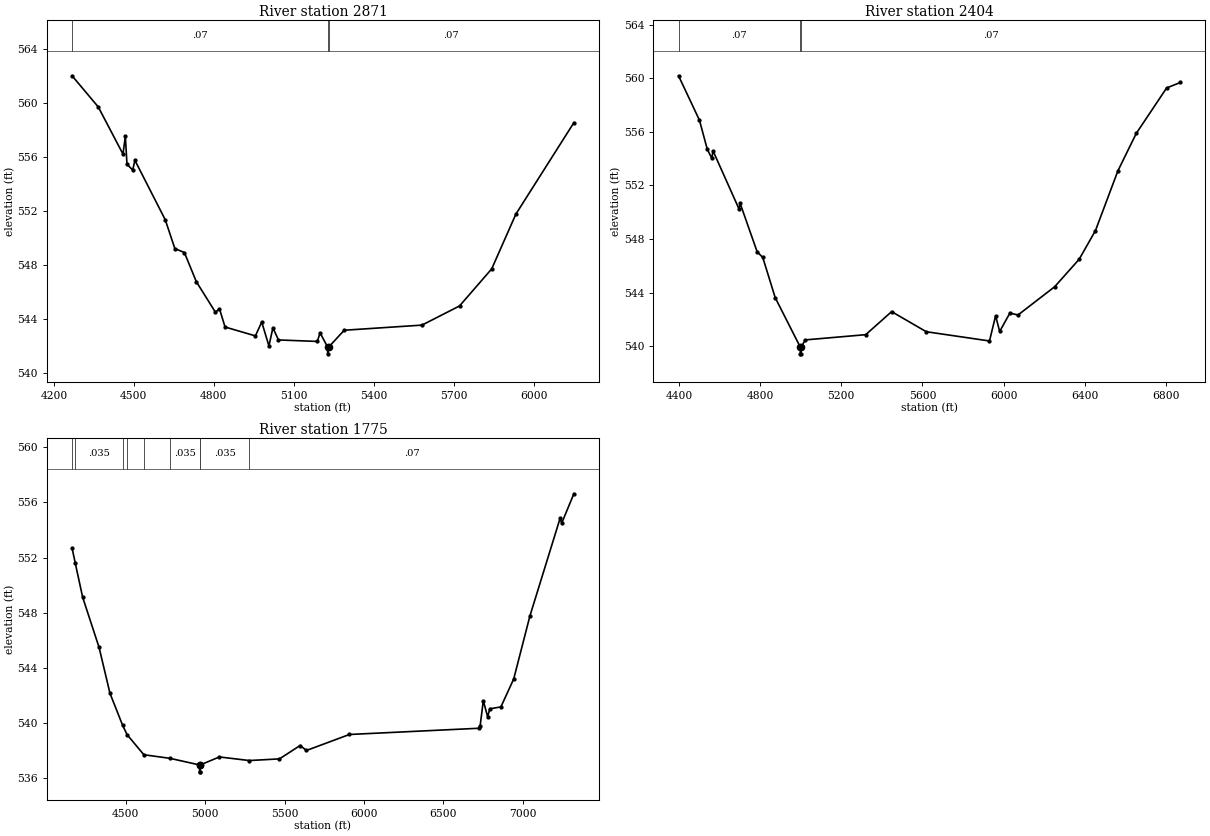
Type RM Length L Ch R = 1,2871,467,467,467
BEGIN DESCRIPTION:
J21850
END DESCRIPTION:
XS GIS Cut Line= 3
      2265424.28     13767292.74      2264945.14     13766591.38
      2263918.72     13766480.42
#Sta/Elev= 30
  4268.3  562.01  4366.5  559.70  4459.3  556.20  4468.1  557.53  4474.2  555.45
  4495.7  555.02  4504.0  555.74  4617.8  551.33  4653.7  549.20  4689.6  548.90
  4734.3  546.74  4806.1  544.47  4821.0  544.74  4842.0  543.38  4955.9  542.72
  4979.5  543.75  5006.5  541.98  5021.5  543.32  5042.4  542.42  5188.2  542.31
  5198.3  542.95  5226.6  541.89  5226.8  541.39  5230.6  541.89  5288.8  543.14
  5580.5  543.52  5721.3  544.94  5842.0  547.69  5932.6  551.75  6150.1  558.53
#Mann=3,-1,0
  4268.3    0.07       0  5226.6    0.05       0  5230.6    0.07       0
Bank Sta=5226.6,5230.6
Exp/Cntr=0.3,0.1

Type RM Length L Ch R = 1,2404,629,629,629
BEGIN DESCRIPTION:
J21849
END DESCRIPTION:
XS GIS Cut Line= 3
      2265715.98     13767292.79      2265299.31     13766466.38
      2263758.86     13766313.73
#Sta/Elev= 30
  4398.0  560.18  4501.0  556.87  4540.0  554.68  4562.3  554.02  4567.9  554.58
  4696.2  550.24  4701.8  550.65  4785.4  547.05  4813.3  546.62  4874.6  543.62
  4998.3  539.93  4998.5  539.43  5002.0  539.43  5002.3  539.93  5022.7  540.47
  5320.7  540.86  5448.4  542.58  5619.3  541.08  5930.8  540.39  5960.9  542.27
  5981.0  541.10  6031.3  542.47  6071.5  542.33  6252.3  544.44  6372.9  546.49
  6453.3  548.63  6563.9  553.09  6654.3  555.88  6803.9  559.27  6871.5  559.68
#Mann=3,-1,0
  4398.0    0.07       0  4998.3    0.05       0  5002.3    0.07       0
Bank Sta=4998.3,5002.3
Exp/Cntr=0.3,0.1

Type RM Length L Ch R = 1,1775,0,0,0
BEGIN DESCRIPTION:
J21848
END DESCRIPTION:
XS GIS Cut Line= 5
      2265847.92     13767237.22      2266077.08     13766646.94
      2265778.47     13766140.00      2264743.75     13766098.33
      2263849.00     13766202.37
#Sta/Elev= 30
  4162.6  552.69  4182.7  551.60  4229.3  549.12  4332.7  545.48  4401.0  542.16
  4480.9  539.83  4509.3  539.15  4614.5  537.70  4778.6  537.44  4964.9  536.96
  4965.1  536.46  4968.6  536.46  4968.9  536.96  5089.8  537.54  5278.1  537.28
  5467.7  537.40  5597.8  538.37  5637.8  538.01  5908.1  539.17  6720.5  539.62
  6730.6  539.79  6750.7  541.62  6778.2  540.44  6791.0  541.03  6861.4  541.17
  6942.0  543.20  7044.0  547.77  7233.9  554.85  7244.0  554.50  7320.5  556.63
#Mann=9,-1,0
  4162.6    0.07       0  4182.7   0.035       0  4480.9    0.07       0
  4509.3   0.035       0  4614.5    0.07       0  4778.6   0.035       0
  4964.9   0.035       0  4968.9   0.035       0  5278.1    0.07       0
Bank Sta=4964.9,4968.9
Exp/Cntr=0.3,0.1

Chan Stop Cuts=-1