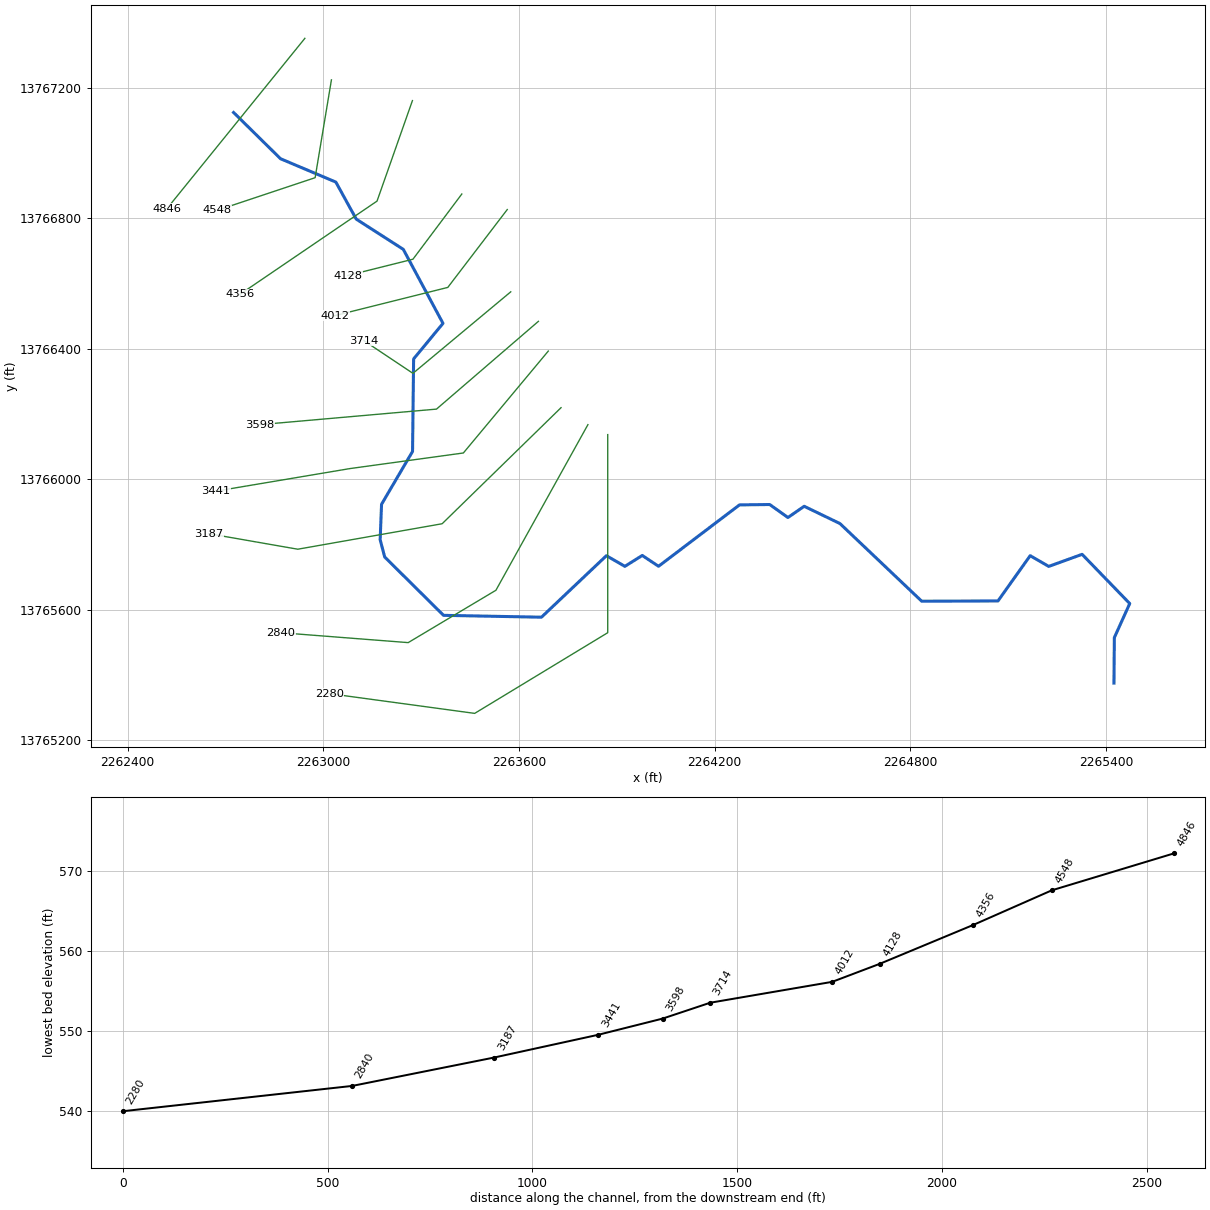
--- YOUNGS TRIBUTARY 3B.prj (project) ---

Proj Title=YOUNGS TRIBUTARY 3B Base Level Engineering
Current Plan=p01
Default Exp/Contr=0.3,0.1
English Units
Geom File=g01
Flow File=f01
Plan File=p01
BEGIN DESCRIPTION:
YOUNGS TRIBUTARY 3B
END DESCRIPTION:

--- YOUNGS TRIBUTARY 3B.p01 (plan) ---

Plan Title=Multiple Run
Short Identifier=Multiple
Geom File=g01
Flow File=f01
Subcritical Flow
K Sum by GR= 0
Std Step Tol= 0.01
Critical Tol= 0.01
Num of Std Step Trials= 20
Max Error Tol= 0.3
Flow Tol Ratio= 0.001
Split Flow NTrial= 30
Split Flow Tol= 0.02
Split Flow Ratio= 0.02
Log Output Level= 0
Friction Slope Method= 1
Unsteady Friction Slope Method= 2
Unsteady Bridges Friction Slope Method= 1
Parabolic Critical Depth
Global Vel Dist=  1 , 1 , 1
Global Log Level= 0
CheckData=True
Encroach Param= -1, 0, 0, 0
BEGIN DESCRIPTION:
Multiple Run
END DESCRIPTION:

--- YOUNGS TRIBUTARY 3B.f01 (steady flow) ---

Flow Title=Multiple
Number of Profiles=7
Profile Names=10-year,25-year,50-year,1pct_min,100-year,1pct_plu,500-year
River Rch & RM= YOUNGS TRIBUTARY,Reach-1,4846
     327     507     664     422     842    1680    1338
Boundary for River Rch & Prof#=YOUNGS TRIBUTARY,Reach-1,1
Up Type=0
Dn Type=3
Dn Slope=0.005
Boundary for River Rch & Prof#=YOUNGS TRIBUTARY,Reach-1,2
Up Type=0
Dn Type=3
Dn Slope=0.005
Boundary for River Rch & Prof#=YOUNGS TRIBUTARY,Reach-1,3
Up Type=0
Dn Type=3
Dn Slope=0.005
Boundary for River Rch & Prof#=YOUNGS TRIBUTARY,Reach-1,4
Up Type=0
Dn Type=3
Dn Slope=0.005
Boundary for River Rch & Prof#=YOUNGS TRIBUTARY,Reach-1,5
Up Type=0
Dn Type=3
Dn Slope=0.005
Boundary for River Rch & Prof#=YOUNGS TRIBUTARY,Reach-1,6
Up Type=0
Dn Type=3
Dn Slope=0.005
Boundary for River Rch & Prof#=YOUNGS TRIBUTARY,Reach-1,7
Up Type=0
Dn Type=3
Dn Slope=0.005

--- YOUNGS TRIBUTARY 3B.g01 (geometry) ---

Geom Title=Existing Conditions

River Reach=YOUNGS TRIBUTARY,Reach-1
Reach XY= 30
      2262725.00     13767125.00      2262868.94     13766983.14
      2263038.56     13766911.52      2263101.17     13766797.87
      2263245.42     13766705.23      2263367.16     13766478.23
      2263277.07     13766369.15      2263273.80     13766085.50
      2263178.74     13765923.44      2263174.45     13765814.81
      2263188.37     13765761.68      2263368.81     13765582.81
      2263669.15     13765577.06      2263868.33     13765765.71
      2263925.00     13765733.03      2263978.33     13765766.46
      2264028.23     13765733.23      2264276.50     13765921.54
      2264369.11     13765922.65      2264425.10     13765882.80
      2264474.92     13765917.24      2264584.68     13765864.25
      2264835.43     13765626.05      2265069.33     13765626.98
      2265168.05     13765765.82      2265224.90     13765732.84
      2265327.29     13765769.89      2265473.38     13765618.97
      2265426.19     13765514.52      2265425.00     13765375.00

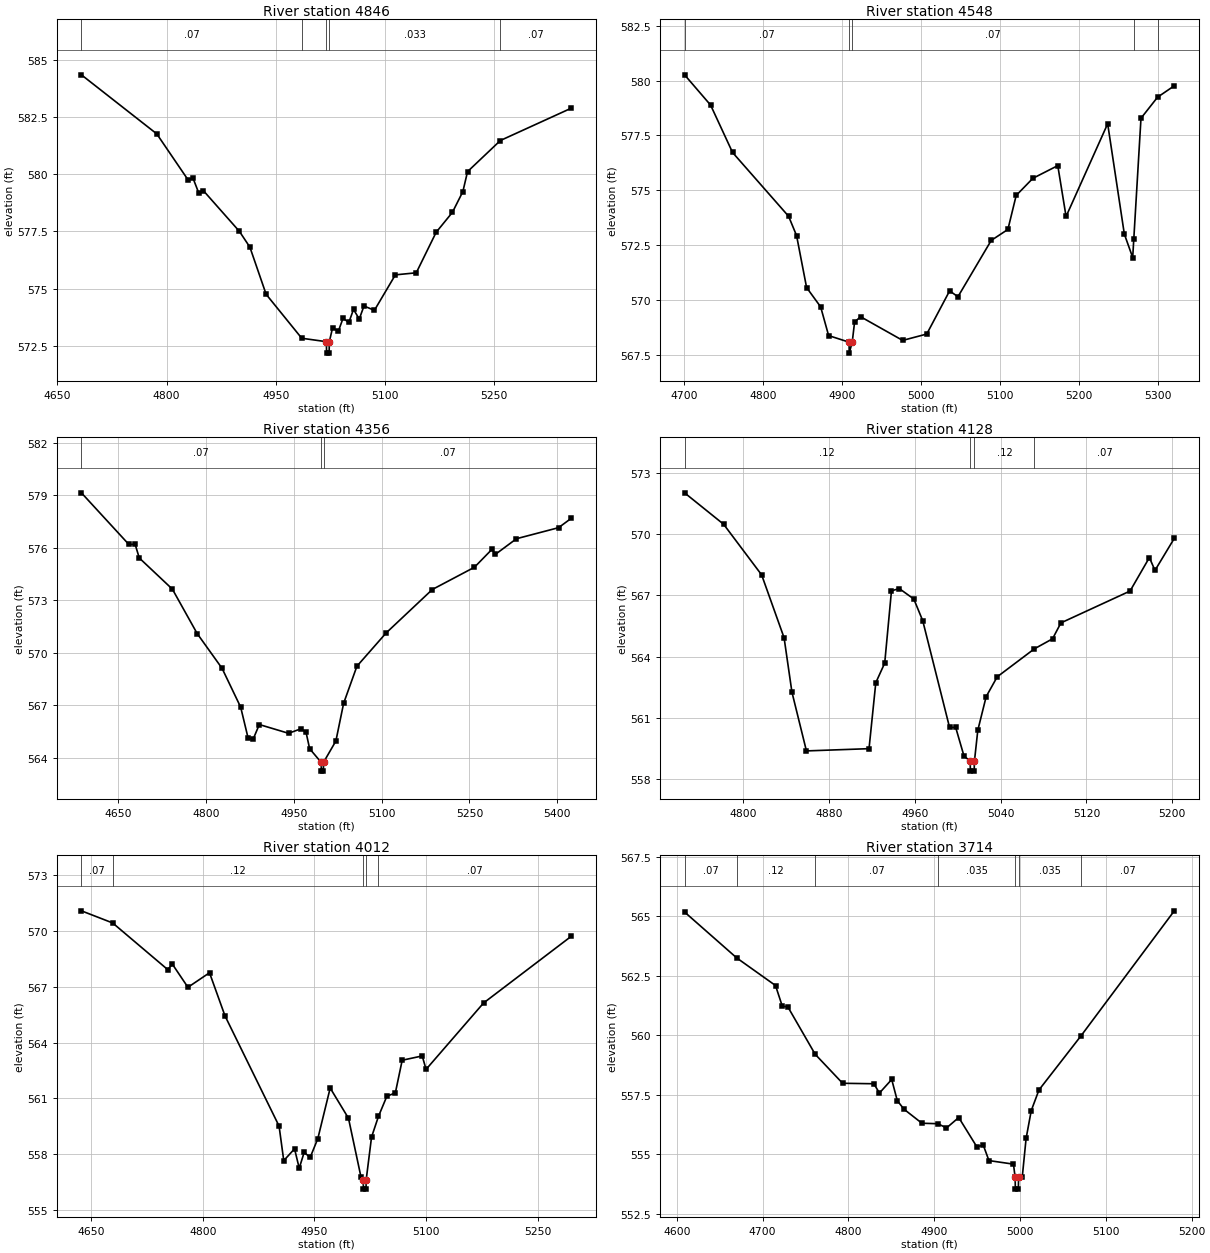
Type RM Length L Ch R = 1,4846,298,298,298
BEGIN DESCRIPTION:
J21859
END DESCRIPTION:
XS GIS Cut Line= 2
      2262943.56     13767352.42      2262520.23     13766829.74
#Sta/Elev= 30
  4682.9  584.34  4786.4  581.76  4829.6  579.74  4836.0  579.84  4843.9  579.19
  4850.4  579.28  4899.9  577.50  4914.3  576.81  4936.6  574.75  4985.5  572.83
  5019.4  572.68  5019.6  572.18  5023.1  572.18  5023.4  572.68  5027.8  573.28
  5035.8  573.14  5042.2  573.70  5050.2  573.52  5056.6  574.09  5064.5  573.67
  5071.0  574.24  5085.3  574.05  5114.1  575.60  5142.8  575.69  5170.1  577.46
  5192.4  578.33  5206.8  579.24  5213.2  580.11  5258.3  581.47  5355.5  582.88
#Mann=5,-1,0
  4682.9    0.07       0  4985.5   0.033       0  5019.4   0.033       0
  5023.4   0.033       0  5258.3    0.07       0
Bank Sta=5019.4,5023.4
Exp/Cntr=0.3,0.1

Type RM Length L Ch R = 1,4548,192,192,192
BEGIN DESCRIPTION:
YOUNGS TRIBUTARY 3B 3.0
END DESCRIPTION:
XS GIS Cut Line= 3
      2263025.00     13767225.01      2262975.00     13766925.00
      2262674.97     13766824.99
#Sta/Elev= 30
  4700.6  580.26  4733.6  578.88  4761.4  576.72  4832.4  573.81  4842.5  572.93
  4855.2  570.56  4873.0  569.68  4883.1  568.37  4909.0  568.07  4909.2  567.57
  4913.0  568.07  4916.0  568.99  4923.6  569.23  4976.9  568.15  5007.4  568.44
  5036.4  570.41  5046.9  570.14  5089.1  572.71  5110.2  573.21  5120.7  574.76
  5141.8  575.54  5173.4  576.12  5183.9  573.80  5236.6  578.03  5257.7  573.00
  5268.3  571.93  5269.7  572.78  5278.8  578.28  5299.8  579.24  5321.0  579.76
#Mann=5,-1,0
  4700.6    0.07       0  4909.0    0.05       0  4913.0    0.07       0
  5269.7   0.033       0  5299.8    0.07       0
Bank Sta=4909,4913
Exp/Cntr=0.3,0.1

Type RM Length L Ch R = 1,4356,228,228,228
BEGIN DESCRIPTION:
J21858
END DESCRIPTION:
XS GIS Cut Line= 3
      2263273.44     13767161.50      2263164.92     13766853.30
      2262743.89     13766566.82
#Sta/Elev= 30
  4587.6  579.13  4668.7  576.18  4679.3  576.19  4686.4  575.41  4742.9  573.63
  4785.3  571.09  4827.7  569.11  4859.5  566.89  4872.2  565.12  4880.7  565.06
  4891.3  565.90  4941.2  565.40  4962.6  565.66  4971.1  565.45  4977.2  564.52
  4996.9  563.74  4997.2  563.24  5000.7  563.24  5000.9  563.74  5022.0  564.96
  5035.2  567.11  5057.9  569.23  5107.8  571.13  5186.6  573.61  5258.5  574.88
  5288.3  575.90  5294.4  575.62  5330.3  576.51  5402.1  577.14  5423.6  577.67
#Mann=3,-1,0
  4587.6    0.07       0  4996.9    0.05       0  5000.9    0.07       0
Bank Sta=4996.9,5000.9
Exp/Cntr=0.3,0.1

Type RM Length L Ch R = 1,4128,116,116,116
BEGIN DESCRIPTION:
YOUNGS TRIBUTARY 3B 2.0
END DESCRIPTION:
XS GIS Cut Line= 3
      2263424.97     13766874.96      2263275.00     13766675.00
      2263075.01     13766625.00
#Sta/Elev= 30
  4745.7  572.02  4782.1  570.48  4817.5  568.00  4838.4  564.92  4845.7  562.26
  4859.2  559.38  4917.5  559.49  4923.8  562.72  4932.1  563.68  4938.4  567.22
  4945.7  567.33  4959.2  566.82  4967.5  565.76  4992.5  560.53  4998.2  560.53
  5006.0  559.12  5011.7  558.89  5011.9  558.39  5015.4  558.39  5015.7  558.89
  5018.8  560.39  5026.6  562.04  5036.9  563.01  5071.5  564.38  5088.4  564.87
  5096.2  565.65  5160.6  567.21  5178.6  568.85  5183.8  568.22  5201.8  569.79
#Mann=4,-1,0
  4745.7    0.12       0  5011.7    0.05       0  5015.7    0.12       0
  5071.5    0.07       0
Bank Sta=5011.7,5015.7
Exp/Cntr=0.3,0.1

Type RM Length L Ch R = 1,4012,298,298,298
BEGIN DESCRIPTION:
J21857
END DESCRIPTION:
XS GIS Cut Line= 3
      2263564.22     13766827.26      2263381.93     13766588.54
      2263034.68     13766501.73
#Sta/Elev= 30
  4636.7  571.06  4678.7  570.41  4752.7  567.91  4759.0  568.20  4779.9  566.96
  4808.9  567.74  4829.7  565.43  4902.4  559.52  4908.7  557.67  4923.2  558.30
  4929.5  557.26  4936.1  558.11  4944.2  557.84  4954.5  558.85  4971.1  561.56
  4995.7  559.94  5012.4  556.81  5015.5  556.64  5015.8  556.14  5019.3  556.14
  5019.5  556.64  5026.7  558.93  5036.0  560.04  5047.3  561.12  5058.7  561.30
  5067.9  563.05  5094.8  563.28  5100.0  562.56  5177.3  566.12  5295.0  569.69
#Mann=5,-1,0
  4636.7    0.07       0  4678.7    0.12       0  5015.5    0.05       0
  5019.5    0.12       0  5036.0    0.07       0
Bank Sta=5015.5,5019.5
Exp/Cntr=0.3,0.1

Type RM Length L Ch R = 1,3714,116,116,116
BEGIN DESCRIPTION:
YOUNGS TRIBUTARY 3B 1.0
END DESCRIPTION:
XS GIS Cut Line= 3
      2263574.97     13766574.97      2263275.00     13766325.00
      2263125.04     13766424.97
#Sta/Elev= 30
  4609.0  565.18  4669.8  563.25  4715.0  562.09  4722.9  561.22  4729.4  561.19
  4761.2  559.20  4793.2  557.98  4829.6  557.96  4836.1  557.57  4850.4  558.14
  4856.9  557.25  4864.7  556.89  4885.6  556.30  4904.3  556.28  4914.2  556.10
  4928.5  556.54  4949.4  555.32  4957.2  555.37  4963.7  554.73  4992.3  554.58
  4994.2  554.03  4994.5  553.53  4998.0  553.53  4998.2  554.03  5002.5  554.03
  5007.0  555.66  5013.0  556.83  5022.0  557.70  5070.9  559.97  5179.7  565.23
#Mann=7,-1,0
  4609.0    0.07       0  4669.8    0.12       0  4761.2    0.07       0
  4904.3   0.035       0  4994.2   0.035       0  4998.2   0.035       0
  5070.9    0.07       0
Bank Sta=4994.2,4998.2
Exp/Cntr=0.3,0.1

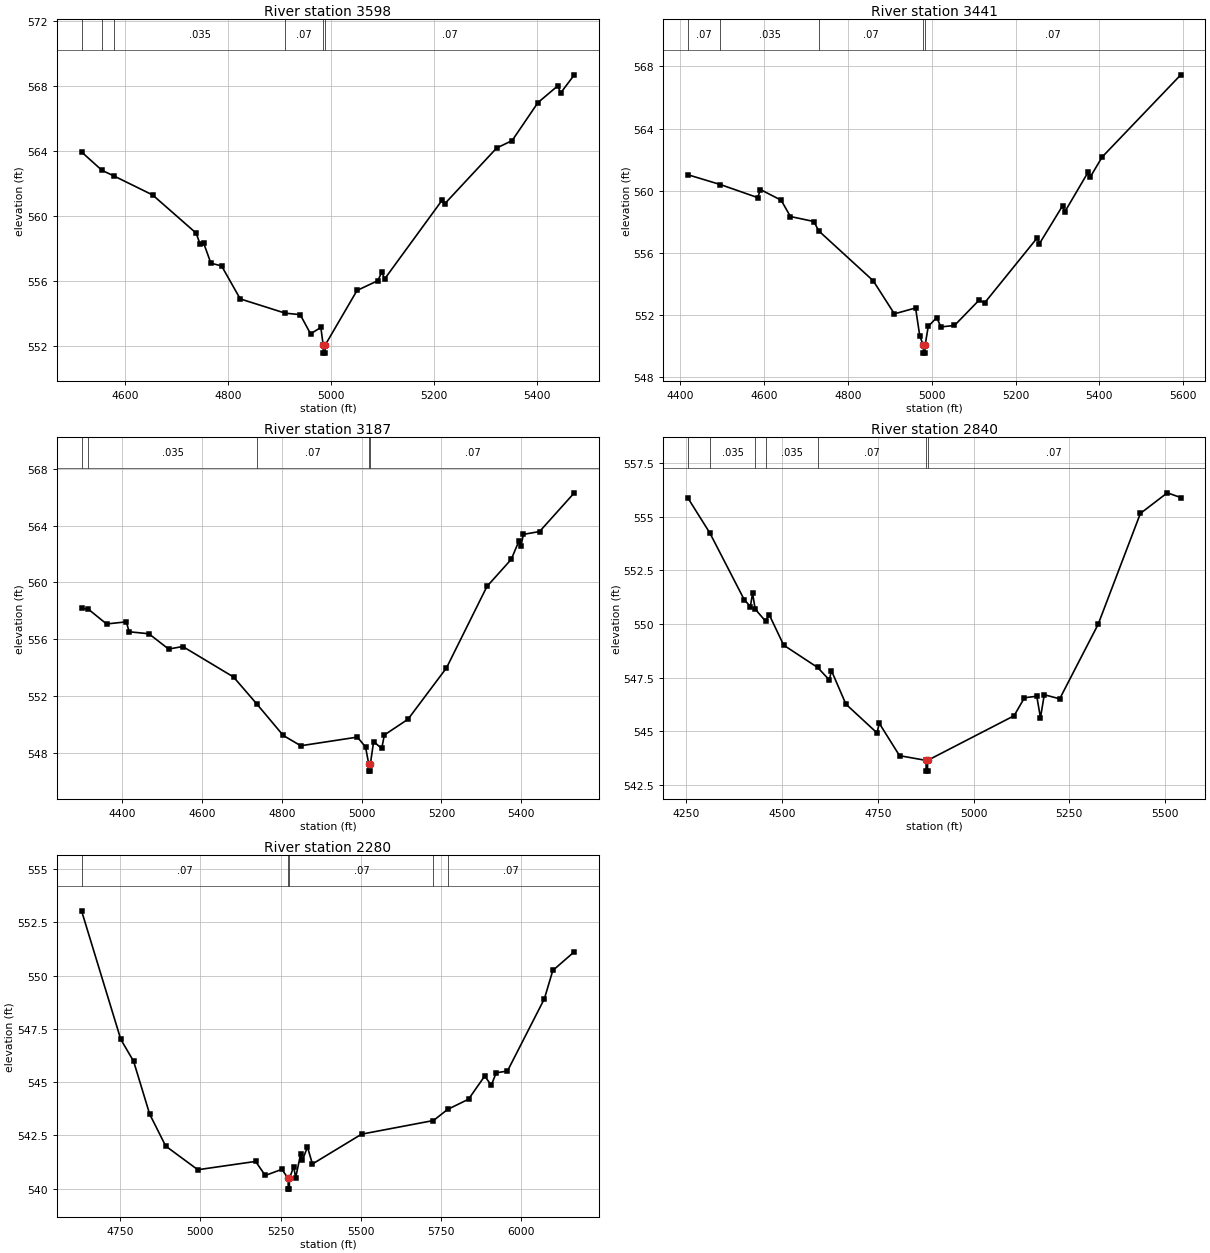
Type RM Length L Ch R = 1,3598,157,157,157
BEGIN DESCRIPTION:
J21856
END DESCRIPTION:
XS GIS Cut Line= 3
      2263659.74     13766484.40      2263347.21     13766215.28
      2262804.64     13766167.53
#Sta/Elev= 30
  4515.1  563.94  4554.6  562.81  4578.7  562.45  4653.2  561.29  4737.7  558.94
  4745.4  558.25  4752.0  558.35  4766.3  557.09  4787.1  556.92  4823.3  554.89
  4910.8  554.01  4939.8  553.92  4959.9  552.74  4979.9  553.13  4984.4  552.05
  4984.6  551.55  4988.1  551.55  4988.4  552.05  5050.2  555.41  5090.4  556.01
  5098.6  556.55  5103.6  556.11  5215.9  560.99  5220.9  560.76  5321.3  564.18
  5351.4  564.64  5401.6  566.98  5440.4  568.02  5445.4  567.56  5472.2  568.69
#Mann=6,-1,0
  4515.1   0.035       0  4554.6    0.07       0  4578.7   0.035       0
  4910.8    0.07       0  4984.4    0.05       0  4988.4    0.07       0
Bank Sta=4984.4,4988.4
Exp/Cntr=0.3,0.1

Type RM Length L Ch R = 1,3441,254,254,254
BEGIN DESCRIPTION:
J21855
END DESCRIPTION:
XS GIS Cut Line= 4
      2263690.12     13766393.26      2263429.68     13766080.73
      2263082.45     13766032.99      2262670.17     13765963.55
#Sta/Elev= 30
  4418.7  561.02  4496.0  560.39  4584.9  559.55  4591.4  560.07  4640.9  559.38
  4663.0  558.33  4719.0  558.01  4730.3  557.41  4860.5  554.19  4911.0  552.06
  4961.5  552.44  4971.6  550.62  4980.2  550.03  4980.4  549.53  4983.9  549.53
  4984.2  550.03  4991.7  551.25  5011.9  551.82  5022.0  551.22  5054.2  551.31
  5112.9  552.94  5126.3  552.77  5251.8  556.96  5256.9  556.58  5312.4  559.03
  5317.4  558.63  5372.9  561.18  5378.0  560.87  5406.7  562.17  5594.1  567.46
#Mann=5,-1,0
  4418.7    0.07       0  4496.0   0.035       0  4730.3    0.07       0
  4980.2    0.05       0  4984.2    0.07       0
Bank Sta=4980.2,4984.2
Exp/Cntr=0.3,0.1

Type RM Length L Ch R = 1,3187,347,347,347
BEGIN DESCRIPTION:
J21854
END DESCRIPTION:
XS GIS Cut Line= 4
      2263729.16     13766219.62      2263364.57     13765863.72
      2262921.86     13765785.59      2262649.24     13765833.19
#Sta/Elev= 30
  4297.5  558.18  4314.6  558.11  4360.2  557.07  4409.8  557.22  4416.8  556.52
  4466.4  556.38  4515.8  555.30  4551.3  555.48  4678.6  553.33  4736.9  551.43
  4803.2  549.21  4847.2  548.48  4989.3  549.09  5009.7  548.39  5017.8  547.19
  5018.1  546.69  5021.6  546.69  5021.8  547.19  5030.0  548.77  5050.3  548.29
  5056.9  549.24  5116.2  550.35  5212.7  553.97  5314.3  559.72  5375.2  561.63
  5394.4  562.92  5399.5  562.57  5405.6  563.39  5446.2  563.59  5533.3  566.32
#Mann=5,-1,0
  4297.5    0.07       0  4314.6   0.035       0  4736.9    0.07       0
  5017.8    0.05       0  5021.8    0.07       0
Bank Sta=5017.8,5021.8
Exp/Cntr=0.3,0.1

Type RM Length L Ch R = 1,2840,560,560,560
BEGIN DESCRIPTION:
J21853
END DESCRIPTION:
XS GIS Cut Line= 4
      2263811.64     13766167.57      2263529.50     13765659.72
      2263260.41     13765499.13      2262869.92     13765529.50
#Sta/Elev= 30
  4254.9  555.86  4311.8  554.24  4401.6  551.13  4417.6  550.81  4423.4  551.43
  4430.2  550.69  4457.2  550.13  4466.8  550.43  4504.6  549.01  4593.2  547.97
  4623.6  547.39  4629.3  547.82  4667.0  546.26  4748.2  544.92  4754.0  545.37
  4806.9  543.86  4876.1  543.64  4876.4  543.14  4879.9  543.14  4880.1  543.64
  5105.8  545.72  5133.0  546.56  5165.1  546.63  5174.7  545.63  5184.7  546.70
  5224.9  546.51  5325.2  549.98  5435.5  555.15  5505.7  556.11  5540.9  555.89
#Mann=7,-1,0
  4254.9    0.07       0  4311.8   0.035       0  4430.2    0.07       0
  4457.2   0.035       0  4593.2    0.07       0  4876.1    0.05       0
  4880.1    0.07       0
Bank Sta=4876.1,4880.1
Exp/Cntr=0.3,0.1

Type RM Length L Ch R = 1,2280,0,0,0
BEGIN DESCRIPTION:
J21852
END DESCRIPTION:
XS GIS Cut Line= 4
      2263872.38     13766137.11      2263872.38     13765529.51
      2263464.40     13765282.12      2263018.63     13765342.71
#Sta/Elev= 30
  4630.0  553.04  4752.1  547.01  4792.1  545.98  4842.1  543.50  4892.1  542.00
  4992.1  540.89  5172.1  541.28  5202.1  540.62  5254.0  540.91  5273.4  540.48
  5273.6  539.98  5277.1  539.98  5277.4  540.48  5290.8  541.04  5296.7  540.51
  5312.2  541.62  5318.0  541.34  5333.5  541.96  5349.0  541.16  5502.2  542.56
  5726.0  543.20  5770.0  543.72  5835.2  544.20  5885.7  545.29  5905.9  544.85
  5921.4  545.44  5956.3  545.52  6071.3  548.91  6097.6  550.24  6164.6  551.12
#Mann=5,-1,0
  4630.0    0.07       0  5273.4    0.05       0  5277.4    0.07       0
  5726.0   0.035       0  5770.0    0.07       0
Bank Sta=5273.4,5277.4
Exp/Cntr=0.3,0.1

Chan Stop Cuts=-1