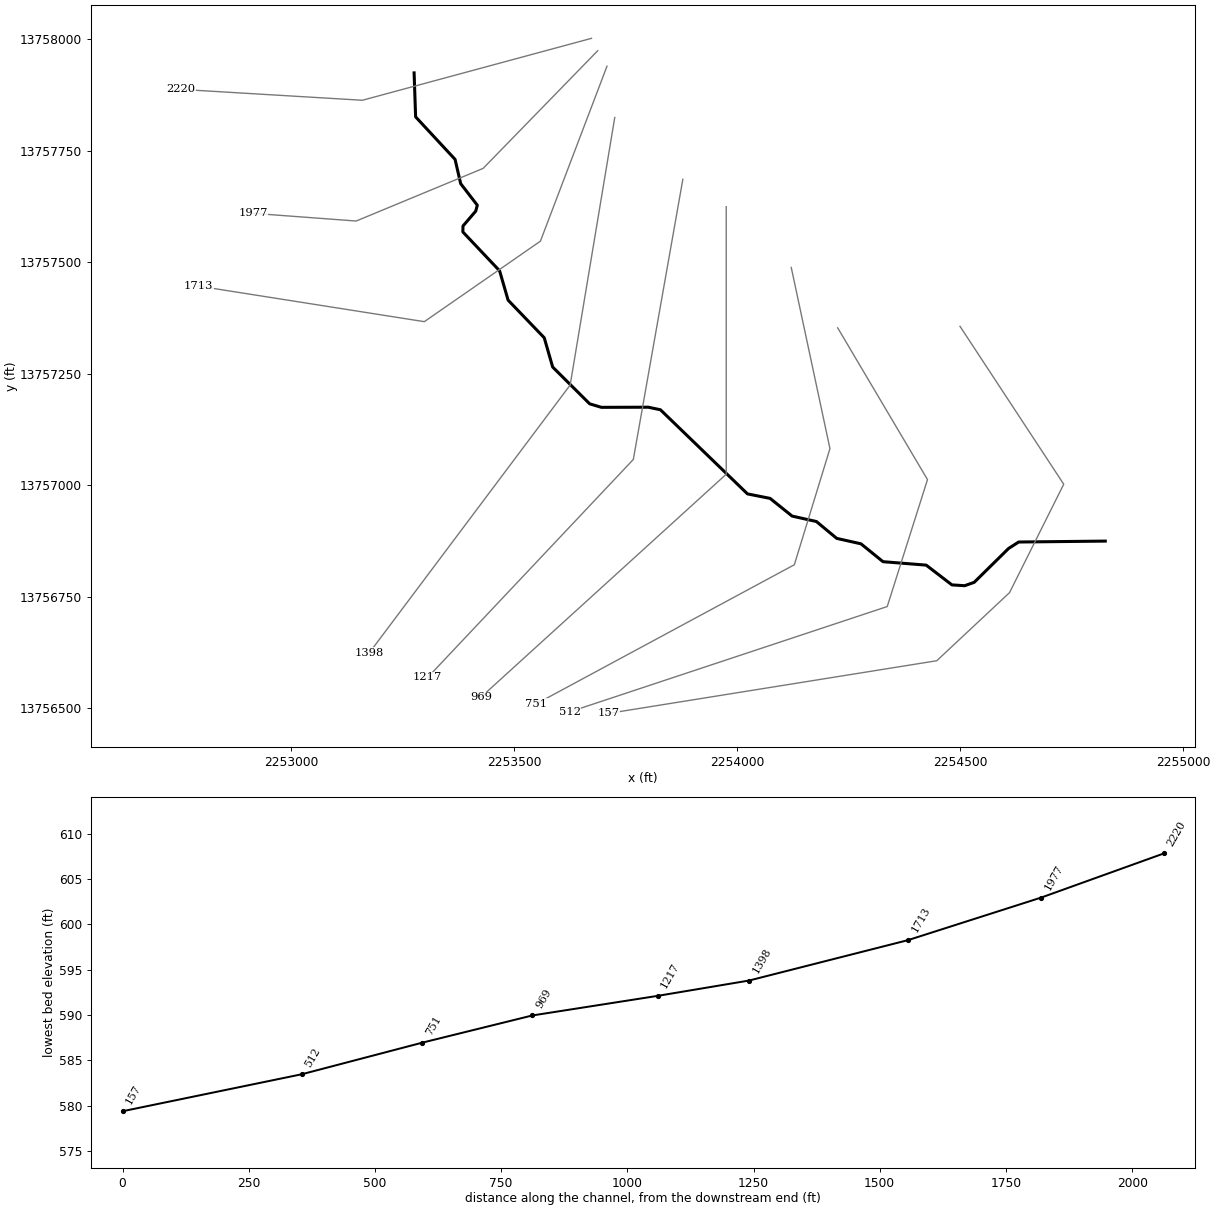
--- YOUNGS TRIBUTARY 4 2.prj (project) ---

Proj Title=YOUNGS TRIBUTARY 4 2 Base Level Engineering
Current Plan=p01
Default Exp/Contr=0.3,0.1
English Units
Geom File=g01
Flow File=f01
Plan File=p01
BEGIN DESCRIPTION:
YOUNGS TRIBUTARY 4 2
END DESCRIPTION:

--- YOUNGS TRIBUTARY 4 2.p01 (plan) ---

Plan Title=Multiple Run
Short Identifier=Multiple
Geom File=g01
Flow File=f01
Subcritical Flow
K Sum by GR= 0
Std Step Tol= 0.01
Critical Tol= 0.01
Num of Std Step Trials= 20
Max Error Tol= 0.3
Flow Tol Ratio= 0.001
Split Flow NTrial= 30
Split Flow Tol= 0.02
Split Flow Ratio= 0.02
Log Output Level= 0
Friction Slope Method= 1
Unsteady Friction Slope Method= 2
Unsteady Bridges Friction Slope Method= 1
Parabolic Critical Depth
Global Vel Dist=  1 , 1 , 1
Global Log Level= 0
CheckData=True
Encroach Param= -1, 0, 0, 0
BEGIN DESCRIPTION:
Multiple Run
END DESCRIPTION:

--- YOUNGS TRIBUTARY 4 2.f01 (steady flow) ---

Flow Title=Multiple
Number of Profiles=7
Profile Names=10-year,25-year,50-year,1pct_min,100-year,1pct_plu,500-year
River Rch & RM= YOUNGS TRIBUTARY,Reach-1,2220
     116     167     208     126     252     503     366
Boundary for River Rch & Prof#=YOUNGS TRIBUTARY,Reach-1,1
Up Type=0
Dn Type=3
Dn Slope=0.005
Boundary for River Rch & Prof#=YOUNGS TRIBUTARY,Reach-1,2
Up Type=0
Dn Type=3
Dn Slope=0.005
Boundary for River Rch & Prof#=YOUNGS TRIBUTARY,Reach-1,3
Up Type=0
Dn Type=3
Dn Slope=0.005
Boundary for River Rch & Prof#=YOUNGS TRIBUTARY,Reach-1,4
Up Type=0
Dn Type=3
Dn Slope=0.005
Boundary for River Rch & Prof#=YOUNGS TRIBUTARY,Reach-1,5
Up Type=0
Dn Type=3
Dn Slope=0.005
Boundary for River Rch & Prof#=YOUNGS TRIBUTARY,Reach-1,6
Up Type=0
Dn Type=3
Dn Slope=0.005
Boundary for River Rch & Prof#=YOUNGS TRIBUTARY,Reach-1,7
Up Type=0
Dn Type=3
Dn Slope=0.005

--- YOUNGS TRIBUTARY 4 2.g01 (geometry) ---

Geom Title=Existing Conditions

River Reach=YOUNGS TRIBUTARY,Reach-1
Reach XY= 30
      2253275.00     13757925.00      2253278.39     13757826.41
      2253366.86     13757731.04      2253379.44     13757676.65
      2253416.75     13757628.23      2253413.16     13757614.95
      2253384.61     13757581.66      2253384.31     13757568.34
      2253466.80     13757481.05      2253485.80     13757415.33
      2253566.82     13757331.04      2253585.77     13757265.30
      2253668.79     13757182.81      2253694.99     13757174.98
      2253800.11     13757175.27      2253827.45     13757169.53
      2254022.70     13756980.83      2254073.26     13756970.81
      2254122.80     13756931.08      2254177.20     13756918.92
      2254222.80     13756881.08      2254277.18     13756868.88
      2254326.58     13756828.83      2254423.42     13756821.11
      2254481.13     13756776.78      2254509.66     13756774.96
      2254531.05     13756782.50      2254608.25     13756858.53
      2254630.85     13756872.94      2254825.00     13756875.00

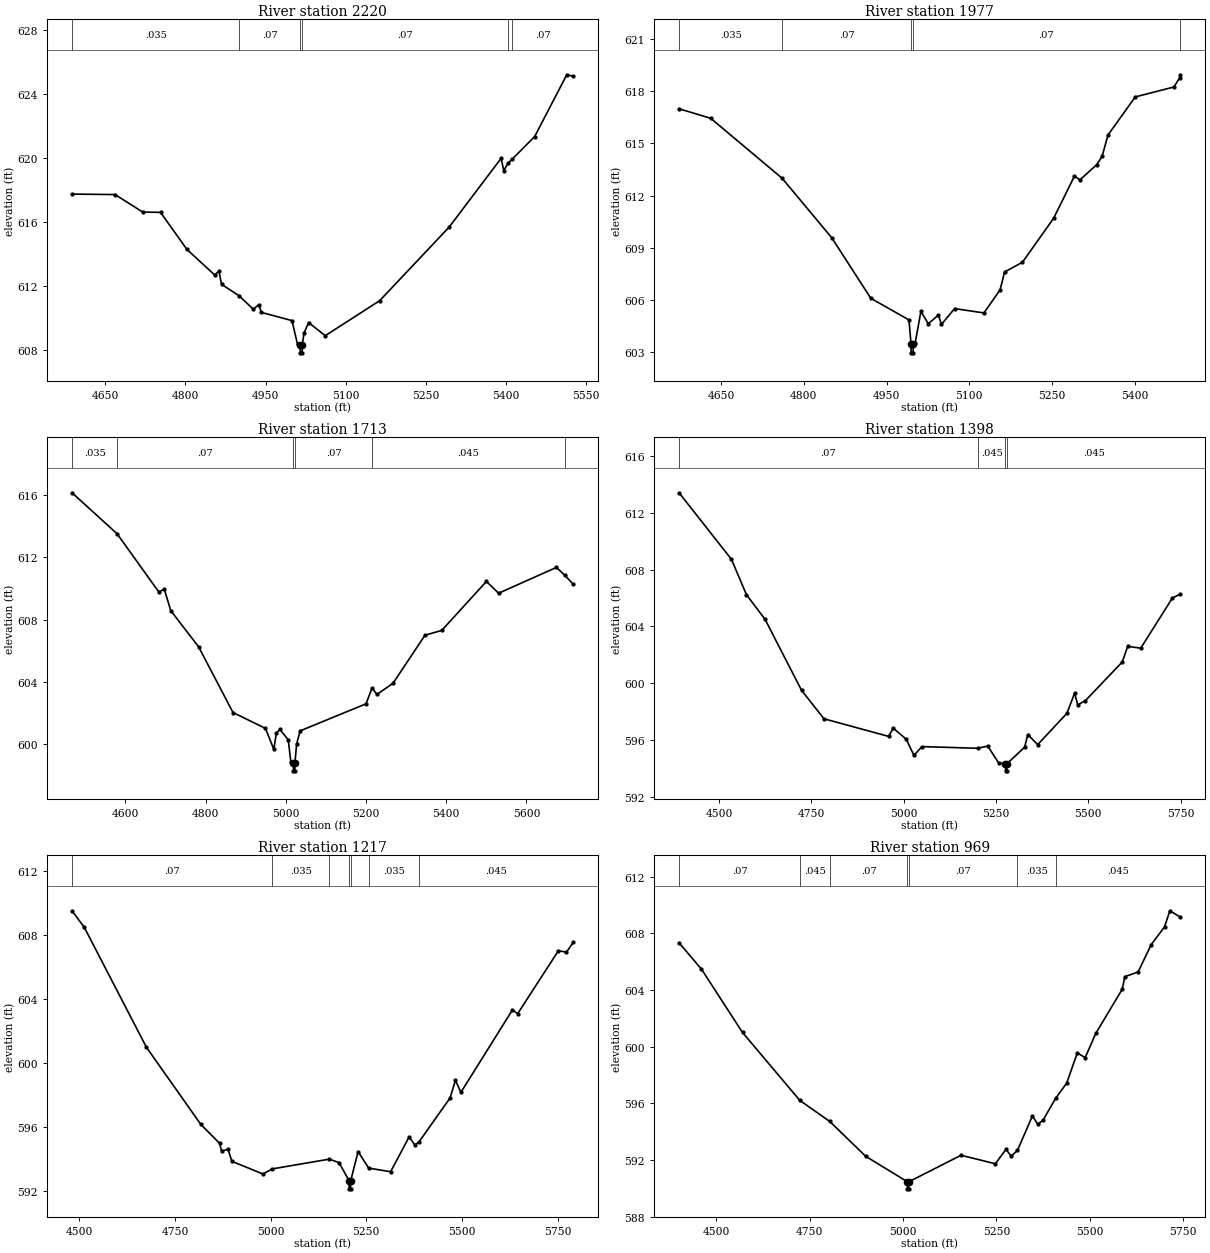
Type RM Length L Ch R = 1,2220,243,243,243
BEGIN DESCRIPTION:
J21868
END DESCRIPTION:
XS GIS Cut Line= 3
      2253672.83     13758002.52      2253158.98     13757863.64
      2252752.70     13757887.95
#Sta/Elev= 30
  4587.5  617.74  4668.1  617.71  4719.9  616.62  4753.3  616.60  4802.8  614.29
  4854.6  612.70  4862.6  612.93  4867.8  612.11  4900.5  611.40  4927.1  610.56
  4937.2  610.84  4942.4  610.36  4999.6  609.85  5010.0  608.37  5015.0  608.34
  5015.2  607.84  5018.7  607.84  5019.0  608.34  5022.1  609.06  5030.7  609.73
  5062.0  608.91  5163.8  611.09  5294.1  615.68  5391.5  619.97  5396.5  619.20
  5404.0  619.65  5412.6  619.93  5454.4  621.33  5514.5  625.18  5526.8  625.09
#Mann=6,-1,0
  4587.5   0.035       0  4900.5    0.07       0  5015.0    0.05       0
  5019.0    0.07       0  5404.0   0.045       0  5412.6    0.07       0
Bank Sta=5015,5019
Exp/Cntr=0.3,0.1

Type RM Length L Ch R = 1,1977,264,264,264
BEGIN DESCRIPTION:
J21867
END DESCRIPTION:
XS GIS Cut Line= 4
      2253686.73     13757974.72      2253429.81     13757710.86
      2253145.09     13757592.81      2252913.53     13757610.09
#Sta/Elev= 30
  4573.9  616.98  4631.4  616.43  4760.7  612.99  4850.8  609.57  4921.5  606.10
  4990.7  604.86  4994.4  603.47  4994.6  602.97  4998.1  602.97  4998.4  603.47
  5001.8  603.51  5012.3  605.35  5025.7  604.64  5044.1  605.14  5049.5  604.60
  5073.4  605.51  5126.6  605.26  5155.9  606.59  5163.9  607.61  5196.4  608.17
  5253.0  610.70  5290.6  613.11  5300.6  612.90  5330.7  613.76  5340.7  614.24
  5351.4  615.47  5400.9  617.66  5471.1  618.23  5481.3  618.76  5482.6  618.93
#Mann=5,-1,0
  4573.9   0.035       0  4760.7    0.07       0  4994.4    0.05       0
  4998.4    0.07       0  5481.3   0.045       0
Bank Sta=4994.4,4998.4
Exp/Cntr=0.3,0.1

Type RM Length L Ch R = 1,1713,315,315,315
BEGIN DESCRIPTION:
J21866
END DESCRIPTION:
XS GIS Cut Line= 4
      2253707.59     13757940.03      2253558.28     13757547.67
      2253297.87     13757367.11      2252790.91     13757446.98
#Sta/Elev= 30
  4467.0  616.15  4579.5  613.51  4683.1  609.78  4697.1  609.94  4713.2  608.57
  4782.7  606.24  4868.3  602.02  4949.2  601.00  4970.2  599.65  4976.3  600.68
  4985.0  600.94  5006.0  600.27  5012.5  598.85  5018.8  598.77  5019.1  598.27
  5022.6  598.27  5022.8  598.77  5026.9  599.99  5035.7  600.84  5199.9  602.58
  5215.1  603.60  5227.1  603.18  5267.3  603.90  5347.0  606.99  5388.8  607.30
  5500.2  610.45  5530.5  609.69  5674.7  611.35  5695.1  610.86  5716.9  610.26
#Mann=6,-1,0
  4467.0   0.035       0  4579.5    0.07       0  5018.8    0.05       0
  5022.8    0.07       0  5215.1   0.045       0  5695.1    0.07       0
Bank Sta=5018.8,5022.8
Exp/Cntr=0.3,0.1

Type RM Length L Ch R = 1,1398,181,181,181
BEGIN DESCRIPTION:
YOUNGS TRIBUTARY 4 2 2.0
END DESCRIPTION:
XS GIS Cut Line= 3
      2253724.99     13757824.96      2253625.00     13757225.00
      2253175.02     13756625.03
#Sta/Elev= 30
  4391.3  613.42  4533.2  608.73  4573.7  606.24  4624.4  604.49  4723.3  599.48
  4784.1  597.48  4959.0  596.24  4971.7  596.82  5006.8  596.04  5027.7  594.90
  5049.5  595.52  5200.5  595.40  5227.7  595.56  5256.8  594.38  5275.7  594.31
  5275.9  593.81  5279.4  593.81  5279.7  594.31  5327.7  595.48  5336.0  596.37
  5363.1  595.66  5442.2  597.87  5463.1  599.29  5471.4  598.46  5492.2  598.76
  5592.2  601.49  5606.8  602.59  5642.2  602.46  5727.7  605.99  5749.5  606.28
#Mann=4,-1,0
  4391.3    0.07       0  5200.5   0.045       0  5275.7    0.05       0
  5279.7   0.045       0
Bank Sta=5275.7,5279.7
Exp/Cntr=0.3,0.1

Type RM Length L Ch R = 1,1217,248,248,248
BEGIN DESCRIPTION:
J21865
END DESCRIPTION:
XS GIS Cut Line= 3
      2253877.72     13757686.51      2253766.62     13757058.09
      2253305.49     13756569.23
#Sta/Elev= 30
  4481.0  609.53  4513.0  608.49  4675.5  600.98  4817.7  596.15  4866.7  594.97
  4871.7  594.49  4888.7  594.59  4898.9  593.84  4980.0  593.05  5004.7  593.37
  5153.6  593.98  5178.9  593.76  5205.2  592.62  5205.5  592.12  5209.0  592.12
  5209.2  592.62  5228.7  594.45  5256.2  593.42  5313.6  593.19  5362.0  595.37
  5377.2  594.86  5387.8  595.06  5469.0  597.81  5483.1  598.92  5497.3  598.16
  5632.0  603.32  5645.8  603.09  5752.2  607.03  5773.2  606.94  5791.2  607.56
#Mann=7,-1,0
  4481.0    0.07       0  5004.7   0.035       0  5153.6    0.07       0
  5205.2    0.05       0  5209.2    0.07       0  5256.2   0.035       0
  5387.8   0.045       0
Bank Sta=5205.2,5209.2
Exp/Cntr=0.3,0.1

Type RM Length L Ch R = 1,969,218,218,218
BEGIN DESCRIPTION:
YOUNGS TRIBUTARY 4 2 1.0
END DESCRIPTION:
XS GIS Cut Line= 3
      2253975.00     13757624.96      2253975.00     13757025.00
      2253424.97     13756524.98
#Sta/Elev= 30
  4399.8  607.33  4459.8  605.47  4569.8  601.00  4723.5  596.20  4803.5  594.72
  4899.8  592.26  5011.6  590.46  5011.9  589.96  5015.4  589.96  5015.6  590.46
  5155.5  592.33  5247.4  591.73  5275.8  592.75  5290.0  592.27  5306.7  592.68
  5346.7  595.11  5360.9  594.52  5375.1  594.80  5408.6  596.34  5438.6  597.43
  5467.0  599.56  5488.0  599.22  5516.4  600.93  5587.3  604.05  5594.4  604.94
  5629.9  605.27  5665.0  607.20  5700.8  608.46  5715.0  609.59  5743.1  609.14
#Mann=7,-1,0
  4399.8    0.07       0  4723.5   0.045       0  4803.5    0.07       0
  5011.6    0.05       0  5015.6    0.07       0  5306.7   0.035       0
  5408.6   0.045       0
Bank Sta=5011.6,5015.6
Exp/Cntr=0.3,0.1

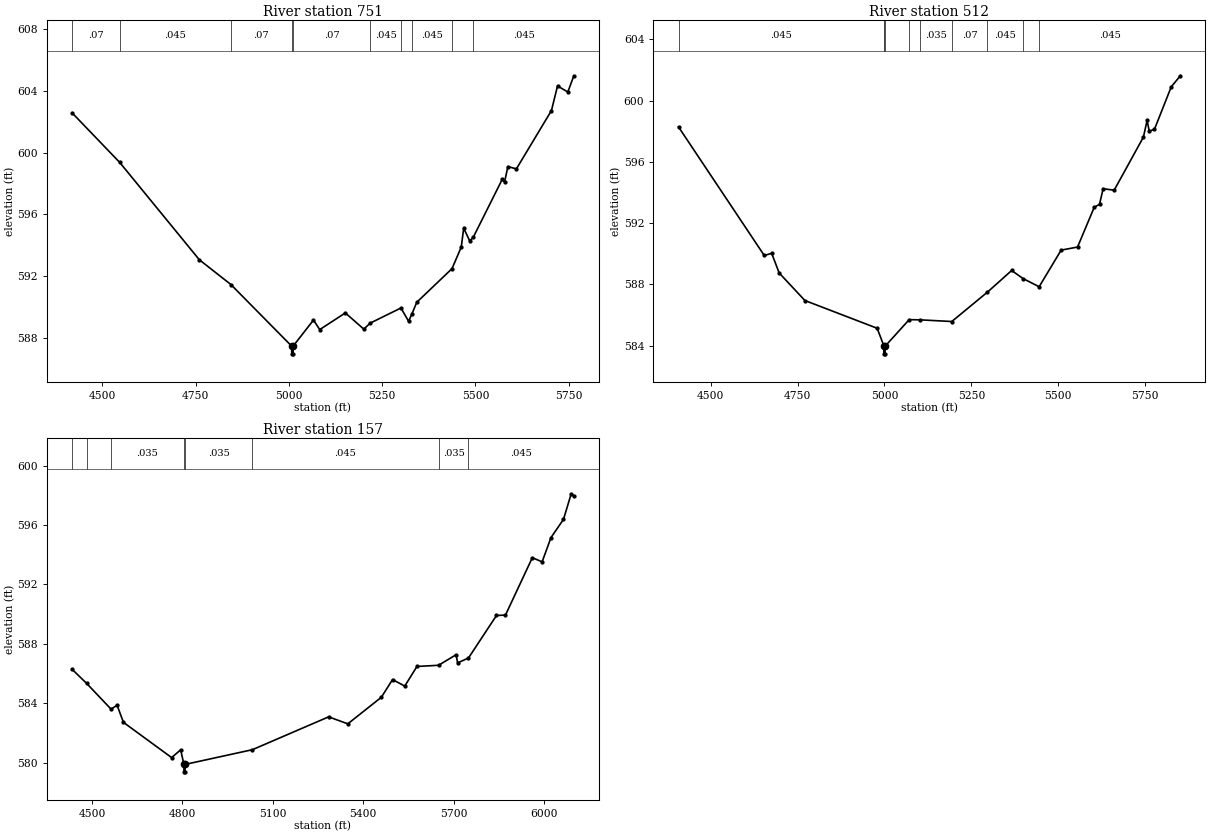
Type RM Length L Ch R = 1,751,239,239,239
BEGIN DESCRIPTION:
J21864
END DESCRIPTION:
XS GIS Cut Line= 4
      2254120.78     13757488.67      2254207.59     13757082.39
      2254127.73     13756821.97      2253549.40     13756510.30
#Sta/Elev= 30
  4419.0  602.57  4546.6  599.36  4760.2  593.05  4844.6  591.45  5007.5  587.46
  5007.8  586.96  5011.3  586.96  5011.5  587.46  5066.0  589.15  5082.7  588.53
  5151.4  589.61  5200.9  588.56  5218.0  588.95  5300.4  589.93  5320.9  589.07
  5329.9  589.55  5342.8  590.30  5437.3  592.48  5462.1  593.88  5468.5  595.10
  5484.8  594.27  5494.2  594.51  5572.4  598.29  5578.0  598.08  5587.0  599.09
  5609.8  598.94  5703.8  602.72  5720.0  604.31  5747.6  603.92  5763.8  604.97
#Mann=10,-1,0
  4419.0    0.07       0  4546.6   0.045       0  4844.6    0.07       0
  5007.5    0.05       0  5011.5    0.07       0  5218.0   0.045       0
  5300.4    0.07       0  5329.9   0.045       0  5437.3    0.07       0
  5494.2   0.045       0
Bank Sta=5007.5,5011.5
Exp/Cntr=0.3,0.1

Type RM Length L Ch R = 1,512,355,355,355
BEGIN DESCRIPTION:
J21863
END DESCRIPTION:
XS GIS Cut Line= 4
      2254224.93     13757353.26      2254426.34     13757012.95
      2254336.06     13756728.22      2253624.24     13756492.11
#Sta/Elev= 30
  4407.3  598.28  4654.0  589.89  4675.4  590.03  4696.9  588.75  4771.0  586.95
  4978.9  585.14  4997.2  584.05  4997.9  583.97  4998.2  583.47  5001.7  583.47
  5001.9  583.97  5071.0  585.70  5101.6  585.69  5193.7  585.58  5296.4  587.50
  5366.0  588.91  5399.1  588.38  5445.1  587.85  5508.4  590.24  5555.6  590.44
  5603.5  593.03  5618.8  593.23  5629.3  594.25  5661.0  594.15  5745.2  597.62
  5755.8  598.71  5761.9  598.01  5776.8  598.12  5825.3  600.90  5851.4  601.62
#Mann=10,-1,0
  4407.3   0.045       0  4997.2   0.035       0  4997.9   0.035       0
  5001.9   0.035       0  5071.0   0.045       0  5101.6   0.035       0
  5193.7    0.07       0  5296.4   0.045       0  5399.1    0.07       0
  5445.1   0.045       0
Bank Sta=4997.9,5001.9
Exp/Cntr=0.3,0.1

Type RM Length L Ch R = 1,157,0,0,0
BEGIN DESCRIPTION:
J21862
END DESCRIPTION:
XS GIS Cut Line= 5
      2254499.24     13757356.72      2254731.90     13757002.53
      2254610.37     13756759.47      2254447.17     13756606.70
      2253711.04     13756488.64
#Sta/Elev= 30
  4434.2  586.29  4482.1  585.35  4563.5  583.61  4583.6  583.87  4604.6  582.72
  4764.4  580.35  4794.5  580.87  4805.2  579.89  4805.4  579.39  4808.9  579.39
  4809.2  579.89  5032.4  580.88  5285.4  583.09  5348.9  582.62  5460.3  584.41
  5497.3  585.60  5537.8  585.16  5578.3  586.48  5650.0  586.56  5708.1  587.27
  5713.2  586.72  5749.2  587.05  5842.1  589.91  5872.0  589.94  5961.0  593.80
  5993.5  593.52  6022.9  595.15  6064.4  596.38  6090.0  598.10  6098.8  597.94
#Mann=8,-1,0
  4434.2   0.045       0  4482.1    0.07       0  4563.5   0.035       0
  4805.2   0.035       0  4809.2   0.035       0  5032.4   0.045       0
  5650.0   0.035       0  5749.2   0.045       0
Bank Sta=4805.2,4809.2
Exp/Cntr=0.3,0.1

Chan Stop Cuts=-1