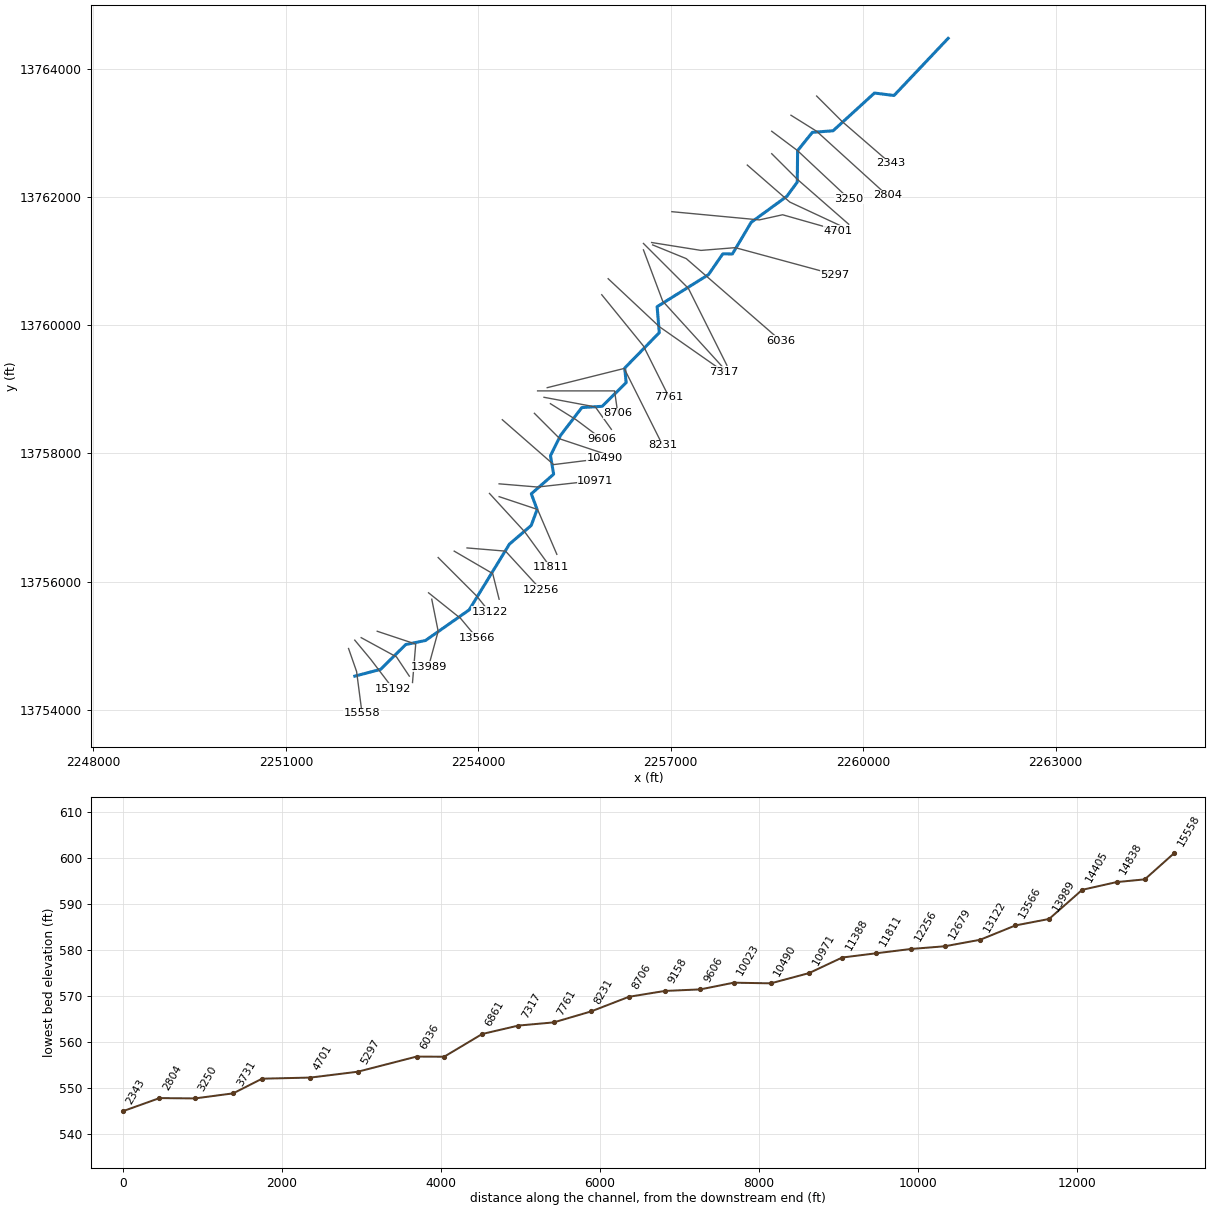
--- YOUNGS TRIBUTARY 4.prj (project) ---

Proj Title=YOUNGS TRIBUTARY 4 Base Level Engineering
Current Plan=p01
Default Exp/Contr=0.3,0.1
English Units
Geom File=g01
Flow File=f01
Plan File=p01
Y Axis Title=Elevation
X Axis Title(PF)=Main Channel Distance
X Axis Title(XS)=Station
BEGIN DESCRIPTION:
YOUNGS TRIBUTARY 4
END DESCRIPTION:
DSS Export Rating Curves= 0
DSS Export Rating Curve Sorted= 0
DSS Export Volume Flow Curves= 0
DXF OffsetX= 0
DXF OffsetY= 0
DXF ScaleX= 1
DXF ScaleY= 10

--- YOUNGS TRIBUTARY 4.p01 (plan) ---

Plan Title=Multiple Run
Short Identifier=Multiple
Geom File=g01
Flow File=f01
Subcritical Flow
K Sum by GR= 0
Std Step Tol= 0.01
Critical Tol= 0.01
Num of Std Step Trials= 20
Max Error Tol= 0.3
Flow Tol Ratio= 0.001
Split Flow NTrial= 30
Split Flow Tol= 0.02
Split Flow Ratio= 0.02
Log Output Level= 0
Friction Slope Method= 1
Unsteady Friction Slope Method= 2
Unsteady Bridges Friction Slope Method= 1
Parabolic Critical Depth
Global Vel Dist=  1 , 1 , 1
Global Log Level= 0
CheckData=True
Encroach Param= -1, 0, 0, 0
BEGIN DESCRIPTION:
Multiple Run
END DESCRIPTION:

--- YOUNGS TRIBUTARY 4.f01 (steady flow) ---

Flow Title=Multiple
Number of Profiles=7
Profile Names=10-year,25-year,50-year,1pct_min,100-year,1pct_plu,500-year
River Rch & RM= YOUNGS TRIBUTARY,Reach-1,15558
     617     993    1332     865    1725    3442    2866
River Rch & RM= YOUNGS TRIBUTARY,Reach-1,11388
     641    1032    1384     899    1793    3578    2977
River Rch & RM= YOUNGS TRIBUTARY,Reach-1,10490
    1113    1839    2509    1652    3296    6575    5635
River Rch & RM= YOUNGS TRIBUTARY,Reach-1,6861
    1481    2481    3417    2269    4527    9033    7878
River Rch & RM= YOUNGS TRIBUTARY,Reach-1,5297
    1724    2905    4015    2675    5337   10649    9346
River Rch & RM= YOUNGS TRIBUTARY,Reach-1,939
    1730    2915    4027    2682    5351   10677    9364
Boundary for River Rch & Prof#=YOUNGS TRIBUTARY,Reach-1,1
Up Type=0
Dn Type=3
Dn Slope=0.005
Boundary for River Rch & Prof#=YOUNGS TRIBUTARY,Reach-1,2
Up Type=0
Dn Type=3
Dn Slope=0.005
Boundary for River Rch & Prof#=YOUNGS TRIBUTARY,Reach-1,3
Up Type=0
Dn Type=3
Dn Slope=0.005
Boundary for River Rch & Prof#=YOUNGS TRIBUTARY,Reach-1,4
Up Type=0
Dn Type=3
Dn Slope=0.005
Boundary for River Rch & Prof#=YOUNGS TRIBUTARY,Reach-1,5
Up Type=0
Dn Type=3
Dn Slope=0.005
Boundary for River Rch & Prof#=YOUNGS TRIBUTARY,Reach-1,6
Up Type=0
Dn Type=3
Dn Slope=0.005
Boundary for River Rch & Prof#=YOUNGS TRIBUTARY,Reach-1,7
Up Type=0
Dn Type=3
Dn Slope=0.005

--- YOUNGS TRIBUTARY 4.g01 (geometry) ---

Geom Title=Existing Conditions
Program Version=4.10

River Reach=YOUNGS TRIBUTARY,Reach-1
Reach XY= 30
        2252075.       13754525.      2252477.42     13754630.54
      2252868.93     13755017.51      2253177.29     13755080.85
      2253858.36     13755558.32      2254485.76      13756584.7
        2254825.       13756875.       2254917.5       13757125.
      2254826.96     13757369.11        2255175.       13757675.
      2255125.75     13757964.32      2255283.02     13758281.34
        2255615.     13758714.93      2255931.67      13758734.3
      2256305.59     13759104.87      2256282.76     13759331.17
      2256821.91     13759883.31      2256788.37     13760288.32
      2257588.57     13760788.47      2257811.76     13761111.88
      2257961.88     13761110.98      2258254.61     13761605.16
      2258808.35     13762008.33      2258972.94     13762230.85
      2258978.34     13762723.28      2259208.23     13763008.57
      2259531.19     13763032.81      2260176.73     13763621.69
      2260481.06     13763583.14        2261325.       13764475.

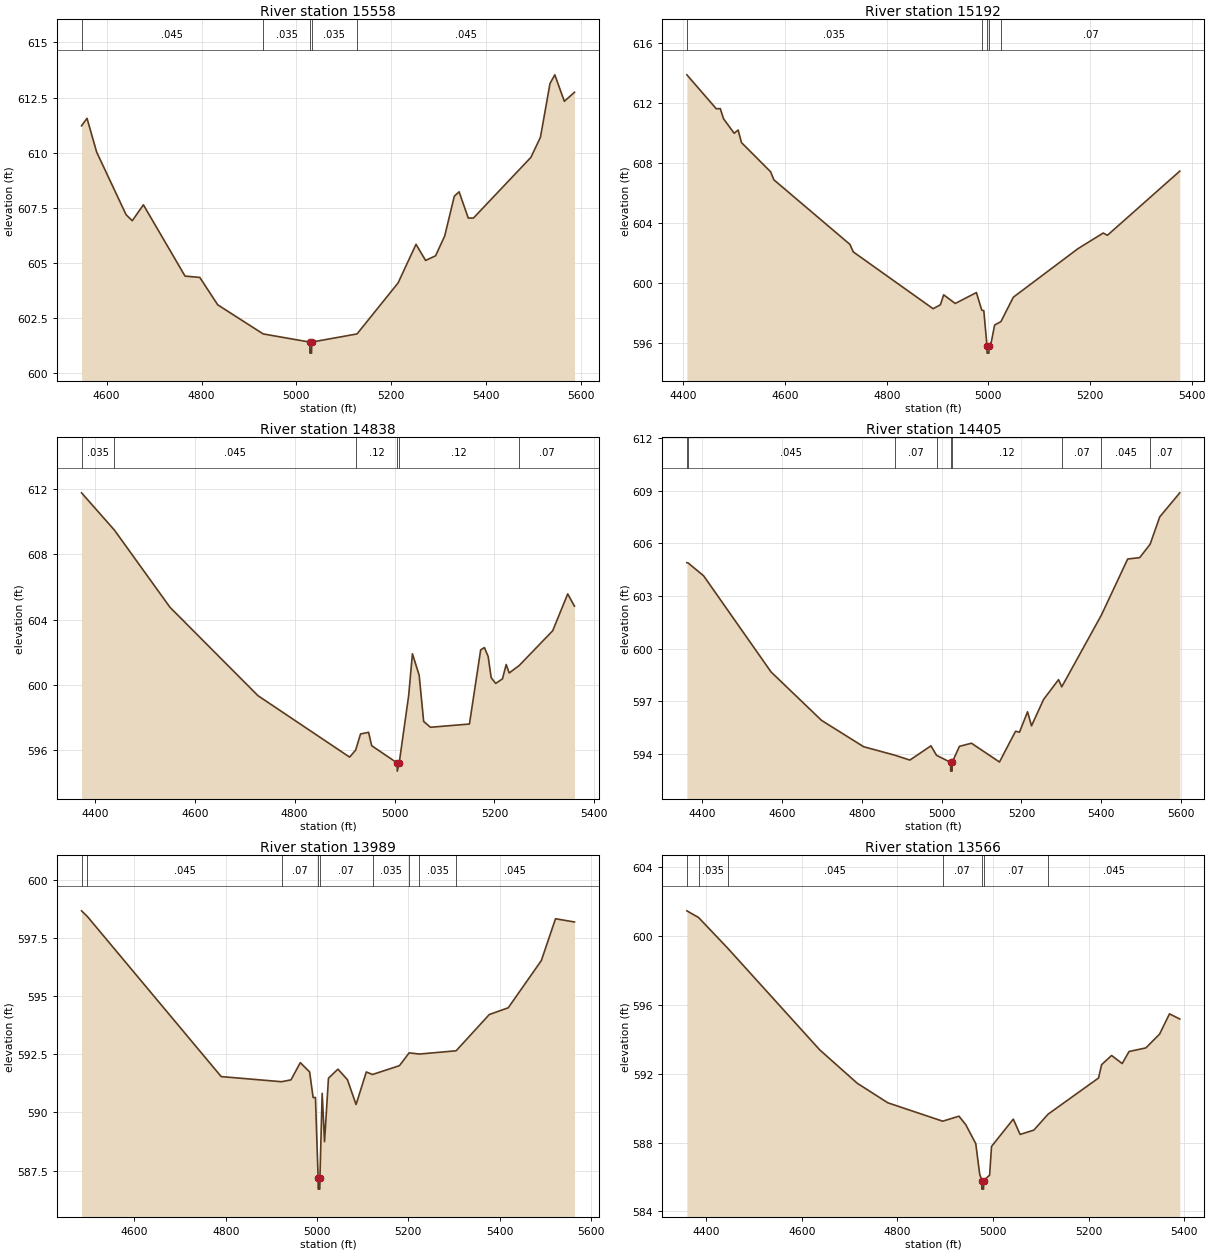
Type RM Length L Ch R = 1 ,15558   ,366,366,366
BEGIN DESCRIPTION:
J21861
END DESCRIPTION:
XS GIS Cut Line= 3
      2251978.05     13754955.88      2252103.14     13754597.69
      2252188.41     13753943.93
#Sta/Elev= 30
  4547.2  611.22  4558.7  611.56    4579  610.03  4641.1  607.19  4654.1  606.92
  4677.5  607.64  4765.3  604.41  4796.4  604.35  4834.1  603.11  4929.9  601.79
  5028.2  601.42  5028.4  600.92  5031.9  600.92  5032.2  601.42  5127.7  601.79
  5214.2   604.1    5252  605.85  5272.2  605.12  5293.2  605.33  5312.5  606.23
  5332.7  608.03  5342.8  608.23  5362.1  607.04    5373  607.04  5494.1  609.79
  5514.2   610.7  5534.4  613.14  5544.5  613.53  5564.6  612.33  5585.9  612.74
#Mann= 5 ,-1 , 0
  4547.2    .045       0  4929.9    .035       0  5028.2    .035       0
  5032.2    .035       0  5127.7    .045       0
Bank Sta=5028.2,5032.2
XS Rating Curve= 0 ,0
Exp/Cntr=0.3,0.1

Type RM Length L Ch R = 1 ,15192   ,354,354,354
BEGIN DESCRIPTION:
YOUNGS TRIBUTARY 4 34.0
END DESCRIPTION:
XS GIS Cut Line= 3
      2252074.71      13755086.6      2252324.85      13754785.3
      2252674.97     13754325.03
#Sta/Elev= 30
  4406.8   613.9  4464.7  611.63  4472.5  611.64    4479  610.96  4499.9  609.99
  4507.7  610.21  4514.2  609.37  4571.5  607.42    4578  606.88  4727.7  602.56
  4734.2  602.06  4891.3  598.26  4905.6  598.52  4912.1  599.19  4934.9  598.61
  4976.5  599.34  4987.1  598.16  4991.1  598.13  4997.3  595.79  4997.6  595.29
  5001.1  595.29  5001.3  595.79  5005.6     596  5012.4  597.17  5024.8   597.4
  5049.2  599.03  5176.1  602.27    5226  603.32  5234.3  603.17  5376.7  607.46
#Mann= 5 ,-1 , 0
  4406.8    .035       0  4987.1     .12       0  4997.3     .05       0
  5001.3     .12       0  5024.8     .07       0
Bank Sta=4997.3,5001.3
XS Rating Curve= 0 ,0
Exp/Cntr=0.3,0.1

Type RM Length L Ch R = 1 ,14838   ,433,433,433
BEGIN DESCRIPTION:
YOUNGS TRIBUTARY 4 33.0
END DESCRIPTION:
XS GIS Cut Line= 3
      2252174.96     13755125.02        2252725.       13754825.
        2252925.       13754525.
#Sta/Elev= 30
  4373.2  611.77  4439.1  609.48  4550.3  604.75  4726.4  599.33    4910  595.56
  4922.1  595.99  4931.9  596.98    4948  597.08  4954.2  596.26  5005.3   595.2
  5005.5   594.7  5009.3   595.2  5028.3  599.34  5035.8   601.9  5049.3  600.58
  5058.3  597.75  5071.9  597.39    5150  597.59  5172.5  602.14    5180  602.28
  5187.5  601.73  5193.5  600.43  5202.6  600.08  5216.1  600.36  5223.6  601.24
  5229.6  600.72  5249.7  601.18  5316.7  603.31  5346.8  605.57  5360.3  604.82
#Mann= 6 ,-1 , 0
  4373.2    .035       0  4439.1    .045       0  4922.1     .12       0
  5005.3     .05       0  5009.3     .12       0  5249.7     .07       0
Bank Sta=5005.3,5009.3
XS Rating Curve= 0 ,0
Exp/Cntr=0.3,0.1

Type RM Length L Ch R = 1 ,14405   ,416,416,416
BEGIN DESCRIPTION:
YOUNGS TRIBUTARY 4 32.0
END DESCRIPTION:
XS GIS Cut Line= 3
      2252425.04     13755224.99        2253025.       13755025.
        2252975.     13754424.99
#Sta/Elev= 30
  4362.1  604.89    4365  604.88  4404.2  604.14  4572.9  598.67  4699.4  595.91
  4804.8  594.41  4882.5  593.93  4920.7  593.65  4973.4  594.46  4987.4  593.92
  5022.6  593.52  5022.9  593.02  5026.4  593.02  5026.6  593.52  5044.7  594.43
  5074.8  594.61    5145  593.54  5185.2  595.29  5195.2  595.24  5215.3   596.4
  5225.3   595.6  5255.4   597.1    5293  598.23    5301  597.82  5400.1   601.9
  5466.1   605.1  5496.2  605.18  5522.3  605.94  5546.4   607.5  5596.6  608.87
#Mann= 9 ,-1 , 0
  4362.1    .035       0    4365    .045       0  4882.5     .07       0
  4987.4     .12       0  5022.6     .05       0  5026.6     .12       0
    5301     .07       0  5400.1    .045       0  5522.3     .07       0
Bank Sta=5022.6,5026.6
XS Rating Curve= 0 ,0
Exp/Cntr=0.3,0.1

Type RM Length L Ch R = 1 ,13989   ,423,423,423
BEGIN DESCRIPTION:
YOUNGS TRIBUTARY 4 31.0
END DESCRIPTION:
XS GIS Cut Line= 3
        2253275.     13755725.01        2253375.       13755225.
        2253225.       13754675.
#Sta/Elev= 30
  4484.1  598.67  4497.1  598.42  4790.1  591.54  4922.5  591.32    4943   591.4
  4963.4  592.14  4983.8  591.74  4991.5  590.64  4996.6  590.64  5002.4   587.2
  5002.6   586.7  5006.1   586.7  5006.4   587.2  5011.3  590.82  5016.5  588.74
  5025.1  591.47  5045.8  591.86  5066.6  591.41  5085.6  590.34    5108  591.74
  5121.6  591.63  5180.6  592.01  5201.9  592.56  5224.4  592.51  5304.8  592.65
  5377.5  594.21    5419   594.5  5491.5  596.53  5522.6  598.33  5564.1  598.19
#Mann= 9 ,-1 , 0
  4484.1    .035       0  4497.1    .045       0  4922.5     .07       0
  5002.4     .05       0  5006.4     .07       0  5121.6    .035       0
  5201.9    .045       0  5224.4    .035       0  5304.8    .045       0
Bank Sta=5002.4,5006.4
XS Rating Curve= 0 ,0
Exp/Cntr=0.3,0.1

Type RM Length L Ch R = 1 ,13566   ,444,444,444
BEGIN DESCRIPTION:
YOUNGS TRIBUTARY 4 30.0
END DESCRIPTION:
XS GIS Cut Line= 3
      2253225.04     13755824.97        2253725.       13755425.
      2253975.01     13755124.98
#Sta/Elev= 30
  4359.7  601.48  4384.2  601.09  4444.7  599.32  4637.4   593.4  4715.8  591.46
  4779.9  590.32  4894.7  589.25  4928.7  589.54  4943.1  589.04  4963.9  587.94
    4972  586.18  4976.4   585.8  4976.6   585.3  4980.1   585.3  4980.4   585.8
  4992.8  586.11  4996.8  587.78  5042.3  589.37  5056.6  588.48  5085.2  588.73
  5115.2  589.66  5220.6  591.76  5227.1  592.54  5247.9  593.07  5270.1   592.6
  5284.4   593.3  5319.5  593.51  5348.2  594.31    5369  595.49  5390.5  595.19
#Mann= 7 ,-1 , 0
  4359.7    .045       0  4384.2    .035       0  4444.7    .045       0
  4894.7     .07       0  4976.4     .05       0  4980.4     .07       0
  5115.2    .045       0
Bank Sta=4976.4,4980.4
XS Rating Curve= 0 ,0
Exp/Cntr=0.3,0.1

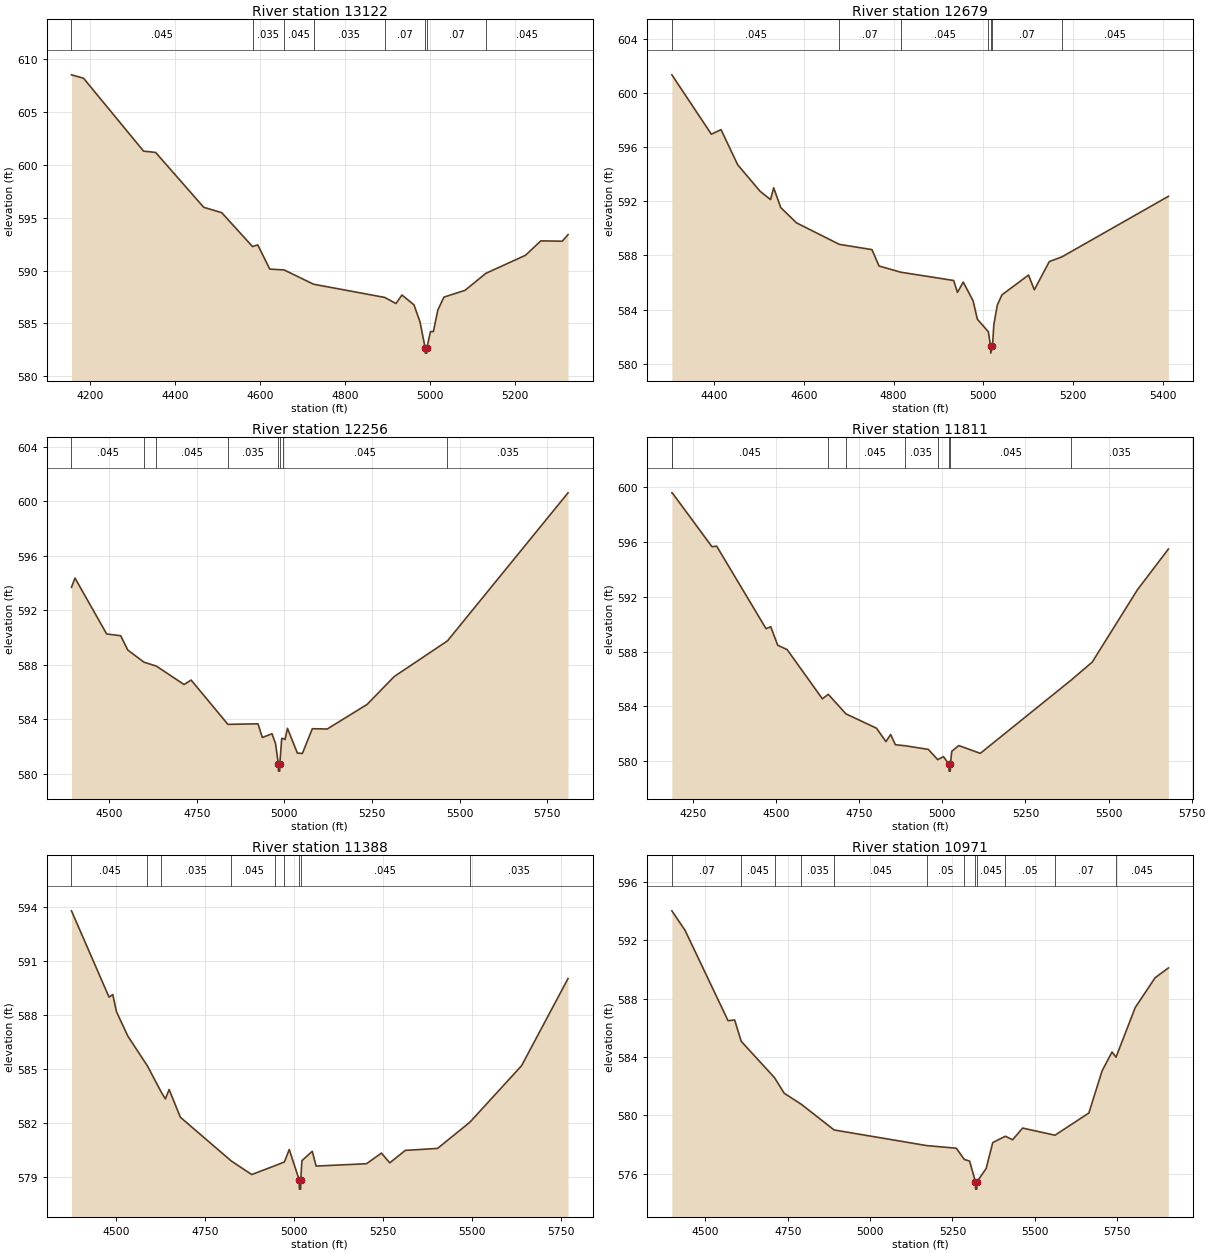
Type RM Length L Ch R = 1 ,13122   ,443,443,443
BEGIN DESCRIPTION:
YOUNGS TRIBUTARY 4 29.0
END DESCRIPTION:
XS GIS Cut Line= 3
      2253374.98     13756375.02        2253975.       13755775.
      2254174.99     13755525.01
#Sta/Elev= 30
  4156.5  608.52  4184.8   608.2  4326.2   601.3  4354.5  601.18  4467.7  595.99
  4510.1  595.48  4582.7  592.27  4594.9  592.43  4623.2  590.14  4657.1  590.06
  4726.2  588.71  4893.7  587.46  4920.2  586.88  4934.3  587.69  4962.6  586.76
  4976.8  585.15  4988.9  582.69  4989.2  582.19  4992.7  582.19  4992.9  582.69
  5001.5  584.23  5008.3  584.23  5018.7  586.26  5033.1  587.49  5082.7  588.13
  5131.9  589.74  5225.2  591.45  5261.2  592.81  5311.6  592.78  5325.2   593.4
#Mann= 8 ,-1 , 0
  4156.5    .045       0  4582.7    .035       0  4657.1    .045       0
  4726.2    .035       0  4893.7     .07       0  4988.9     .05       0
  4992.9     .07       0  5131.9    .045       0
Bank Sta=4988.9,4992.9
XS Rating Curve= 0 ,0
Exp/Cntr=0.3,0.1

Type RM Length L Ch R = 1 ,12679   ,423,423,423
BEGIN DESCRIPTION:
YOUNGS TRIBUTARY 4 28.0
END DESCRIPTION:
XS GIS Cut Line= 3
        2253625.       13756475.        2254225.       13756125.
      2254324.99     13755725.03
#Sta/Elev= 30
  4305.6  601.35  4393.7  596.96  4415.2   597.3  4452.4   594.7  4502.4  592.74
  4525.6  592.13  4532.6     593  4548.3  591.54  4583.4  590.41  4678.9  588.82
  4751.7  588.43  4767.4  587.22    4816  586.76  4933.7  586.15  4942.3  585.27
  4955.2  586.03  4977.1  584.65  4986.6  583.29  5011.1  582.36  5016.3  581.28
  5016.5  580.78  5020.3  581.28  5023.4  582.89  5031.1  584.33  5041.5  585.09
  5100.7  586.55  5113.6  585.46  5147.1  587.55  5174.9  587.89  5412.5  592.37
#Mann= 7 ,-1 , 0
  4305.6    .045       0  4678.9     .07       0    4816    .045       0
  5011.1     .07       0  5016.3    .045       0  5020.3     .07       0
  5174.9    .045       0
Bank Sta=5016.3,5020.3
XS Rating Curve= 0 ,0
Exp/Cntr=0.3,0.1

Type RM Length L Ch R = 1 ,12256   ,445,445,445
BEGIN DESCRIPTION:
YOUNGS TRIBUTARY 4 27.0
END DESCRIPTION:
XS GIS Cut Line= 3
      2253825.05       13756525.        2254425.       13756475.
      2254975.02     13755874.98
#Sta/Elev= 30
  4392.8  593.68  4402.8  594.36  4493.1  590.26  4533.2  590.13  4553.3  589.08
  4599.5  588.19  4634.9   587.9  4713.9  586.55  4733.9  586.88  4838.9  583.63
  4924.6  583.67  4937.1  582.67  4964.7  582.94  4974.8  582.21  4982.8   580.7
    4983   580.2  4986.5   580.2  4986.8   580.7  4992.3   582.6  4995.2   582.6
  5001.9  582.52  5008.7  583.34  5037.1  581.52  5051.3   581.5  5079.6  583.31
  5122.2  583.29  5235.6  585.09  5313.3  587.14  5464.9  589.75  5808.8  600.61
#Mann= 8 ,-1 , 0
  4392.8    .045       0  4599.5    .035       0  4634.9    .045       0
  4838.9    .035       0  4982.8    .045       0  4986.8    .035       0
  4995.2    .045       0  5464.9    .035       0
Bank Sta=4982.8,4986.8
XS Rating Curve= 0 ,0
Exp/Cntr=0.3,0.1

Type RM Length L Ch R = 1 ,11811   ,423,423,423
BEGIN DESCRIPTION:
YOUNGS TRIBUTARY 4 26.0
END DESCRIPTION:
XS GIS Cut Line= 3
      2254174.98     13757375.02        2254725.       13756775.
      2255124.97     13756225.04
#Sta/Elev= 30
    4186  599.61  4187.2  599.61  4306.6  595.67  4320.8  595.71  4469.4  589.67
  4483.6  589.81  4504.5  588.46  4532.9  588.14  4638.9  584.54  4656.5  584.87
  4709.8  583.44  4801.7  582.39  4830.1  581.41  4844.3  581.93  4858.5  581.18
    4887  581.11  4957.7  580.84  4985.9  580.09  5003.1  580.31    5020  579.75
  5020.2  579.25  5023.7  579.25    5024  579.75  5028.2   580.7  5049.4  581.12
    5114  580.55  5387.4  585.91  5450.9  587.23  5586.9  592.52    5680   595.5
#Mann= 9 ,-1 , 0
    4186     .07       0  4187.2    .045       0  4656.5    .035       0
  4709.8    .045       0    4887    .035       0  4985.9    .045       0
    5020    .045       0    5024    .045       0  5387.4    .035       0
Bank Sta=5020,5024
XS Rating Curve= 0 ,0
Exp/Cntr=0.3,0.1

Type RM Length L Ch R = 1 ,11388   ,417,417,417
BEGIN DESCRIPTION:
YOUNGS TRIBUTARY 4 25.0
END DESCRIPTION:
XS GIS Cut Line= 3
      2254325.01       13757325.        2254925.       13757125.
      2255224.99     13756425.02
#Sta/Elev= 30
  4375.9  593.79  4481.3     589  4491.8  589.14  4502.4  588.18    4534  586.84
  4589.1  585.18  4627.8  583.73  4639.4  583.35    4650  583.87  4681.6  582.33
  4824.7   579.9  4881.9  579.15  4947.2  579.64  4973.7  579.85  4987.3  580.54
  5015.4  578.84  5015.7  578.34  5019.2  578.34  5019.4  578.84  5022.8  579.92
  5051.9  580.44  5062.7  579.62  5204.2  579.75  5245.9  580.34  5269.5   579.8
    5313  580.49  5403.6   580.6  5494.1  582.05  5639.4  585.19  5769.9  590.03
#Mann= 9 ,-1 , 0
  4375.9    .045       0  4589.1     .07       0  4627.8    .035       0
  4824.7    .045       0  4947.2    .035       0  4973.7    .045       0
  5015.4    .045       0  5019.4    .045       0  5494.1    .035       0
Bank Sta=5015.4,5019.4
XS Rating Curve= 0 ,0
Exp/Cntr=0.3,0.1

Type RM Length L Ch R = 1 ,10971   ,481,481,481
BEGIN DESCRIPTION:
YOUNGS TRIBUTARY 4 24.0
END DESCRIPTION:
XS GIS Cut Line= 3
      2254324.96       13757525.        2254925.       13757475.
      2255825.04       13757575.
#Sta/Elev= 30
  4397.9  594.01  4438.1  592.67  4568.5  586.49  4588.6  586.54  4608.4  585.08
  4709.6  582.59  4739.1  581.52  4791.5  580.76  4890.6  579.01  5171.9  577.94
  5261.6  577.76  5285.9  576.99  5301.9  576.88  5319.8  575.46  5320.1  574.96
  5323.8  574.96  5324.1  575.46  5352.2  576.37  5372.3  578.15  5410.5  578.58
  5432.7  578.34  5462.9  579.14  5561.1  578.65  5664.1  580.17  5704.3  583.06
  5734.5  584.35  5746.5  583.99  5804.9  587.39  5865.3  589.43  5905.6   590.1
#Mann= 12 ,-1 , 0
  4397.9     .07       0  4608.4    .045       0  4709.6     .07       0
  4791.5    .035       0  4890.6    .045       0  5171.9     .05       0
  5285.9    .045       0  5319.8    .045       0  5324.1    .045       0
  5410.5     .05       0  5561.1     .07       0  5746.5    .045       0
Bank Sta=5319.8,5324.1
XS Rating Curve= 0 ,0
Exp/Cntr=0.3,0.1

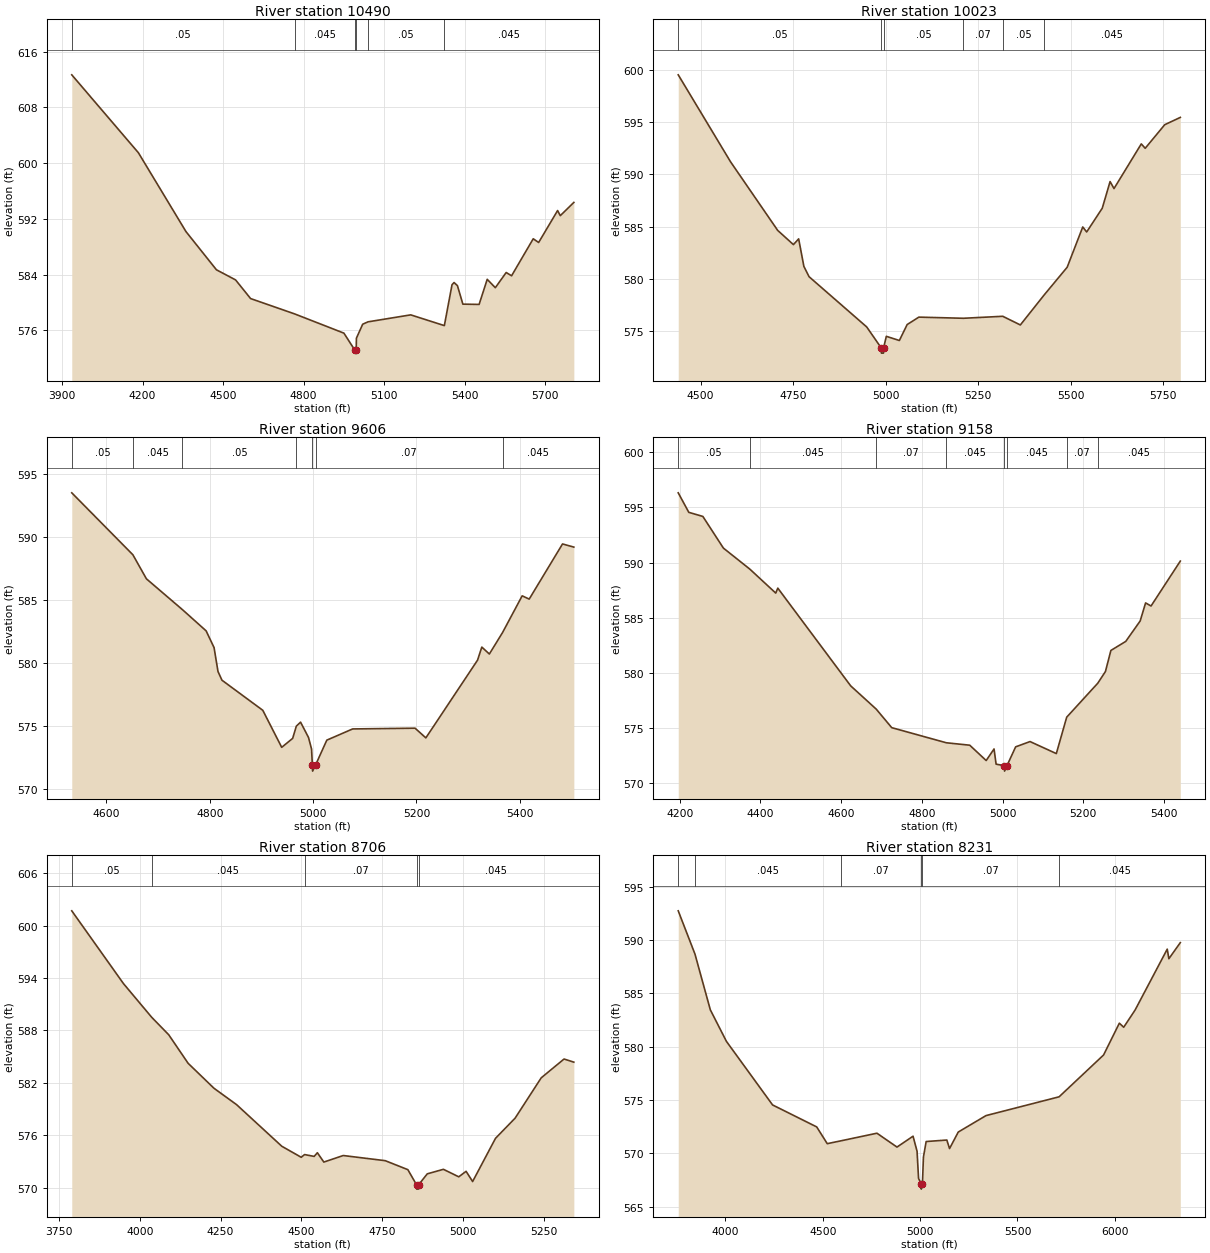
Type RM Length L Ch R = 1 ,10490   ,467,467,467
BEGIN DESCRIPTION:
YOUNGS TRIBUTARY 4 23.0
END DESCRIPTION:
XS GIS Cut Line= 3
      2254375.03     13758524.98        2255175.       13757825.
        2255975.       13757925.
#Sta/Elev= 30
  3936.6  612.68  4184.8  601.49  4361.8  590.18  4475.2   584.7  4546.4  583.25
  4602.4  580.57  4766.9  578.36  4949.7  575.61  4989.3  573.24  4989.8  572.74
  4995.6  573.24  4996.3  574.88  5019.7  576.89  5039.4  577.23  5198.6  578.23
  5323.7  576.69  5352.3  582.56  5359.9  582.87  5372.5  582.42  5392.6  579.77
  5453.1  579.73  5483.3  583.33  5513.5  582.13  5553.9  584.31    5574  583.84
  5654.6  589.15  5674.8  588.62  5745.3   593.2  5755.4  592.47  5805.8  594.37
#Mann= 6 ,-1 , 0
  3936.6     .05       0  4766.9    .045       0  4989.3    .045       0
  4995.6    .045       0  5039.4     .05       0  5323.7    .045       0
Bank Sta=4989.3,4995.6
XS Rating Curve= 0 ,0
Exp/Cntr=0.3,0.1

Type RM Length L Ch R = 1 ,10023   ,417,417,417
BEGIN DESCRIPTION:
YOUNGS TRIBUTARY 4 22.0
END DESCRIPTION:
XS GIS Cut Line= 3
      2254875.01     13758624.99        2255275.       13758225.
      2256024.95     13757975.02
#Sta/Elev= 30
  4439.4  599.55  4580.8  591.21  4708.1  584.64  4750.5  583.28  4764.7  583.83
  4778.8  581.19  4792.9   580.2  4948.5  575.39  4987.7  573.38  4988.2  572.88
  4993.6  572.88  4994.1  573.38  5001.5  574.49  5036.7  574.09  5057.8  575.62
  5089.4  576.33  5209.8  576.22    5316  576.41  5363.5  575.58  5428.2  578.47
    5490  581.11  5532.1  584.97  5542.7  584.49  5584.8  586.77  5605.9  589.32
  5616.5  588.65  5690.2  592.93  5700.8  592.51  5753.5  594.77  5795.6  595.47
#Mann= 6 ,-1 , 0
  4439.4     .05       0  4987.7     .05       0  4994.1     .05       0
  5209.8     .07       0    5316     .05       0  5428.2    .045       0
Bank Sta=4987.7,4994.1
XS Rating Curve= 0 ,0
Exp/Cntr=0.3,0.1

Type RM Length L Ch R = 1 ,9606    ,448,448,448
BEGIN DESCRIPTION:
YOUNGS TRIBUTARY 4 21.0
END DESCRIPTION:
XS GIS Cut Line= 3
      2255124.98     13758775.01        2255525.       13758525.
      2255924.99     13758225.01
#Sta/Elev= 30
  4532.9  593.53  4651.2  588.61  4677.4   586.7  4746.9  584.26  4792.9  582.57
  4808.3  581.24  4815.9  579.34  4823.6  578.65  4902.6  576.26  4939.2  573.32
  4960.4  574.03  4967.5     575  4975.7  575.32  4991.1   574.1    4997  573.18
  4998.5  571.93    4999  571.43  5004.9  571.93  5026.5  573.89  5076.5  574.78
  5197.3  574.84  5218.2  574.07  5318.2  580.24  5326.5  581.28  5341.1  580.73
  5366.7  582.44  5404.6  585.35  5418.2  585.09  5482.7  589.47  5504.6  589.22
#Mann= 7 ,-1 , 0
  4532.9     .05       0  4651.2    .045       0  4746.9     .05       0
  4967.5     .07       0  4998.5     .05       0  5004.9     .07       0
  5366.7    .045       0
Bank Sta=4998.5,5004.9
XS Rating Curve= 0 ,0
Exp/Cntr=0.3,0.1

Type RM Length L Ch R = 1 ,9158    ,452,452,452
BEGIN DESCRIPTION:
YOUNGS TRIBUTARY 4 20.0
END DESCRIPTION:
XS GIS Cut Line= 3
      2255025.04     13758874.99        2255825.       13758725.
      2256074.99     13758375.01
#Sta/Elev= 30
  4196.4  596.32  4222.6  594.55  4257.4  594.18  4308.3  591.31  4373.6  589.41
    4438  587.23  4443.1  587.68  4623.7  578.82    4687  576.71  4725.4  575.03
  4860.7  573.66  4918.7  573.44  4959.4  572.05  4978.9   573.1    4984  571.72
  5004.5  571.59    5005  571.09    5011  571.59  5032.4  573.29  5068.1  573.77
  5133.2  572.68  5158.9  575.98  5235.9  579.06  5254.9  580.12  5268.4  582.03
  5305.2  582.85  5340.9   584.7  5354.4  586.34  5367.9  586.06  5440.4  590.13
#Mann= 8 ,-1 , 0
  4196.4     .05       0  4373.6    .045       0    4687     .07       0
  4860.7    .045       0  5004.5    .045       0    5011    .045       0
  5158.9     .07       0  5235.9    .045       0
Bank Sta=5004.5,5011
XS Rating Curve= 0 ,0
Exp/Cntr=0.3,0.1

Type RM Length L Ch R = 1 ,8706    ,475,475,475
BEGIN DESCRIPTION:
YOUNGS TRIBUTARY 4 19.0
END DESCRIPTION:
XS GIS Cut Line= 3
      2254924.96       13758975.        2256125.       13758975.
        2256175.     13758624.99
#Sta/Elev= 30
  3789.4  601.71  3949.4  593.37    4037   589.5  4089.4  587.51  4149.4  584.24
  4229.4  581.38  4299.4   579.5  4439.4  574.73  4499.4  573.47  4509.8  573.78
  4539.4  573.57  4549.4  573.99  4569.4  572.92  4629.4  573.67  4759.4  573.08
  4829.4  572.05  4856.2  570.32  4856.7  569.82  4862.2  569.82  4862.7  570.32
  4889.4  571.57  4939.4  572.09  4986.9  571.23  5009.6  571.86  5029.8  570.69
  5100.6  575.64  5161.2  577.95    5242  582.57  5312.7  584.73    5343  584.37
#Mann= 5 ,-1 , 0
  3789.4     .05       0    4037    .045       0  4509.8     .07       0
  4856.2    .045       0  4862.7    .045       0
Bank Sta=4856.2,4862.7
XS Rating Curve= 0 ,0
Exp/Cntr=0.3,0.1

Type RM Length L Ch R = 1 ,8231    ,470,470,470
BEGIN DESCRIPTION:
YOUNGS TRIBUTARY 4 18.0
END DESCRIPTION:
XS GIS Cut Line= 3
      2255075.01       13759025.        2256275.       13759325.
      2256875.02     13758124.97
#Sta/Elev= 30
  3757.8  592.73  3843.7  588.68  3922.7  583.45  4005.2   580.5  4242.3  574.54
    4469  572.48  4523.1  570.91  4591.8  571.17  4778.3  571.89  4881.3  570.59
  4963.8  571.61  4984.4   570.2  4992.1  567.65  5005.4  567.15  5005.9  566.65
    5012  567.15  5017.1  569.66  5031.1  571.11  5137.3  571.25  5151.2  570.45
    5196     572  5338.5  573.54  5713.8   575.3  5942.3  579.22  6023.3   582.2
  6045.7  581.82  6104.4  583.44  6269.3  589.14  6277.7  588.24  6336.4  589.75
#Mann= 6 ,-1 , 0
  3757.8     .05       0  3843.7    .045       0  4591.8     .07       0
  5005.4     .05       0    5012     .07       0  5713.8    .045       0
Bank Sta=5005.4,5012
XS Rating Curve= 0 ,0
Exp/Cntr=0.3,0.1

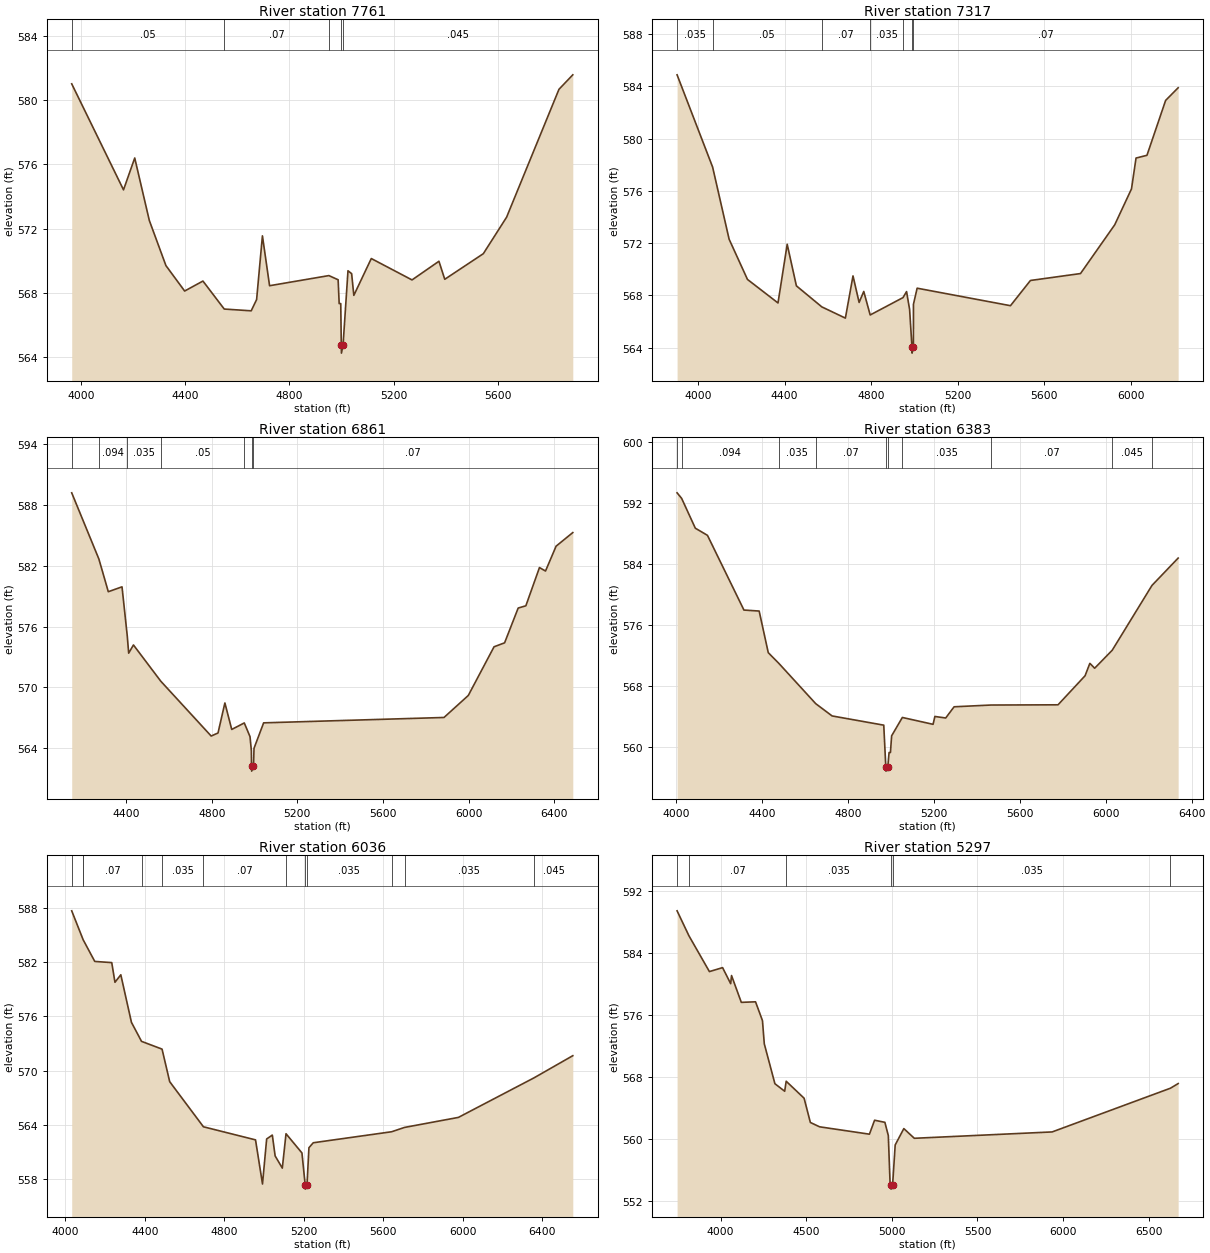
Type RM Length L Ch R = 1 ,7761    ,444,444,444
BEGIN DESCRIPTION:
YOUNGS TRIBUTARY 4 17.0
END DESCRIPTION:
XS GIS Cut Line= 3
        2255925.       13760475.        2256575.       13759675.
        2256975.     13758875.01
#Sta/Elev= 30
  3963.3  581.01  4162.3  574.42  4205.4   576.4  4261.4  572.52  4325.3  569.71
  4397.2  568.13  4467.5  568.75  4549.3  567.01  4652.9   566.9  4673.7   567.6
    4696  571.56  4723.5  568.46  4951.4  569.09  4986.9  568.83  4990.9  567.35
  4996.9  567.35  4999.1  564.77  4999.6  564.27  5005.8  564.77  5024.8  569.39
  5038.8  569.21  5047.2  567.86  5114.3  570.15  5270.8  568.82  5374.2  569.98
  5396.6  568.86  5544.7  570.45  5634.2  572.72  5835.4  580.67  5888.5  581.57
#Mann= 5 ,-1 , 0
  3963.3     .05       0  4549.3     .07       0  4951.4    .045       0
  4999.1    .045       0  5005.8    .045       0
Bank Sta=4999.1,5005.8
XS Rating Curve= 0 ,0
Exp/Cntr=0.3,0.1

Type RM Length L Ch R = 1 ,7317    ,456,456,456
BEGIN DESCRIPTION:
YOUNGS TRIBUTARY 4 16.0
END DESCRIPTION:
XS GIS Cut Line= 3
      2256025.01     13760724.99        2256825.       13759975.
      2257824.97     13759275.02
#Sta/Elev= 30
  3903.2  584.88  4067.5  577.82  4143.8   572.3  4228.7  569.22  4369.9  567.42
  4412.4  571.91  4454.9  568.73  4572.4  567.12  4681.5  566.26  4716.7  569.49
    4745  567.46  4766.5   568.3  4796.2   566.5    4948  567.83  4964.4  568.29
  4978.5  566.92  4989.3  564.08  4989.8  563.58    4996  564.08  4996.3  567.32
  5013.3  568.55  5444.9  567.21  5537.3  569.14  5768.8  569.67    5927   573.4
  6004.6  576.15  6025.6  578.51  6076.1  578.72  6162.4  582.92  6220.4  583.89
#Mann= 7 ,-1 , 0
  3903.2    .035       0  4067.5     .05       0  4572.4     .07       0
  4796.2    .035       0    4948     .07       0  4989.3     .05       0
    4996     .07       0
Bank Sta=4989.3,4996
XS Rating Curve= 0 ,0
Exp/Cntr=0.3,0.1

Type RM Length L Ch R = 1 ,6861    ,478,478,478
BEGIN DESCRIPTION:
YOUNGS TRIBUTARY 4 15.0
END DESCRIPTION:
XS GIS Cut Line= 3
        2256575.     13761175.01        2256875.       13760375.
      2257874.99     13759275.01
#Sta/Elev= 30
  4145.9  589.19  4272.9  582.66  4316.8  579.44  4380.9  579.92  4405.4  575.08
    4412  573.38  4434.3  574.19  4561.9  570.62  4797.4  565.21  4829.4  565.51
  4861.5  568.47  4893.5  565.86  4952.1   566.5  4978.9  565.15  4985.2  563.77
    4986  562.25  4986.5  561.75  4995.1  562.25  4997.6     564  5042.5  566.51
  5885.2  567.04  5998.7  569.21    6119  574.01  6168.3   574.4  6231.8  577.83
  6267.6  578.05  6331.2  581.82  6359.5  581.48  6408.9  583.93  6486.9  585.27
#Mann= 7 ,-1 , 0
  4145.9    .045       0  4272.9    .094       0  4405.4    .035       0
  4561.9     .05       0  4952.1     .07       0    4986     .05       0
  4995.1     .07       0
Bank Sta=4986,4995.1
XS Rating Curve= 0 ,0
Exp/Cntr=0.3,0.1

Type RM Length L Ch R = 1 ,6383    ,347,347,347
BEGIN DESCRIPTION:
YOUNGS TRIBUTARY 4 14.0
END DESCRIPTION:
XS GIS Cut Line= 3
      2256574.99     13761275.01        2257275.       13760575.
        2257875.       13759375.
#Sta/Elev= 30
  4005.7  593.33  4026.9   592.6  4090.6  588.69  4147.1  587.75  4316.8  577.95
  4387.6  577.82    4430  572.36  4480.4  570.92  4650.8  565.67    4727  564.06
  4967.4  562.85    4977  557.32  4977.5  556.82  4986.1  557.32  4992.1  559.26
  4998.5  559.26    5004  561.45  5053.9  563.86  5196.9  562.96  5205.3  563.99
  5255.6  563.79  5294.7  565.26  5466.1  565.49  5778.3  565.52  5904.1  569.33
  5926.4  570.96  5948.8  570.32  6030.5  572.68  6215.4  581.18  6337.3  584.77
#Mann= 10 ,-1 , 0
  4005.7    .045       0  4026.9    .094       0  4480.4    .035       0
  4650.8     .07       0    4977     .05       0  4986.1     .07       0
  5053.9    .035       0  5466.1     .07       0  6030.5    .045       0
  6215.4     .07       0
Bank Sta=4977,4986.1
XS Rating Curve= 0 ,0
Exp/Cntr=0.3,0.1

Type RM Length L Ch R = 1 ,6036    ,739,739,739
BEGIN DESCRIPTION:
YOUNGS TRIBUTARY 4 13.0
END DESCRIPTION:
XS GIS Cut Line= 3
      2256718.51      13761252.2      2257242.42     13761038.36
      2258717.85     13759755.38
#Sta/Elev= 30
  4032.2   587.7  4089.6   584.5  4090.3  584.47  4148.2  582.09  4233.6  581.96
  4249.8  579.78  4279.2  580.61  4332.7  575.34  4383.4  573.23  4486.7  572.37
  4525.2  568.76  4694.9  563.76    4957  562.31  4992.1  557.42    5013  562.41
  5041.5  562.84  5055.7  560.53  5091.8  559.18  5110.4  562.99  5190.6  560.86
  5206.7  557.35  5207.2  556.85  5216.1  557.35  5225.7  561.44  5247.5  561.99
  5641.9  563.21  5706.8  563.69  5977.7   564.8  6358.7  569.19  6553.3  571.64
#Mann= 12 ,-1 , 0
  4032.2    .035       0  4089.6    .094       0  4090.3     .07       0
  4383.4    .094       0  4486.7    .035       0  4694.9     .07       0
  5110.4    .035       0  5206.7     .05       0  5216.1    .035       0
  5641.9     .07       0  5706.8    .035       0  6358.7    .045       0
Bank Sta=5206.7,5216.1
XS Rating Curve= 0 ,0
Exp/Cntr=0.3,0.1

Type RM Length L Ch R = 1 ,5297    ,596,596,596
BEGIN DESCRIPTION:
YOUNGS TRIBUTARY 4 11.0
END DESCRIPTION:
XS GIS Cut Line= 4
       2256702.5     13761289.61      2257472.29     13761166.66
      2258006.86     13761209.43      2259561.27     13760787.44
#Sta/Elev= 30
  3745.8  589.48    3815  586.26  3934.6  581.64  4011.6  582.15  4058.8  580.08
  4063.8  581.13  4120.9  577.67    4204  577.74  4244.5  575.31  4255.1  572.32
  4317.2  567.17  4374.2   566.2    4383  567.49  4487.6   565.3  4524.2  562.17
  4578.2  561.61  4869.2  560.66  4899.3  562.46  4959.4  562.19  4979.5  560.48
  4989.5  554.52  4994.7  554.07  4995.2  553.57  5004.4  554.07  5019.6  559.27
  5070.1  561.38  5131.4  560.13  5936.3  560.95  6627.1  566.59  6672.3  567.19
#Mann= 6 ,-1 , 0
  3745.8    .035       0    3815     .07       0    4383    .035       0
  4994.7    .035       0  5004.4    .035       0  6627.1    .045       0
Bank Sta=4994.7,5004.4
XS Rating Curve= 0 ,0
Exp/Cntr=0.3,0.1

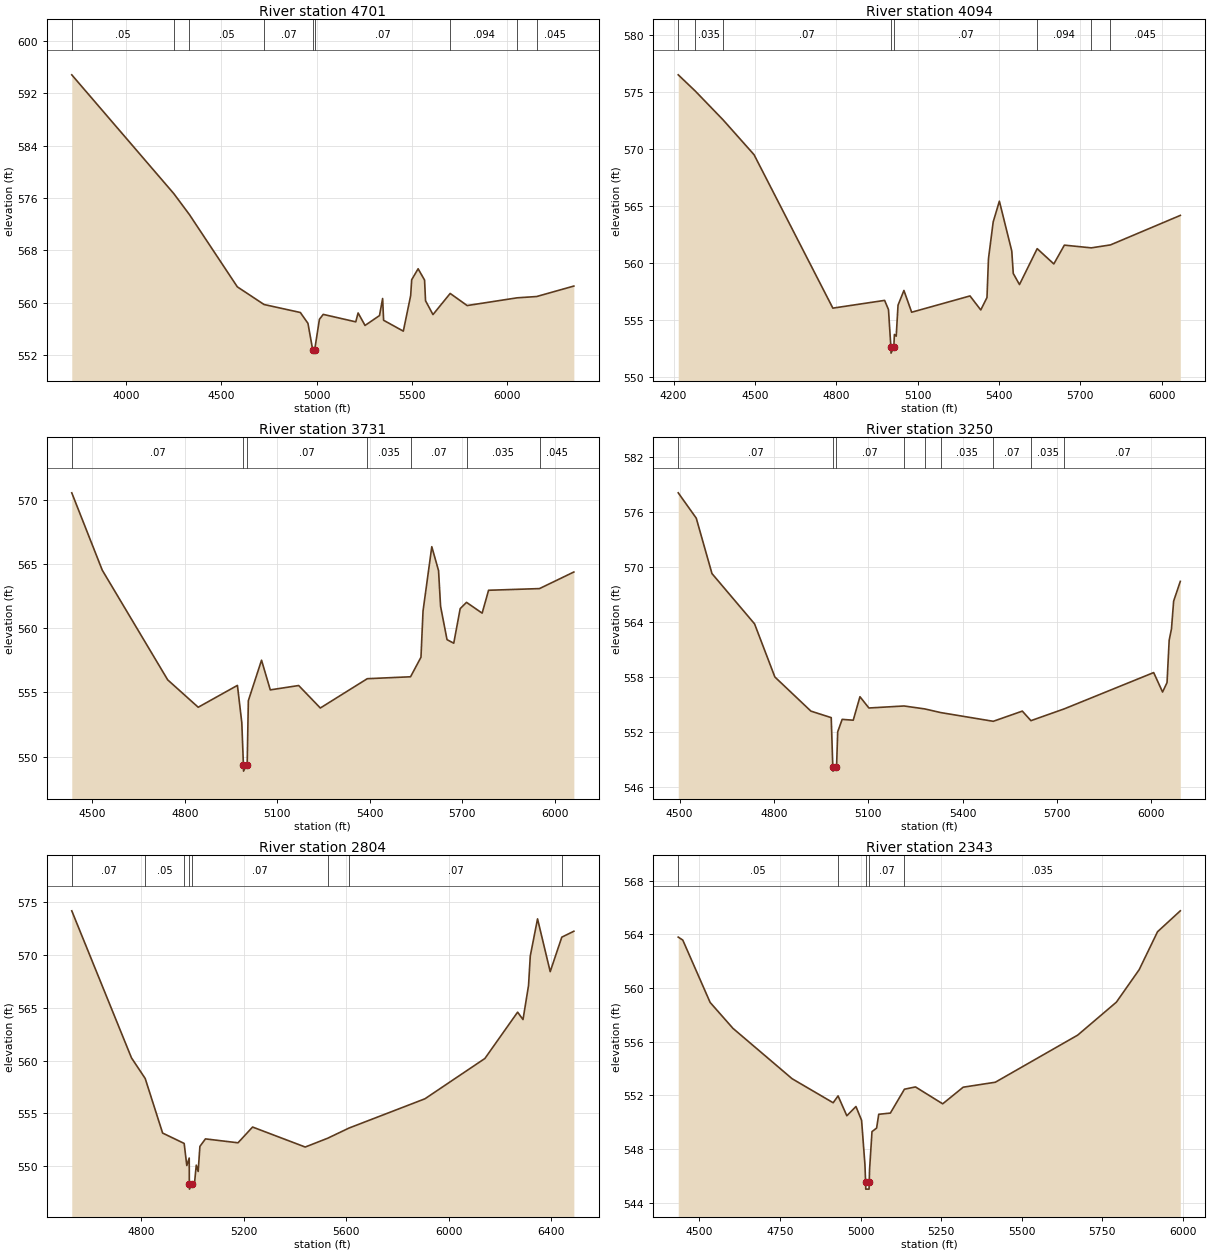
Type RM Length L Ch R = 1 ,4701    ,607,607,607
BEGIN DESCRIPTION:
YOUNGS TRIBUTARY 4 10.0
END DESCRIPTION:
XS GIS Cut Line= 4
      2257017.86     13761770.73      2258381.06     13761642.43
      2258744.57     13761722.61      2259610.28      13761476.8
#Sta/Elev= 30
  3712.3  594.83  4249.6  576.66  4331.3  573.47  4583.3  562.43  4723.9  559.73
  4914.7  558.51  4954.9  556.85  4979.9   552.8  4980.4   552.3  4990.2   552.8
  5015.2  557.47  5035.3  558.22  5206.4  557.08  5218.7  558.44  5255.2  556.53
  5331.3  558.04  5347.7  560.65  5352.9  557.32  5456.6  555.66  5495.3   561.1
  5500.5  563.51  5534.4  565.19  5568.3  563.47  5573.5   560.3  5612.6  558.19
  5703.1  561.42  5792.4  559.57  6054.9  560.75  6158.1  560.95  6353.7  562.55
#Mann= 9 ,-1 , 0
  3712.3     .05       0  4249.6     .07       0  4331.3     .05       0
  4723.9     .07       0  4979.9     .05       0  4990.2     .07       0
  5703.1    .094       0  6054.9    .035       0  6158.1    .045       0
Bank Sta=4979.9,4990.2
XS Rating Curve= 0 ,0
Exp/Cntr=0.3,0.1

Type RM Length L Ch R = 1 ,4094    ,363,363,363
BEGIN DESCRIPTION:
YOUNGS TRIBUTARY 4 9.0
END DESCRIPTION:
XS GIS Cut Line= 3
      2258193.99     13762497.72      2258856.83     13761920.41
      2259737.55      13761509.4
#Sta/Elev= 30
  4217.4  576.49  4279.6  575.08  4383.4  572.52  4496.9  569.48  4787.4  556.01
  4978.2  556.69  4992.5  555.88  5001.4  552.56  5001.9  552.06  5012.1  552.56
  5014.3   553.7    5021  553.55  5027.7  556.27  5049.4  557.56  5077.9  555.65
    5293  557.08  5332.7  555.85  5355.6  556.94  5361.1  560.35  5378.5  563.58
  5401.3   565.4    5447  561.02  5452.5  559.05  5475.4  558.08  5540.7  561.23
    5602  559.89  5640.9  561.54    5740   561.3  5810.9  561.56  6068.3  564.15
#Mann= 8 ,-1 , 0
  4217.4     .07       0  4279.6    .035       0  4383.4     .07       0
  5001.4     .05       0  5012.1     .07       0  5540.7    .094       0
    5740    .035       0  5810.9    .045       0
Bank Sta=5001.4,5012.1
XS Rating Curve= 0 ,0
Exp/Cntr=0.3,0.1

Type RM Length L Ch R = 1 ,3731    ,481,481,481
BEGIN DESCRIPTION:
YOUNGS TRIBUTARY 4 8.0
END DESCRIPTION:
XS GIS Cut Line= 3
      2258574.97     13762675.03        2258975.       13762275.
      2259774.97     13761575.03
#Sta/Elev= 30
  4433.7  570.53  4532.7  564.51  4744.9  555.98  4843.9  553.85  4971.1  555.55
  4985.3  552.65  4990.5  549.38    4991  548.88  5001.2  549.38  5002.7  549.38
  5006.5  554.36  5049.3  557.51  5077.7   555.2  5169.8  555.54    5240  553.79
  5392.3  556.07  5532.7  556.22  5566.5  557.74  5573.2  561.34  5601.6  566.34
  5623.5  564.48  5630.1   561.7    5651  559.11  5672.8  558.83  5693.7  561.52
  5714.2  562.01  5764.9  561.17  5785.8  562.95    5951  563.08  6062.4  564.37
#Mann= 7 ,-1 , 0
  4433.7     .07       0  4990.5     .05       0  5001.2     .07       0
  5392.3    .035       0  5532.7     .07       0  5714.2    .035       0
    5951    .045       0
Bank Sta=4990.5,5001.2
XS Rating Curve= 0 ,0
Exp/Cntr=0.3,0.1

Type RM Length L Ch R = 1 ,3250    ,446,446,446
BEGIN DESCRIPTION:
YOUNGS TRIBUTARY 4 7.0
END DESCRIPTION:
XS GIS Cut Line= 3
      2258574.97     13763025.02        2258975.       13762725.
      2259774.99     13761975.01
#Sta/Elev= 30
  4495.9  578.11  4553.2  575.35  4603.2  569.31  4738.6  563.83  4803.2  558.04
  4917.8  554.32  4982.4  553.61  4987.4  548.28  4987.9  547.78  4998.2  548.28
  4999.4  548.28    5003  552.06  5017.2  553.42  5052.4  553.33  5073.8  555.89
  5102.2  554.66    5214  554.88  5279.8  554.56  5330.7  554.16  5497.7  553.21
  5590.1  554.32  5617.5  553.28  5723.8  554.57  6007.8  558.52  6036.1   556.4
  6050.3  557.43  6057.1  562.05  6064.4  563.28  6071.3  566.31  6092.5  568.46
#Mann= 9 ,-1 , 0
  4495.9     .07       0  4987.4     .05       0  4998.2     .07       0
    5214    .035       0  5279.8     .07       0  5330.7    .035       0
  5497.7     .07       0  5617.5    .035       0  5723.8     .07       0
Bank Sta=4987.4,4998.2
XS Rating Curve= 0 ,0
Exp/Cntr=0.3,0.1

Type RM Length L Ch R = 1 ,2804    ,461,461,461
BEGIN DESCRIPTION:
YOUNGS TRIBUTARY 4 6.0
END DESCRIPTION:
XS GIS Cut Line= 3
      2258874.99       13763275.        2259275.       13763025.
      2260374.99     13762025.01
#Sta/Elev= 30
  4529.1  574.16    4762  560.26  4815.5  558.31  4883.5  553.15  4967.5  552.17
  4977.8  550.08  4987.2  550.79  4987.7  548.35  4988.2  547.85  4998.6  548.35
  5007.9  548.43  5014.7  550.12  5022.1  549.52  5028.9  551.89  5050.5   552.6
  5177.5  552.23  5234.3  553.72  5439.7  551.83  5527.1  552.66  5610.1  553.62
  5906.6  556.39  6140.4   560.2  6268.1  564.58  6289.1  563.88  6310.7   567.1
  6317.5  569.89  6345.8   573.4  6395.2  568.41  6440.4  571.67  6487.4  572.23
#Mann= 8 ,-1 , 0
  4529.1     .07       0  4815.5     .05       0  4967.5     .07       0
  4987.7     .05       0  4998.6     .07       0  5527.1    .035       0
  5610.1     .07       0  6440.4    .035       0
Bank Sta=4987.7,4998.6
XS Rating Curve= 0 ,0
Exp/Cntr=0.3,0.1

Type RM Length L Ch R = 1 ,2343    ,470,470,470
BEGIN DESCRIPTION:
YOUNGS TRIBUTARY 4 5.0
END DESCRIPTION:
XS GIS Cut Line= 3
      2259275.01     13763574.99        2259675.       13763175.
      2260424.96     13762525.03
#Sta/Elev= 30
  4434.3  563.79  4448.4  563.57  4533.3  558.92    4604  556.99  4787.8  553.23
  4915.1  551.44  4930.3  551.95  4957.5  550.47  4985.8  551.16  5003.3  550.13
  5013.7  546.83  5015.8   545.5  5016.3     545  5026.5     545    5027   545.5
    5028  546.43  5035.6  549.29  5049.9  549.55  5056.5  550.58  5092.6  550.67
  5136.3  552.45  5170.5  552.62    5255  551.36  5318.6   552.6  5418.3  552.97
  5673.8  556.48    5794  558.94  5864.7  561.36  5921.7  564.19  5992.4  565.75
#Mann= 5 ,-1 , 0
  4434.3     .05       0  4930.3     .07       0  5015.8     .05       0
    5027     .07       0  5136.3    .035       0
Bank Sta=5015.8,5027
XS Rating Curve= 0 ,0
Exp/Cntr=0.3,0.1