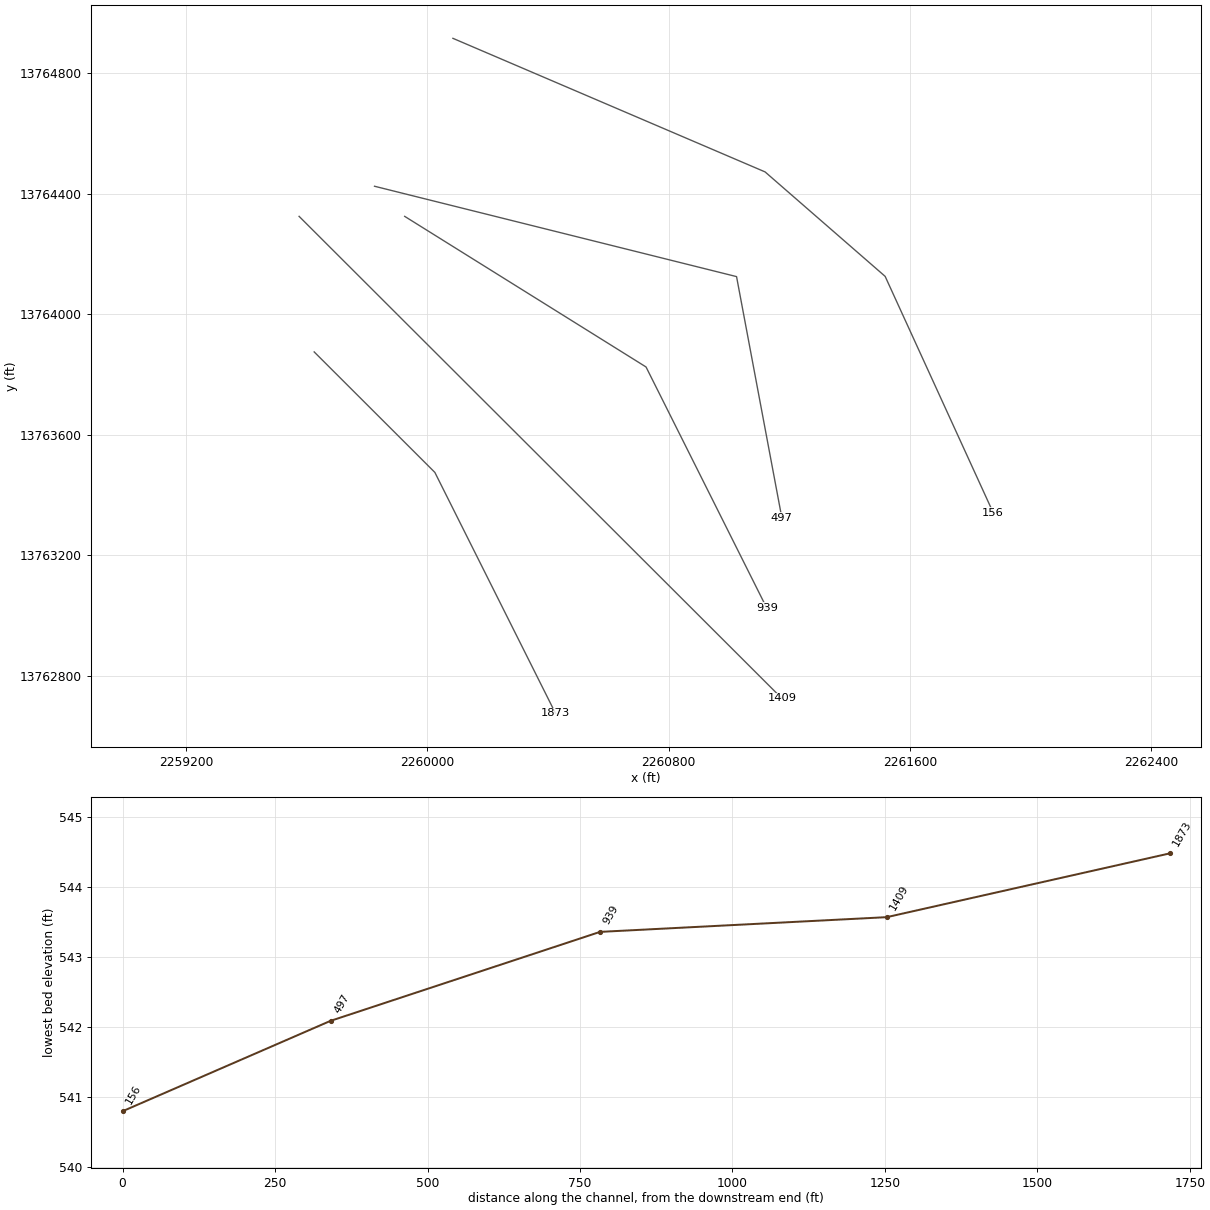
HEC-RAS study YOUNGS TRIBUTARY 4.prj: YOUNGS TRIBUTARY 4 Base Level Engineering

--- YOUNGS TRIBUTARY 4.g01 (geometry) --- (continued)

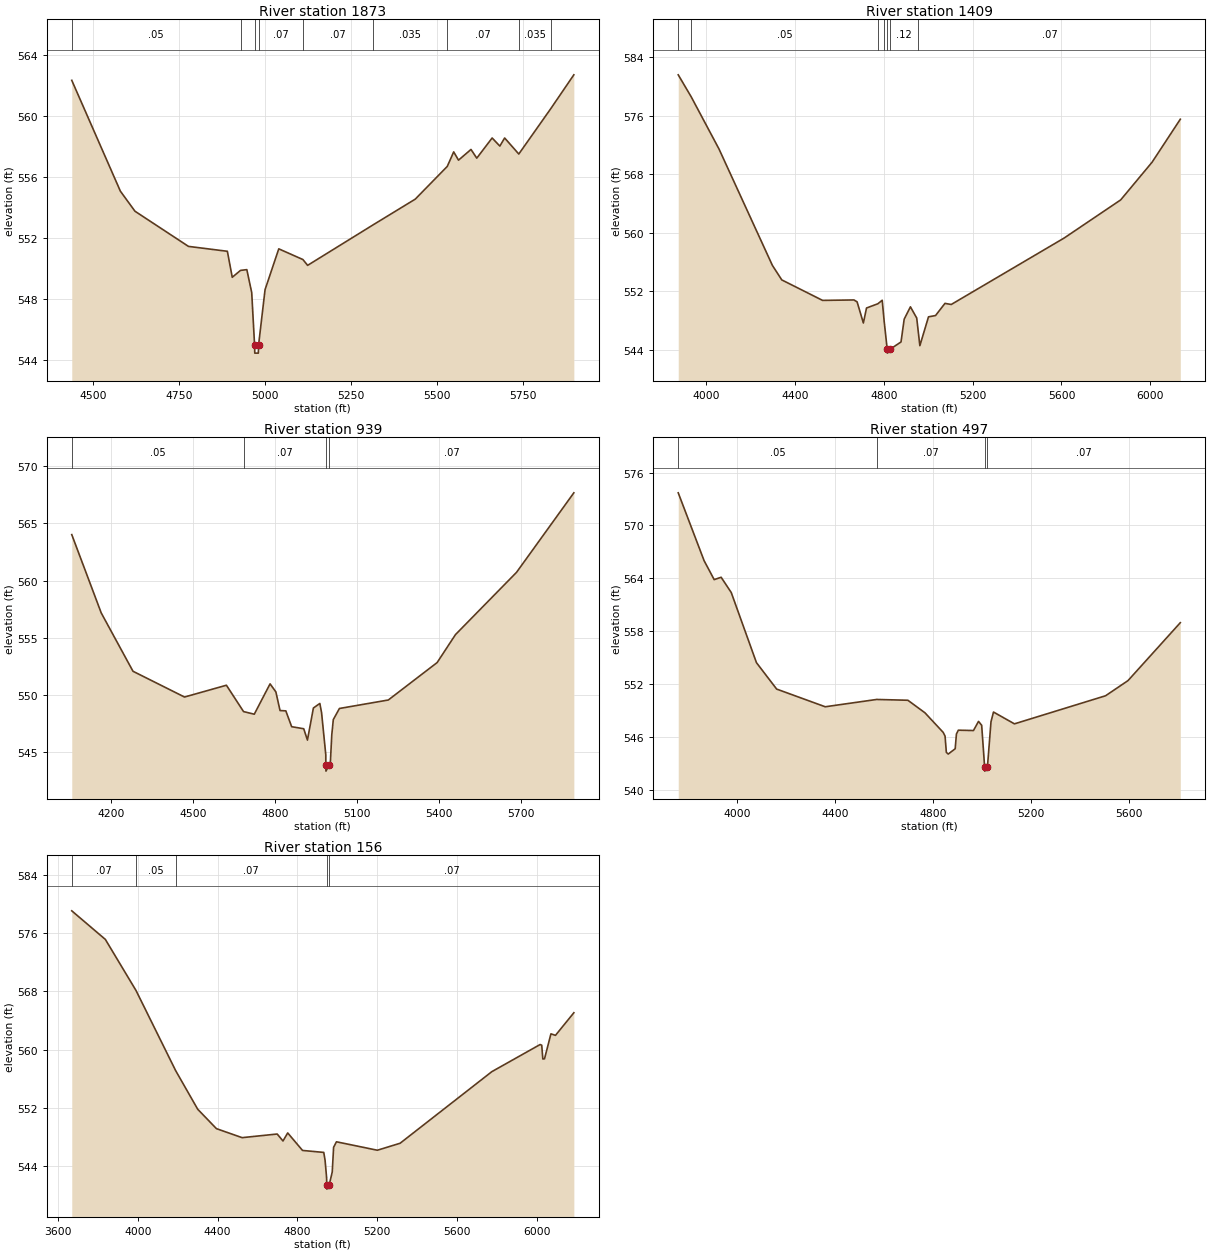
Type RM Length L Ch R = 1 ,1873    ,464,464,464
BEGIN DESCRIPTION:
YOUNGS TRIBUTARY 4 4.0
END DESCRIPTION:
XS GIS Cut Line= 3
      2259625.01     13763874.99        2260025.       13763475.
        2260425.       13762675.
#Sta/Elev= 30
    4439  562.32  4580.4  555.07  4622.8  553.76  4778.4  551.46  4891.5  551.14
  4905.7  549.44  4929.7  549.89  4948.1  549.94  4962.3  548.44  4970.7  544.98
  4971.2  544.48  4981.6  544.48  4982.1  544.98  5001.1  548.63    5041   551.3
  5111.2   550.6  5124.9  550.22    5314  552.85  5437.9  554.55    5531  556.69
  5549.7  557.64  5563.7   557.1    5600   557.8  5616.8  557.23  5661.5  558.55
  5683.9  558.02  5697.9  558.55    5739   557.5  5832.4  560.48  5899.1  562.68
#Mann= 9 ,-1 , 0
    4439     .05       0  4929.7     .07       0  4970.7     .05       0
  4982.1     .07       0  5111.2     .07       0    5314    .035       0
    5531     .07       0    5739    .035       0  5832.4     .07       0
Bank Sta=4970.7,4982.1
XS Rating Curve= 0 ,0
Exp/Cntr=0.3,0.1

Type RM Length L Ch R = 1 ,1409    ,470,470,470
BEGIN DESCRIPTION:
YOUNGS TRIBUTARY 4 3.0
END DESCRIPTION:
XS GIS Cut Line= 3
      2259574.98     13764325.02        2260375.       13763525.
      2261175.02     13762724.98
#Sta/Elev= 30
  3872.7  581.62    3931  578.62  4056.6  571.47    4297  555.57  4339.4  553.58
  4523.3  550.78  4664.7  550.84  4678.8  550.58  4707.1  547.69  4721.3  549.74
  4772.5  550.32    4792   550.8  4800.7  547.96  4814.6  544.07  4815.1  543.57
    4826  544.07  4876.8   545.1    4891  548.21  4919.2   549.9  4947.5  548.37
  4954.9   546.4  4961.7  544.59  5000.6  548.53  5032.4  548.71  5074.8  550.37
  5103.1  550.22  5612.2  559.31  5866.8  564.52  6008.2  569.67  6135.5  575.55
#Mann= 7 ,-1 , 0
  3872.7     .07       0    3931     .05       0  4772.5     .07       0
  4800.7     .12       0  4814.6     .05       0    4826     .12       0
  4954.9     .07       0
Bank Sta=4814.6,4826
XS Rating Curve= 0 ,0
Exp/Cntr=0.3,0.1

Type RM Length L Ch R = 1 ,939     ,442,442,442
BEGIN DESCRIPTION:
YOUNGS TRIBUTARY 4 2.0
END DESCRIPTION:
XS GIS Cut Line= 3
      2259924.97     13764325.02        2260725.       13763825.
      2261125.02     13763024.97
#Sta/Elev= 30
  4056.6  564.01  4164.5  557.17  4280.7  552.08  4469.4  549.83  4622.7  550.86
  4685.4  548.56  4724.7  548.33  4782.5  550.98  4803.7  550.28    4819  548.65
  4840.2  548.62  4861.5  547.24  4905.7  547.06  4919.3  546.07  4941.1  548.87
  4964.7  549.27  4971.1  548.45  4986.5  544.78  4986.6  543.86  4987.1  543.36
  4998.1  543.86  5002.8  543.93  5008.4  546.53    5014  547.86  5036.4  548.83
  5215.3  549.57  5394.1  552.84  5461.2  555.28  5684.8  560.72  5894.5  567.66
#Mann= 4 ,-1 , 0
  4056.6     .05       0  4685.4     .07       0  4986.6     .05       0
  4998.1     .07       0
Bank Sta=4986.6,4998.1
XS Rating Curve= 0 ,0
Exp/Cntr=0.3,0.1

Type RM Length L Ch R = 1 ,497     ,341,341,341
BEGIN DESCRIPTION:
YOUNGS TRIBUTARY 4 1.0
END DESCRIPTION:
XS GIS Cut Line= 3
        2259825.       13764425.        2261025.       13764125.
        2261175.     13763324.98
#Sta/Elev= 30
  3758.8   573.7  3864.5  565.99  3905.7  563.84    3934  564.11  3975.3  562.38
  4078.3  554.41  4160.8  551.41  4359.2   549.4  4569.4  550.23  4696.8  550.14
  4766.4  548.72  4841.1  546.49  4848.8  546.06    4854  544.22  4861.7  544.03
  4890.1  544.63  4895.2  546.31    4903  546.74  4964.8   546.7  4985.4  547.74
  4998.3   547.3  5010.3  542.59  5010.8  542.09  5021.9  542.59  5036.4   547.7
  5046.6   548.8  5132.2  547.46  5504.4  550.65    5596  552.37  5809.7  558.95
#Mann= 4 ,-1 , 0
  3758.8     .05       0  4569.4     .07       0  5010.3     .05       0
  5021.9     .07       0
Bank Sta=5010.3,5021.9
XS Rating Curve= 0 ,0
Exp/Cntr=0.3,0.1

Type RM Length L Ch R = 1 ,156     ,0,0,0
BEGIN DESCRIPTION:
J21860
END DESCRIPTION:
XS GIS Cut Line= 4
       2260084.9     13764916.03      2261119.59     13764472.59
      2261517.55      13764125.8      2261875.71     13763341.26
#Sta/Elev= 30
  3669.2  579.08  3837.4  575.15  3991.2  568.12    4190  557.09  4300.3  551.79
  4394.1  549.12  4522.8  547.88  4698.7  548.38  4727.7  547.42  4751.3  548.53
  4825.6  546.12    4932  545.85  4938.6  544.76  4946.2  542.38    4947   541.3
  4947.5   540.8  4958.6   541.3  4974.5  543.17  4981.3  546.55  4995.6  547.31
  5200.6  546.15  5314.6  547.11  5774.4  556.96  6016.2  560.69  6024.3  560.59
  6029.8   558.7  6038.2  558.72  6070.4  562.16  6093.1  561.95  6185.2  565.06
#Mann= 5 ,-1 , 0
  3669.2     .07       0  3991.2     .05       0    4190     .07       0
    4947     .05       0  4958.6     .07       0
Bank Sta=4947,4958.6
XS Rating Curve= 0 ,0
Exp/Cntr=0.3,0.1

Chan Stop Cuts=-1
Use User Specified Reach Order=0
Composite Channel Slope=5