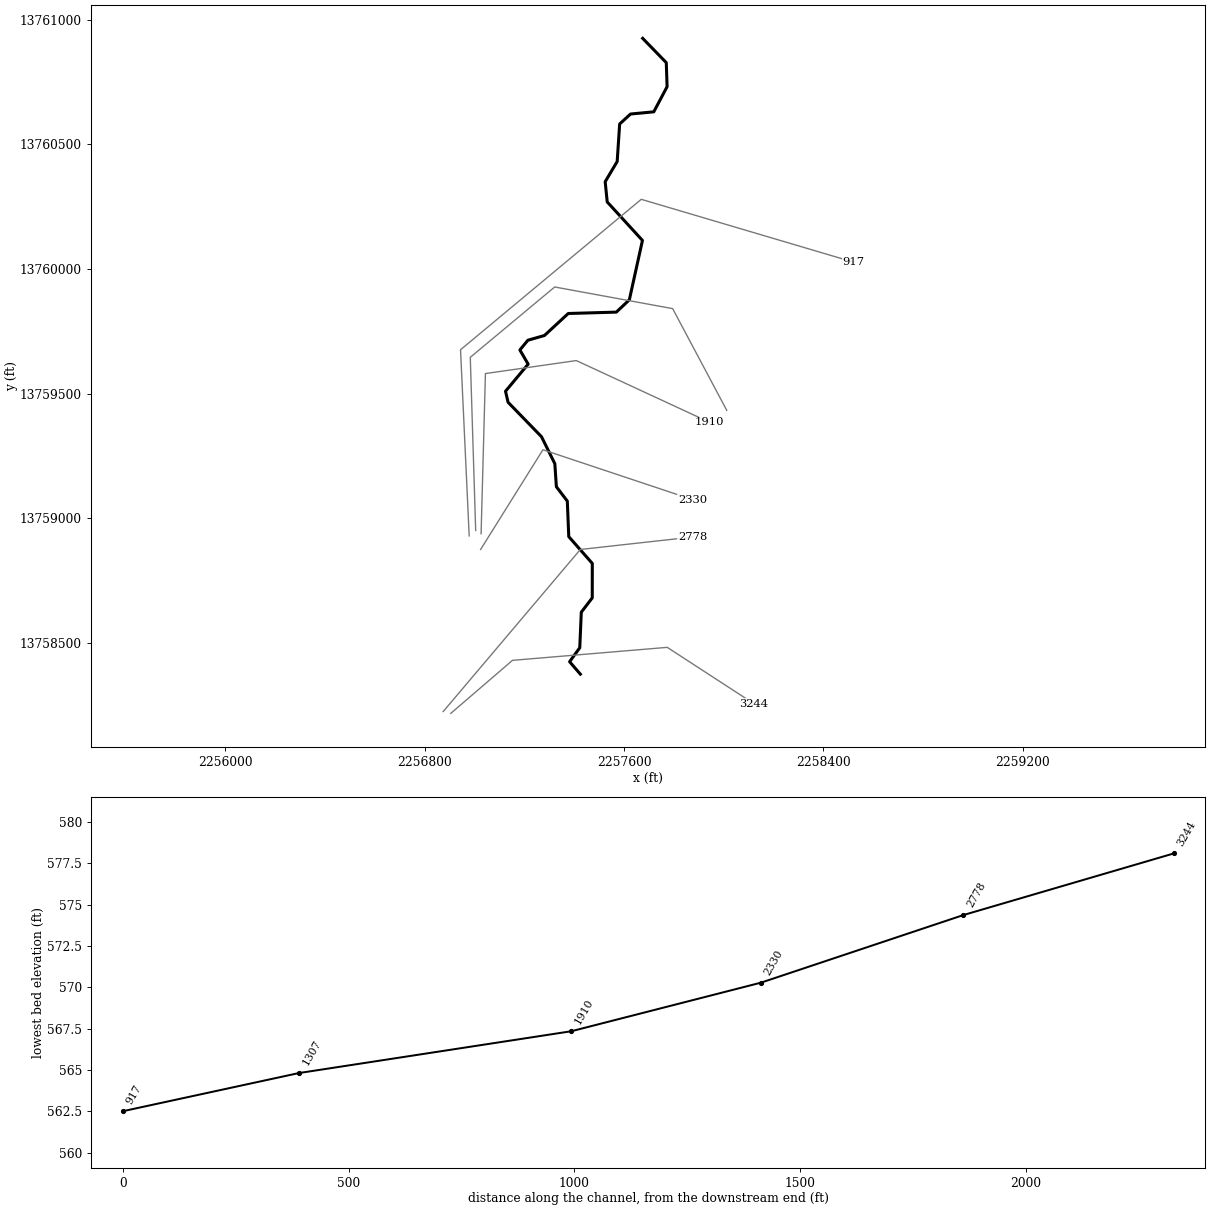
--- YOUNGS TRIBUTARY 4C.prj (project) ---

Proj Title=YOUNGS TRIBUTARY 4C Base Level Engineering
Current Plan=p01
Default Exp/Contr=0.3,0.1
English Units
Geom File=g01
Flow File=f01
Plan File=p01
BEGIN DESCRIPTION:
YOUNGS TRIBUTARY 4C
END DESCRIPTION:

--- YOUNGS TRIBUTARY 4C.p01 (plan) ---

Plan Title=Multiple Run
Short Identifier=Multiple
Geom File=g01
Flow File=f01
Subcritical Flow
K Sum by GR= 0
Std Step Tol= 0.01
Critical Tol= 0.01
Num of Std Step Trials= 20
Max Error Tol= 0.3
Flow Tol Ratio= 0.001
Split Flow NTrial= 30
Split Flow Tol= 0.02
Split Flow Ratio= 0.02
Log Output Level= 0
Friction Slope Method= 1
Unsteady Friction Slope Method= 2
Unsteady Bridges Friction Slope Method= 1
Parabolic Critical Depth
Global Vel Dist=  1 , 1 , 1
Global Log Level= 0
CheckData=True
Encroach Param= -1, 0, 0, 0
BEGIN DESCRIPTION:
Multiple Run
END DESCRIPTION:

--- YOUNGS TRIBUTARY 4C.f01 (steady flow) ---

Flow Title=Multiple
Number of Profiles=7
Profile Names=10-year,25-year,50-year,1pct_min,100-year,1pct_plu,500-year
River Rch & RM= YOUNGS TRIBUTARY,Reach-1,3244
     160     236     297     183     365     728     540
Boundary for River Rch & Prof#=YOUNGS TRIBUTARY,Reach-1,1
Up Type=0
Dn Type=3
Dn Slope=0.005
Boundary for River Rch & Prof#=YOUNGS TRIBUTARY,Reach-1,2
Up Type=0
Dn Type=3
Dn Slope=0.005
Boundary for River Rch & Prof#=YOUNGS TRIBUTARY,Reach-1,3
Up Type=0
Dn Type=3
Dn Slope=0.005
Boundary for River Rch & Prof#=YOUNGS TRIBUTARY,Reach-1,4
Up Type=0
Dn Type=3
Dn Slope=0.005
Boundary for River Rch & Prof#=YOUNGS TRIBUTARY,Reach-1,5
Up Type=0
Dn Type=3
Dn Slope=0.005
Boundary for River Rch & Prof#=YOUNGS TRIBUTARY,Reach-1,6
Up Type=0
Dn Type=3
Dn Slope=0.005
Boundary for River Rch & Prof#=YOUNGS TRIBUTARY,Reach-1,7
Up Type=0
Dn Type=3
Dn Slope=0.005

--- YOUNGS TRIBUTARY 4C.g01 (geometry) ---

Geom Title=Existing Conditions

River Reach=YOUNGS TRIBUTARY,Reach-1
Reach XY= 30
      2257425.00     13758375.00      2257381.91     13758424.86
      2257422.63     13758480.84      2257428.79     13758623.43
      2257472.75     13758680.94      2257472.94     13758819.14
      2257378.56     13758926.47      2257372.73     13759069.06
      2257328.86     13759126.60      2257322.67     13759219.03
      2257269.17     13759327.30      2257135.17     13759465.32
      2257124.90     13759509.64      2257215.67     13759618.35
      2257182.47     13759675.21      2257214.61     13759714.22
      2257281.00     13759733.18      2257376.47     13759821.45
      2257569.35     13759826.97      2257621.49     13759876.25
      2257674.07     13760114.52      2257532.76     13760268.83
      2257524.59     13760350.00      2257572.73     13760430.94
      2257582.68     13760581.52      2257626.32     13760621.46
      2257719.56     13760630.25      2257772.87     13760730.94
      2257769.67     13760827.45      2257675.00     13760925.00

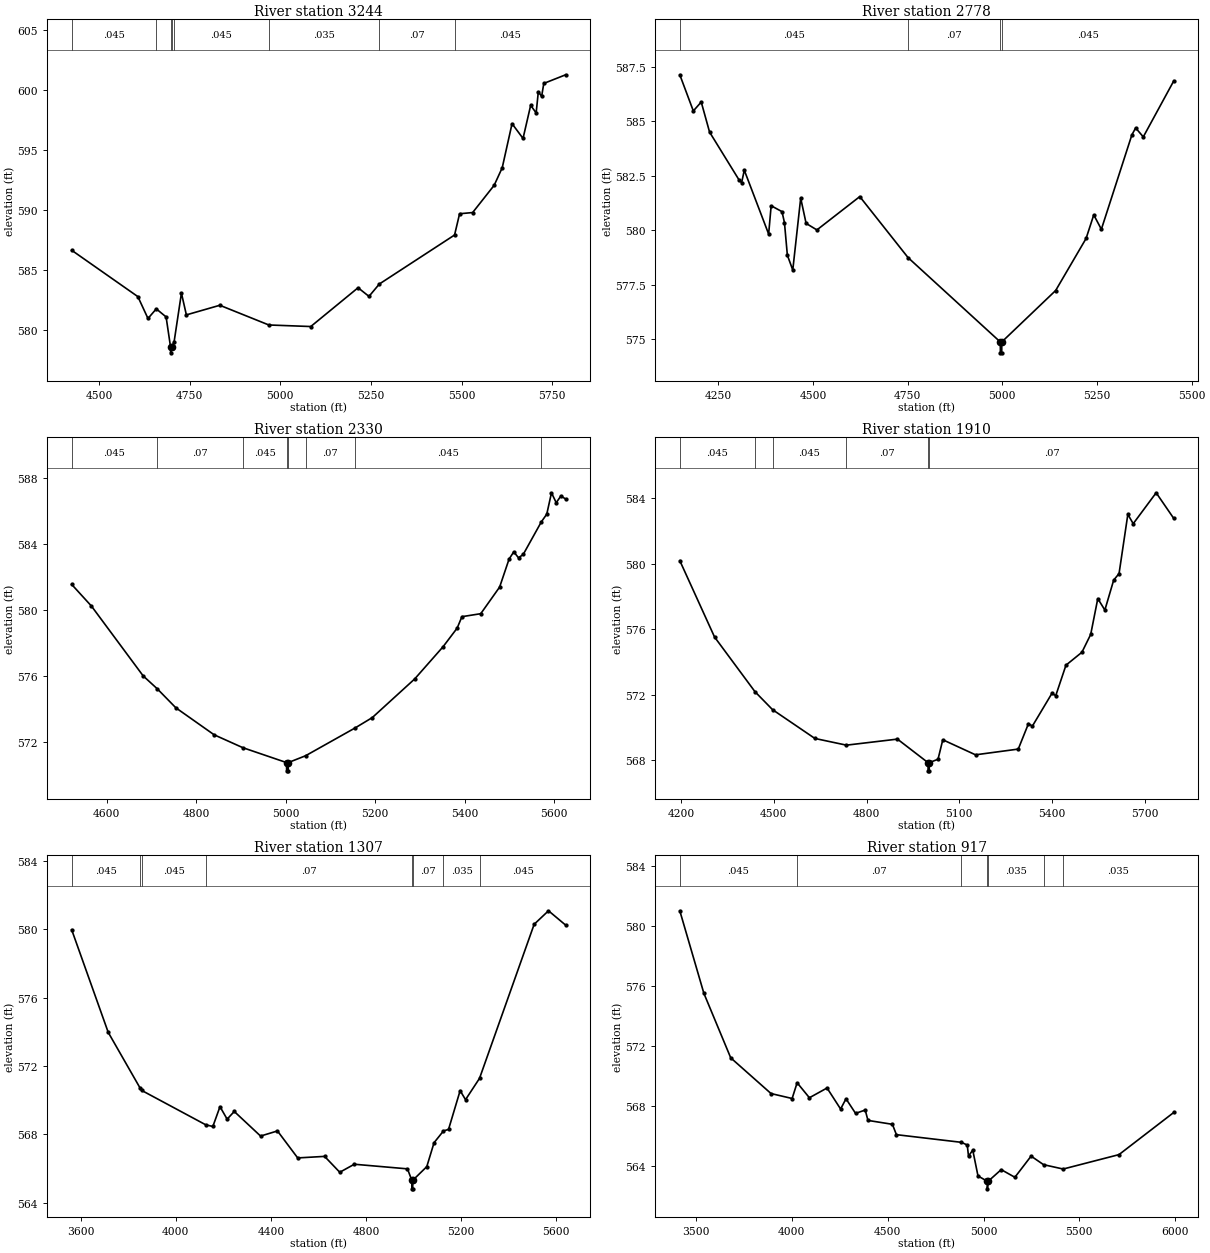
Type RM Length L Ch R = 1,3244,466,466,466
BEGIN DESCRIPTION:
J21872
END DESCRIPTION:
XS GIS Cut Line= 4
      2256905.41     13758217.70      2257152.82     13758430.38
      2257773.48     13758482.47      2258120.34     13758257.00
#Sta/Elev= 30
  4424.5  586.64  4607.1  582.78  4635.0  580.96  4657.9  581.76  4685.0  581.09
  4697.2  578.60  4697.5  578.10  4701.2  578.60  4707.2  579.04  4727.3  583.07
  4740.9  581.26  4833.2  582.06  4968.4  580.42  5084.1  580.29  5214.6  583.52
  5244.7  582.80  5273.3  583.83  5480.8  587.91  5494.7  589.68  5530.7  589.78
  5590.1  592.05  5612.3  593.51  5639.4  597.18  5669.7  595.95  5690.8  598.71
  5705.9  598.07  5711.9  599.84  5721.0  599.45  5727.0  600.53  5787.3  601.25
#Mann=8,-1,0
  4424.5   0.045       0  4657.9    0.07       0  4697.2   0.035       0
  4701.2    0.07       0  4707.2   0.045       0  4968.4   0.035       0
  5273.3    0.07       0  5480.8   0.045       0
Bank Sta=4697.2,4701.2
Exp/Cntr=0.3,0.1

Type RM Length L Ch R = 1,2778,448,448,448
BEGIN DESCRIPTION:
YOUNGS TRIBUTARY 4C 2.0
END DESCRIPTION:
XS GIS Cut Line= 3
      2256874.99     13758224.98      2257425.00     13758875.00
      2257875.04     13758925.00
#Sta/Elev= 30
  4148.5  587.13  4184.2  585.47  4205.1  585.88  4227.1  584.50  4305.1  582.30
  4311.7  582.18  4318.8  582.75  4383.1  579.82  4389.7  581.12  4418.3  580.85
  4424.8  580.35  4432.5  578.85  4446.8  578.17  4467.7  581.47  4482.0  580.31
  4510.5  580.01  4623.7  581.54  4751.2  578.74  4994.7  574.87  4995.0  574.37
  4998.5  574.37  4998.7  574.87  5140.9  577.23  5221.3  579.62  5241.5  580.70
  5261.6  580.04  5342.1  584.37  5352.1  584.69  5372.3  584.28  5452.8  586.85
#Mann=4,-1,0
  4148.5   0.045       0  4751.2    0.07       0  4994.7   0.045       0
  4998.7   0.045       0
Bank Sta=4994.7,4998.7
Exp/Cntr=0.3,0.1

Type RM Length L Ch R = 1,2330,420,420,420
BEGIN DESCRIPTION:
YOUNGS TRIBUTARY 4C 1.0
END DESCRIPTION:
XS GIS Cut Line= 3
      2257025.00     13758874.99      2257275.00     13759275.00
      2257875.04     13759074.99
#Sta/Elev= 30
  4521.9  581.55  4566.1  580.24  4681.7  576.02  4713.2  575.24  4754.8  574.09
  4840.3  572.46  4904.5  571.68  5002.1  570.78  5002.4  570.28  5005.9  570.28
  5006.1  570.78  5044.6  571.19  5155.9  572.88  5193.9  573.50  5288.8  575.84
  5352.0  577.78  5383.6  578.91  5394.2  579.60  5436.3  579.78  5478.5  581.39
  5499.6  583.08  5510.1  583.52  5520.7  583.16  5531.2  583.36  5571.7  585.33
  5583.9  585.80  5594.4  587.09  5605.0  586.49  5615.5  586.90  5626.1  586.71
#Mann=8,-1,0
  4521.9   0.045       0  4713.2    0.07       0  4904.5   0.045       0
  5002.1   0.045       0  5006.1   0.045       0  5044.6    0.07       0
  5155.9   0.045       0  5571.7    0.07       0
Bank Sta=5002.1,5006.1
Exp/Cntr=0.3,0.1

Type RM Length L Ch R = 1,1910,603,603,603
BEGIN DESCRIPTION:
J21871
END DESCRIPTION:
XS GIS Cut Line= 4
      2257026.95     13758938.22      2257044.31     13759580.56
      2257408.89     13759632.64      2257941.34     13759385.90
#Sta/Elev= 30
  4196.1  580.19  4308.5  575.52  4439.2  572.18  4496.1  571.08  4633.0  569.32
  4735.0  568.91  4900.0  569.28  4999.0  567.84  4999.2  567.34  5002.7  567.34
  5003.0  567.84  5031.3  568.05  5046.7  569.24  5152.5  568.32  5290.8  568.67
  5323.9  570.23  5336.3  570.07  5399.5  572.07  5412.1  571.94  5445.1  573.80
  5496.7  574.59  5525.1  575.68  5548.0  577.87  5570.9  577.17  5599.4  579.00
  5616.8  579.40  5645.2  583.02  5662.6  582.45  5736.8  584.34  5793.8  582.77
#Mann=6,-1,0
  4196.1   0.045       0  4439.2    0.07       0  4496.1   0.045       0
  4735.0    0.07       0  4999.0    0.05       0  5003.0    0.07       0
Bank Sta=4999,5003
Exp/Cntr=0.3,0.1

Type RM Length L Ch R = 1,1307,390,390,390
BEGIN DESCRIPTION:
J21870
END DESCRIPTION:
XS GIS Cut Line= 5
      2257005.25     13758951.26      2256983.55     13759645.66
      2257322.09     13759927.78      2257795.18     13759840.97
      2258012.18     13759433.01
#Sta/Elev= 30
  3561.7  579.98  3715.5  573.97  3849.6  570.71  3856.5  570.57  4125.7  568.56
  4155.7  568.46  4185.7  569.62  4215.8  568.89  4245.8  569.34  4356.5  567.90
  4427.6  568.20  4512.7  566.62  4625.9  566.71  4689.7  565.78  4750.9  566.25
  4974.6  565.98  4992.9  565.31  4993.2  564.81  4996.7  564.81  4996.9  565.31
  5055.9  566.11  5086.4  567.51  5126.1  568.20  5147.4  568.29  5196.2  570.56
  5218.9  570.03  5277.8  571.28  5507.7  580.30  5568.0  581.09  5640.2  580.25
#Mann=8,-1,0
  3561.7   0.045       0  3849.6    0.07       0  3856.5   0.045       0
  4125.7    0.07       0  4992.9    0.05       0  4996.9    0.07       0
  5126.1   0.035       0  5277.8   0.045       0
Bank Sta=4992.9,4996.9
Exp/Cntr=0.3,0.1

Type RM Length L Ch R = 1,917,0,0,0
BEGIN DESCRIPTION:
J21869
END DESCRIPTION:
XS GIS Cut Line= 4
      2256979.20     13758929.55      2256944.48     13759676.04
      2257669.31     13760279.34      2258520.00     13760027.61
#Sta/Elev= 30
  3415.3  581.03  3540.9  575.53  3681.0  571.23  3891.3  568.85  4001.4  568.52
  4027.5  569.57  4091.5  568.57  4183.6  569.22  4254.3  567.82  4282.5  568.50
  4332.4  567.53  4382.8  567.75  4397.1  567.06  4524.7  566.80  4545.5  566.11
  4884.5  565.60  4915.2  565.42  4921.7  564.68  4943.9  565.08  4971.2  563.36
  5020.0  563.00  5020.2  562.50  5024.0  563.00  5092.3  563.78  5163.7  563.27
  5248.3  564.68  5313.4  564.11  5415.7  563.82  5706.8  564.78  5992.8  567.59
#Mann=7,-1,0
  3415.3   0.045       0  4027.5    0.07       0  4884.5   0.035       0
  5020.0   0.035       0  5024.0   0.035       0  5313.4    0.07       0
  5415.7   0.035       0
Bank Sta=5020,5024
Exp/Cntr=0.3,0.1

Chan Stop Cuts=-1