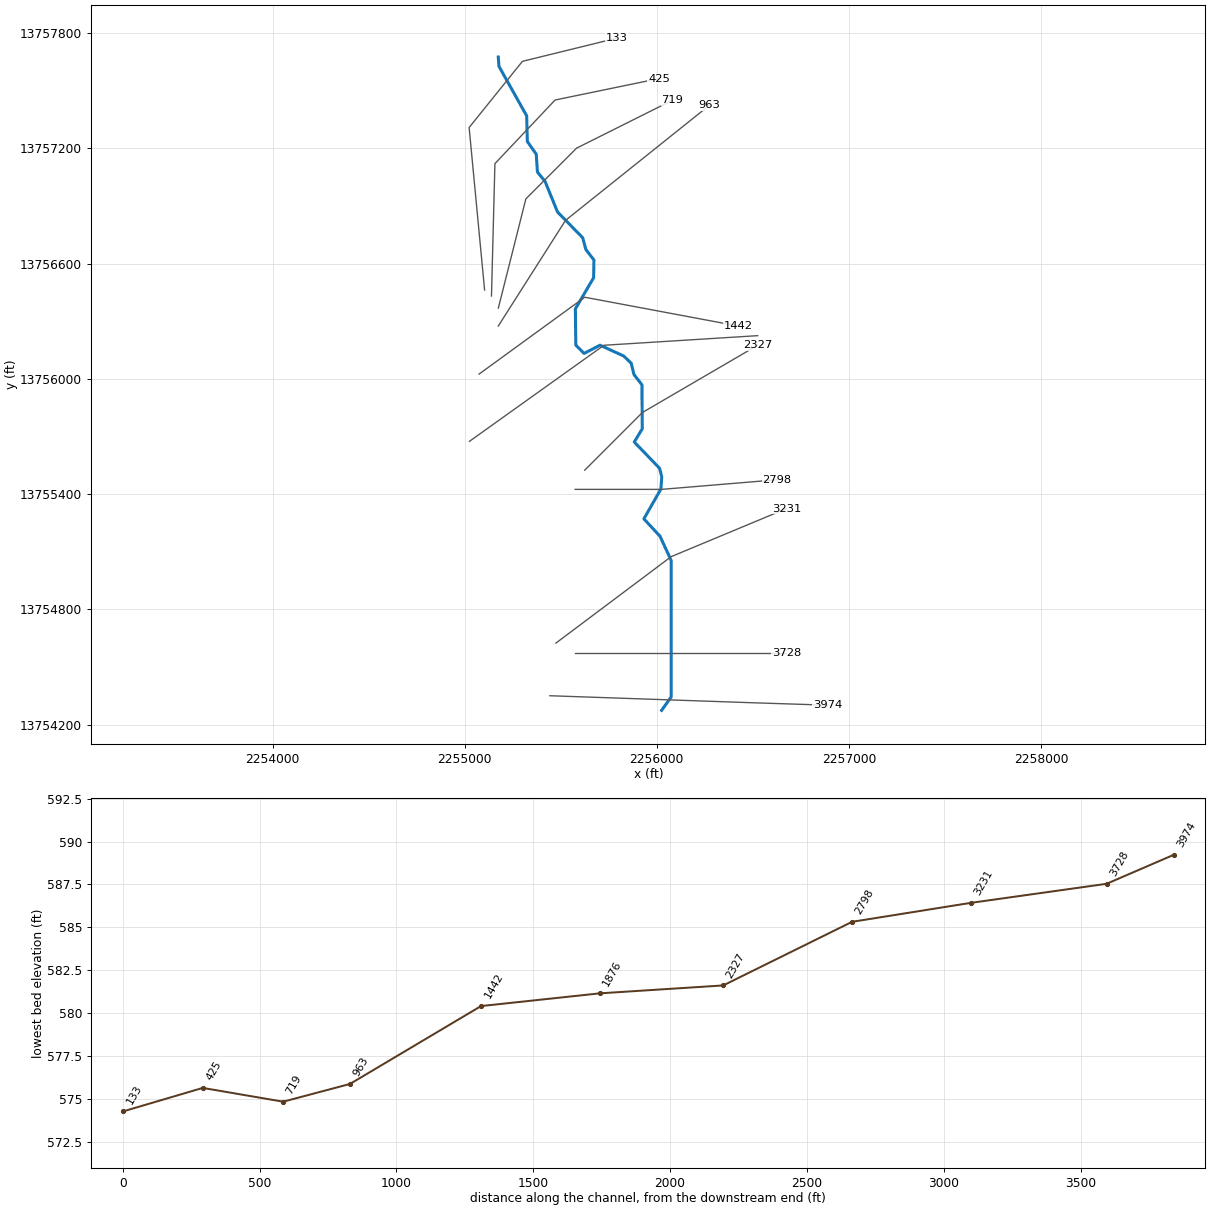
--- YOUNGS TRIBUTARY 6.prj (project) ---

Proj Title=YOUNGS TRIBUTARY 6 Base Level Engineering
Current Plan=p01
Default Exp/Contr=0.3,0.1
English Units
Geom File=g01
Flow File=f01
Plan File=p01
BEGIN DESCRIPTION:
YOUNGS TRIBUTARY 6
END DESCRIPTION:

--- YOUNGS TRIBUTARY 6.p01 (plan) ---

Plan Title=Multiple Run
Short Identifier=Multiple
Geom File=g01
Flow File=f01
Subcritical Flow
K Sum by GR= 0
Std Step Tol= 0.01
Critical Tol= 0.01
Num of Std Step Trials= 20
Max Error Tol= 0.3
Flow Tol Ratio= 0.001
Split Flow NTrial= 30
Split Flow Tol= 0.02
Split Flow Ratio= 0.02
Log Output Level= 0
Friction Slope Method= 1
Unsteady Friction Slope Method= 2
Unsteady Bridges Friction Slope Method= 1
Parabolic Critical Depth
Global Vel Dist=  1 , 1 , 1
Global Log Level= 0
CheckData=True
Encroach Param= -1, 0, 0, 0
BEGIN DESCRIPTION:
Multiple Run
END DESCRIPTION:

--- YOUNGS TRIBUTARY 6.f01 (steady flow) ---

Flow Title=Multiple
Number of Profiles=7
Profile Names=10-year,25-year,50-year,1pct_min,100-year,1pct_plu,500-year
River Rch & RM= YOUNGS TRIBUTARY,Reach-1,3974
     686    1106    1484     963    1921    3833    3187
Boundary for River Rch & Prof#=YOUNGS TRIBUTARY,Reach-1,1
Up Type=0
Dn Type=3
Dn Slope=0.005
Boundary for River Rch & Prof#=YOUNGS TRIBUTARY,Reach-1,2
Up Type=0
Dn Type=3
Dn Slope=0.005
Boundary for River Rch & Prof#=YOUNGS TRIBUTARY,Reach-1,3
Up Type=0
Dn Type=3
Dn Slope=0.005
Boundary for River Rch & Prof#=YOUNGS TRIBUTARY,Reach-1,4
Up Type=0
Dn Type=3
Dn Slope=0.005
Boundary for River Rch & Prof#=YOUNGS TRIBUTARY,Reach-1,5
Up Type=0
Dn Type=3
Dn Slope=0.005
Boundary for River Rch & Prof#=YOUNGS TRIBUTARY,Reach-1,6
Up Type=0
Dn Type=3
Dn Slope=0.005
Boundary for River Rch & Prof#=YOUNGS TRIBUTARY,Reach-1,7
Up Type=0
Dn Type=3
Dn Slope=0.005

--- YOUNGS TRIBUTARY 6.g01 (geometry) ---

Geom Title=Existing Conditions

River Reach=YOUNGS TRIBUTARY,Reach-1
Reach XY= 30
      2256025.00     13754275.00      2256075.02     13754344.99
      2256074.94     13755054.97      2256016.82     13755181.06
      2255932.78     13755271.60      2256021.33     13755426.59
      2256025.77     13755490.09      2256014.56     13755534.79
      2255882.79     13755671.58      2255924.34     13755740.16
      2255922.76     13755969.07      2255881.15     13756022.85
      2255866.98     13756081.34      2255827.55     13756119.28
      2255704.79     13756175.22      2255621.30     13756132.70
      2255578.53     13756175.99      2255576.20     13756364.50
      2255671.33     13756526.58      2255672.86     13756619.03
      2255631.15     13756672.83      2255614.24     13756734.68
      2255483.14     13756868.94      2255418.88     13757027.18
      2255378.83     13757076.58      2255372.64     13757169.02
      2255326.23     13757235.51      2255322.75     13757369.07
      2255178.60     13757626.49      2255175.00     13757675.00

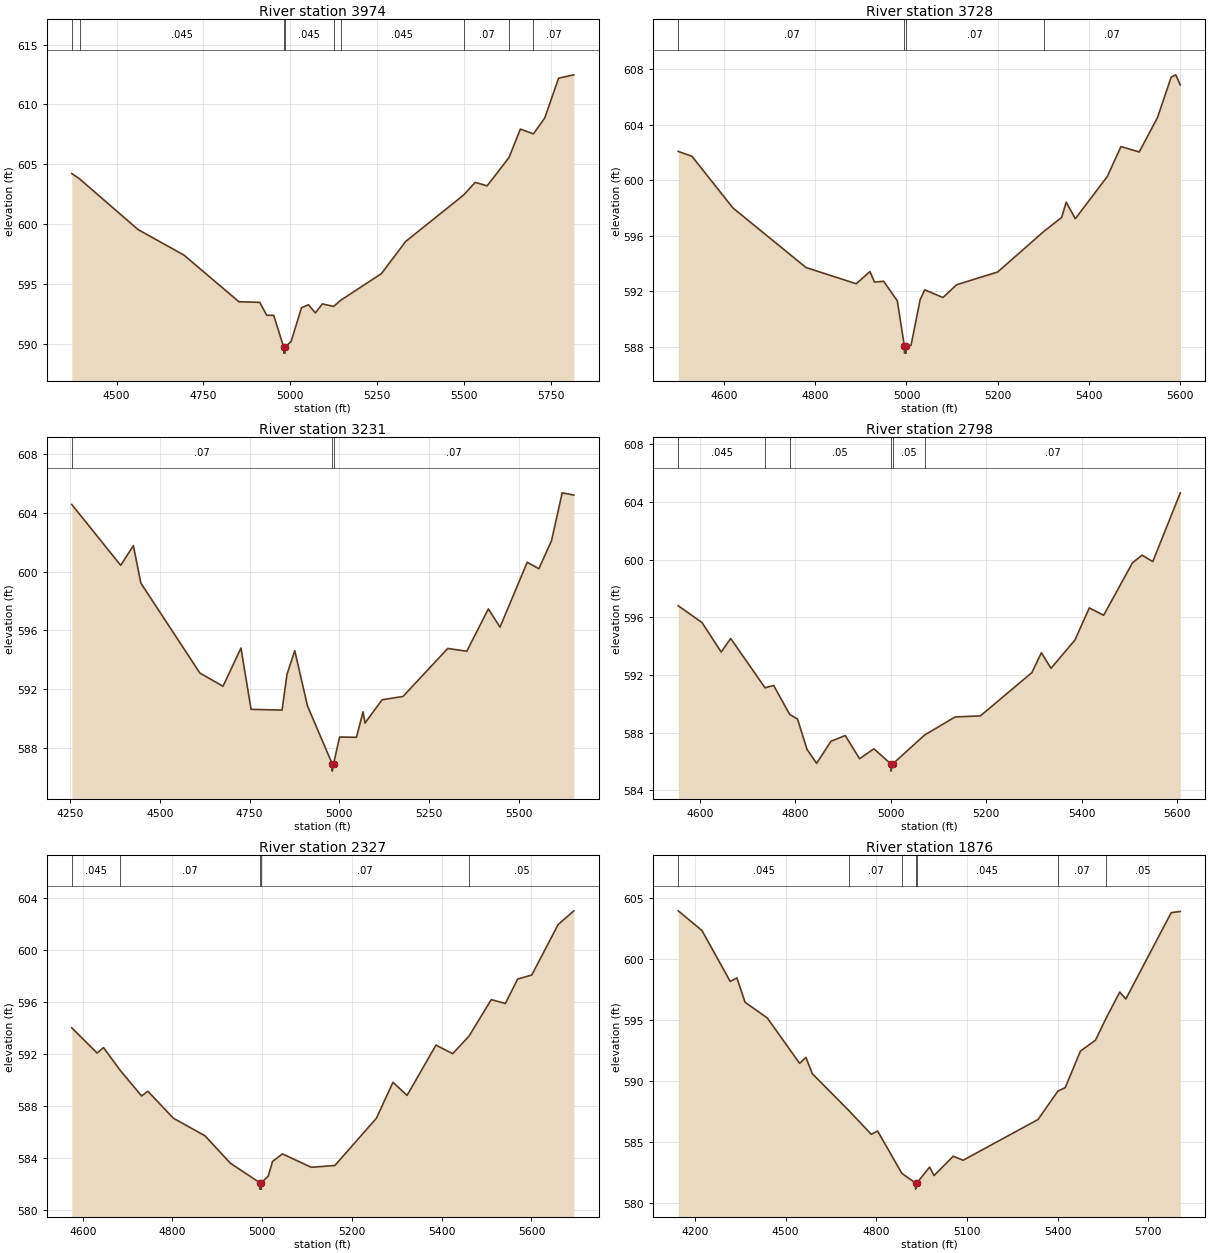
Type RM Length L Ch R = 1,3974,246,246,246
BEGIN DESCRIPTION:
J21876
END DESCRIPTION:
XS GIS Cut Line= 3
      2255443.81     13754351.05      2256477.26     13754315.26
      2256888.87     13754301.84
#Sta/Elev= 30
  4370.8  604.23  4393.3  603.78  4562.1  599.54  4693.7  597.42  4852.3  593.52
  4912.3  593.47  4932.3  592.39  4952.3  592.39  4981.2  589.73  4981.5  589.23
  4985.0  589.23  4985.2  589.73  5002.4  590.20  5032.4  593.02  5052.4  593.27
  5072.4  592.59  5092.4  593.34  5124.8  593.13  5145.6  593.65  5262.5  595.87
  5332.6  598.56  5499.2  602.43  5532.7  603.49  5567.0  603.20  5630.1  605.57
  5662.7  607.94  5700.3  607.54  5732.8  608.86  5772.8  612.19  5816.7  612.47
#Mann=9,-1,0
  4370.8    0.07       0  4393.3   0.045       0  4981.2   0.045       0
  4985.2   0.045       0  5124.8   0.035       0  5145.6   0.045       0
  5499.2    0.07       0  5630.1   0.045       0  5700.3    0.07       0
Bank Sta=4981.2,4985.2
Exp/Cntr=0.3,0.1

Type RM Length L Ch R = 1,3728,497,497,497
BEGIN DESCRIPTION:
YOUNGS TRIBUTARY 6 7.0
END DESCRIPTION:
XS GIS Cut Line= 3
      2255575.01     13754575.00      2256075.00     13754575.00
      2256675.01     13754575.00
#Sta/Elev= 30
  4500.0  602.08  4530.0  601.73  4620.0  598.00  4780.0  593.71  4890.0  592.54
  4920.0  593.42  4930.0  592.66  4950.0  592.72  4980.0  591.31  4995.5  588.04
  4995.7  587.54  4999.2  587.54  4999.5  588.04  5010.0  588.10  5030.0  591.39
  5040.0  592.10  5080.0  591.55  5110.0  592.47  5200.0  593.39  5300.5  596.30
  5340.0  597.32  5350.0  598.42  5370.0  597.23  5440.0  600.27  5470.0  602.43
  5510.0  602.04  5550.0  604.52  5580.0  607.43  5590.0  607.60  5600.0  606.87
#Mann=4,-1,0
  4500.0    0.07       0  4995.5   0.045       0  4999.5    0.07       0
  5300.5    0.07       0
Bank Sta=4995.5,4999.5
Exp/Cntr=0.3,0.1

Type RM Length L Ch R = 1,3231,433,433,433
BEGIN DESCRIPTION:
YOUNGS TRIBUTARY 6 6.0
END DESCRIPTION:
XS GIS Cut Line= 3
      2255475.04     13754625.03      2256075.00     13755075.00
      2256675.04     13755325.02
#Sta/Elev= 30
  4254.3  604.56  4390.7  600.42  4426.1  601.76  4447.0  599.21  4611.5  593.10
  4676.1  592.20  4726.1  594.80  4754.3  590.63  4840.7  590.58  4854.3  593.00
  4876.1  594.62  4911.5  590.87  4980.4  586.93  4980.6  586.43  4984.4  586.93
  5001.1  588.75  5048.1  588.73  5066.5  590.46  5072.0  589.70  5119.6  591.28
  5178.1  591.51  5302.7  594.77  5355.8  594.58  5415.9  597.46  5448.4  596.22
  5524.3  600.63  5556.8  600.19  5592.0  602.09  5621.8  605.35  5654.3  605.20
#Mann=3,-1,0
  4254.3    0.07       0  4980.4    0.05       0  4984.4    0.07       0
Bank Sta=4980.4,4984.4
Exp/Cntr=0.3,0.1

Type RM Length L Ch R = 1,2798,471,471,471
BEGIN DESCRIPTION:
YOUNGS TRIBUTARY 6 5.0
END DESCRIPTION:
XS GIS Cut Line= 3
      2255575.03     13755425.00      2256025.00     13755425.00
      2256625.05     13755475.00
#Sta/Elev= 30
  4554.5  596.80  4604.5  595.63  4644.5  593.59  4664.5  594.53  4736.4  591.11
  4754.5  591.27  4788.1  589.26  4804.5  588.94  4824.5  586.83  4844.5  585.87
  4874.5  587.40  4904.5  587.80  4934.5  586.19  4964.5  586.88  5000.0  585.83
  5000.2  585.33  5004.0  585.83  5071.0  587.84  5134.9  589.09  5187.6  589.16
  5295.5  592.16  5315.5  593.54  5335.6  592.46  5385.8  594.42  5415.9  596.65
  5446.0  596.14  5506.2  599.77  5526.3  600.31  5548.9  599.86  5606.6  604.63
#Mann=6,-1,0
  4554.5   0.045       0  4736.4    0.07       0  4788.1    0.05       0
  5000.0    0.05       0  5004.0    0.05       0  5071.0    0.07       0
Bank Sta=5000,5004
Exp/Cntr=0.3,0.1

Type RM Length L Ch R = 1,2327,451,451,451
BEGIN DESCRIPTION:
YOUNGS TRIBUTARY 6 4.0
END DESCRIPTION:
XS GIS Cut Line= 3
      2255624.98     13755524.98      2255925.00     13755825.00
      2256524.99     13756174.99
#Sta/Elev= 30
  4575.6  594.04  4632.2  592.10  4646.3  592.52  4684.0  590.75  4731.2  588.80
  4745.3  589.16  4801.9  587.09  4872.6  585.73  4929.2  583.62  4994.4  582.13
  4994.6  581.63  4998.1  581.63  4998.4  582.13  5013.5  582.64  5023.0  583.76
  5045.0  584.34  5109.5  583.31  5162.0  583.45  5254.6  587.09  5291.4  589.85
  5322.8  588.84  5387.3  592.71  5424.5  592.05  5461.1  593.41  5510.5  596.21
  5541.9  595.91  5569.2  597.79  5600.7  598.10  5659.4  601.98  5694.5  603.04
#Mann=5,-1,0
  4575.6   0.045       0  4684.0    0.07       0  4994.4    0.05       0
  4998.4    0.07       0  5461.1    0.05       0
Bank Sta=4994.4,4998.4
Exp/Cntr=0.3,0.1

Type RM Length L Ch R = 1,1876,434,434,434
BEGIN DESCRIPTION:
YOUNGS TRIBUTARY 6 3.0
END DESCRIPTION:
XS GIS Cut Line= 3
      2255025.03     13755675.02      2255725.00     13756175.00
      2256525.04     13756225.00
#Sta/Elev= 30
  4144.4  603.92  4223.0  602.31  4316.4  598.15  4338.5  598.44  4365.6  596.45
  4439.3  595.16  4546.2  591.45  4567.1  591.94  4588.0  590.61  4710.3  587.56
  4783.4  585.65  4804.3  585.92  4884.9  582.45  4930.1  581.67  4930.3  581.17
  4934.1  581.67  4976.3  582.97  4991.1  582.28  5054.7  583.86  5087.3  583.53
  5335.2  586.86  5401.0  589.18  5425.4  589.47  5475.5  592.45  5525.6  593.35
  5560.1  595.12  5605.8  597.28  5625.8  596.71  5776.1  603.77  5806.2  603.87
#Mann=7,-1,0
  4144.4   0.045       0  4710.3    0.07       0  4884.9   0.045       0
  4930.1   0.045       0  4934.1   0.045       0  5401.0    0.07       0
  5560.1    0.05       0
Bank Sta=4930.1,4934.1
Exp/Cntr=0.3,0.1

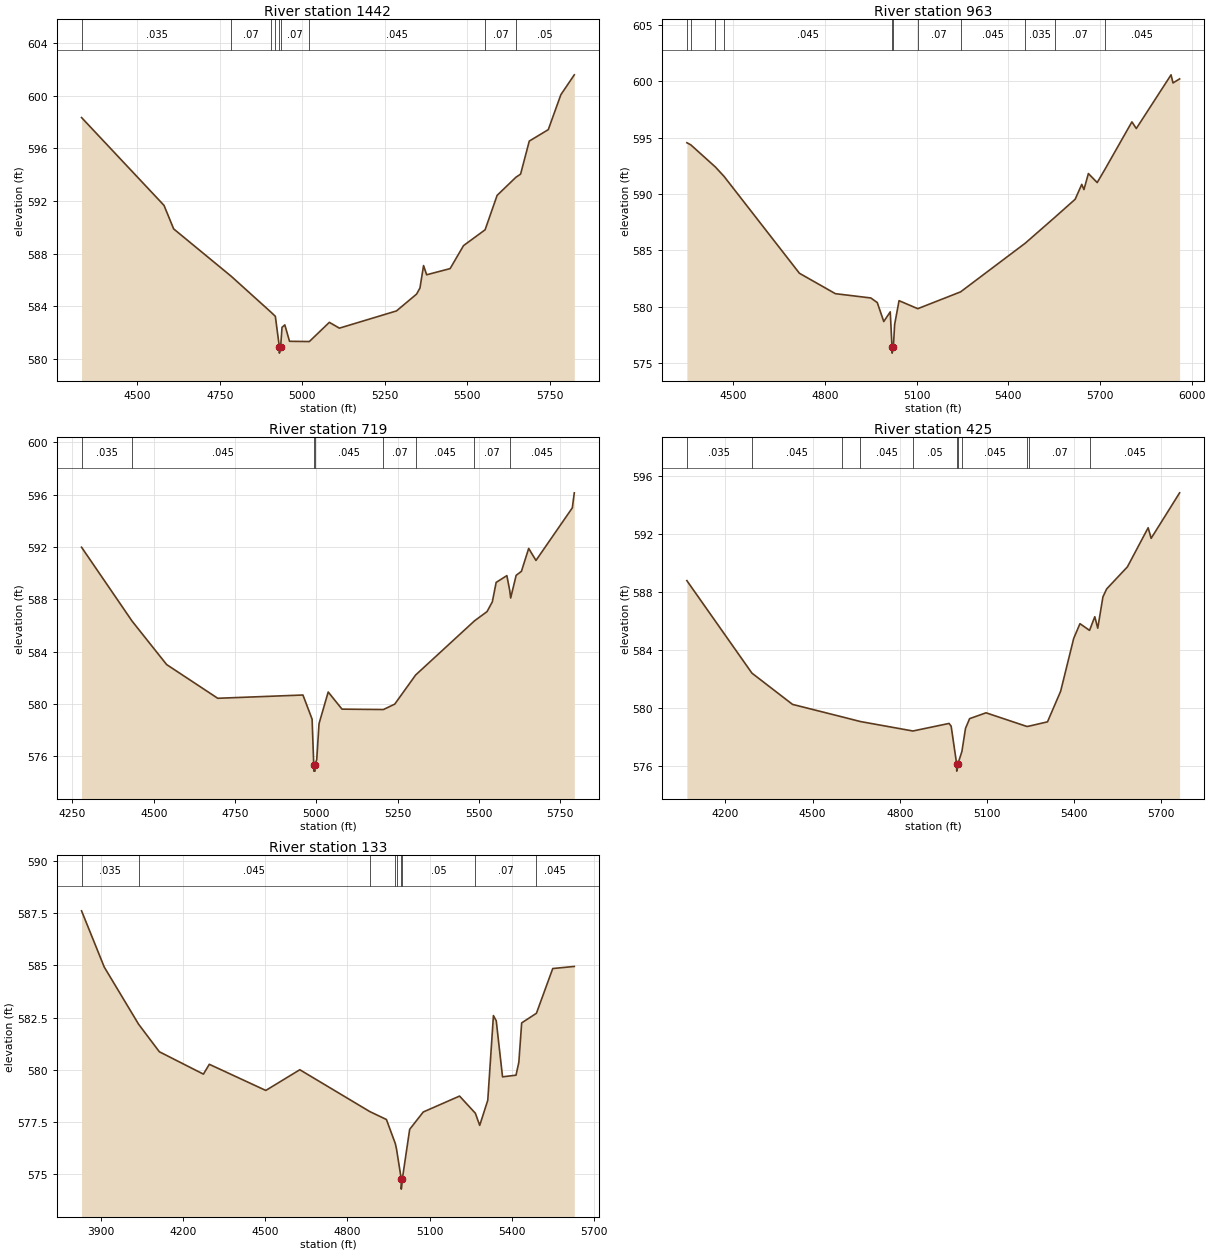
Type RM Length L Ch R = 1,1442,479,479,479
BEGIN DESCRIPTION:
YOUNGS TRIBUTARY 6 2.0
END DESCRIPTION:
XS GIS Cut Line= 3
      2255075.02     13756025.01      2255625.00     13756425.00
      2256425.01     13756275.00
#Sta/Elev= 30
  4330.9  598.35  4580.9  591.67  4610.2  589.88  4785.0  586.27  4904.2  583.57
  4918.5  583.23  4930.5  580.93  4930.8  580.43  4934.6  580.93  4938.7  582.39
  4947.2  582.58  4961.5  581.33  5021.5  581.31  5082.2  582.77  5112.7  582.33
  5285.7  583.64  5346.7  584.92  5356.9  585.38  5367.9  587.09  5377.2  586.39
  5448.4  586.86  5489.1  588.61  5554.4  589.81  5590.9  592.43  5648.0  593.81
  5662.1  594.05  5688.4  596.56  5746.0  597.43  5784.2  600.09  5824.9  601.60
#Mann=9,-1,0
  4330.9   0.035       0  4785.0    0.07       0  4904.2   0.045       0
  4918.5    0.07       0  4930.5    0.05       0  4934.6    0.07       0
  5021.5   0.045       0  5554.4    0.07       0  5648.0    0.05       0
Bank Sta=4930.5,4934.6
Exp/Cntr=0.3,0.1

Type RM Length L Ch R = 1,963,244,244,244
BEGIN DESCRIPTION:
YOUNGS TRIBUTARY 6 1.0
END DESCRIPTION:
XS GIS Cut Line= 3
      2255175.00     13756274.99      2255525.00     13756825.00
      2256275.00     13757425.00
#Sta/Elev= 30
  4348.3  594.55  4361.3  594.36  4441.6  592.40  4469.9  591.57  4716.6  582.98
  4834.3  581.17  4950.3  580.79  4971.4  580.38  4992.6  578.70  5013.8  579.56
  5019.7  576.40  5020.0  575.90  5023.9  576.40  5028.2  578.44  5042.6  580.55
  5103.9  579.84  5244.0  581.33  5455.8  585.65  5552.9  587.95  5618.9  589.54
  5640.5  590.86  5647.7  590.40  5662.2  591.82  5691.0  591.02  5716.5  592.20
  5804.6  596.40  5819.0  595.81  5932.7  600.57  5939.1  599.85  5960.7  600.21
#Mann=11,-1,0
  4348.3   0.035       0  4361.3   0.045       0  4441.6   0.035       0
  4469.9   0.045       0  5019.7   0.045       0  5023.9   0.045       0
  5103.9    0.07       0  5244.0   0.045       0  5455.8   0.035       0
  5552.9    0.07       0  5716.5   0.045       0
Bank Sta=5019.7,5023.9
Exp/Cntr=0.3,0.1

Type RM Length L Ch R = 1,719,294,294,294
BEGIN DESCRIPTION:
J21875
END DESCRIPTION:
XS GIS Cut Line= 4
      2255175.42     13756368.70      2255318.57     13756936.84
      2255582.52     13757200.79      2256080.47     13757449.76
#Sta/Elev= 30
  4277.9  591.99  4433.7  586.33  4539.6  583.02  4696.9  580.44  4959.0  580.69
  4987.2  578.84  4992.2  575.37  4992.5  574.87  4996.2  574.87  4996.4  575.37
  5001.4  575.75  5008.5  578.50  5036.7  580.92  5079.2  579.61  5206.6  579.58
  5241.3  579.99  5305.7  582.22  5486.7  586.36  5525.5  587.07  5541.7  587.82
  5553.4  589.30  5586.4  589.82  5595.2  588.68  5598.1  588.11  5614.9  589.84
  5631.2  590.15  5653.5  591.90  5675.9  590.98  5787.7  595.00  5793.8  596.15
#Mann=8,-1,0
  4277.9   0.035       0  4433.7   0.045       0  4992.2   0.045       0
  4996.4   0.045       0  5206.6    0.07       0  5305.7   0.045       0
  5486.7    0.07       0  5595.2   0.045       0
Bank Sta=4992.2,4996.4
Exp/Cntr=0.3,0.1

Type RM Length L Ch R = 1,425,292,292,292
BEGIN DESCRIPTION:
J21874
END DESCRIPTION:
XS GIS Cut Line= 4
      2255139.63     13756431.35      2255157.52     13757120.26
      2255470.68     13757451.32      2256011.02     13757562.96
#Sta/Elev= 30
  4067.2  588.77  4291.2  582.41  4431.0  580.26  4601.9  579.40  4664.8  579.08
  4845.4  578.43  4970.0  578.95  4977.2  578.76  4996.1  576.17  4996.4  575.67
  5000.4  576.17  5014.2  577.02  5026.6  578.61  5040.7  579.28  5097.4  579.68
  5238.3  578.74  5246.6  578.77  5308.9  579.06  5354.1  581.16  5399.2  584.80
  5420.7  585.81  5453.7  585.35  5471.7  586.29  5482.0  585.50  5499.7  587.65
  5512.6  588.20  5584.1  589.72  5655.5  592.41  5665.8  591.68  5763.8  594.81
#Mann=11,-1,0
  4067.2   0.035       0  4291.2   0.045       0  4601.9    0.05       0
  4664.8   0.045       0  4845.4    0.05       0  4996.1    0.05       0
  5000.4    0.05       0  5014.2   0.045       0  5238.3    0.05       0
  5246.6    0.07       0  5453.7   0.045       0
Bank Sta=4996.1,5000.4
Exp/Cntr=0.3,0.1

Type RM Length L Ch R = 1,133,0,0,0
BEGIN DESCRIPTION:
J21873
END DESCRIPTION:
XS GIS Cut Line= 4
      2255103.84     13756462.61      2255023.31     13757308.16
      2255300.68     13757652.63      2255791.38     13757773.08
#Sta/Elev= 30
  3830.2  587.61  3913.0  584.92  4038.1  582.19  4113.9  580.87  4274.6  579.80
  4296.1  580.27  4502.1  579.02  4626.2  580.01  4881.2  578.01  4942.0  577.63
  4974.4  576.48  4978.8  576.22  4995.9  574.80  4996.2  574.30  5000.2  574.80
  5026.8  577.16  5076.4  577.99  5208.7  578.75  5266.3  577.93  5282.2  577.35
  5311.6  578.55  5332.2  582.60  5342.5  582.35  5365.4  579.67  5414.6  579.75
  5424.9  580.37  5435.2  582.25  5489.0  582.71  5548.5  584.85  5627.1  584.95
#Mann=9,-1,0
  3830.2   0.035       0  4038.1   0.045       0  4881.2    0.05       0
  4974.4   0.045       0  4978.8    0.05       0  4995.9    0.05       0
  5000.2    0.05       0  5266.3    0.07       0  5489.0   0.045       0
Bank Sta=4995.9,5000.2
Exp/Cntr=0.3,0.1

Chan Stop Cuts=-1