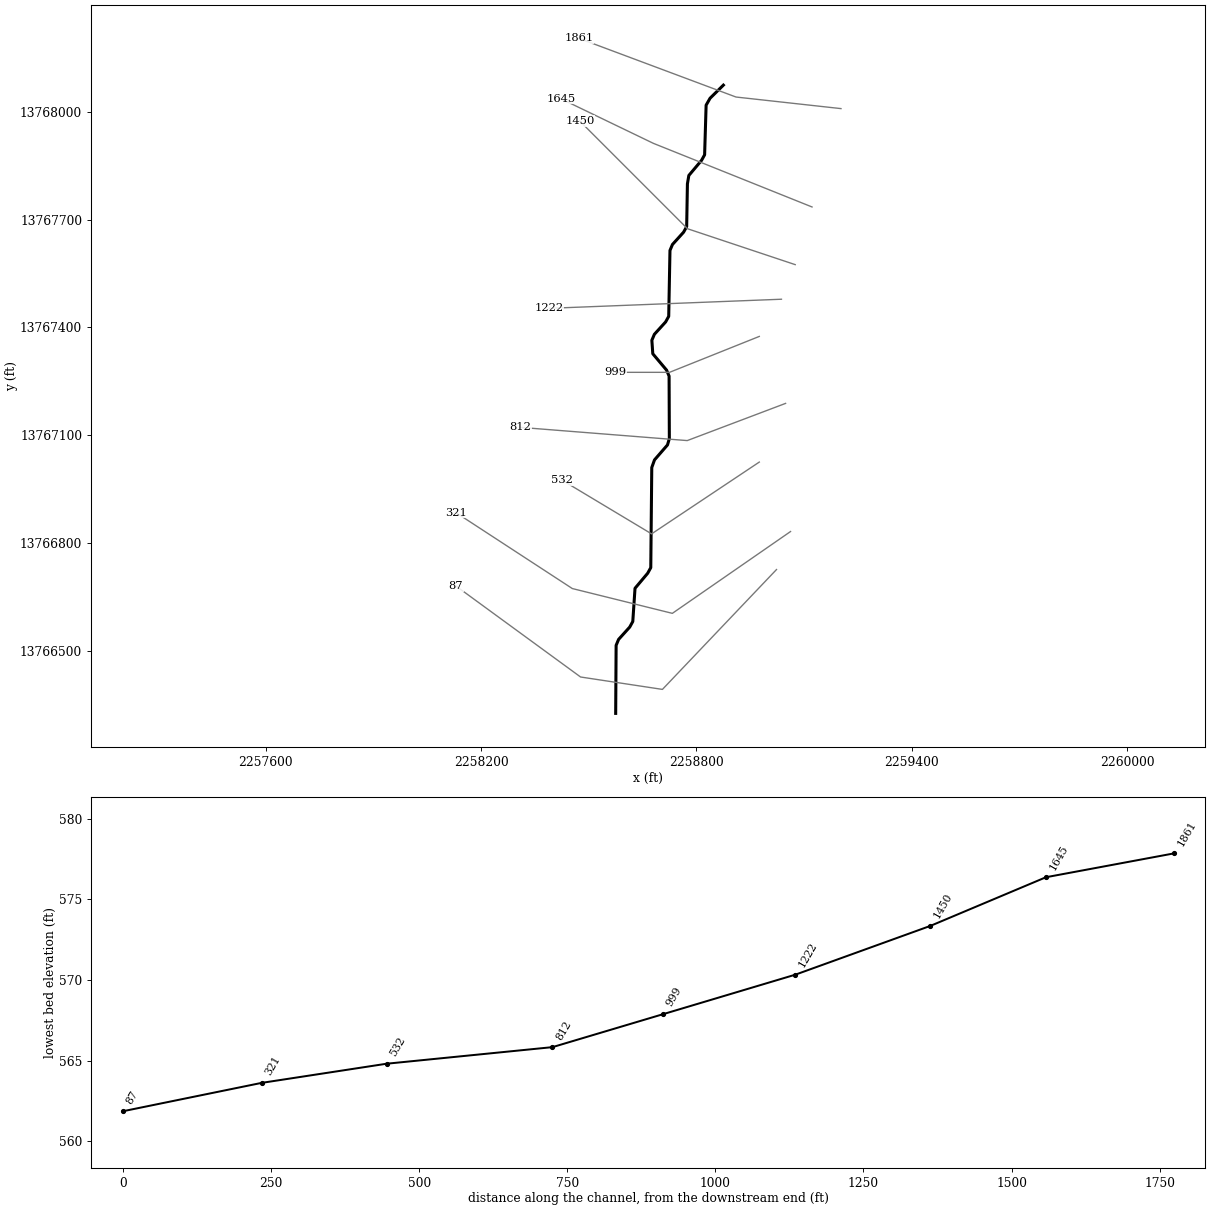
--- YOUNGS TRIBUTARY 9.prj (project) ---

Proj Title=YOUNGS TRIBUTARY 9 Base Level Engineering
Current Plan=p01
Default Exp/Contr=0.3,0.1
English Units
Geom File=g01
Flow File=f01
Plan File=p01
Y Axis Title=Elevation
X Axis Title(PF)=Main Channel Distance
X Axis Title(XS)=Station
BEGIN DESCRIPTION:
YOUNGS TRIBUTARY 9
END DESCRIPTION:
DSS Export Rating Curves= 0
DSS Export Rating Curve Sorted= 0
DSS Export Volume Flow Curves= 0
DXF OffsetX= 0
DXF OffsetY= 0
DXF ScaleX= 1
DXF ScaleY= 10

--- YOUNGS TRIBUTARY 9.p01 (plan) ---

Plan Title=Multiple Run
Short Identifier=Multiple
Geom File=g01
Flow File=f01
Subcritical Flow
K Sum by GR= 0
Std Step Tol= 0.01
Critical Tol= 0.01
Num of Std Step Trials= 20
Max Error Tol= 0.3
Flow Tol Ratio= 0.001
Split Flow NTrial= 30
Split Flow Tol= 0.02
Split Flow Ratio= 0.02
Log Output Level= 0
Friction Slope Method= 1
Unsteady Friction Slope Method= 2
Unsteady Bridges Friction Slope Method= 1
Parabolic Critical Depth
Global Vel Dist=  1 , 1 , 1
Global Log Level= 0
CheckData=True
Encroach Param= -1, 0, 0, 0
BEGIN DESCRIPTION:
Multiple Run
END DESCRIPTION:

--- YOUNGS TRIBUTARY 9.f01 (steady flow) ---

Flow Title=Multiple
Number of Profiles=7
Profile Names=10-year,25-year,50-year,1pct_min,100-year,1pct_plu,500-year
River Rch & RM= YOUNGS TRIBUTARY,Reach-1,1861
     445     708     943     610    1217    2428    2001
Boundary for River Rch & Prof#=YOUNGS TRIBUTARY,Reach-1,1
Up Type=0
Dn Type=3
Dn Slope=0.005
Boundary for River Rch & Prof#=YOUNGS TRIBUTARY,Reach-1,2
Up Type=0
Dn Type=3
Dn Slope=0.005
Boundary for River Rch & Prof#=YOUNGS TRIBUTARY,Reach-1,3
Up Type=0
Dn Type=3
Dn Slope=0.005
Boundary for River Rch & Prof#=YOUNGS TRIBUTARY,Reach-1,4
Up Type=0
Dn Type=3
Dn Slope=0.005
Boundary for River Rch & Prof#=YOUNGS TRIBUTARY,Reach-1,5
Up Type=0
Dn Type=3
Dn Slope=0.005
Boundary for River Rch & Prof#=YOUNGS TRIBUTARY,Reach-1,6
Up Type=0
Dn Type=3
Dn Slope=0.005
Boundary for River Rch & Prof#=YOUNGS TRIBUTARY,Reach-1,7
Up Type=0
Dn Type=3
Dn Slope=0.005

--- YOUNGS TRIBUTARY 9.g01 (geometry) ---

Geom Title=Existing Conditions
Program Version=4.10

River Reach=YOUNGS TRIBUTARY,Reach-1
Reach XY= 30
        2258875.       13768075.      2258837.92      13768038.5
      2258826.91     13768019.21      2258822.73     13767880.94
      2258814.14     13767865.35      2258778.79     13767823.43
      2258774.82     13767800.07      2258772.73     13767680.94
      2258764.14     13767665.36      2258733.14     13767631.06
      2258726.22     13767614.49      2258722.71     13767430.93
      2258714.09     13767415.33      2258682.81     13767380.92
      2258675.77     13767364.31      2258678.37     13767326.74
      2258716.81     13767281.07      2258723.76      13767264.5
      2258724.48     13767090.22      2258719.25     13767072.67
      2258683.14     13767031.06      2258675.52     13767009.78
      2258672.74     13766730.94      2258664.15     13766715.35
      2258628.86      13766673.4      2258622.65     13766580.98
      2258614.11     13766565.37      2258583.13     13766531.06
      2258576.21      13766514.5        2258575.       13766325.

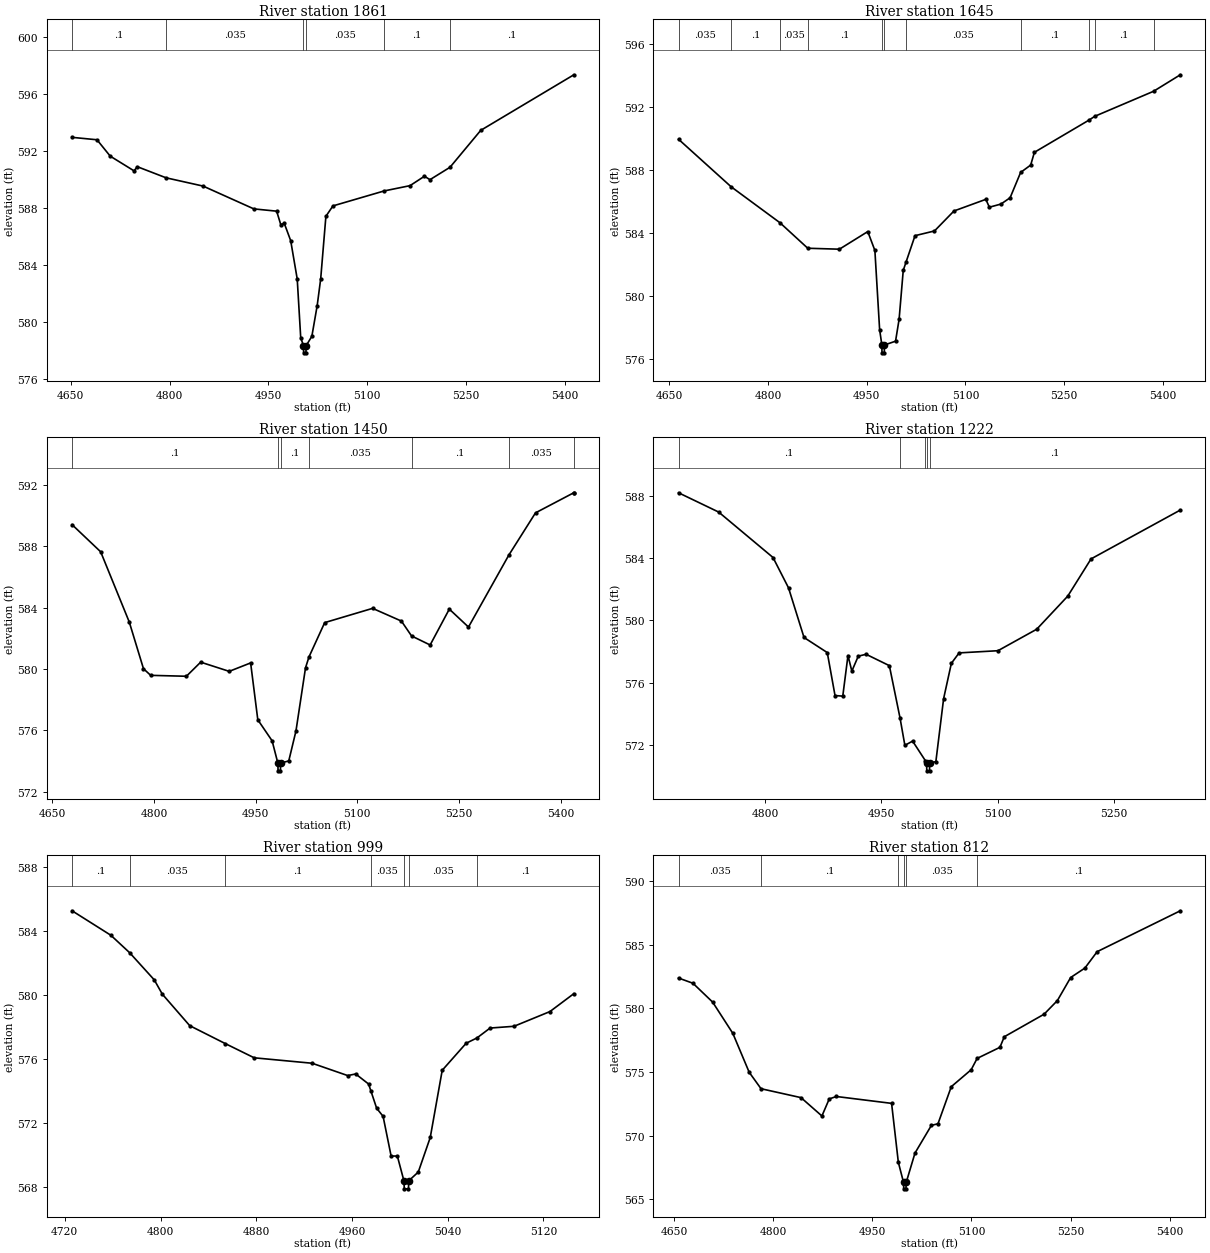
Type RM Length L Ch R = 1 ,1861    ,216,216,216
BEGIN DESCRIPTION:
J21882
END DESCRIPTION:
XS GIS Cut Line= 3
      2259202.59      13768009.6      2258910.13     13768041.84
      2258472.61     13768205.34
#Sta/Elev= 30
  4652.1  592.98  4689.9  592.81    4710  591.66  4746.1  590.63  4751.1  590.92
  4794.8  590.14  4850.9  589.56  4927.9  587.96  4962.5   587.8  4968.7  586.86
  4974.1  586.94  4983.8  585.73  4993.7  583.04    4999  578.92  5003.2  578.36
  5003.4  577.86  5006.9  577.86  5007.2  578.36  5015.9  579.02    5024  581.18
  5029.3  583.05  5037.2  587.44  5047.9  588.17  5125.6  589.22  5164.8  589.59
  5186.7  590.25  5195.1  590.01  5225.5  590.88  5272.1  593.47  5413.4  597.37
#Mann= 6 ,-1 , 0
  4652.1      .1       0  4794.8    .035       0  5003.2    .035       0
  5007.2    .035       0  5125.6      .1       0  5225.5      .1       0
Bank Sta=5003.2,5007.2
XS Rating Curve= 0 ,0
Exp/Cntr=0.3,0.1

Type RM Length L Ch R = 1 ,1645    ,195,195,195
BEGIN DESCRIPTION:
J21881
END DESCRIPTION:
XS GIS Cut Line= 3
      2259121.98     13767735.59      2258679.87     13767912.89
      2258422.01     13768037.22
#Sta/Elev= 30
    4664  589.96  4743.9  586.94  4818.2  584.65  4860.4  583.03  4908.5  582.97
  4951.6  584.09  4962.4  582.89  4969.6  577.86    4973  576.88  4973.2  576.38
  4976.7  576.38    4977  576.88  4993.8  577.12  4999.2  578.51  5005.5  581.62
    5010  582.18  5023.4  583.83    5053  584.13  5082.6   585.4    5131  586.14
  5136.4  585.64    5154  585.84  5167.9  586.24  5183.9  587.85  5199.2  588.32
  5204.8  589.13  5287.9  591.18  5296.6  591.42  5385.9  593.01  5426.6  594.06
#Mann= 11 ,-1 , 0
    4664    .035       0  4743.9      .1       0  4818.2    .035       0
  4860.4      .1       0    4973     .05       0    4977      .1       0
    5010    .035       0  5183.9      .1       0  5287.9      .1       0
  5296.6      .1       0  5385.9      .1       0
Bank Sta=4973,4977
XS Rating Curve= 0 ,0
Exp/Cntr=0.3,0.1

Type RM Length L Ch R = 1 ,1450    ,228,228,228
BEGIN DESCRIPTION:
YOUNGS TRIBUTARY 9 3.0
END DESCRIPTION:
XS GIS Cut Line= 3
      2259075.02     13767574.99        2258775.       13767675.
      2258475.01     13767974.99
#Sta/Elev= 30
  4679.2  589.42  4721.4  587.65  4763.6  583.07  4784.6  580.02  4795.2  579.59
  4847.9  579.53    4869  580.45  4911.1  579.85  4942.7   580.4  4953.3  576.69
  4974.4  575.32  4982.9  573.86  4983.2  573.36  4986.7  573.36  4986.9  573.86
    4999  574.01  5009.6  575.96  5023.7  580.08  5028.8  580.79    5052  583.03
  5122.7  583.96  5165.2  583.13  5180.2  582.16  5207.6  581.57  5235.9  583.91
  5264.2  582.74  5323.8  587.44  5363.1  590.19  5419.5   591.5  5419.7   591.5
#Mann= 7 ,-1 , 0
  4679.2      .1       0  4982.9     .05       0  4986.9      .1       0
  5028.8    .035       0  5180.2      .1       0  5323.8    .035       0
  5419.5      .1       0
Bank Sta=4982.9,4986.9
XS Rating Curve= 0 ,0
Exp/Cntr=0.3,0.1

Type RM Length L Ch R = 1 ,1222    ,223,223,223
BEGIN DESCRIPTION:
J21880
END DESCRIPTION:
XS GIS Cut Line= 2
      2259036.77     13767478.62      2258389.87     13767453.29
#Sta/Elev= 30
  4688.4   588.2  4740.2  586.96  4810.3  584.04  4830.3  582.09  4850.3   578.9
  4880.3  577.93  4890.3  575.17  4900.3  575.13    4907  577.74    4912  576.74
  4920.3   577.7  4930.4  577.82  4960.4  577.09  4974.2  573.72  4980.4  571.97
  4990.4  572.24  5006.9  570.98  5008.4  570.83  5008.7  570.33  5012.2  570.33
  5012.4  570.83  5020.4  570.92  5030.4  574.97  5040.4  577.24  5050.4  577.91
  5100.5  578.05  5150.5  579.43  5190.6  581.56  5220.6  583.95  5335.8  587.09
#Mann= 5 ,-1 , 0
  4688.4      .1       0  4974.2    .035       0  5006.9      .1       0
  5008.4    .035       0  5012.4      .1       0
Bank Sta=5008.4,5012.4
XS Rating Curve= 0 ,0
Exp/Cntr=0.3,0.1

Type RM Length L Ch R = 1 ,999     ,187,187,187
BEGIN DESCRIPTION:
YOUNGS TRIBUTARY 9 2.0
END DESCRIPTION:
XS GIS Cut Line= 3
      2258975.04     13767375.02        2258725.       13767275.
        2258575.       13767275.
#Sta/Elev= 30
  4726.1  585.26  4758.5  583.73  4774.2  582.64  4794.8  580.94  4801.5  580.05
  4824.4  578.08  4854.1  576.96  4878.3  576.07  4926.7  575.73  4956.4  574.96
  4963.1  575.06  4973.9  574.43  4975.8     574  4980.6  572.92    4986  572.41
  4992.7  569.93  4997.9  569.93  5003.4  568.38  5003.7  567.88  5007.2  567.88
  5007.4  568.38  5015.4  568.93  5025.4  571.09  5035.4  575.29  5055.4  576.98
  5064.4  577.31  5075.4  577.93  5095.4  578.04  5125.4  578.96  5145.4  580.08
#Mann= 7 ,-1 , 0
  4726.1      .1       0  4774.2    .035       0  4854.1      .1       0
  4975.8    .035       0  5003.4    .035       0  5007.4    .035       0
  5064.4      .1       0
Bank Sta=5003.4,5007.4
XS Rating Curve= 0 ,0
Exp/Cntr=0.3,0.1

Type RM Length L Ch R = 1 ,812     ,280,280,280
BEGIN DESCRIPTION:
J21879
END DESCRIPTION:
XS GIS Cut Line= 3
      2259048.28     13767188.48      2258774.28     13767084.87
      2258309.57     13767121.68
#Sta/Elev= 30
  4656.9  582.38  4678.7  581.97  4708.5  580.49    4739  578.04  4763.8  574.98
  4781.7  573.69  4842.2  572.99  4873.8  571.55  4884.9  572.89  4895.6  573.08
  4979.2  572.54  4989.4  567.92  4997.3  566.33  4997.5  565.83    5001  565.83
  5001.3  566.33  5014.6  568.64  5039.4  570.81  5049.4  570.94  5069.5  573.85
  5099.6  575.18  5108.6  576.07  5143.1  576.94  5149.7  577.77  5209.9  579.54
    5230  580.61  5250.1  582.42  5271.6  583.16  5290.2  584.45    5416  587.66
#Mann= 6 ,-1 , 0
  4656.9    .035       0  4781.7      .1       0  4989.4    .035       0
  4997.3    .035       0  5001.3    .035       0  5108.6      .1       0
Bank Sta=4997.3,5001.3
XS Rating Curve= 0 ,0
Exp/Cntr=0.3,0.1

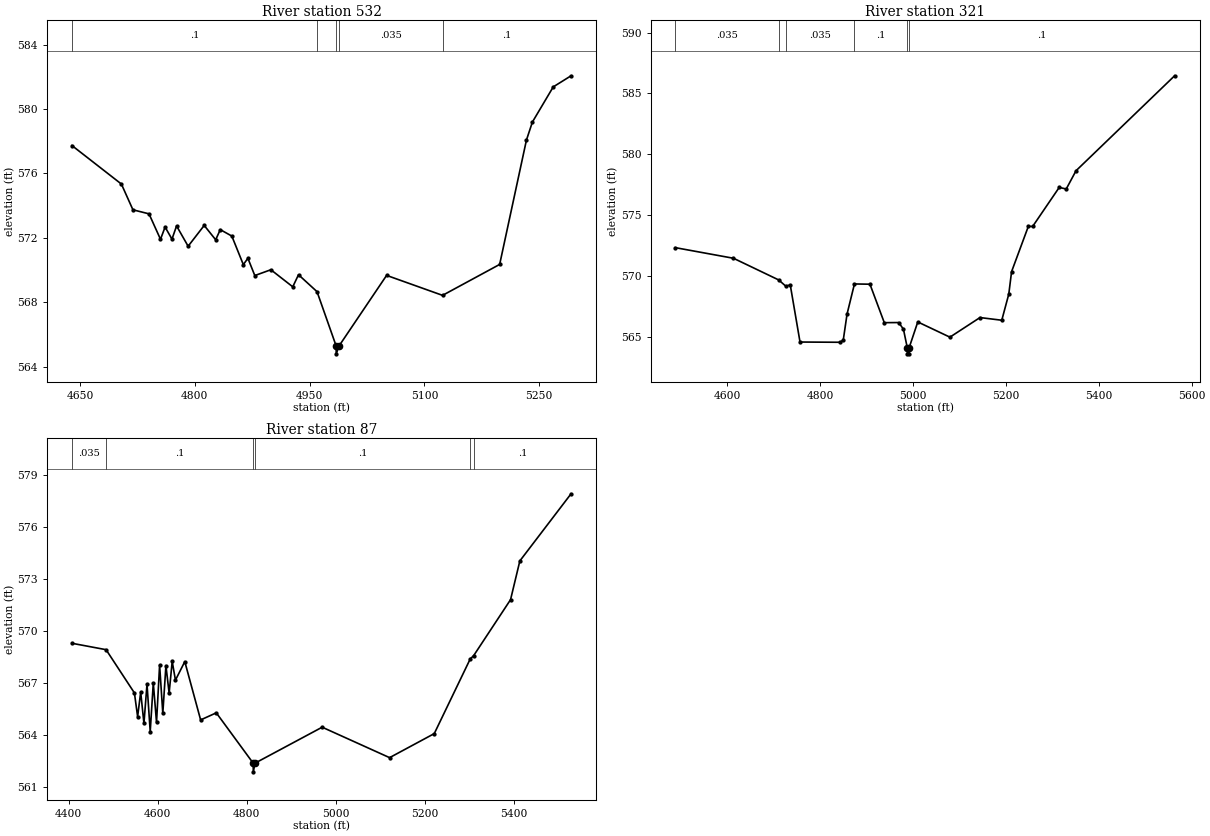
Type RM Length L Ch R = 1 ,532     ,211,211,211
BEGIN DESCRIPTION:
YOUNGS TRIBUTARY 9 1.0
END DESCRIPTION:
XS GIS Cut Line= 3
      2258975.03     13767025.02        2258675.       13766825.
      2258425.03     13766974.98
#Sta/Elev= 30
  4639.5  577.73  4704.1  575.34  4719.2  573.74  4740.2  573.49  4755.2  571.91
  4761.2  572.67  4770.2  571.92  4776.2  572.74  4791.3  571.48  4812.3  572.77
  4827.3  571.88  4833.3  572.51  4848.4  572.11  4863.4  570.34  4869.4  570.73
  4878.4  569.66  4899.4  570.02    4928  568.96  4935.5  569.71  4959.7  568.66
  4984.6   565.3  4984.8   564.8  4988.6   565.3  5050.6  569.67  5123.7  568.43
  5198.3  570.35  5233.3  578.07  5241.1  579.19  5268.3  581.37  5291.6  582.06
#Mann= 5 ,-1 , 0
  4639.5      .1       0  4959.7    .035       0  4984.6    .035       0
  4988.6    .035       0  5123.7      .1       0
Bank Sta=4984.6,4988.6
XS Rating Curve= 0 ,0
Exp/Cntr=0.3,0.1

Type RM Length L Ch R = 1 ,321     ,234,234,234
BEGIN DESCRIPTION:
J21878
END DESCRIPTION:
XS GIS Cut Line= 4
      2259062.08     13766831.56      2258732.83     13766603.62
      2258454.21      13766672.7      2258129.77     13766884.39
#Sta/Elev= 30
  4488.4  572.33  4613.3  571.46  4710.7  569.68  4725.9  569.17  4735.6  569.27
  4756.6  564.58  4843.1  564.56  4849.7  564.73  4857.9  566.88  4873.8  569.35
  4907.2  569.33  4938.1  566.17    4969  566.18  4979.3  565.64  4987.6  564.11
  4987.9  563.61  4991.4  563.61  4991.6  564.11  5010.2  566.23  5079.4  564.98
  5144.2  566.59  5191.1  566.37  5206.2  568.52  5212.2  570.36  5248.4  574.09
  5257.5  574.07  5314.8  577.28  5329.9  577.15    5351  578.65  5563.3  586.45
#Mann= 6 ,-1 , 0
  4488.4    .035       0  4710.7      .1       0  4725.9    .035       0
  4873.8      .1       0  4987.6     .05       0  4991.6      .1       0
Bank Sta=4987.6,4991.6
XS Rating Curve= 0 ,0
Exp/Cntr=0.3,0.1

Type RM Length L Ch R = 1 ,87      ,0,0,0
BEGIN DESCRIPTION:
J21877
END DESCRIPTION:
XS GIS Cut Line= 4
      2259022.98     13766725.68       2258705.2     13766391.78
      2258477.24     13766426.32       2258129.9     13766679.96
#Sta/Elev= 30
  4407.3  569.28    4484  568.91  4547.7  566.41  4554.9  565.04  4561.8  566.46
  4569.1  564.65    4576  566.92  4583.2  564.18  4590.1  566.98  4597.4  564.71
  4604.3  568.02  4611.5  565.23  4618.5  567.99  4625.7   566.4  4632.6  568.23
  4639.9  567.15  4660.9  568.22  4696.5  564.85  4731.7  565.26  4814.6  562.35
  4814.9  561.85  4818.6  562.35  4969.6  564.43  5121.1  562.67  5221.5  564.06
  5302.2  568.37  5310.1  568.57  5392.9   571.8  5413.8  574.04  5528.9  577.92
#Mann= 6 ,-1 , 0
  4407.3    .035       0    4484      .1       0  4814.6     .05       0
  4818.6      .1       0  5302.2     .12       0  5310.1      .1       0
Bank Sta=4814.6,4818.6
XS Rating Curve= 0 ,0
Exp/Cntr=0.3,0.1

Chan Stop Cuts=-1
Use User Specified Reach Order=0
Composite Channel Slope=5