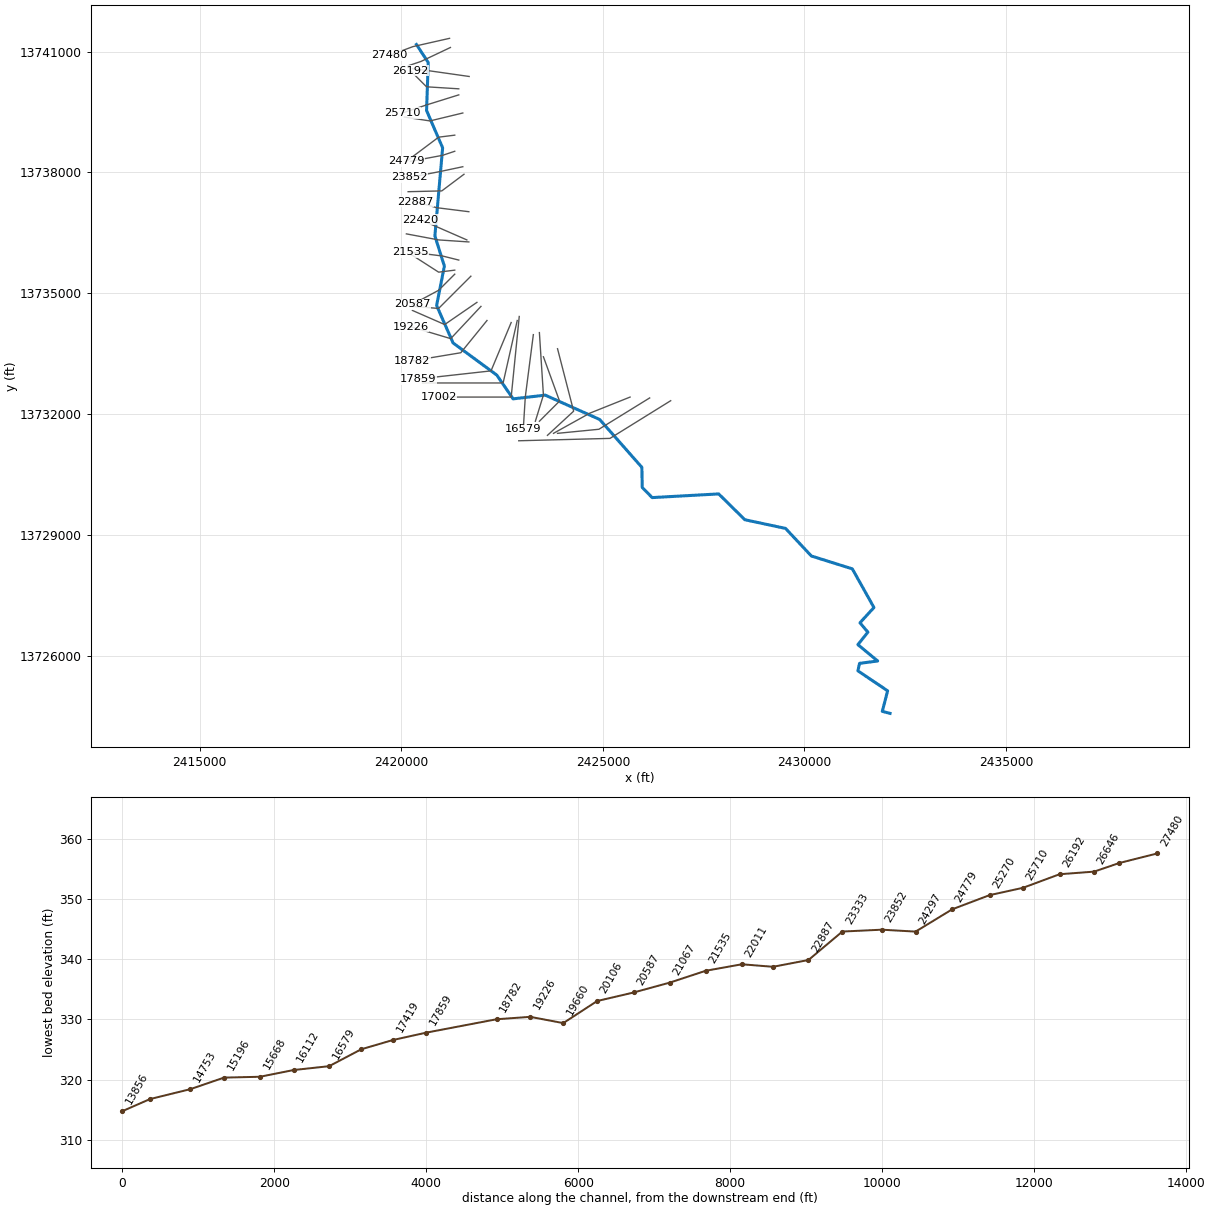
--- ANSWORTH BRANCH.prj (project) ---

Proj Title=ANSWORTH BRANCH Base Level Engineering
Current Plan=p01
Default Exp/Contr=0.3,0.1
English Units
Geom File=g01
Flow File=f01
Plan File=p01
Y Axis Title=Elevation
X Axis Title(PF)=Main Channel Distance
X Axis Title(XS)=Station
BEGIN DESCRIPTION:
ANSWORTH BRANCH
END DESCRIPTION:
DSS Export Rating Curves= 0
DSS Export Rating Curve Sorted= 0
DSS Export Volume Flow Curves= 0
DXF OffsetX= 0
DXF OffsetY= 0
DXF ScaleX= 1
DXF ScaleY= 10

--- ANSWORTH BRANCH.p01 (plan) ---

Plan Title=Multiple Run
Short Identifier=Multiple
Geom File=g01
Flow File=f01
Subcritical Flow
K Sum by GR= 0
Std Step Tol= 0.01
Critical Tol= 0.01
Num of Std Step Trials= 20
Max Error Tol= 0.3
Flow Tol Ratio= 0.001
Split Flow NTrial= 30
Split Flow Tol= 0.02
Split Flow Ratio= 0.02
Log Output Level= 0
Friction Slope Method= 1
Unsteady Friction Slope Method= 2
Unsteady Bridges Friction Slope Method= 1
Parabolic Critical Depth
Global Vel Dist=  1 , 1 , 1
Global Log Level= 0
CheckData=True
Encroach Param= -1, 0, 0, 0
BEGIN DESCRIPTION:
Multiple Run
END DESCRIPTION:

--- ANSWORTH BRANCH.f01 (steady flow) ---

Flow Title=Multiple
Number of Profiles=7
Profile Names=10-year,25-year,50-year,1pct_min,100-year,1pct_plu,500-year
River Rch & RM= ANSWORTH BRANCH,Reach-1,27480
     709    1142    1533     995    1986    3962    3301
River Rch & RM= ANSWORTH BRANCH,Reach-1,26646
     948    1550    2099    1374    2741    5469    4634
River Rch & RM= ANSWORTH BRANCH,Reach-1,22887
    1167    1920    2611    1715    3421    6827    5823
River Rch & RM= ANSWORTH BRANCH,Reach-1,16579
    1754    2936    4040    2680    5348   10670    9291
River Rch & RM= ANSWORTH BRANCH,Reach-1,14753
    2233    3761    5195    3456    6896   13760   12053
Boundary for River Rch & Prof#=ANSWORTH BRANCH,Reach-1,1
Up Type=0
Dn Type=3
Dn Slope=0.005
Boundary for River Rch & Prof#=ANSWORTH BRANCH,Reach-1,2
Up Type=0
Dn Type=3
Dn Slope=0.005
Boundary for River Rch & Prof#=ANSWORTH BRANCH,Reach-1,3
Up Type=0
Dn Type=3
Dn Slope=0.005
Boundary for River Rch & Prof#=ANSWORTH BRANCH,Reach-1,4
Up Type=0
Dn Type=3
Dn Slope=0.005
Boundary for River Rch & Prof#=ANSWORTH BRANCH,Reach-1,5
Up Type=0
Dn Type=3
Dn Slope=0.005
Boundary for River Rch & Prof#=ANSWORTH BRANCH,Reach-1,6
Up Type=0
Dn Type=3
Dn Slope=0.005
Boundary for River Rch & Prof#=ANSWORTH BRANCH,Reach-1,7
Up Type=0
Dn Type=3
Dn Slope=0.005

--- ANSWORTH BRANCH.g01 (geometry) ---

Geom Title=Existing Conditions
Program Version=4.10

River Reach=ANSWORTH BRANCH ,Reach-1
Reach XY= 30
        2420375.       13741175.      2420666.76     13740728.24
       2420626.2      13739535.5      2421024.32     13738611.08
      2420832.33      13736424.9      2421067.68      13735674.9
      2420874.89     13734697.68      2421283.14     13733768.94
      2422369.38     13732969.38      2422772.56     13732380.39
      2423569.06     13732472.74      2424919.75     13731869.55
      2425967.15     13730681.19      2425976.96     13730180.89
      2426222.55     13729930.45      2427873.41     13730021.18
      2428522.56     13729380.39      2429531.61     13729165.57
      2430172.57     13728480.52      2431188.57     13728161.53
      2431725.29     13727202.23      2431378.08     13726823.32
      2431575.11     13726590.36      2431326.69     13726280.64
      2431817.69      13725875.1        2431368.     13725816.18
      2431327.16     13725630.44      2432064.53     13725134.83
      2431932.31     13724624.88        2432125.       13724575.

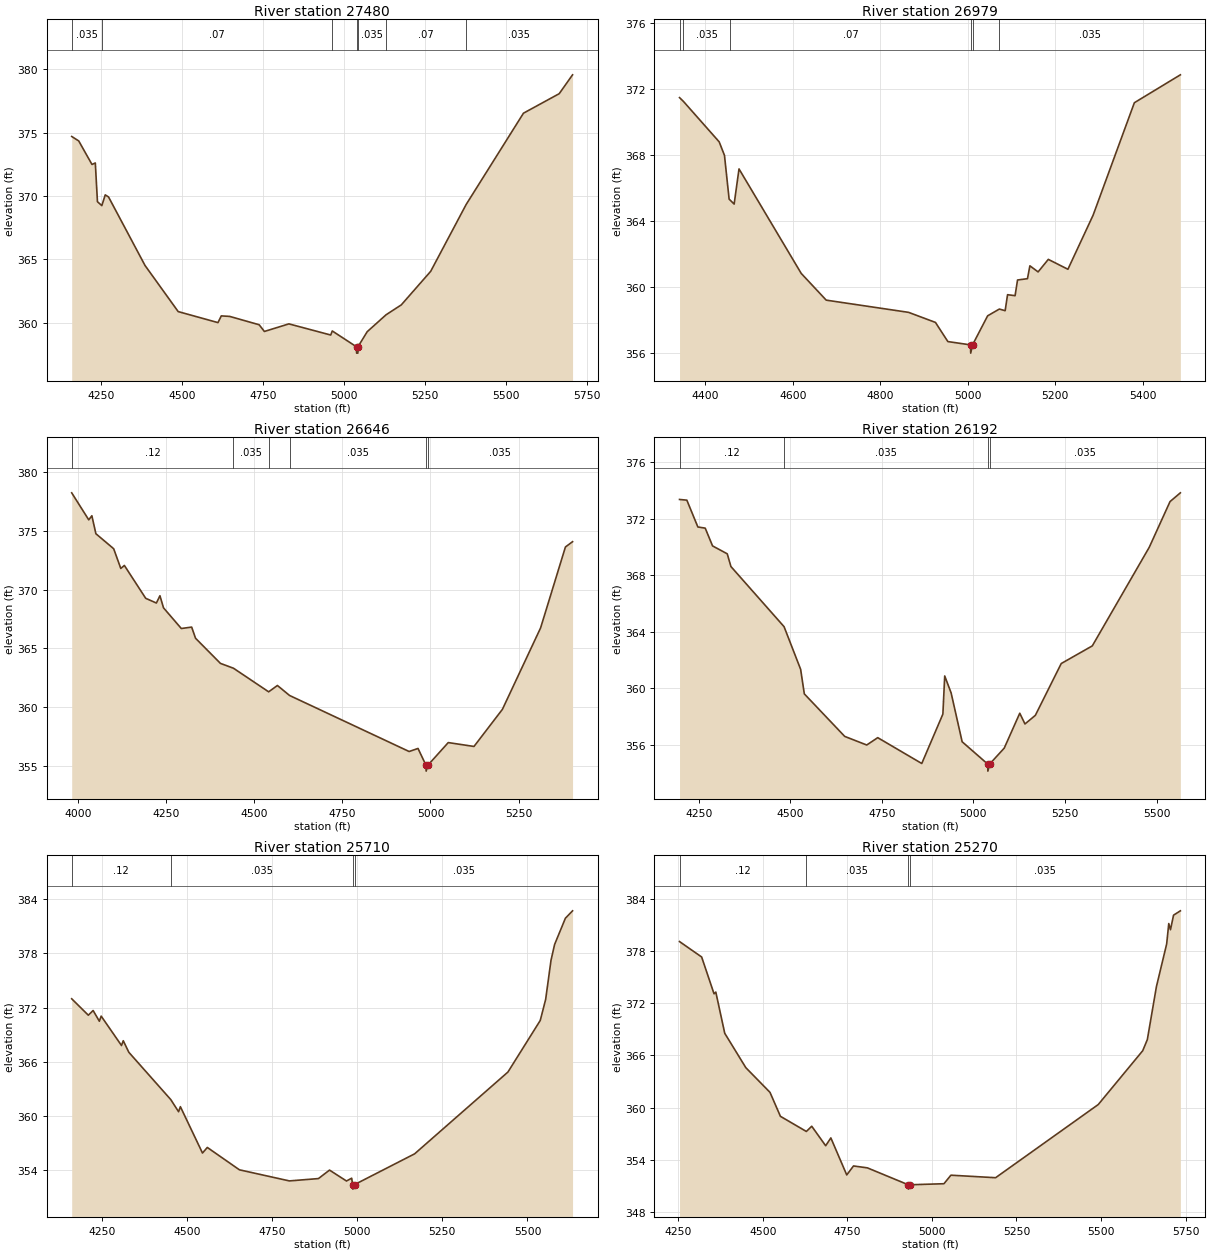
Type RM Length L Ch R = 1 ,27480   ,501,501,501
BEGIN DESCRIPTION:
X18068
END DESCRIPTION:
XS GIS Cut Line= 3
      2421196.17     13741327.89      2420287.56     13741122.37
       2419709.4     13740906.24
#Sta/Elev= 30
    4158   374.7  4179.7  374.35  4220.7  372.49    4231  372.61  4237.6  369.55
  4251.2  369.24  4261.7  370.09    4272  369.92  4384.8  364.51  4487.3  360.87
  4610.3     360  4620.6  360.53  4646.6  360.49  4737.7  359.83  4753.8   359.3
  4829.6   359.9  4958.9  359.02  4963.8  359.34  5038.7  358.09    5039  357.59
  5042.9  357.59  5043.2  358.09  5071.7  359.28  5130.2  360.62  5177.2   361.4
  5268.1  364.05  5377.8  369.33    5555  376.54  5665.5  378.08  5706.8  379.57
#Mann= 7 ,-1 , 0
    4158    .035       0  4251.2     .07       0  4963.8    .035       0
  5038.7    .035       0  5043.2    .035       0  5130.2     .07       0
  5377.8    .035       0
Bank Sta=5038.7,5043.2
XS Rating Curve= 0 ,0
Exp/Cntr=0.3,0.1

Type RM Length L Ch R = 1 ,26979   ,333,333,333
BEGIN DESCRIPTION:
X18067
END DESCRIPTION:
XS GIS Cut Line= 3
      2421217.81     13741100.73      2420487.67     13740754.59
       2420169.3     13740646.67
#Sta/Elev= 30
  4341.4  371.48  4350.3  371.25    4432   368.8  4444.1  367.98  4454.7  365.33
  4457.8  365.25  4466.2  365.03  4477.3  367.16  4619.4  360.83  4676.5  359.21
  4864.7  358.47  4926.1  357.86  4954.4   356.7  5006.2   356.5  5006.6     356
  5010.8   356.5  5045.3  358.26  5072.1  358.67  5085.3  358.57  5090.8  359.54
    5108  359.48  5113.6  360.43  5136.3  360.51  5141.8  361.29  5160.6  360.92
  5183.9  361.68  5228.7  361.08  5286.3  364.36  5380.5  371.17  5485.6  372.86
#Mann= 6 ,-1 , 0
  4341.4     .07       0  4350.3    .035       0  4457.8     .07       0
  5006.2     .05       0  5010.8     .07       0  5072.1    .035       0
Bank Sta=5006.2,5010.8
XS Rating Curve= 0 ,0
Exp/Cntr=0.3,0.1

Type RM Length L Ch R = 1 ,26646   ,454,454,454
BEGIN DESCRIPTION:
ANSWORTH BRANCH 38.0
END DESCRIPTION:
XS GIS Cut Line= 3
      2421682.91     13740381.41        2420675.       13740525.
        2420275.       13740575.
#Sta/Elev= 30
  3981.9  378.25  4030.3  375.95  4039.1   376.3  4050.5  374.77    4101  373.49
  4121.2  371.81  4131.3  372.07  4191.9  369.27  4222.2  368.87  4232.3  369.49
  4242.4  368.46  4292.9   366.7  4322.3  366.82  4333.3  365.87    4404  363.73
  4440.9  363.32  4540.8  361.31  4565.6  361.85  4600.1     361  4939.4  356.23
  4964.6  356.49  4987.2  355.06  4987.7  354.56  4992.5  355.06  5050.4  356.99
  5123.4  356.66  5204.1  359.82  5312.4  366.75  5382.9  373.64  5403.1  374.09
#Mann= 6 ,-1 , 0
  3981.9     .12       0  4440.9    .035       0  4540.8     .07       0
  4600.1    .035       0  4987.2    .035       0  4992.5    .035       0
Bank Sta=4987.2,4992.5
XS Rating Curve= 0 ,0
Exp/Cntr=0.3,0.1

Type RM Length L Ch R = 1 ,26192   ,482,482,482
BEGIN DESCRIPTION:
ANSWORTH BRANCH 37.0
END DESCRIPTION:
XS GIS Cut Line= 3
        2421425.       13740075.        2420625.       13740125.
      2420225.03     13740524.97
#Sta/Elev= 30
  4197.8  373.37  4217.8  373.32  4247.9  371.42  4267.9  371.34    4288  370.08
  4328.1  369.52  4338.1  368.62  4483.2  364.36  4528.4  361.34  4538.5   359.6
  4648.7  356.59  4708.8  355.98  4738.9   356.5  4859.1  354.67  4916.7  358.17
  4921.7  360.87  4939.2  359.67  4969.3  356.21  5039.1  354.63  5039.5  354.13
  5044.4  354.63  5084.2  355.76  5126.6  358.23  5140.8  357.47  5169.1  358.08
  5239.8  361.75  5324.6     363  5480.2  369.99  5536.8  373.22    5565  373.84
#Mann= 4 ,-1 , 0
  4197.8     .12       0  4483.2    .035       0  5039.1    .035       0
  5044.4    .035       0
Bank Sta=5039.1,5044.4
XS Rating Curve= 0 ,0
Exp/Cntr=0.3,0.1

Type RM Length L Ch R = 1 ,25710   ,440,440,440
BEGIN DESCRIPTION:
ANSWORTH BRANCH 36.0
END DESCRIPTION:
XS GIS Cut Line= 3
      2421425.04     13739925.01        2420625.       13739675.
      2420025.05     13739475.02
#Sta/Elev= 30
  4161.7  372.97  4210.5  371.15  4224.6  371.67  4242.9  370.48  4248.2  371.05
  4307.9  367.79  4313.1  368.32  4329.4  367.04  4452.5   361.8  4475.5  360.45
  4480.8  361.01  4545.7  355.87  4559.9  356.49  4654.2  354.01  4800.8  352.78
  4886.2  353.04  4918.7  353.98  4968.5  352.77  4983.7  353.08  4986.7  352.37
  4987.2  351.87  4992.1  352.37  5168.5  355.78  5442.6  364.85  5537.5  370.57
  5553.3   372.9  5569.1  377.25  5579.6  378.99  5611.3   381.9  5632.3  382.72
#Mann= 4 ,-1 , 0
  4161.7     .12       0  4452.5    .035       0  4986.7    .035       0
  4992.1    .035       0
Bank Sta=4986.7,4992.1
XS Rating Curve= 0 ,0
Exp/Cntr=0.3,0.1

Type RM Length L Ch R = 1 ,25270   ,491,491,491
BEGIN DESCRIPTION:
ANSWORTH BRANCH 35.0
END DESCRIPTION:
XS GIS Cut Line= 3
      2421524.99       13739475.      2420709.42     13739278.07
      2420074.99       13739375.
#Sta/Elev= 30
    4254  379.07  4319.4   377.3  4356.1  373.07  4361.3  373.27  4387.7  368.54
  4450.1  364.59  4521.5  361.76  4552.3  359.01    4629  357.27  4644.9  357.87
  4686.1  355.63  4701.4  356.53  4748.4  352.28  4768.4  353.31  4809.5  353.09
  4930.3  351.15  4930.7  350.65  4935.7  351.15  5035.8  351.27  5056.4  352.25
  5188.5  351.96    5492  360.36  5623.5  366.54  5637.1  367.81    5664   373.9
  5694.3   378.8  5700.5  381.14  5705.6  380.43  5714.6   382.1  5734.8   382.6
#Mann= 4 ,-1 , 0
    4254     .12       0    4629    .035       0  4930.3    .035       0
  4935.7    .035       0
Bank Sta=4930.3,4935.7
XS Rating Curve= 0 ,0
Exp/Cntr=0.3,0.1

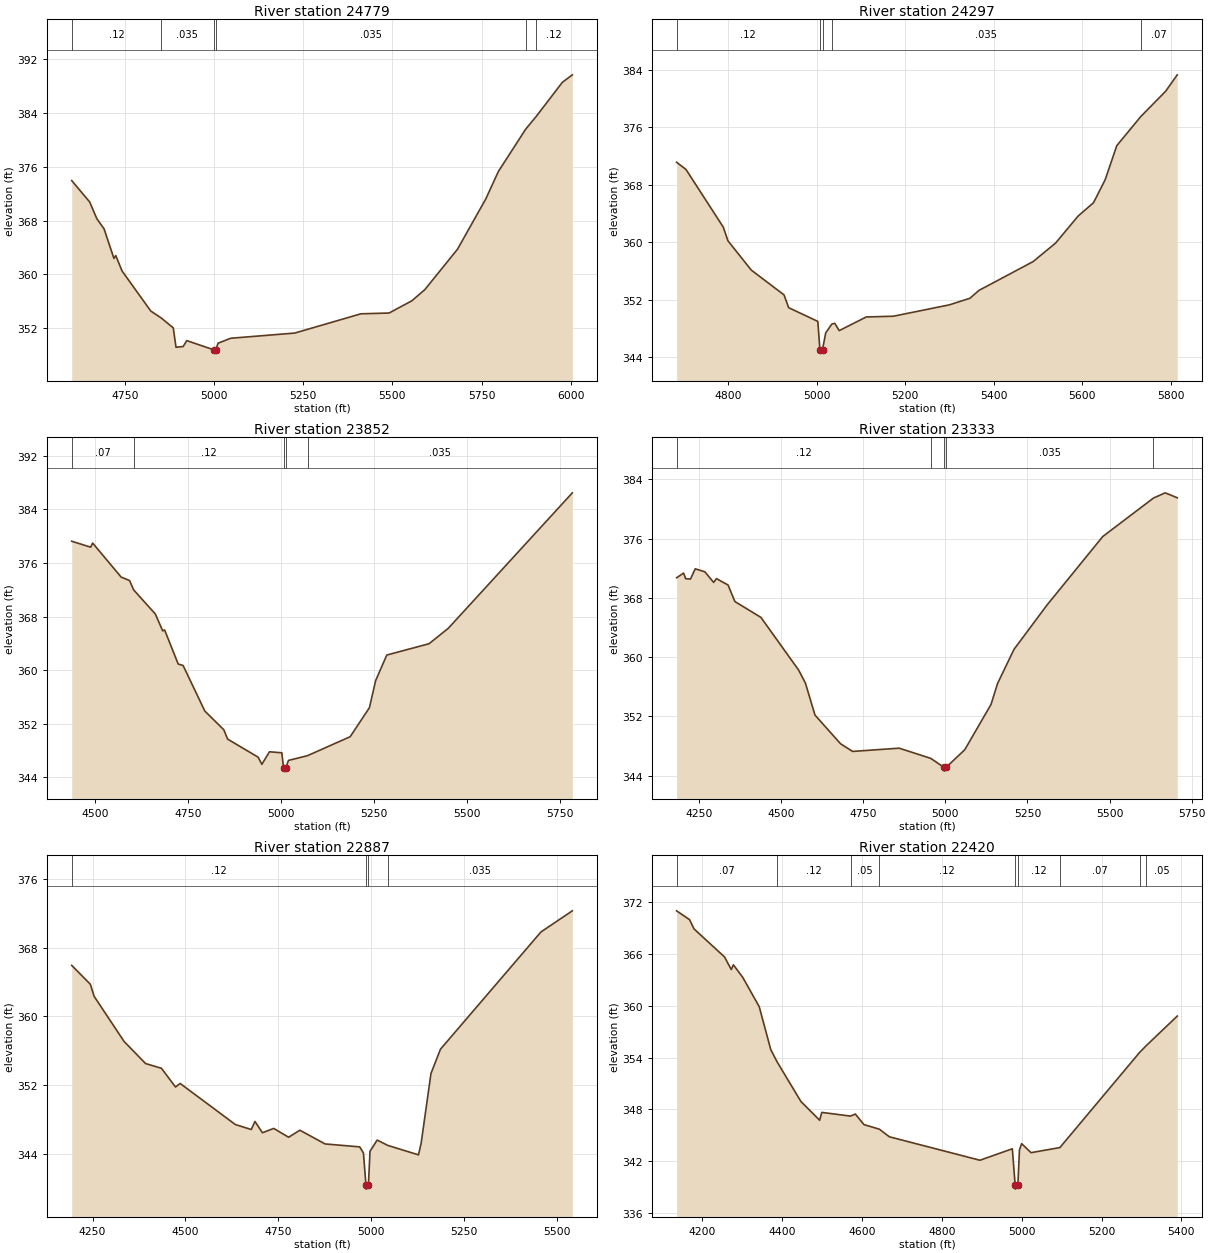
Type RM Length L Ch R = 1 ,24779   ,482,482,482
BEGIN DESCRIPTION:
ANSWORTH BRANCH 34.0
END DESCRIPTION:
XS GIS Cut Line= 3
        2421325.       13738925.        2420925.       13738875.
      2420125.01     13738275.01
#Sta/Elev= 30
  4601.3  373.94  4651.7  370.76  4671.8  368.27    4692  366.77  4719.7  362.37
  4724.8   362.8  4742.4  360.51    4823  354.55    4852  353.53    4886  352.05
  4893.6  349.17  4913.7  349.28  4923.8  350.16    4999   348.8  4999.5   348.3
  5004.7   348.8  5011.7  349.78  5047.1  350.51  5226.3  351.28  5411.7  354.14
  5490.9  354.26  5554.4  356.07  5590.9  357.73  5682.5  363.74  5761.7   371.2
  5797.1  375.29  5873.7  381.58    5903  383.46  5976.3  388.53  6004.4  389.65
#Mann= 6 ,-1 , 0
  4601.3     .12       0    4852    .035       0    4999    .035       0
  5004.7    .035       0  5873.7     .07       0    5903     .12       0
Bank Sta=4999,5004.7
XS Rating Curve= 0 ,0
Exp/Cntr=0.3,0.1

Type RM Length L Ch R = 1 ,24297   ,445,445,445
BEGIN DESCRIPTION:
ANSWORTH BRANCH 33.0
END DESCRIPTION:
XS GIS Cut Line= 3
      2421325.04     13738525.01        2421025.       13738425.
      2420225.01       13738275.
#Sta/Elev= 30
  4684.1  371.13  4705.2  370.14  4789.5  362.11  4800.1   360.2  4852.8  356.13
  4926.6  352.69  4937.1  350.91  5002.9     349  5007.6  345.09  5008.1  344.59
    5013  344.59  5013.5  345.09  5020.7   347.4  5034.5  348.63  5041.1  348.74
  5051.2  347.72  5112.3  349.62  5173.3  349.72  5299.7   351.3  5346.3  352.22
  5366.6  353.31  5488.7  357.31  5539.6  359.89  5590.5  363.65  5625.2   365.5
  5651.5  368.69  5677.8  373.44    5732  377.49    5788     381  5814.3  383.29
#Mann= 5 ,-1 , 0
  4684.1     .12       0  5007.6     .05       0  5013.5     .12       0
  5034.5    .035       0    5732     .07       0
Bank Sta=5007.6,5013.5
XS Rating Curve= 0 ,0
Exp/Cntr=0.3,0.1

Type RM Length L Ch R = 1 ,23852   ,519,519,519
BEGIN DESCRIPTION:
ANSWORTH BRANCH 32.0
END DESCRIPTION:
XS GIS Cut Line= 3
      2421524.94      13738141.7        2420975.       13738025.
        2420206.     13737875.94
#Sta/Elev= 30
  4437.9  379.25    4489  378.36  4494.2  378.98  4570.7   373.9  4593.5  373.37
  4604.3  371.99  4662.7  368.38  4682.5  365.86  4687.6     366  4724.1  360.91
  4737.3  360.69  4795.6  353.89  4846.7  351.09    4857  349.69  4938.8     347
    4949  345.93  4969.4   347.8  5002.6  347.65  5007.3  345.41  5007.8  344.91
  5013.3  345.41  5020.5  346.51  5071.7  347.22  5186.3  350.05    5238  354.38
  5254.7  358.42  5284.7  362.25  5398.3  363.94  5450.1  366.25  5783.4  386.48
#Mann= 5 ,-1 , 0
  4437.9     .07       0  4604.3     .12       0  5007.3     .05       0
  5013.3     .12       0  5071.7    .035       0
Bank Sta=5007.3,5013.3
XS Rating Curve= 0 ,0
Exp/Cntr=0.3,0.1

Type RM Length L Ch R = 1 ,23333   ,446,446,446
BEGIN DESCRIPTION:
ANSWORTH BRANCH 31.0
END DESCRIPTION:
XS GIS Cut Line= 3
      2421554.45      13737954.7      2421003.24      13737541.3
      2420168.28     13737521.65
#Sta/Elev= 30
    4182  370.71  4203.3  371.34  4209.5  370.59  4224.1  370.53  4238.7  371.92
  4267.9  371.52  4294.9  370.08  4303.3   370.6  4338.7  369.73  4359.5   367.5
  4438.7  365.36  4553.3  358.26  4574.1   356.5  4603.3  352.17  4681.3  348.29
  4717.9  347.26  4859.5   347.7    4956  346.32  4996.2   345.1  4996.7   344.6
  5002.3   345.1  5059.3  347.49  5139.3  353.61  5159.3  356.45  5209.3  361.05
  5309.4  367.01  5479.4  376.28  5633.7  381.47  5669.5  382.18  5706.2  381.51
#Mann= 5 ,-1 , 0
    4182     .12       0    4956    .035       0  4996.2    .035       0
  5002.3    .035       0  5633.7     .12       0
Bank Sta=4996.2,5002.3
XS Rating Curve= 0 ,0
Exp/Cntr=0.3,0.1

Type RM Length L Ch R = 1 ,22887   ,467,467,467
BEGIN DESCRIPTION:
ANSWORTH BRANCH 30.0
END DESCRIPTION:
XS GIS Cut Line= 3
      2421674.95     13737025.01        2420875.       13737125.
      2420353.68     13737275.53
#Sta/Elev= 30
  4193.8  365.92  4244.1  363.72  4254.2  362.32  4334.8  357.07  4392.8  354.49
  4435.6  353.94  4473.4  351.76    4486  352.17  4634.7  347.39  4677.5  346.81
  4687.6  347.75  4707.7  346.43    4738  346.94  4778.3  345.91  4808.5  346.73
  4876.5  345.13  4969.7  344.79  4979.8  344.08  4986.5  340.37    4987  339.87
  4993.2  340.37  4997.5  344.28  5016.8  345.58  5045.4  344.96  5128.1  343.86
  5135.3  345.23  5161.7  353.33  5187.3  356.16    5458  369.81  5542.6  372.27
#Mann= 4 ,-1 , 0
  4193.8     .12       0  4986.5     .05       0  4993.2     .12       0
  5045.4    .035       0
Bank Sta=4986.5,4993.2
XS Rating Curve= 0 ,0
Exp/Cntr=0.3,0.1

Type RM Length L Ch R = 1 ,22420   ,409,409,409
BEGIN DESCRIPTION:
ANSWORTH BRANCH 29.0
END DESCRIPTION:
XS GIS Cut Line= 3
      2421625.04     13736324.98        2420825.       13736675.
      2420475.04     13736824.98
#Sta/Elev= 30
  4135.7  371.02  4168.1     370  4179.4  368.92  4255.8  365.67  4272.6  364.21
    4278  364.76  4301.4   363.3  4342.7   359.9  4371.6  354.92  4387.7  353.48
  4447.2   348.9    4494  346.73  4499.4  347.64  4571.4  347.21  4583.3  347.45
  4605.1  346.22  4643.7  345.69  4668.6  344.81  4895.5  342.09  4976.6  343.42
  4983.7  339.24  4984.2  338.74  4990.5  339.24  4994.5   343.3    5000  344.01
  5023.5  342.97  5095.7  343.56  5295.3  354.59  5312.6  355.41  5389.7  358.81
#Mann= 9 ,-1 , 0
  4135.7     .07       0  4387.7     .12       0  4571.4     .05       0
  4643.7     .12       0  4983.7    .035       0  4990.5     .12       0
  5095.7     .07       0  5295.3    .035       0  5312.6     .05       0
Bank Sta=4983.7,4990.5
XS Rating Curve= 0 ,0
Exp/Cntr=0.3,0.1

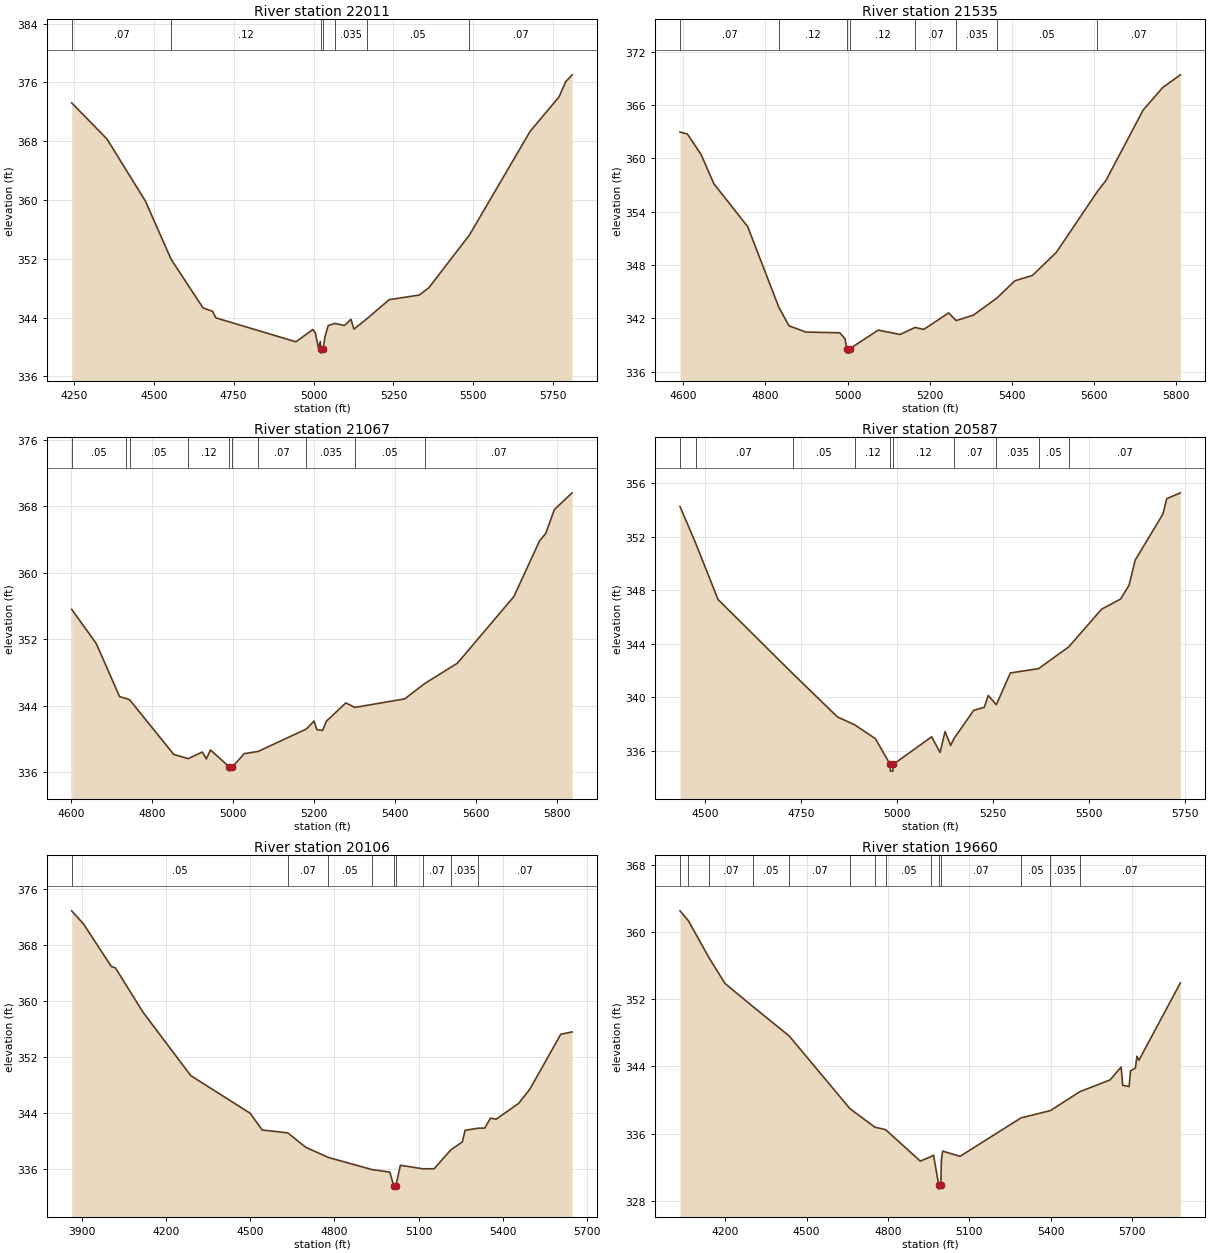
Type RM Length L Ch R = 1 ,22011   ,476,476,476
BEGIN DESCRIPTION:
ANSWORTH BRANCH 28.0
END DESCRIPTION:
XS GIS Cut Line= 3
      2421675.04       13736275.        2420925.       13736325.
      2420125.05     13736474.99
#Sta/Elev= 30
  4243.4   373.2  4353.7   368.3    4474  359.85  4554.5  351.93  4654.4  345.31
  4684.4  344.84  4694.4  343.96    4945   340.7  4997.6  342.36  5005.3  341.99
  5015.5  339.85  5021.4  340.76  5022.8  339.66  5023.3  339.16  5030.1  339.66
  5035.8  341.38    5046  342.91    5067   343.2  5096.8  342.92  5117.2  343.76
  5126.5  342.42  5167.7  343.86  5236.7  346.43  5330.9  347.06  5361.4  348.08
    5488  355.24  5677.6  369.32  5768.4  374.03  5788.7  376.07    5809  377.02
#Mann= 7 ,-1 , 0
  4243.4     .07       0  4554.5     .12       0  5022.8     .05       0
  5030.1     .12       0    5067    .035       0  5167.7     .05       0
    5488     .07       0
Bank Sta=5022.8,5030.1
XS Rating Curve= 0 ,0
Exp/Cntr=0.3,0.1

Type RM Length L Ch R = 1 ,21535   ,468,468,468
BEGIN DESCRIPTION:
ANSWORTH BRANCH 27.0
END DESCRIPTION:
XS GIS Cut Line= 3
      2421424.98     13735825.01        2421025.       13735925.
      2420225.01       13736025.
#Sta/Elev= 30
  4591.9  362.96  4609.9  362.74  4643.4  360.42  4674.3  357.15  4756.8  352.31
  4832.3  343.27  4857.3  341.15  4898.5  340.45    4981  340.37  4993.9  339.69
  4997.9  338.58  4998.4  338.08  5004.8  338.08  5005.3  338.58  5074.7  340.67
  5127.6  340.18  5164.7  340.97  5185.6  340.75  5246.1  342.61  5264.3  341.74
  5306.5  342.36  5363.9  344.29  5407.3  346.22  5450.1  346.82  5508.1  349.41
  5608.3  356.27    5629   357.5  5719.7  365.44  5767.6  367.98  5810.4   369.4
#Mann= 8 ,-1 , 0
  4591.9     .07       0  4832.3     .12       0  4997.9     .05       0
  5005.3     .12       0  5164.7     .07       0  5264.3    .035       0
  5363.9     .05       0  5608.3     .07       0
Bank Sta=4997.9,5005.3
XS Rating Curve= 0 ,0
Exp/Cntr=0.3,0.1

Type RM Length L Ch R = 1 ,21067   ,480,480,480
BEGIN DESCRIPTION:
ANSWORTH BRANCH 26.0
END DESCRIPTION:
XS GIS Cut Line= 3
      2421324.97       13735575.        2420925.       13735525.
      2420225.04     13735974.98
#Sta/Elev= 30
  4601.5  355.59  4661.9   351.5  4719.9  345.08  4735.5  344.88  4744.7   344.7
  4853.4  338.14  4889.1  337.63    4924  338.43    4934   337.6  4944.1  338.68
  4990.8  336.63  4991.3  336.13  4998.2  336.63  5027.4  338.23  5061.8   338.5
    5181   341.2  5199.7  342.15  5206.7  341.12  5220.9  341.02  5230.1  342.13
  5278.3  344.34  5300.3  343.79  5423.6  344.82    5474   346.7  5553.7  349.11
  5693.1  357.13  5756.5  363.83  5771.7  364.71  5792.8  367.57  5836.7   369.6
#Mann= 10 ,-1 , 0
  4601.5     .05       0  4735.5     .07       0  4744.7     .05       0
  4889.1     .12       0  4990.8     .05       0  4998.2     .12       0
  5061.8     .07       0    5181    .035       0  5300.3     .05       0
    5474     .07       0
Bank Sta=4990.8,4998.2
XS Rating Curve= 0 ,0
Exp/Cntr=0.3,0.1

Type RM Length L Ch R = 1 ,20587   ,481,481,481
BEGIN DESCRIPTION:
ANSWORTH BRANCH 25.0
END DESCRIPTION:
XS GIS Cut Line= 3
      2421325.02     13735475.02        2420925.       13735075.
      2420274.97     13734724.98
#Sta/Elev= 30
  4434.4  354.28  4475.4  351.52  4533.4  347.32  4728.2  341.77  4844.6  338.53
  4890.6  337.92  4943.6   336.9  4982.2  334.97  4982.7  334.47  4989.3  334.47
  4989.8  334.97  5090.2  337.04  5112.1  335.87  5125.1  337.43  5139.7  336.39
  5148.6  336.92  5199.7  339.02  5227.3  339.25  5237.8  340.13  5258.7  339.44
  5295.4  341.82  5368.8  342.14  5447.4  343.77  5533.1  346.59  5582.6  347.35
  5604.5  348.38  5620.7  350.27  5692.9  353.71  5702.7  354.86  5738.4   355.3
#Mann= 10 ,-1 , 0
  4434.4     .05       0  4475.4     .07       0  4728.2     .05       0
  4890.6     .12       0  4982.2     .05       0  4989.8     .12       0
  5148.6     .07       0  5258.7    .035       0  5368.8     .05       0
  5447.4     .07       0
Bank Sta=4982.2,4989.8
XS Rating Curve= 0 ,0
Exp/Cntr=0.3,0.1

Type RM Length L Ch R = 1 ,20106   ,446,446,446
BEGIN DESCRIPTION:
ANSWORTH BRANCH 24.0
END DESCRIPTION:
XS GIS Cut Line= 3
      2421724.98     13735424.98        2420925.       13734625.
      2420274.96       13734675.
#Sta/Elev= 30
  3863.4  372.92  3905.8  371.03  4004.8  364.94  4018.9  364.77  4117.9  358.38
  4287.6  349.32  4499.8  343.91  4542.2  341.52  4633.5  341.11  4697.8  339.04
  4778.2  337.59  4933.8  335.85  4997.2  335.49  5010.9  333.55  5011.4  333.05
  5018.7  333.55  5034.9  336.47  5115.1  335.96  5155.2  335.97  5214.1  338.66
  5255.5  339.81  5265.5  341.48  5313.1  341.78  5335.7   341.8  5355.8  343.22
  5375.9  343.06  5456.1  345.33  5496.2  347.37  5606.5  355.24  5646.7  355.57
#Mann= 9 ,-1 , 0
  3863.4     .05       0  4633.5     .07       0  4778.2     .05       0
  4933.8     .12       0  5010.9     .05       0  5018.7     .12       0
  5115.1     .07       0  5214.1    .035       0  5313.1     .07       0
Bank Sta=5010.9,5018.7
XS Rating Curve= 0 ,0
Exp/Cntr=0.3,0.1

Type RM Length L Ch R = 1 ,19660   ,434,434,434
BEGIN DESCRIPTION:
ANSWORTH BRANCH 23.0
END DESCRIPTION:
XS GIS Cut Line= 3
      2421875.01     13734775.01        2421075.       13734225.
      2420274.96     13734575.02
#Sta/Elev= 30
  4033.6  362.54  4064.7  361.35  4140.2  356.97  4199.4  353.89  4302.1  351.14
    4436  347.63  4659.8  338.97  4751.9  336.76  4791.2  336.47  4919.2  332.72
  4960.3  333.28    4968  333.44    4987  329.88  4987.5  329.38  4994.8  329.88
    4997  332.89  5001.4  333.91  5065.6  333.29  5289.9  337.86  5398.8  338.74
  5507.6     341  5618.4  342.39  5659.3  343.93  5665.2  341.75  5688.6   341.6
    5694  343.47    5712  343.81  5717.4  345.21  5724.8  344.73  5877.7  353.96
#Mann= 14 ,-1 , 0
  4033.6     .07       0  4064.7     .05       0  4140.2     .07       0
  4302.1     .05       0    4436     .07       0  4659.8     .05       0
  4751.9     .07       0  4791.2     .05       0  4960.3     .07       0
    4987     .05       0  4994.8     .07       0  5289.9     .05       0
  5398.8    .035       0  5507.6     .07       0
Bank Sta=4987,4994.8
XS Rating Curve= 0 ,0
Exp/Cntr=0.3,0.1

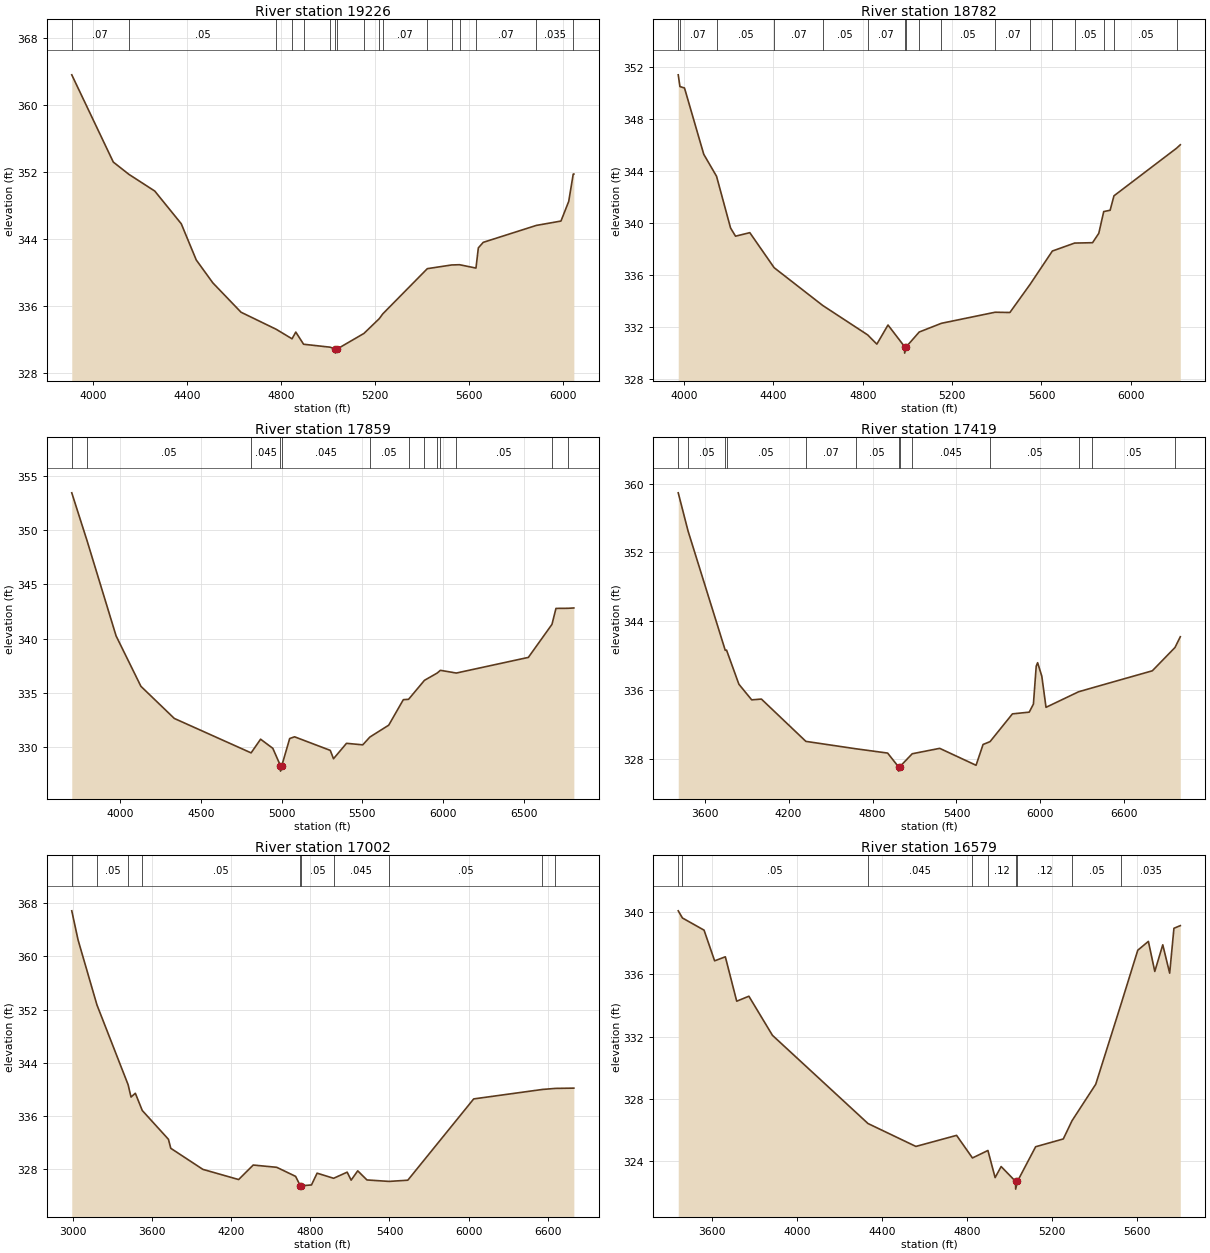
Type RM Length L Ch R = 1 ,19226   ,444,444,444
BEGIN DESCRIPTION:
ANSWORTH BRANCH 22.0
END DESCRIPTION:
XS GIS Cut Line= 3
      2421975.03     13734675.03        2421225.       13733875.
      2420224.96     13734175.01
#Sta/Elev= 30
  3907.6  363.63  4084.7  353.22  4150.9  351.76  4261.5  349.76  4374.4  345.86
  4438.3  341.54  4509.2   338.8  4629.3   335.3  4778.9  333.27  4846.7  332.13
  4862.8  332.93    4896  331.48  5008.9  331.13  5031.4  330.92  5031.9  330.42
  5039.6  330.92  5153.3  332.77  5218.9  334.54  5233.5   335.1  5423.6   340.5
  5527.3  340.94  5560.8  340.97    5631  340.57  5641.1  342.98    5662  343.64
  5888.3  345.66  5993.4  346.18  6026.5  348.53  6045.7  351.79  6048.3  351.79
#Mann= 17 ,-1 , 0
  3907.6     .07       0  4150.9     .05       0  4778.9    .035       0
  4846.7     .05       0    4896     .07       0  5008.9     .05       0
  5031.4     .05       0  5039.6     .05       0  5153.3     .07       0
  5218.9     .05       0  5233.5     .07       0  5423.6     .05       0
  5527.3     .07       0  5560.8    .035       0    5631     .07       0
  5888.3    .035       0  6045.7     .07       0
Bank Sta=5031.4,5039.6
XS Rating Curve= 0 ,0
Exp/Cntr=0.3,0.1

Type RM Length L Ch R = 1 ,18782   ,923,923,923
BEGIN DESCRIPTION:
ANSWORTH BRANCH 21.0
END DESCRIPTION:
XS GIS Cut Line= 3
        2422125.       13734325.        2421475.       13733525.
      2420275.03     13733325.01
#Sta/Elev= 30
  3974.3  351.39  3981.9  350.49  4002.3  350.38  4088.5  345.29  4145.8   343.6
  4208.5  339.63  4230.8     339  4294.7  339.27  4403.6  336.58    4621  333.68
  4822.2  331.42  4863.3  330.71  4913.2  332.18  4987.3  330.52  4987.8  330.02
  4995.6  330.52  5052.9  331.64  5152.3  332.31  5392.6  333.16  5458.8  333.14
  5549.6  335.31  5648.9  337.86  5748.3  338.47  5828.8   338.5  5856.7  339.22
  5878.8  340.89  5907.4  340.99  5924.7   342.1  6205.2  345.76  6221.6  346.02
#Mann= 17 ,-1 , 0
  3974.3     .05       0  3981.9     .07       0  4145.8     .05       0
  4403.6     .07       0    4621     .05       0  4822.2     .07       0
  4987.3     .05       0  4995.6     .07       0  5052.9    .035       0
  5152.3     .05       0  5392.6     .07       0  5549.6     .05       0
  5648.9     .07       0  5748.3     .05       0  5878.8    .035       0
  5924.7     .05       0  6205.2     .07       0
Bank Sta=4987.3,4995.6
XS Rating Curve= 0 ,0
Exp/Cntr=0.3,0.1

Type RM Length L Ch R = 1 ,17859   ,440,440,440
BEGIN DESCRIPTION:
ANSWORTH BRANCH 20.0
END DESCRIPTION:
XS GIS Cut Line= 3
      2422724.99     13734274.98        2422225.       13733075.
      2420424.96       13732875.
#Sta/Elev= 30
    3700  353.42    3795     349  3974.6  340.25  4128.4  335.61  4335.4  332.65
  4811.3  329.48    4870  330.74  4945.8   329.9  4993.1   328.3  4993.6   327.8
  5001.4   328.3  5050.3   330.8  5080.5  330.96  5301.8  329.71  5321.9  328.94
  5402.4  330.36  5503.1  330.22  5547.4  330.94    5664  332.03  5754.6  334.38
  5786.8  334.41  5885.5  336.16  5964.5  336.83  5984.2  337.08    6083  336.83
  6529.3  338.27  6675.5  341.31  6700.4  342.78  6774.2  342.79  6811.1  342.82
#Mann= 13 ,-1 , 0
    3700     .07       0    3795     .05       0  4811.3    .045       0
  4993.1    .045       0  5001.4    .045       0  5547.4     .05       0
  5786.8    .035       0  5885.5     .07       0  5964.5    .035       0
  5984.2     .07       0    6083     .05       0  6675.5    .035       0
  6774.2     .05       0
Bank Sta=4993.1,5001.4
XS Rating Curve= 0 ,0
Exp/Cntr=0.3,0.1

Type RM Length L Ch R = 1 ,17419   ,417,417,417
BEGIN DESCRIPTION:
ANSWORTH BRANCH 19.0
END DESCRIPTION:
XS GIS Cut Line= 3
      2422875.01     13734325.02        2422525.       13732775.
      2420525.05       13732775.
#Sta/Elev= 30
  3411.2  358.94  3481.4   354.5  3747.3  340.62  3756.5  340.65  3844.7  336.68
  3936.3  334.86  4005.8  334.95  4323.7  330.03  4680.8  329.17    4908  328.67
  4985.8  327.07  4986.3  326.57  4994.2  327.07  5083.8  328.59  5280.2  329.22
  5540.2  327.25  5590.2  329.67  5640.1     330  5800.2  333.23  5920.2  333.43
  5950.2  334.37  5970.2  338.78  5980.2  339.18  6010.2  337.61  6040.2  333.99
    6273   335.8  6371.4  336.26  6800.2  338.24  6962.2  340.95  7000.2   342.2
#Mann= 13 ,-1 , 0
  3411.2     .07       0  3481.4     .05       0  3747.3     .07       0
  3756.5     .05       0  4323.7     .07       0  4680.8     .05       0
  4985.8     .05       0  4994.2     .05       0  5083.8    .045       0
  5640.1     .05       0    6273    .035       0  6371.4     .05       0
  6962.2    .035       0
Bank Sta=4985.8,4994.2
XS Rating Curve= 0 ,0
Exp/Cntr=0.3,0.1

Type RM Length L Ch R = 1 ,17002   ,423,423,423
BEGIN DESCRIPTION:
ANSWORTH BRANCH 18.0
END DESCRIPTION:
XS GIS Cut Line= 3
        2422925.     13734424.97        2422725.       13732425.
      2420925.05       13732425.
#Sta/Elev= 30
  2989.4  366.86  3037.1  362.49  3180.3  352.73    3417  340.72  3439.1  338.87
  3471.8  339.44  3524.4  336.85    3723  332.52  3740.6  331.17  3984.3     328
  4255.7  326.47  4366.2  328.65  4544.6  328.31  4687.8  326.95  4723.8  325.53
  4724.3  325.03  4732.2  325.53  4808.4  325.66  4851.1  327.43  4976.3  326.66
  5079.3  327.58  5109.3  326.38  5159.3  327.78  5229.3  326.41  5397.2  326.19
  5539.3  326.37  6039.3  338.59  6560.5  340.01  6658.9  340.17  6799.3  340.21
#Mann= 10 ,-1 , 0
  2989.4     .07       0  3180.3     .05       0    3417     .07       0
  3524.4     .05       0  4723.8    .045       0  4732.2     .05       0
  4976.3    .045       0  5397.2     .05       0  6560.5    .035       0
  6658.9     .07       0
Bank Sta=4723.8,4732.2
XS Rating Curve= 0 ,0
Exp/Cntr=0.3,0.1

Type RM Length L Ch R = 1 ,16579   ,467,467,467
BEGIN DESCRIPTION:
ANSWORTH BRANCH 17.0
END DESCRIPTION:
XS GIS Cut Line= 3
        2423275.     13733975.01        2423075.       13732425.
        2423025.     13731625.02
#Sta/Elev= 30
  3441.2  340.08  3461.1  339.62  3562.8  338.84  3612.6  336.87    3663  337.13
  3716.6  334.28  3773.9   334.6  3884.9  332.09  4334.9  326.43  4560.4  324.96
    4752  325.67  4826.8  324.22  4899.6   324.7  4933.5  322.96  4961.8  323.67
  5029.7  322.72  5030.2  322.22  5038.6  322.72  5124.3  324.94  5254.5  325.44
  5295.7  326.61  5407.3  328.95  5527.1  334.12  5605.2  337.55  5655.3  338.12
  5685.4  336.19    5723   337.9  5755.5  336.08  5775.6  338.96  5805.6  339.13
#Mann= 9 ,-1 , 0
  3441.2    .035       0  3461.1     .05       0  4334.9    .045       0
  4826.8     .05       0  4899.6     .12       0  5029.7     .05       0
  5038.6     .12       0  5295.7     .05       0  5527.1    .035       0
Bank Sta=5029.7,5038.6
XS Rating Curve= 0 ,0
Exp/Cntr=0.3,0.1

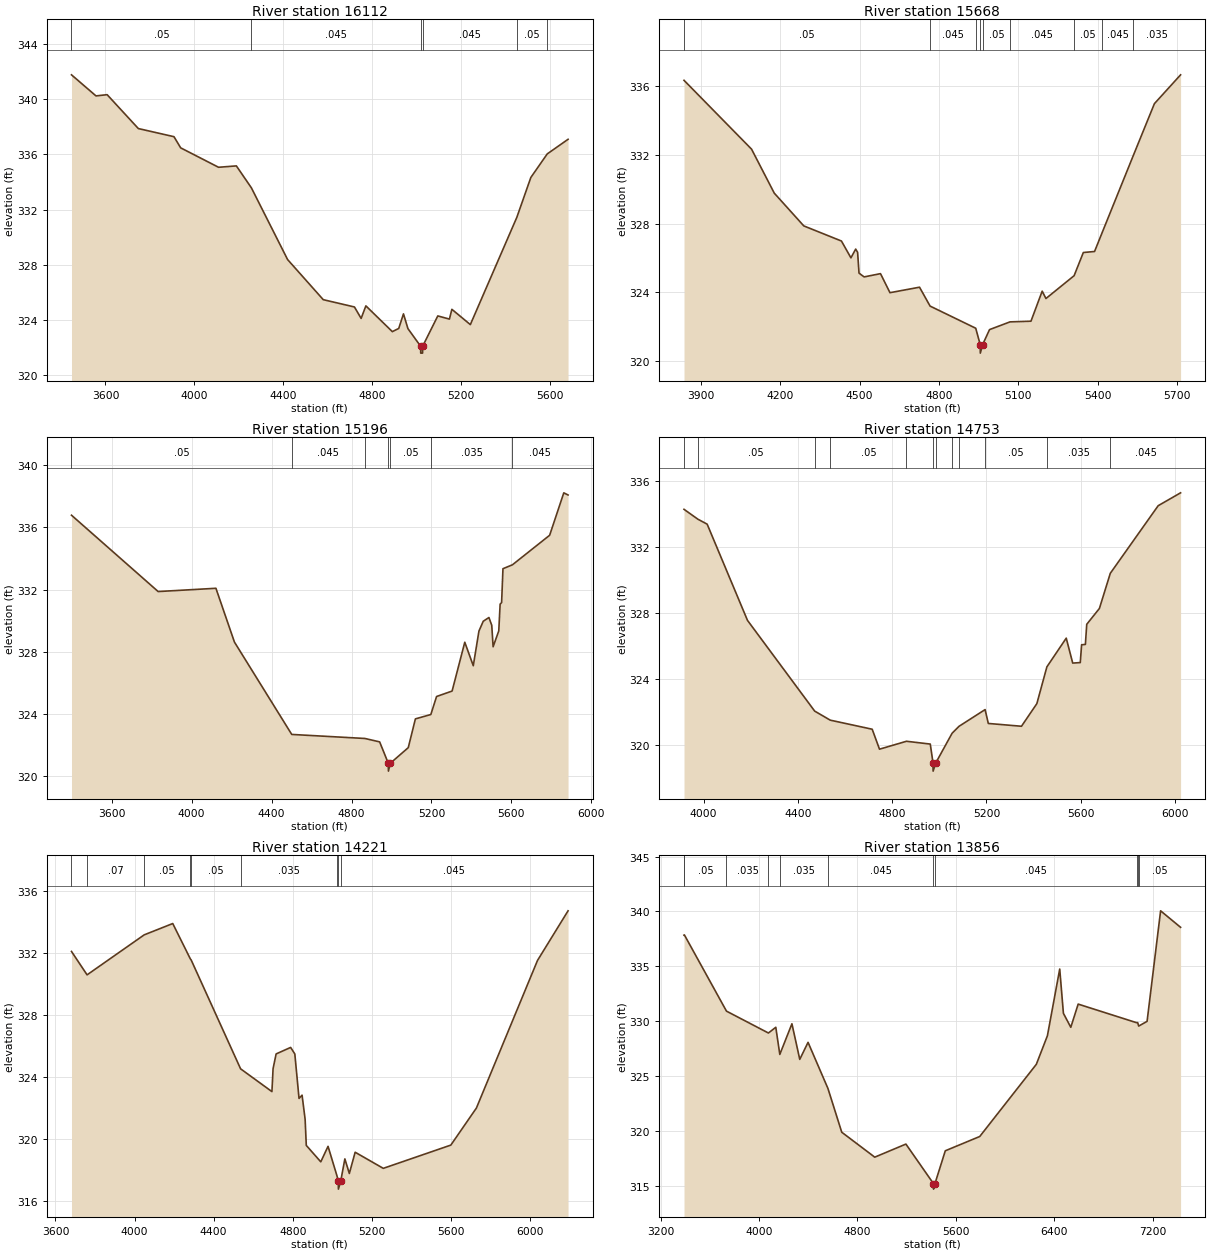
Type RM Length L Ch R = 1 ,16112   ,444,444,444
BEGIN DESCRIPTION:
ANSWORTH BRANCH 16.0
END DESCRIPTION:
XS GIS Cut Line= 3
        2423425.     13734024.98        2423525.       13732475.
      2423324.99     13731824.97
#Sta/Elev= 30
  3447.2  341.78  3557.4  340.25  3607.5  340.34  3747.8  337.88  3908.1  337.29
  3938.2  336.48  4108.5  335.07  4188.7  335.17  4256.2  333.58  4419.2  328.37
  4579.5  325.46  4719.8  324.93  4749.9   324.1  4771.2  325.01  4890.2  323.14
    4919  323.37  4940.3  324.43  4960.3  323.36  5017.4  322.08  5017.9  321.58
  5026.1  321.58  5026.6  322.08  5094.6  324.28  5146.9  324.05    5158  324.76
    5241  323.65  5450.2  331.44  5513.1  334.33  5586.9  336.04  5680.5   337.1
#Mann= 6 ,-1 , 0
  3447.2     .05       0  4256.2    .045       0  5017.4    .045       0
  5026.6    .045       0  5450.2     .05       0  5586.9    .035       0
Bank Sta=5017.4,5026.6
XS Rating Curve= 0 ,0
Exp/Cntr=0.3,0.1

Type RM Length L Ch R = 1 ,15668   ,472,472,472
BEGIN DESCRIPTION:
ANSWORTH BRANCH 15.0
END DESCRIPTION:
XS GIS Cut Line= 3
      2423524.99     13733425.02        2423925.       13732325.
        2423425.       13731825.
#Sta/Elev= 30
  3836.1  336.35  4091.5  332.34  4177.3  329.78    4289  327.87  4431.3  326.99
  4467.2  326.01  4485.2  326.52  4492.5  326.33  4497.8  325.12  4517.1   324.9
    4579  325.09  4614.9  323.98  4726.6   324.3  4766.5   323.2  4939.1  321.91
    4956  320.96  4956.5  320.46  4965.3  320.96  4991.3  321.83  5068.7  322.28
    5148  322.32  5190.4  324.07  5204.6  323.64  5311.1  324.97    5346  326.32
  5388.4  326.38  5414.8  327.39  5535.2  331.98  5614.7  334.99  5713.7  336.67
#Mann= 9 ,-1 , 0
  3836.1     .05       0  4766.5    .045       0  4939.1     .05       0
    4956     .05       0  4965.3     .05       0  5068.7    .045       0
  5311.1     .05       0  5414.8    .045       0  5535.2    .035       0
Bank Sta=4956,4965.3
XS Rating Curve= 0 ,0
Exp/Cntr=0.3,0.1

Type RM Length L Ch R = 1 ,15196   ,443,443,443
BEGIN DESCRIPTION:
ANSWORTH BRANCH 14.0
END DESCRIPTION:
XS GIS Cut Line= 3
        2423875.     13733625.01        2424275.       13732075.
      2423624.99     13731474.99
#Sta/Elev= 30
  3398.5  336.78  3832.3  331.87  4121.4  332.08  4214.1  328.62  4500.9  322.68
  4867.5  322.42  4940.9   322.2  4984.3  320.82  4984.8  320.32  4993.6  320.82
  5084.1  321.83  5119.8  323.68    5197  323.96  5225.8  325.12  5303.5  325.47
    5367  328.61  5409.5   327.1  5437.9  329.33  5459.4  329.96  5487.8   330.2
    5502   329.7  5508.8  328.32  5537.1  329.34  5543.9  331.06  5551.3  331.16
  5558.1  333.34  5605.4  333.59  5791.7  335.49  5862.6  338.22  5883.9  338.08
#Mann= 7 ,-1 , 0
  3398.5     .05       0  4500.9    .045       0  4867.5     .05       0
  4984.3     .05       0  4993.6     .05       0    5197    .035       0
  5605.4    .045       0
Bank Sta=4984.3,4993.6
XS Rating Curve= 0 ,0
Exp/Cntr=0.3,0.1

Type RM Length L Ch R = 1 ,14753   ,532,532,532
BEGIN DESCRIPTION:
ANSWORTH BRANCH 13.0
END DESCRIPTION:
XS GIS Cut Line= 3
      2425674.96     13732424.98        2424675.       13732025.
      2423774.96     13731524.98
#Sta/Elev= 30
  3917.2  334.27  3976.2  333.67  4015.4  333.37  4186.4  327.54  4471.4  322.04
  4537.5  321.49  4715.5  320.94  4746.5  319.73  4860.9  320.21  4961.9  320.04
  4973.5   318.9    4974   318.4  4985.3   318.9  5054.7   320.7  5084.2  321.12
  5194.5  322.13  5208.1  321.29  5348.8  321.12    5414  322.49  5456.6  324.72
  5538.7  326.46  5566.2  324.95  5598.2  324.98  5603.9  326.06  5619.9  326.08
  5625.7   327.3  5679.4  328.26  5725.6  330.39  5928.8  334.49  6023.8  335.27
#Mann= 12 ,-1 , 0
  3917.2    .035       0  3976.2     .05       0  4471.4    .045       0
  4537.5     .05       0  4860.9    .045       0  4973.5    .045       0
  4985.3    .045       0  5054.7     .05       0  5084.2    .035       0
  5194.5     .05       0  5456.6    .035       0  5725.6    .045       0
Bank Sta=4973.5,4985.3
XS Rating Curve= 0 ,0
Exp/Cntr=0.3,0.1

Type RM Length L Ch R = 1 ,14221   ,365,365,365
BEGIN DESCRIPTION:
ANSWORTH BRANCH 12.0
END DESCRIPTION:
XS GIS Cut Line= 3
      2426160.77     13732403.51      2424900.89     13731625.92
      2423874.96       13731525.
#Sta/Elev= 30
    3681  332.08  3759.8  330.57  4048.7  333.15  4193.1  333.88  4282.1   331.6
  4286.3  331.53  4536.2  324.51  4694.7  323.04  4700.5  324.52  4715.9  325.47
  4789.3  325.89  4810.5  325.47  4831.8   322.6  4847.2  322.81  4862.6  321.25
  4868.5  319.57  4941.8  318.51  4978.5  319.51  5024.3  317.58  5030.4  317.25
  5030.9  316.75  5042.4  317.25  5063.6   318.7  5086.2  317.76  5115.6  319.13
  5257.9  318.09  5599.5  319.59  5728.9  321.98  6037.9   331.5  6192.4   334.7
#Mann= 9 ,-1 , 0
    3681     .05       0  3759.8     .07       0  4048.7     .05       0
  4282.1    .035       0  4286.3     .05       0  4536.2    .035       0
  5024.3    .045       0  5030.4    .035       0  5042.4    .045       0
Bank Sta=5030.4,5042.4
XS Rating Curve= 0 ,0
Exp/Cntr=0.3,0.1

Type RM Length L Ch R = 1 ,13856   ,657,657,657
BEGIN DESCRIPTION:
ANSWORTH BRANCH 11.0
END DESCRIPTION:
XS GIS Cut Line= 3
      2426682.36     13732334.57      2425176.48     13731399.55
       2422912.7     13731340.49
#Sta/Elev= 30
  3390.1  337.85    3393  337.87  3735.3  330.93  4076.2  328.94  4136.3  329.46
  4168.9  326.99  4267.4  329.78  4331.1  326.54  4398.5  328.09  4560.3  323.89
  4672.4  319.91  4940.7  317.64  5194.1  318.83  5418.2  315.23  5418.7  314.73
  5430.2  315.23  5514.3  318.22  5794.3  319.52  6254.5  326.09  6344.5  328.69
  6444.6  334.76  6474.6  330.73  6534.6  329.46  6594.6  331.57    7069  329.88
  7078.2  329.89  7086.6  329.57  7154.8     330  7264.8  340.06  7427.2  338.56
#Mann= 11 ,-1 , 0
  3390.1    .035       0    3393     .05       0  3735.3    .035       0
  4076.2     .05       0  4168.9    .035       0  4560.3    .045       0
  5418.2    .045       0  5430.2    .045       0    7069     .05       0
  7078.2    .045       0  7086.6     .05       0
Bank Sta=5418.2,5430.2
XS Rating Curve= 0 ,0
Exp/Cntr=0.3,0.1