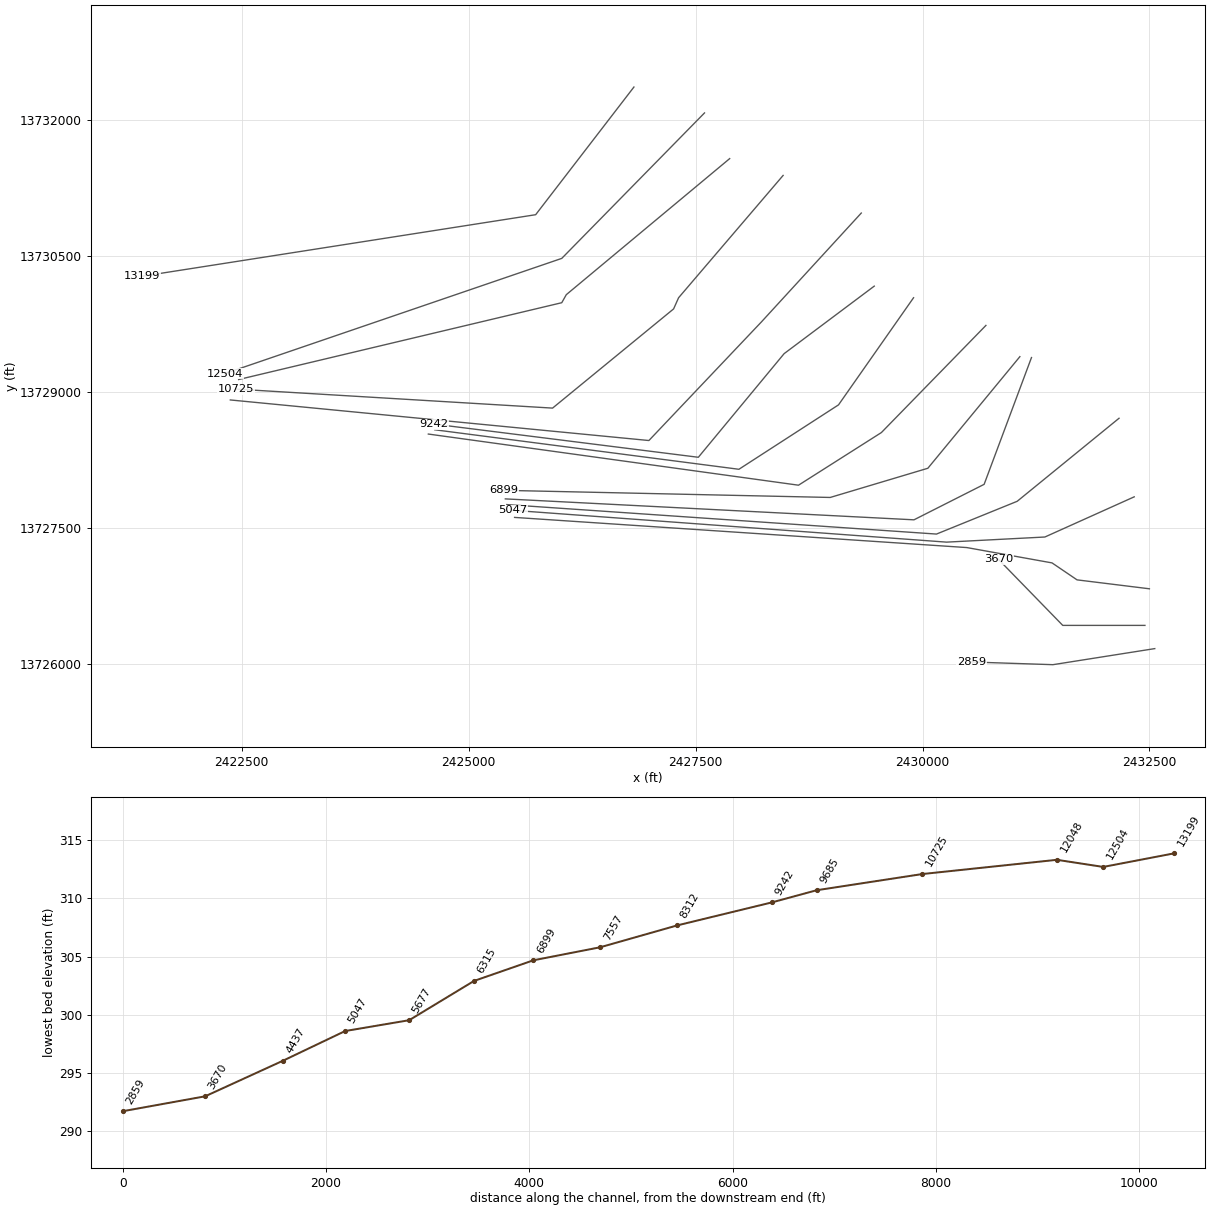
HEC-RAS study ANSWORTH BRANCH.prj: ANSWORTH BRANCH Base Level Engineering

--- ANSWORTH BRANCH.g01 (geometry) --- (continued)

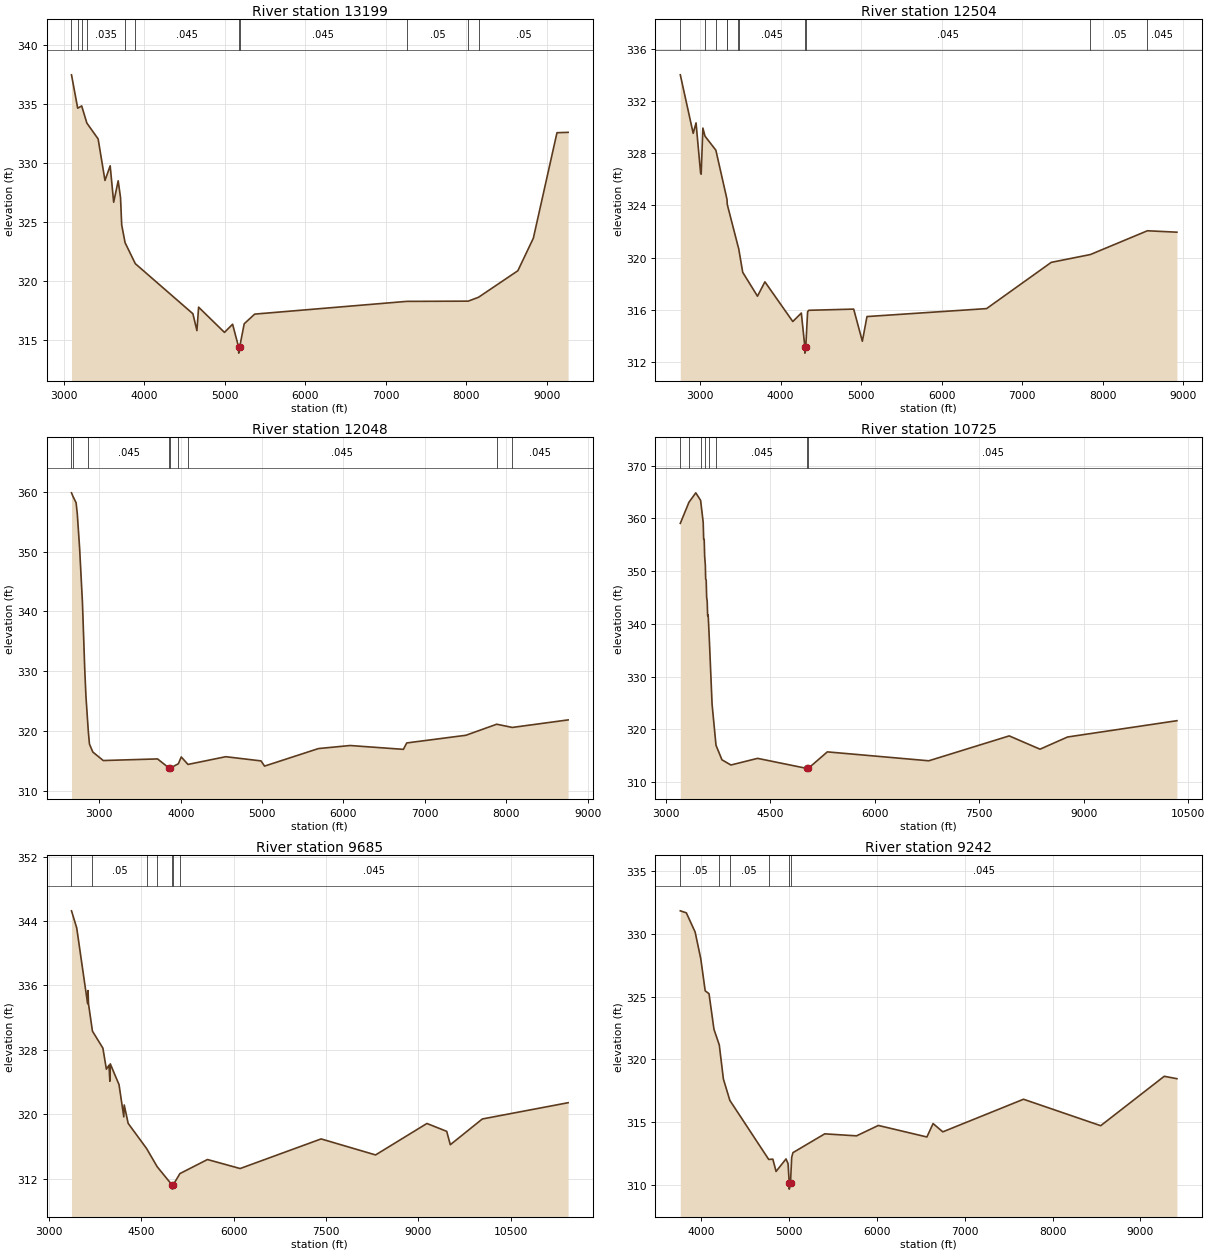
Type RM Length L Ch R = 1 ,13199   ,695,695,695
BEGIN DESCRIPTION:
ANSWORTH BRANCH 10.0
END DESCRIPTION:
XS GIS Cut Line= 3
      2426820.18     13732364.12       2425737.5     13730956.63
      2421398.42     13730277.73
#Sta/Elev= 30
  3098.2  337.46  3175.2  334.63  3224.9  334.82  3288.9  333.37    3429  332.02
  3514.1   328.5  3578.5  329.74    3622  326.65  3678.1  328.47  3707.2  327.04
  3721.7  324.73  3763.7  323.22  3890.7  321.44  4606.1  317.19  4655.9  315.76
  4676.7  317.75  4997.9  315.61  5099.1   316.3  5174.4  314.35  5174.9  313.85
  5186.4  314.35  5243.1  316.34  5373.6  317.16  7259.7  318.24    8025  318.26
  8153.3  318.59  8641.7  320.84    8834   323.6  9127.6  332.55  9265.8  332.58
#Mann= 11 ,-1 , 0
  3098.2     .05       0  3175.2    .035       0  3224.9     .05       0
  3288.9    .035       0  3763.7     .05       0  3890.7    .045       0
  5174.4    .045       0  5186.4    .045       0  7259.7     .05       0
    8025     .07       0  8153.3     .05       0
Bank Sta=5174.4,5186.4
XS Rating Curve= 0 ,0
Exp/Cntr=0.3,0.1

Type RM Length L Ch R = 1 ,12504   ,456,456,456
BEGIN DESCRIPTION:
ANSWORTH BRANCH 9.0
END DESCRIPTION:
XS GIS Cut Line= 3
      2427597.75     13732078.69        2426025.       13730475.
      2422312.31     13729204.66
#Sta/Elev= 30
  2754.4     334  2914.5  329.52  2949.9  330.32  3006.5  326.49  3013.5  326.39
  3034.8  329.92  3061.6   329.3  3196.2  328.23  3334.8  324.46  3338.1  324.07
  3471.4  320.88    3480  320.69  3529.8  318.88  3713.5  317.05  3805.5  318.15
    4152  315.11  4258.2  315.76  4301.5  313.19    4302  312.69  4313.6  313.19
  4335.9  315.85    4350  315.97  4908.7  316.06  5016.2   313.6  5073.6  315.49
    6560   316.1  7363.2  319.64  7849.8  320.24    8558  322.06  8924.6  321.95
#Mann= 11 ,-1 , 0
  2754.4    .035       0  3061.6     .07       0  3196.2    .035       0
  3334.8     .07       0  3338.1    .035       0  3471.4     .05       0
    3480    .045       0  4301.5    .045       0  4313.6    .045       0
  7849.8     .05       0    8558    .045       0
Bank Sta=4301.5,4313.6
XS Rating Curve= 0 ,0
Exp/Cntr=0.3,0.1

Type RM Length L Ch R = 1 ,12048   ,1323,1323,1323
BEGIN DESCRIPTION:
ANSWORTH BRANCH 8.0
END DESCRIPTION:
XS GIS Cut Line= 4
      2427874.99     13731574.99        2426075.       13730075.
       2426025.1      13729986.5      2422465.32     13729139.55
#Sta/Elev= 30
  2656.9  359.81  2673.3  359.27  2713.5  358.15  2727.8  356.36  2756.5  350.61
  2791.6  341.46  2820.2  330.19  2834.6   325.8  2863.8  319.92  2877.5  317.83
  2919.2  316.49  3047.4  315.07  3714.5  315.34  3857.7   313.8  3858.2   313.3
  3870.8   313.8  3970.8  314.54  4006.1  315.67  4088.5  314.42  4552.8  315.71
  4986.3  315.01  5029.6  314.14    5692  317.07  6081.7  317.58    6736  316.94
  6777.2  318.01  7503.8  319.29  7883.4  321.14  8074.5   320.6  8760.7  321.86
#Mann= 9 ,-1 , 0
  2656.9     .07       0  2673.3     .12       0  2863.8    .045       0
  3857.7    .045       0  3870.8    .045       0  3970.8    .035       0
  4088.5    .045       0  7883.4     .05       0  8074.5    .045       0
Bank Sta=3857.7,3870.8
XS Rating Curve= 0 ,0
Exp/Cntr=0.3,0.1

Type RM Length L Ch R = 1 ,10725   ,1040,1040,1040
BEGIN DESCRIPTION:
ANSWORTH BRANCH 7.0
END DESCRIPTION:
XS GIS Cut Line= 5
      2428463.87     13731389.68      2427312.31     13730041.27
      2427257.15     13729917.99      2425923.78     13728824.49
      2422433.37     13729034.22
#Sta/Elev= 30
    3209  359.05    3333  363.05  3431.3  364.84  3500.6  363.41  3537.8  359.22
  3544.4  356.04  3552.1     356  3558.7   352.8  3568.5  351.15    3573  348.49
  3580.7  348.32  3587.2  345.01  3594.9  344.36  3601.5  341.52  3609.2  341.67
  3626.3  336.88  3665.2  324.76  3721.6  316.98  3806.9  314.23  3935.3  313.24
  4318.4   314.5  5030.9  312.58  5031.4  312.08  5044.3  312.58  5319.8  315.73
  6775.9  314.04  7930.7  318.76  8373.2  316.24  8768.2  318.55 10338.4  321.64
#Mann= 8 ,-1 , 0
    3209     .07       0    3333     .12       0  3500.6     .07       0
  3568.5     .12       0  3626.3     .07       0  3721.6    .045       0
  5030.9    .045       0  5044.3    .045       0
Bank Sta=5030.9,5044.3
XS Rating Curve= 0 ,0
Exp/Cntr=0.3,0.1

Type RM Length L Ch R = 1 ,9685    ,443,443,443
BEGIN DESCRIPTION:
ANSWORTH BRANCH 6.0
END DESCRIPTION:
XS GIS Cut Line= 4
      2429324.97     13730974.96        2428225.       13729775.
      2426985.08     13728467.14      2422373.44     13728914.38
#Sta/Elev= 30
  3367.3  345.28    3452  343.16    3629  333.74  3636.4  335.37  3643.2  333.73
  3707.3  330.33  3876.9  328.22  3933.6   325.6  3976.2  326.09  3990.3   324.1
  3997.1  326.26    4139  323.68  4216.6  319.67  4223.4  321.15  4287.6  318.86
  4586.4  315.74  4759.2  313.47  5001.8  311.19  5002.3  310.69  5016.4  311.19
  5127.3  312.62    5575  314.37  6105.7  313.25  7420.3  316.93  8304.4  314.94
  9138.3  318.85  9459.8  317.87  9517.8  316.21   10038  319.41 11430.6  321.43
#Mann= 7 ,-1 , 0
  3367.3     .07       0  3707.3     .05       0  4586.4     .07       0
  4759.2     .05       0  5001.8     .05       0  5016.4     .05       0
  5127.3    .045       0
Bank Sta=5001.8,5016.4
XS Rating Curve= 0 ,0
Exp/Cntr=0.3,0.1

Type RM Length L Ch R = 1 ,9242    ,930,930,930
BEGIN DESCRIPTION:
ANSWORTH BRANCH 5.0
END DESCRIPTION:
XS GIS Cut Line= 4
      2429467.86     13730169.25        2428475.       13729425.
      2427529.76     13728282.41      2424618.91     13728648.33
#Sta/Elev= 30
  3758.7  331.84  3827.6  331.68  3927.6  330.15  3992.2  328.01  4042.2  325.46
  4085.9  325.23  4142.2  322.39  4202.8  321.14  4249.7  318.42  4323.2  316.72
  4765.8  312.01  4813.1  312.03  4849.6  311.05  4963.1  312.05    4986  311.68
  4999.4  310.14  4999.9  309.64  5014.1  310.14  5027.5  312.17  5041.9  312.55
    5404  314.05  5766.1  313.89  6014.9  314.72  6567.9   313.8  6638.4  314.87
  6749.3  314.21  7668.6  316.81    8548   314.7  9271.6  318.64  9416.2  318.45
#Mann= 6 ,-1 , 0
  3758.7     .05       0  4202.8    .035       0  4323.2     .05       0
  4765.8    .045       0  4999.4    .045       0  5014.1    .045       0
Bank Sta=4999.4,5014.1
XS Rating Curve= 0 ,0
Exp/Cntr=0.3,0.1

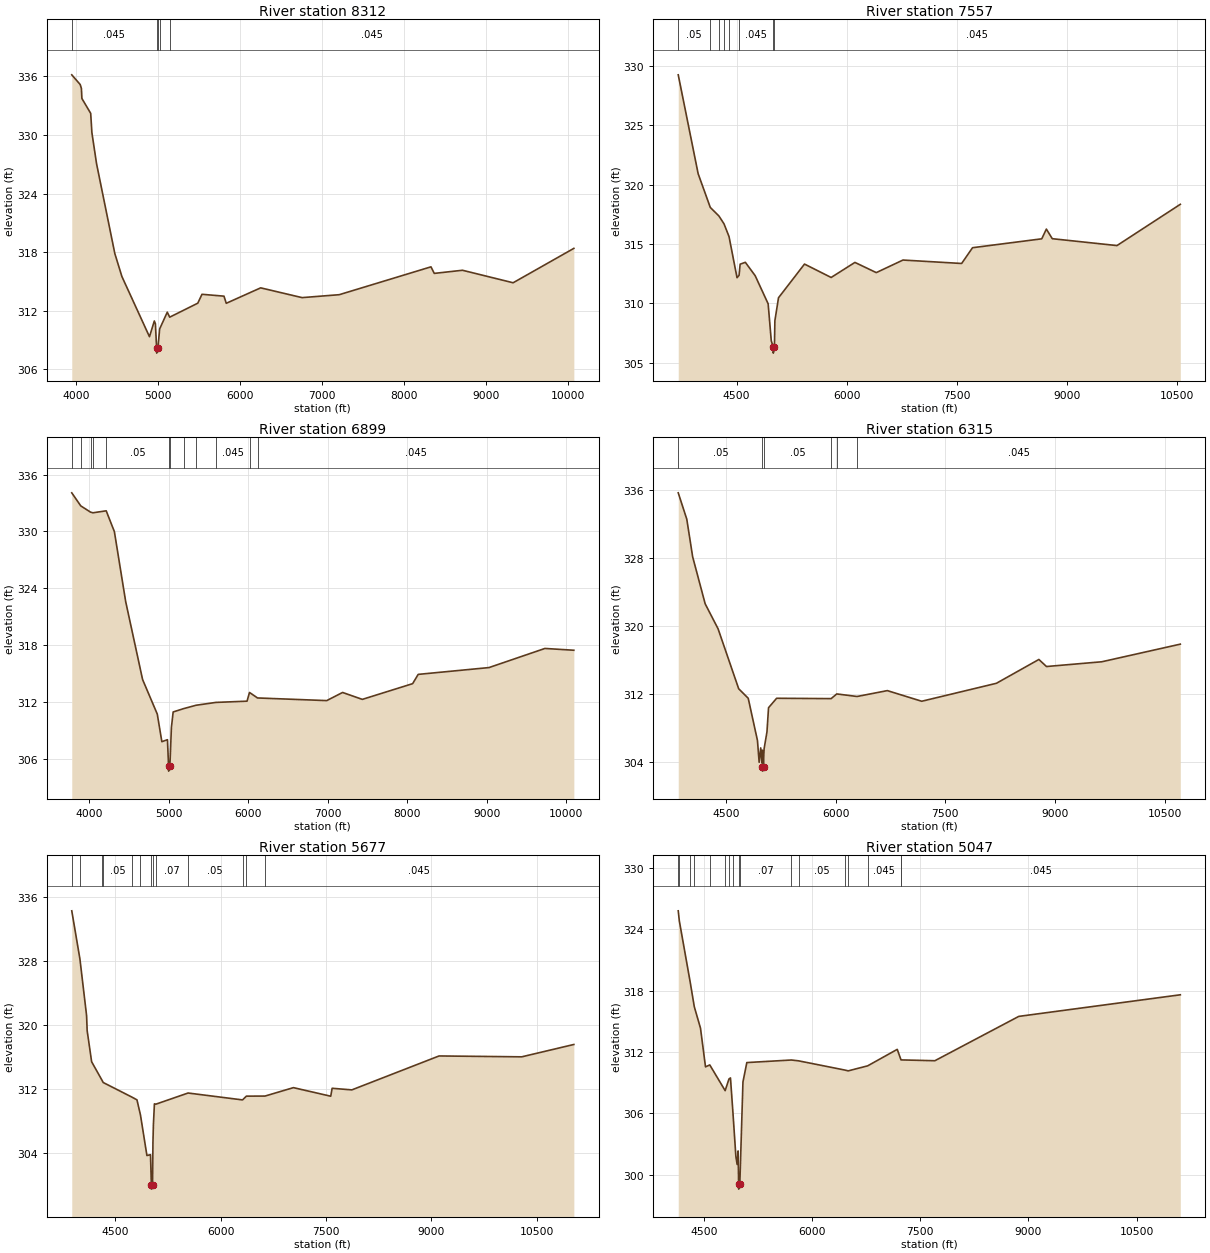
Type RM Length L Ch R = 1 ,8312    ,755,755,755
BEGIN DESCRIPTION:
X18066
END DESCRIPTION:
XS GIS Cut Line= 4
      2429900.91     13730041.28      2429074.13     13728860.17
      2427976.77     13728150.12      2424625.73     13728585.62
#Sta/Elev= 30
  3942.9  336.15  4045.6  335.16  4060.4  334.76  4066.5  333.73  4173.8  332.21
  4188.6  330.23  4245.3  327.06  4468.5  317.86  4554.8  315.51  4891.4  309.35
  4950.6  310.96  4963.7  310.67  4978.6  308.17  4979.1  307.67  4994.2  308.17
  5015.7  310.15  5108.5  311.86  5138.3  311.35  5480.9  312.78  5532.3  313.69
  5800.5   313.5  5828.5  312.77  6248.6  314.35    6754  313.35  7207.8  313.65
  8327.1   316.5  8367.4  315.83  8711.8  316.15  9329.7  314.87 10070.9  318.39
#Mann= 5 ,-1 , 0
  3942.9    .045       0  4978.6    .045       0  4994.2    .045       0
  5015.7    .035       0  5138.3    .045       0
Bank Sta=4978.6,4994.2
XS Rating Curve= 0 ,0
Exp/Cntr=0.3,0.1

Type RM Length L Ch R = 1 ,7557    ,658,658,658
BEGIN DESCRIPTION:
X18065
END DESCRIPTION:
XS GIS Cut Line= 4
      2430698.15     13729736.15      2429546.57     13728555.05
       2428633.3     13727974.65      2424555.07     13728538.49
#Sta/Elev= 30
  3702.7  329.27  3974.4  320.93  4139.7  318.09  4258.5  317.36  4327.4   316.7
  4395.5  315.63  4504.8  312.16  4532.5  312.36  4547.2   313.3    4618  313.46
  4752.3  312.33  4929.2  309.96  4971.6  306.85    4999   306.3  4999.5   305.8
  5014.7   306.3    5021  308.53  5070.6  310.47  5425.2  313.31  5788.6  312.18
  6112.9  313.45  6404.3  312.59  6768.2  313.65  7568.5  313.36  7717.3  314.69
  8661.3  315.44  8724.3  316.26    8805  315.45  9687.3  314.87 10551.4  318.35
#Mann= 8 ,-1 , 0
  3702.7     .05       0  4139.7    .045       0  4258.5    .035       0
  4327.4    .045       0  4395.5    .035       0  4532.5    .045       0
    4999    .045       0  5014.7    .045       0
Bank Sta=4999,5014.7
XS Rating Curve= 0 ,0
Exp/Cntr=0.3,0.1

Type RM Length L Ch R = 1 ,6899    ,584,584,584
BEGIN DESCRIPTION:
X18064
END DESCRIPTION:
XS GIS Cut Line= 4
      2431072.19      13729391.7      2430058.38     13728161.35
      2428982.58     13727839.53      2425388.78     13727917.97
#Sta/Elev= 30
  3782.5  334.08  3895.6   332.7  4018.7  332.04  4048.7  331.97  4215.5  332.18
  4318.3  329.98  4460.3  322.59  4672.7  314.36  4857.7   310.7  4915.1  307.79
  4985.4     308  4999.6  305.18  5000.1  304.68  5015.7  305.18  5035.1  309.29
  5057.1  310.93  5191.7  311.29  5345.7  311.64    5595  311.94  5985.7  312.07
  6017.1  312.99  6117.5  312.41  6987.3  312.13  7187.4  312.99  7435.1  312.26
  8067.6  313.92  8137.6   314.9  9027.8  315.62  9731.1  317.64 10094.3  317.45
#Mann= 12 ,-1 , 0
  3782.5     .05       0  3895.6     .07       0  4018.7     .05       0
  4048.7     .07       0  4215.5     .05       0  4999.6     .05       0
  5015.7     .05       0  5191.7    .035       0  5345.7     .05       0
    5595    .045       0  6017.1    .035       0  6117.5    .045       0
Bank Sta=4999.6,5015.7
XS Rating Curve= 0 ,0
Exp/Cntr=0.3,0.1

Type RM Length L Ch R = 1 ,6315    ,638,638,638
BEGIN DESCRIPTION:
X18063
END DESCRIPTION:
XS GIS Cut Line= 4
       2431200.1     13729381.78      2430678.46     13727984.18
      2429905.54     13727592.95      2425403.32     13727823.74
#Sta/Elev= 30
  3848.2  335.61  3965.2  332.51  4045.5  328.09  4216.6  322.57  4393.2  319.63
  4674.9  312.59  4805.4  311.47  4931.7  306.51  4954.8  303.95  4976.2  305.64
  4992.3  303.92  4997.6  305.37  5000.2  303.41  5000.7  302.91  5016.3  303.41
  5017.3  304.57  5022.6  305.54  5061.6  307.52  5083.2  310.36  5193.8  311.47
  5939.3  311.43  6016.2  311.98  6294.2  311.68  6707.5  312.37  7178.1  311.12
  8199.4  313.23  8780.2  316.03  8884.3   315.2  9641.3  315.76 10714.4  317.83
#Mann= 6 ,-1 , 0
  3848.2     .05       0  5000.2     .05       0  5016.3     .05       0
  5939.3    .035       0  6016.2     .05       0  6294.2    .045       0
Bank Sta=5000.2,5016.3
XS Rating Curve= 0 ,0
Exp/Cntr=0.3,0.1

Type RM Length L Ch R = 1 ,5677    ,630,630,630
BEGIN DESCRIPTION:
X18062
END DESCRIPTION:
XS GIS Cut Line= 4
      2432164.68     13728712.53      2431042.64     13727797.17
      2430153.28     13727435.88      2425419.52     13727760.87
#Sta/Elev= 30
  3878.9  334.23    3995  328.23    4090  321.17  4097.9  319.31  4161.8  315.42
  4311.1  313.09  4326.8  312.83  4733.5  311.02  4807.7  310.67  4857.9  308.77
  4949.6  303.73  5000.4  303.83  5013.1  300.04  5013.6  299.54  5029.4  300.04
  5035.6  305.43  5042.1   307.6  5056.4  310.17  5077.5  310.13  5536.1  311.52
  6311.6  310.66  6366.7  311.13    6632  311.14  7036.9  312.19  7568.2  311.12
  7588.2  312.11  7868.9  311.91  9111.8  316.14 10289.3  316.03 11031.8  317.57
#Mann= 13 ,-1 , 0
  3878.9     .07       0    3995     .05       0  4311.1     .07       0
  4326.8     .05       0  4733.5     .07       0  4857.9     .05       0
  5013.1     .05       0  5029.4     .05       0  5077.5     .07       0
  5536.1     .05       0  6311.6    .035       0  6366.7     .05       0
    6632    .045       0
Bank Sta=5013.1,5029.4
XS Rating Curve= 0 ,0
Exp/Cntr=0.3,0.1

Type RM Length L Ch R = 1 ,5047    ,610,610,610
BEGIN DESCRIPTION:
X18061
END DESCRIPTION:
XS GIS Cut Line= 4
      2432332.04      13727846.4      2431347.75     13727403.47
      2430264.69     13727346.96      2425481.85     13727698.07
#Sta/Elev= 30
  4146.2  325.79  4161.3  324.81  4312.4  318.81  4368.9  316.42  4454.8  314.33
  4524.3  310.55  4583.4  310.74  4796.6  308.23  4849.7  309.37  4870.3  309.47
  4903.2  306.21  4945.3  301.79  4962.9  301.02  4976.4  302.34  4983.4  299.11
  4983.9  298.61  4999.8  299.11  5043.3  309.08    5097  310.97  5715.3  311.22
  5813.7  311.14  6454.9  310.24  6502.1  310.16    6772  310.65  7182.1  312.26
  7234.4  311.23  7238.7  311.23  7703.5  311.15  8866.6  315.48 11105.8  317.59
#Mann= 17 ,-1 , 0
  4146.2    .035       0  4161.3     .07       0  4312.4      .1       0
  4368.9     .07       0  4583.4     .05       0  4796.6     .07       0
  4849.7     .05       0  4903.2     .07       0  4983.4     .05       0
  4999.8     .07       0  5715.3    .035       0  5813.7     .05       0
  6454.9    .035       0  6502.1     .05       0    6772    .045       0
  7234.4     .05       0  7238.7    .045       0
Bank Sta=4983.4,4999.8
XS Rating Curve= 0 ,0
Exp/Cntr=0.3,0.1

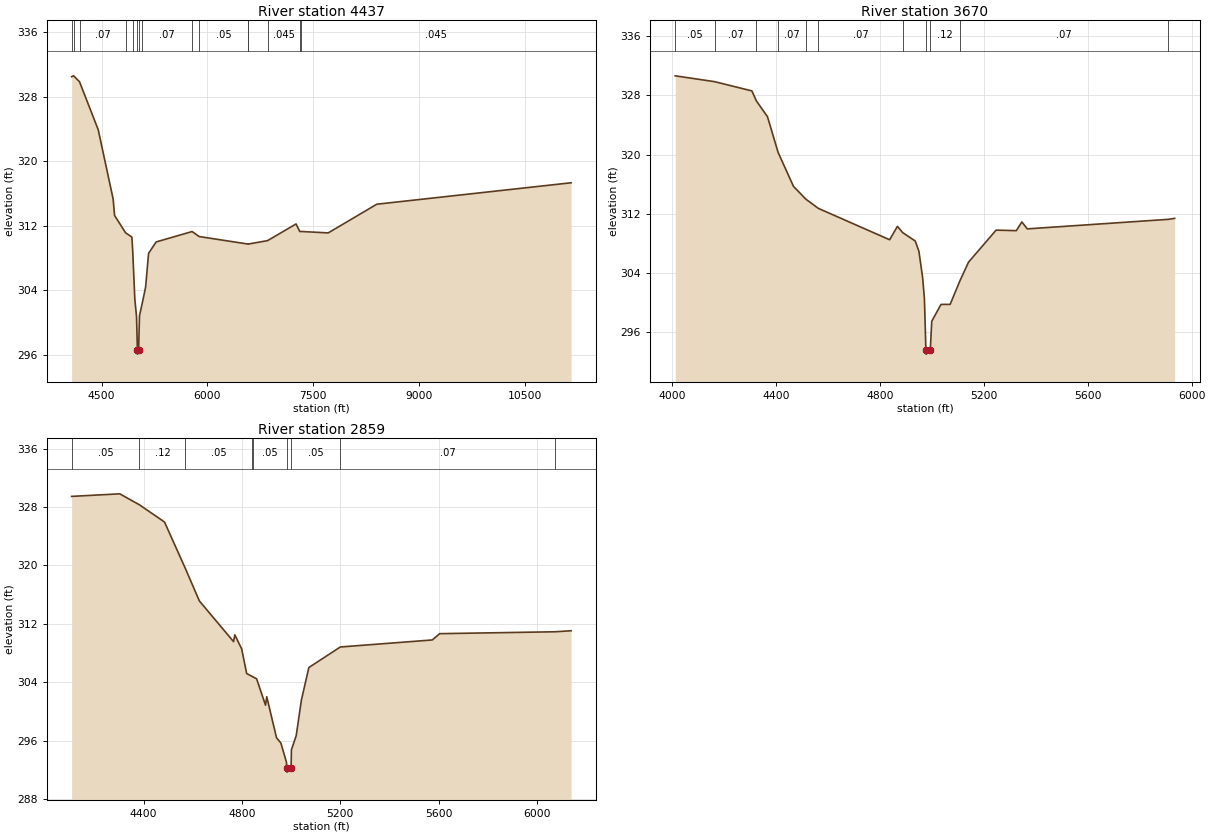
Type RM Length L Ch R = 1 ,4437    ,767,767,767
BEGIN DESCRIPTION:
X18060
END DESCRIPTION:
XS GIS Cut Line= 5
      2432499.33     13726832.61      2431702.09     13726931.03
      2431426.49     13727118.04      2430487.51     13727287.06
      2425505.41     13727619.53
#Sta/Elev= 30
  4073.9  330.49  4102.2   330.6  4185.5  329.87  4451.1  323.91  4662.7  315.31
  4682.8  313.28  4838.3  311.13  4928.4  310.59  4939.2  309.05  4970.4  302.86
  4994.3  300.73  5006.9  296.57  5007.4  296.07  5023.6  296.57  5036.2  300.83
  5077.6  302.47  5123.1  304.39    5165  308.57  5272.7  309.99  5782.6  311.28
  5883.1  310.66  6579.5  309.72  6579.8  309.73  6852.3  310.15    7257  312.22
  7310.1  311.28    7327  311.29  7712.8  311.11  8401.8  314.67 11157.5  317.33
#Mann= 15 ,-1 , 0
  4073.9     .05       0  4102.2    .035       0  4185.5     .07       0
  4838.3     .12       0  4939.2     .12       0  5006.9     .05       0
  5023.6     .12       0  5077.6     .07       0  5782.6    .035       0
  5883.1     .05       0  6579.5    .035       0  6579.8     .05       0
  6852.3    .045       0  7310.1     .05       0    7327    .045       0
Bank Sta=5006.9,5023.6
XS Rating Curve= 0 ,0
Exp/Cntr=0.3,0.1

Type RM Length L Ch R = 1 ,3670    ,811,811,811
BEGIN DESCRIPTION:
X18059
END DESCRIPTION:
XS GIS Cut Line= 3
      2432450.15     13726429.06      2431544.61     13726429.06
      2430835.91     13727157.44
#Sta/Elev= 30
  4012.8  330.65  4164.4  329.86  4307.9  328.61  4325.1  327.26  4367.9  325.12
  4408.9  320.28  4467.9   315.7  4515.2  313.98  4563.7  312.72  4837.9  308.48
  4867.9  310.29  4887.9  309.45  4936.4  308.31  4950.6  306.91  4964.7   303.4
  4971.7  300.54  4977.5  293.51    4978  293.01  4994.2  293.51    5000  297.46
  5035.5  299.73  5070.7  299.74  5108.3  302.92  5141.5  305.45  5247.5  309.78
  5325.4  309.71  5346.5  310.89  5367.8  309.95  5910.1  311.24  5934.6  311.37
#Mann= 11 ,-1 , 0
  4012.8     .05       0  4164.4     .07       0  4325.1     .05       0
  4408.9     .07       0  4515.2     .12       0  4563.7     .07       0
  4887.9     .12       0  4977.5     .05       0  4994.2     .12       0
  5108.3     .07       0  5910.1    .035       0
Bank Sta=4977.5,4994.2
XS Rating Curve= 0 ,0
Exp/Cntr=0.3,0.1

Type RM Length L Ch R = 1 ,2859    ,1064,1064,1064
BEGIN DESCRIPTION:
X18058
END DESCRIPTION:
XS GIS Cut Line= 3
      2432558.36     13726173.15      2431436.34     13725995.99
      2430540.65     13726025.52
#Sta/Elev= 30
  4107.2  329.45    4303   329.8  4382.5  328.31  4485.2  325.94  4570.3  319.56
  4626.9  315.15  4766.1  309.58  4771.1  310.51    4799  308.59  4819.3  305.22
  4842.3  304.81  4843.2  304.79  4859.8   304.5    4896  300.89  4901.1  302.04
  4940.8  296.43  4958.4  295.72  4981.3  293.09  4982.7  292.23  4983.2  291.73
    5000  292.23  5001.5   294.8  5020.9  296.71    5042  301.58  5072.4  306.04
  5200.4  308.85  5574.6  309.81  5604.7  310.67  6074.4  310.93  6139.3  311.07
#Mann= 9 ,-1 , 0
  4107.2     .05       0  4382.5     .12       0  4570.3     .05       0
  4842.3     .12       0  4843.2     .05       0  4982.7     .05       0
    5000     .05       0  5200.4     .07       0  6074.4     .05       0
Bank Sta=4982.7,5000
XS Rating Curve= 0 ,0
Exp/Cntr=0.3,0.1