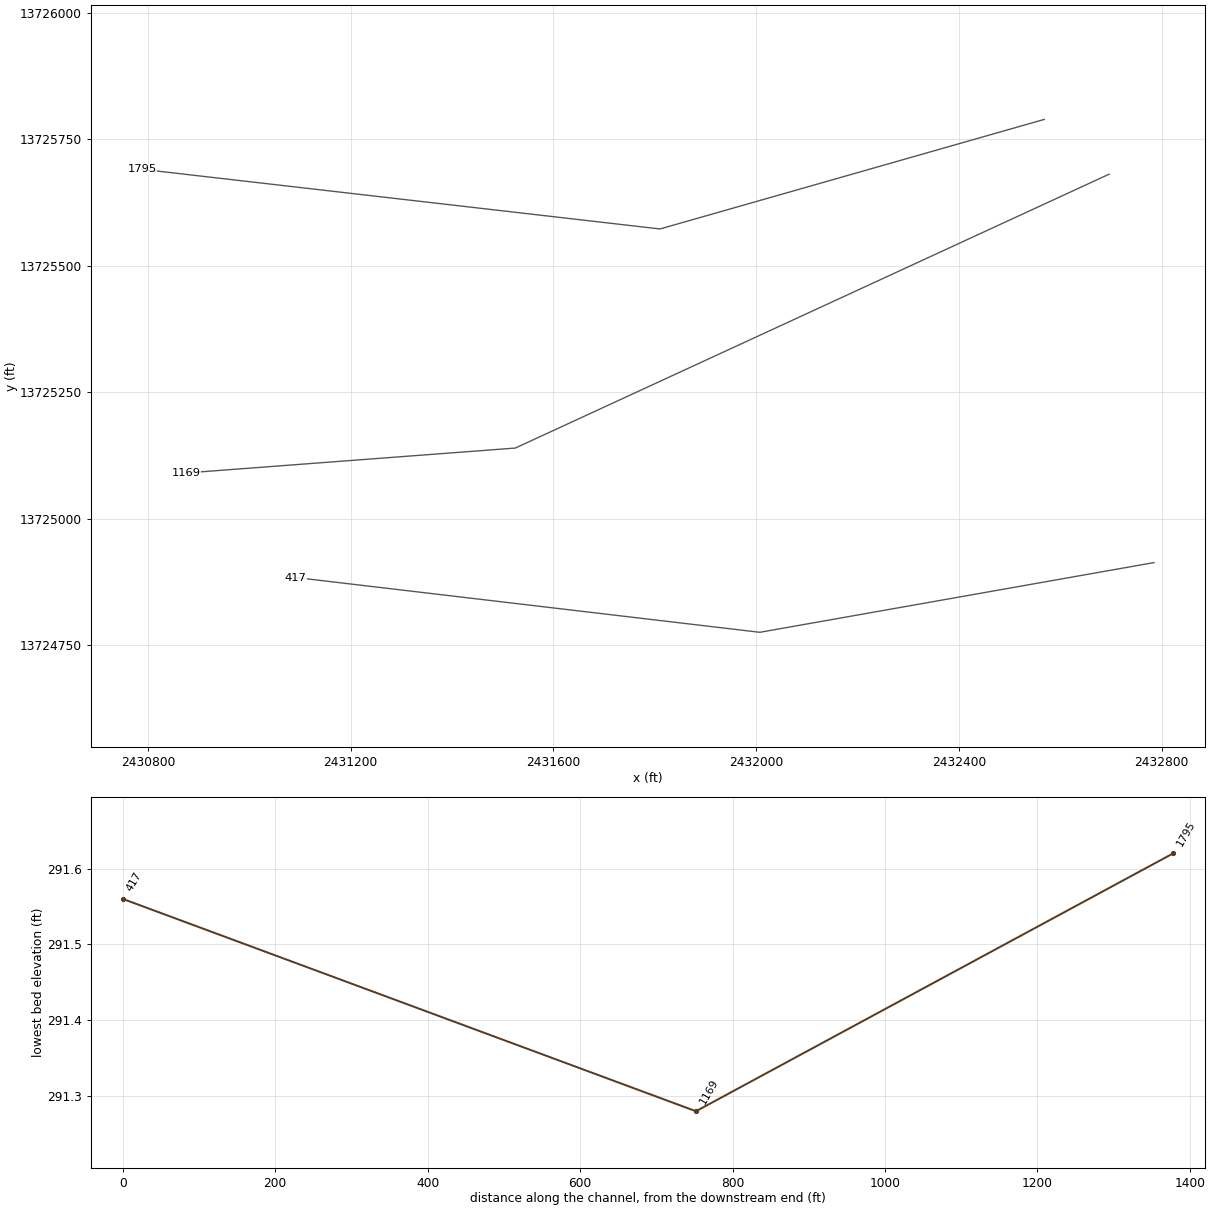
HEC-RAS study ANSWORTH BRANCH.prj: ANSWORTH BRANCH Base Level Engineering

--- ANSWORTH BRANCH.g01 (geometry) --- (continued)

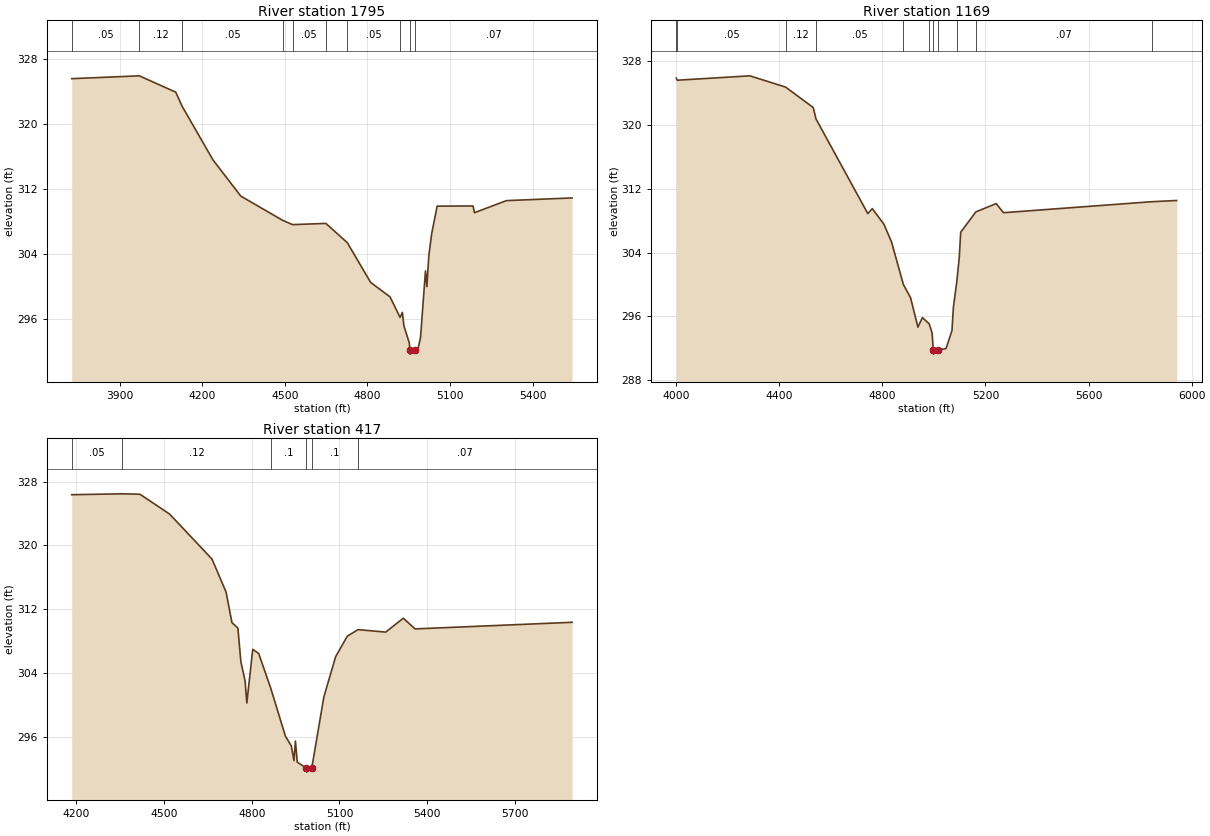
Type RM Length L Ch R = 1 ,1795    ,626,626,626
BEGIN DESCRIPTION:
X18057
END DESCRIPTION:
XS GIS Cut Line= 3
      2432568.22     13725789.29      2431810.35     13725572.76
      2430788.32     13725690.69
#Sta/Elev= 30
  3726.1  325.57  3971.5  325.92  4103.9  323.91  4127.7  322.13  4239.1  315.56
  4340.1   311.1  4492.1  308.11  4528.2  307.58  4649.1  307.73  4727.1  305.35
  4811.6  300.46  4882.1  298.68  4918.6  296.15  4926.9  296.77  4932.4  295.13
  4952.5  292.94  4953.9  292.12  4954.4  291.62  4971.2  292.12  4982.7  292.12
  4992.8  293.65  5010.8  301.88  5015.8  299.94    5023  303.76  5033.1  306.42
  5053.2  309.86  5183.6  309.88  5188.6  309.05  5304.9  310.54  5543.1  310.87
#Mann= 10 ,-1 , 0
  3726.1     .05       0  3971.5     .12       0  4127.7     .05       0
  4492.1     .12       0  4528.2     .05       0  4649.1     .12       0
  4727.1     .05       0  4918.6     .07       0  4953.9     .05       0
  4971.2     .07       0
Bank Sta=4953.9,4971.2
XS Rating Curve= 0 ,0
Exp/Cntr=0.3,0.1

Type RM Length L Ch R = 1 ,1169    ,752,752,752
BEGIN DESCRIPTION:
X18056
END DESCRIPTION:
XS GIS Cut Line= 3
      2432696.22     13725681.04      2431524.92     13725139.69
      2430875.33     13725090.48
#Sta/Elev= 30
  4000.1  325.86  4003.7   325.6  4285.5  326.15  4424.3  324.74  4531.4  322.18
  4542.4  320.74  4743.3  308.89  4760.7  309.51  4805.6  307.57    4835  305.37
  4881.5  299.99  4909.3  298.34  4937.8  294.66  4955.2  295.86  4981.6  295.08
  4992.9  293.91  4997.5  291.78    4998  291.28  5015.6  291.78  5046.9  291.98
  5069.9  294.23  5075.4  297.15  5088.7  300.36  5098.3  303.43  5103.8  306.55
  5162.5   309.1  5241.4  310.14  5269.9     309  5846.3  310.38  5941.9  310.53
#Mann= 11 ,-1 , 0
  4000.1     .07       0  4003.7     .05       0  4424.3     .12       0
  4542.4     .05       0  4881.5     .12       0  4981.6     .05       0
  4997.5     .05       0  5015.6     .05       0  5088.7     .12       0
  5162.5     .07       0  5846.3     .05       0
Bank Sta=4997.5,5015.6
XS Rating Curve= 0 ,0
Exp/Cntr=0.3,0.1

Type RM Length L Ch R = 1 ,417     ,0,0,0
BEGIN DESCRIPTION:
X18055
END DESCRIPTION:
XS GIS Cut Line= 3
      2432784.77     13724913.31       2432007.2     13724775.51
      2431091.86     13724883.78
#Sta/Elev= 30
  4184.2  326.37  4356.7  326.48  4417.5  326.43  4519.1  323.94    4664   318.3
  4712.1  314.17  4732.4  310.31  4752.7  309.64  4762.8  305.42  4777.2  303.02
  4783.2  300.24  4803.5  306.96  4823.8  306.45  4865.2  302.07  4915.2  296.08
  4935.5  294.83  4944.4     293  4949.4  295.46  4955.8  292.81  4987.1  292.06
  4987.6  291.56  5005.3  292.06  5046.6  300.98  5086.9  306.04  5127.1  308.63
  5163.6  309.44    5258  309.13  5318.5  310.87  5358.7  309.53  5895.6  310.36
#Mann= 6 ,-1 , 0
  4184.2     .05       0  4356.7     .12       0  4865.2      .1       0
  4987.1     .05       0  5005.3      .1       0  5163.6     .07       0
Bank Sta=4987.1,5005.3
XS Rating Curve= 0 ,0
Exp/Cntr=0.3,0.1

Chan Stop Cuts=-1
Use User Specified Reach Order=0
Composite Channel Slope=5