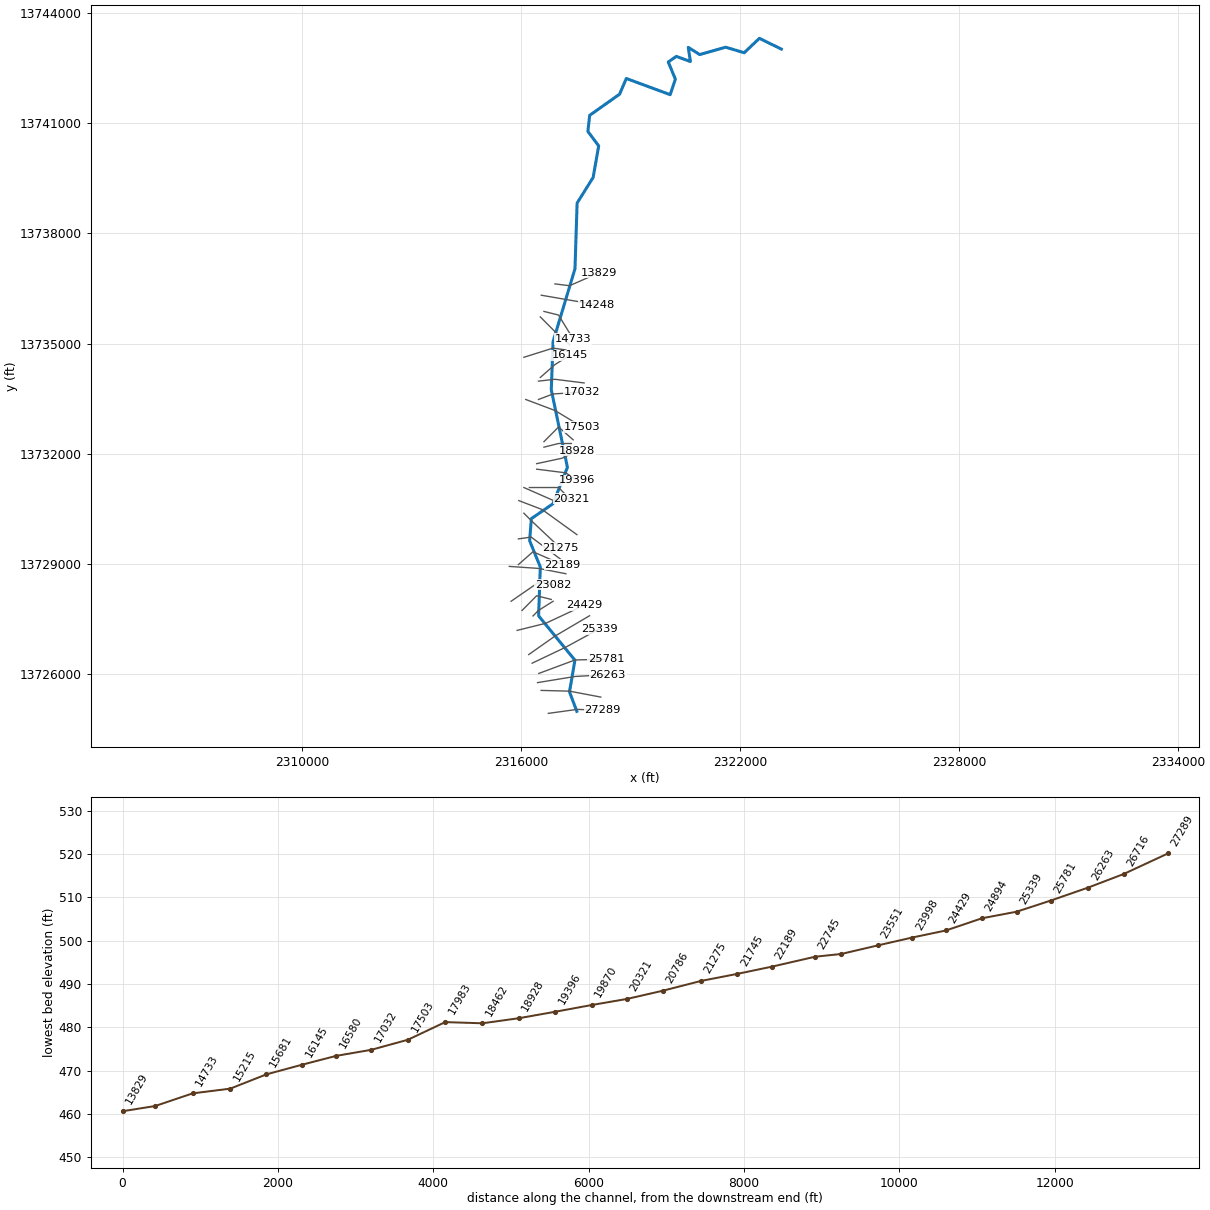
--- CANTAU CREEK.prj (project) ---

Proj Title=CANTAU CREEK Base Level Engineering
Current Plan=p01
Default Exp/Contr=0.3,0.1
English Units
Geom File=g01
Flow File=f01
Plan File=p01
Y Axis Title=Elevation
X Axis Title(PF)=Main Channel Distance
X Axis Title(XS)=Station
BEGIN DESCRIPTION:
CANTAU CREEK
END DESCRIPTION:
DSS Export Rating Curves= 0
DSS Export Rating Curve Sorted= 0
DSS Export Volume Flow Curves= 0
DXF OffsetX= 0
DXF OffsetY= 0
DXF ScaleX= 1
DXF ScaleY= 10

--- CANTAU CREEK.p01 (plan) ---

Plan Title=Multiple Run
Program Version=4.10
Short Identifier=Multiple
Geom File=g01
Flow File=f01
Subcritical Flow
K Sum by GR= 0
Std Step Tol= 0.01
Critical Tol= 0.01
Num of Std Step Trials= 20
Max Error Tol= 0.3
Flow Tol Ratio= 0.001
Split Flow NTrial= 30
Split Flow Tol= 0.02
Split Flow Ratio= 0.02
Log Output Level= 0
Friction Slope Method= 1
Unsteady Friction Slope Method= 2
Unsteady Bridges Friction Slope Method= 1
Parabolic Critical Depth
Global Vel Dist= 1 , 1 , 1
Global Log Level= 0
CheckData=True
Encroach Param=-1 ,0,0, 0
BEGIN DESCRIPTION:
Multiple Run
END DESCRIPTION:
Computation Interval=1HOUR
Output Interval=1HOUR
Run HTab= 0
Run UNet= 0
Run PostProcess= 0
Run WQNet= 0
UNET Theta= 1
UNET Theta Warmup= 1
UNET ZTol= 0.02
UNET ZSATol= 0.05
UNET MxIter= 20
UNET MaxInSteps= 0
UNET DtIC= 0
UNET DtMin= 0
UNET MaxCRTS= 20
UNET WFStab= 2
UNET SFStab= 1
UNET WFX= 1
UNET SFX= 1
UNET DSS MLevel= 4
UNET DZMax Abort= 100
UNET Convert EG Bridges= 0
UNET Use Existing IB Tables=-1
UNET Froude Reduction=False
UNET Froude Limit= 1
UNET Froude Power= 10
UNET Time Slicing=0,0, 5
UNET Junction Losses=0
Instantaneous Interval=1HOUR
Write IC File= 0
Write IC File at Sim End=0
Echo Input=False
Echo Parameters=False
Echo Output=False
Write Detailed= 0
WQ AD Non Conservative
WQ ULTIMATE=-1
WQ Max Comp Step=1HOUR
WQ Output Interval=15MIN
WQ Output Selected Increments= 0
WQ Output face flow=0
WQ Output face velocity=0
WQ Output face area=0
WQ Output face dispersion=0
WQ Output cell volume=0
WQ Output cell surface area=0
WQ Output cell continuity=0
WQ Output cumulative cell continuity=0
WQ Output face conc=0
WQ Output face dconc_dx=0
WQ Output face courant=0
WQ Output face peclet=0
WQ Output face adv mass=0
WQ Output face disp mass=0
WQ Output cell mass=0
WQ Output cell source sink temp=0
WQ Output cell source sink nsm=0
WQ Output MaxMinRange=-1
WQ Daily Max Min Mean=-1
WQ Daily Range=0
WQ Daily Time=0
WQ Create Restart=0
WQ Fixed Restart=0
WQ System Summary=0
WQ Use Fixed Temperature=0
Sorting and Armoring Iterations= 10
XS Update Threshold= 0.02
Hydraulics Update Threshold= 0.02
Energy Slope Method= 1
Volume Change Method= 0
XS Weighting Method= 0
Number of US Weighted Cross Sections= 1
Number of DS Weighted Cross Sections= 1
Upstream XS Weight=0.25
Main XS Weight=0.5
Downstream XS Weight=0.25
Number of DS XS's Weighted with US Boundary= 1
Upstream Boundary Weight= 1
Weight of XSs Associated with US Boundary= 0
Number of US XS's Weighted with DS Boundary= 1
Downstream Boundary Weight= 0.5
Weight of XSs Associated with DS Boundary= 0.5
Sediment Output Level= 4
Mass or Volume Output= 0
Output Increment Type= 1
Profile and TS Output Increment= 10
XS Output Flag= 0
XS Output Increment= 10
Disregard all LS=0
Disregard all Conn=0
Disregard all Breaches=0
Disregard all Pumps=0

--- CANTAU CREEK.f01 (steady flow) ---

Flow Title=Multiple
Number of Profiles=7
Profile Names=10-year,25-year,50-year,1pct_min,100-year,1pct_plu,500-year
River Rch & RM= CANTAU CREEK,Reach-1,27289
    1116    1898    2642    1782    3556    7096    6385
River Rch & RM= CANTAU CREEK,Reach-1,26716
    1492    2561    3588    2431    4850    9678    8792
River Rch & RM= CANTAU CREEK,Reach-1,18928
    1610    2762    3867    2616    5220   10416    9438
River Rch & RM= CANTAU CREEK,Reach-1,14248
    1977    3424    4824    3282    6549   13066   11974
River Rch & RM= CANTAU CREEK,Reach-1,12399
    1930    3324    4664    3160    6304   12579   11426
River Rch & RM= CANTAU CREEK,Reach-1,8200
    2226    3855    5430    3691    7364   14693   13435
River Rch & RM= CANTAU CREEK,Reach-1,6864
    2251    3888    5464    3705    7392   14749   13423
Boundary for River Rch & Prof#=CANTAU CREEK,Reach-1,1
Up Type=0
Dn Type=3
Dn Slope=0.005
Boundary for River Rch & Prof#=CANTAU CREEK,Reach-1,2
Up Type=0
Dn Type=3
Dn Slope=0.005
Boundary for River Rch & Prof#=CANTAU CREEK,Reach-1,3
Up Type=0
Dn Type=3
Dn Slope=0.005
Boundary for River Rch & Prof#=CANTAU CREEK,Reach-1,4
Up Type=0
Dn Type=3
Dn Slope=0.005
Boundary for River Rch & Prof#=CANTAU CREEK,Reach-1,5
Up Type=0
Dn Type=3
Dn Slope=0.005
Boundary for River Rch & Prof#=CANTAU CREEK,Reach-1,6
Up Type=0
Dn Type=3
Dn Slope=0.005
Boundary for River Rch & Prof#=CANTAU CREEK,Reach-1,7
Up Type=0
Dn Type=3
Dn Slope=0.005

--- CANTAU CREEK.g01 (geometry) ---

Geom Title=Existing Conditions
Program Version=4.10

River Reach=CANTAU CREEK    ,Reach-1
Reach XY= 30
        2317525.       13724975.      2317324.41     13725504.95
      2317472.76     13726369.07      2316478.54     13727576.46
      2316524.66     13728909.96      2316232.53     13729625.01
      2316280.09      13730227.3      2316871.95     13730633.28
      2317267.47     13731625.01      2316825.52     13733740.22
      2316875.07     13735054.97       2317474.4     13737035.62
      2317532.81     13738828.41      2317971.46     13739526.46
       2318123.8     13740385.51      2317827.04     13740780.85
      2317877.24     13741219.07      2318695.49     13741794.79
      2318880.71     13742223.11      2320081.07     13741782.45
      2320224.93     13742204.97      2320028.52     13742673.54
      2320250.13     13742825.55      2320635.24     13742685.35
      2320576.39     13743071.98      2320890.22     13742875.25
      2321599.97      13743075.5      2322109.78     13742925.52
       2322524.9     13743317.72        2323125.       13743025.

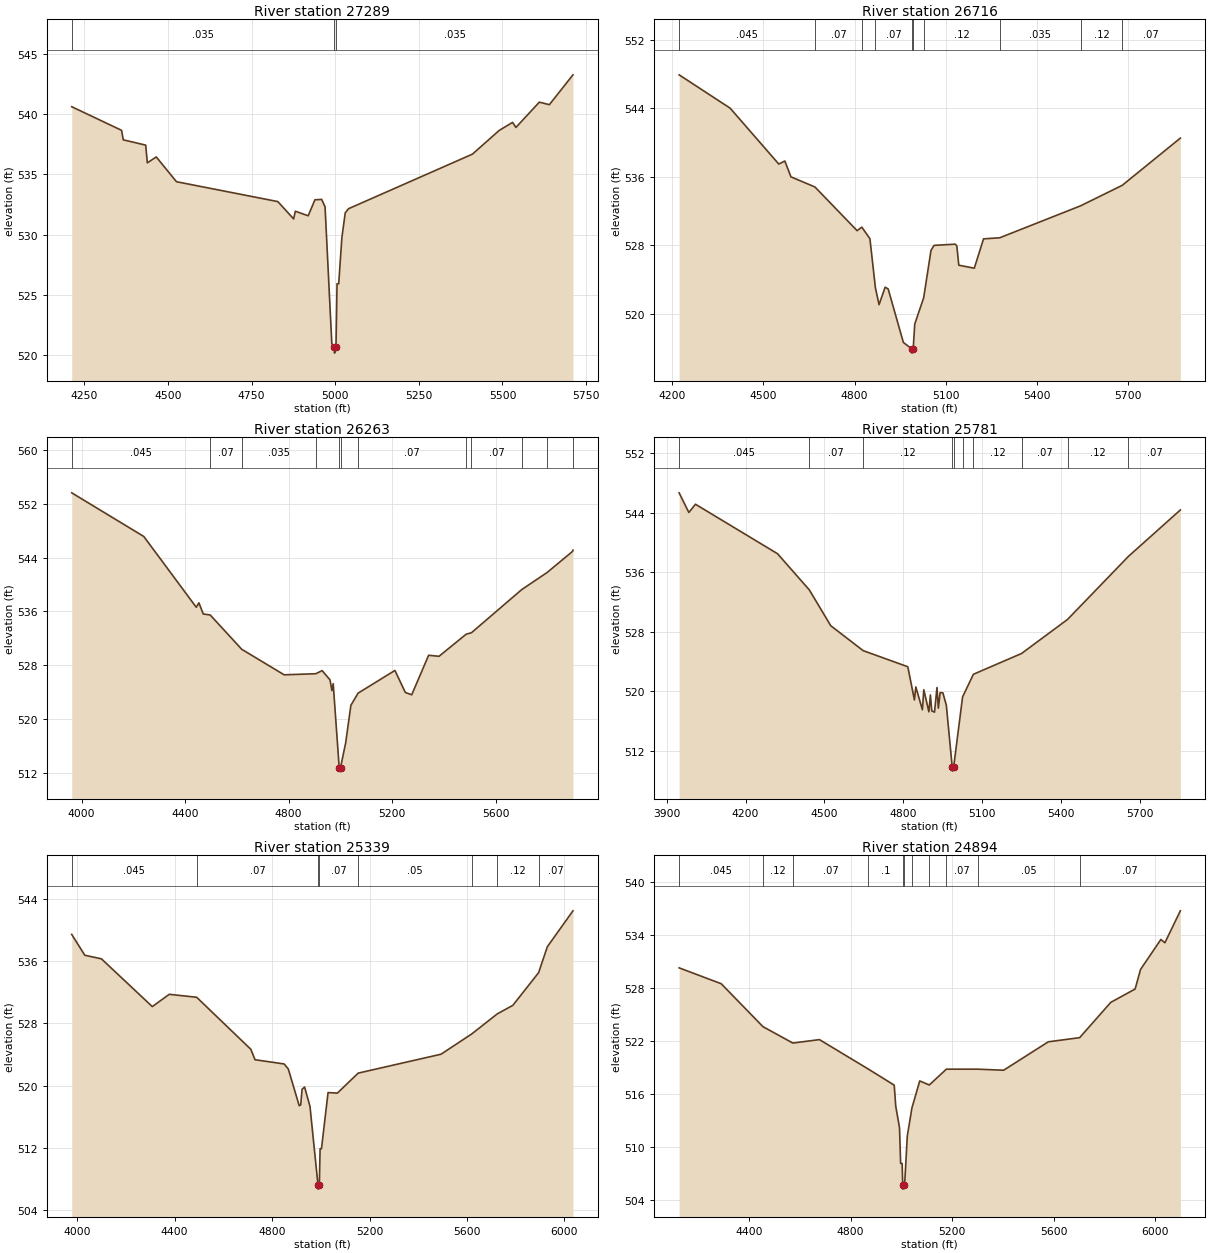
Type RM Length L Ch R = 1 ,27289   ,573,573,573
BEGIN DESCRIPTION:
CANTAU CREEK 51.0
END DESCRIPTION:
XS GIS Cut Line= 3
      2316744.67      13724919.4      2317531.05     13725027.48
      2318235.42     13725005.11
#Sta/Elev= 30
  4212.2  540.63  4361.2  538.67  4366.3  537.88  4433.3  537.44  4438.3  535.97
  4464.9  536.46  4525.4   534.4  4828.3  532.75  4875.7  531.31  4880.7  531.95
  4919.1  531.57  4939.3   532.9  4959.5  532.93  4969.6  532.31  4989.8  520.94
  4997.5  520.66  4997.9  520.16  5002.2  520.66  5005.4  525.92  5010.4  525.92
  5019.9  529.77  5029.9  531.81  5039.9  532.16  5410.1  536.69  5490.2  538.66
  5530.2  539.33  5540.2  538.91  5610.2  541.01  5640.2   540.8  5710.7  543.28
#Mann= 3 ,-1 , 0
  4212.2    .035       0  4997.5    .035       0  5002.2    .035       0
Bank Sta=4997.5,5002.2
XS Rating Curve= 0 ,0
Exp/Cntr=0.3,0.1

Type RM Length L Ch R = 1 ,26716   ,453,453,453
BEGIN DESCRIPTION:
CANTAU CREEK 50.0
END DESCRIPTION:
XS GIS Cut Line= 3
      2316547.07     13725545.53        2317325.       13725525.
      2318181.66     13725363.21
#Sta/Elev= 30
  4222.6  547.93  4390.6  544.03  4550.6   537.5  4570.6  537.85  4590.7     536
  4669.6  534.82  4808.5  529.71    4824  530.12  4850.7  528.77  4868.7  523.04
  4880.8  521.06  4900.8   523.1  4910.8  522.89  4960.8  516.64  4988.4  515.89
  4988.8  515.39  4993.1  515.89  4998.3  518.79  5027.7  521.87  5051.7   527.4
  5061.9  527.99  5131.8  528.13  5136.8  527.92  5143.3  525.67  5194.3  525.32
  5224.7  528.75  5278.3  528.88    5544  532.61  5681.3  535.01  5872.6  540.53
#Mann= 10 ,-1 , 0
  4222.6    .045       0  4669.6     .07       0    4824    .035       0
  4868.7     .07       0  4988.4     .05       0  4993.1     .07       0
  5027.7     .12       0  5278.3    .035       0    5544     .12       0
  5681.3     .07       0
Bank Sta=4988.4,4993.1
XS Rating Curve= 0 ,0
Exp/Cntr=0.3,0.1

Type RM Length L Ch R = 1 ,26263   ,482,482,482
BEGIN DESCRIPTION:
CANTAU CREEK 49.0
END DESCRIPTION:
XS GIS Cut Line= 3
       2316450.2     13725757.96        2317475.       13725925.
      2318371.63     13725974.04
#Sta/Elev= 30
    3962  553.61  4240.4  547.13  4443.1  536.62  4453.2  537.28  4470.2  535.62
  4496.8  535.48  4618.8  530.38  4782.6  526.59  4904.8  526.75  4929.4  527.21
  4959.8  525.84  4967.1  524.25  4972.1  525.28  4995.3  512.79  4995.6  512.29
  5000.3  512.79  5020.4  516.52  5040.4  522.06  5068.3  523.87  5210.6  527.24
  5250.7  523.97  5275.4  523.62  5340.8  529.49  5380.9  529.34  5485.8  532.62
  5506.3  532.84  5700.3  539.24  5798.8  541.79  5897.2  544.93  5898.3   545.1
#Mann= 12 ,-1 , 0
    3962    .045       0  4496.8     .07       0  4618.8    .035       0
  4904.8     .12       0  4995.3     .05       0  5000.3     .12       0
  5068.3     .07       0  5485.8     .12       0  5506.3     .07       0
  5700.3     .12       0  5798.8     .07       0  5897.2     .12       0
Bank Sta=4995.3,5000.3
XS Rating Curve= 0 ,0
Exp/Cntr=0.3,0.1

Type RM Length L Ch R = 1 ,25781   ,442,442,442
BEGIN DESCRIPTION:
CANTAU CREEK 48.0
END DESCRIPTION:
XS GIS Cut Line= 3
       2316483.8     13726007.69        2317475.       13726375.
      2318324.89     13726395.29
#Sta/Elev= 30
    3947  546.67    3984  544.03  4009.1  545.14  4321.5  538.49  4442.7  533.62
    4524  528.82  4647.5  525.47  4817.2  523.31  4842.3  518.85  4847.6   520.6
  4872.7  517.53    4878  520.22  4897.4  517.25  4903.1  519.52  4908.4  517.38
  4918.8  517.21  4928.1  520.52  4933.4  517.75  4940.1  519.84  4950.7   519.8
  4963.8  518.13  4986.3  509.79  4986.7  509.29  4991.4  509.79  5025.6  519.26
  5066.8   522.3    5250  525.09  5425.2  529.67  5656.5  538.13  5854.2  544.37
#Mann= 10 ,-1 , 0
    3947    .045       0  4442.7     .07       0  4647.5     .12       0
  4986.3     .05       0  4991.4     .12       0  5025.6     .07       0
  5066.8     .12       0    5250     .07       0  5425.2     .12       0
  5656.5     .07       0
Bank Sta=4986.3,4991.4
XS Rating Curve= 0 ,0
Exp/Cntr=0.3,0.1

Type RM Length L Ch R = 1 ,25339   ,445,445,445
BEGIN DESCRIPTION:
CANTAU CREEK 47.0
END DESCRIPTION:
XS GIS Cut Line= 3
       2316301.1     13726287.19        2317225.       13726725.
      2318134.78     13727218.93
#Sta/Elev= 30
  3977.4  539.44  4031.1  536.76  4099.3   536.3  4308.2  530.16  4377.8  531.74
  4490.3  531.36  4712.7  524.67    4730  523.33  4849.2  522.79  4866.4  522.15
  4911.3  517.42  4917.4  517.53    4923  519.54  4933.4  519.82  4955.5  517.33
  4988.5   507.2    4989   506.7  4993.8   507.2    4997  511.89  5002.6  511.89
  5029.7  519.11  5067.8  519.04  5153.4  521.61  5493.5  524.04  5620.1  526.66
  5724.1  529.22  5788.2  530.32    5894  534.52  5929.8  537.85    6035  542.47
#Mann= 8 ,-1 , 0
  3977.4    .045       0  4490.3     .07       0  4988.5     .05       0
  4993.8     .07       0  5153.4     .05       0  5620.1     .07       0
  5724.1     .12       0    5894     .07       0
Bank Sta=4988.5,4993.8
XS Rating Curve= 0 ,0
Exp/Cntr=0.3,0.1

Type RM Length L Ch R = 1 ,24894   ,465,465,465
BEGIN DESCRIPTION:
CANTAU CREEK 46.0
END DESCRIPTION:
XS GIS Cut Line= 3
      2316207.99     13726522.03        2316925.       13727025.
      2317873.51     13727580.23
#Sta/Elev= 30
  4124.4  530.26  4290.3  528.46  4454.6   523.6  4572.4  521.74  4677.3  522.13
    4870  518.79  4971.9  516.97    4978  514.57  4992.8  512.15  4997.2   508.1
  5003.1   508.1  5005.4  505.69  5005.8  505.19  5010.7  505.69  5013.9   506.2
  5023.4  511.19  5041.6  514.38  5072.5  517.45  5110.1  516.99  5177.3  518.78
  5301.1  518.78    5403  518.66    5579  521.88  5702.5  522.35  5825.2  526.35
  5921.1  527.86  5942.5  530.08  6022.7  533.48  6038.4   533.1  6099.3  536.72
#Mann= 11 ,-1 , 0
  4124.4    .045       0  4454.6     .12       0  4572.4     .07       0
    4870      .1       0  5005.4     .05       0  5010.7      .1       0
  5041.6     .07       0  5110.1     .05       0  5177.3     .07       0
  5301.1     .05       0  5702.5     .07       0
Bank Sta=5005.4,5010.7
XS Rating Curve= 0 ,0
Exp/Cntr=0.3,0.1

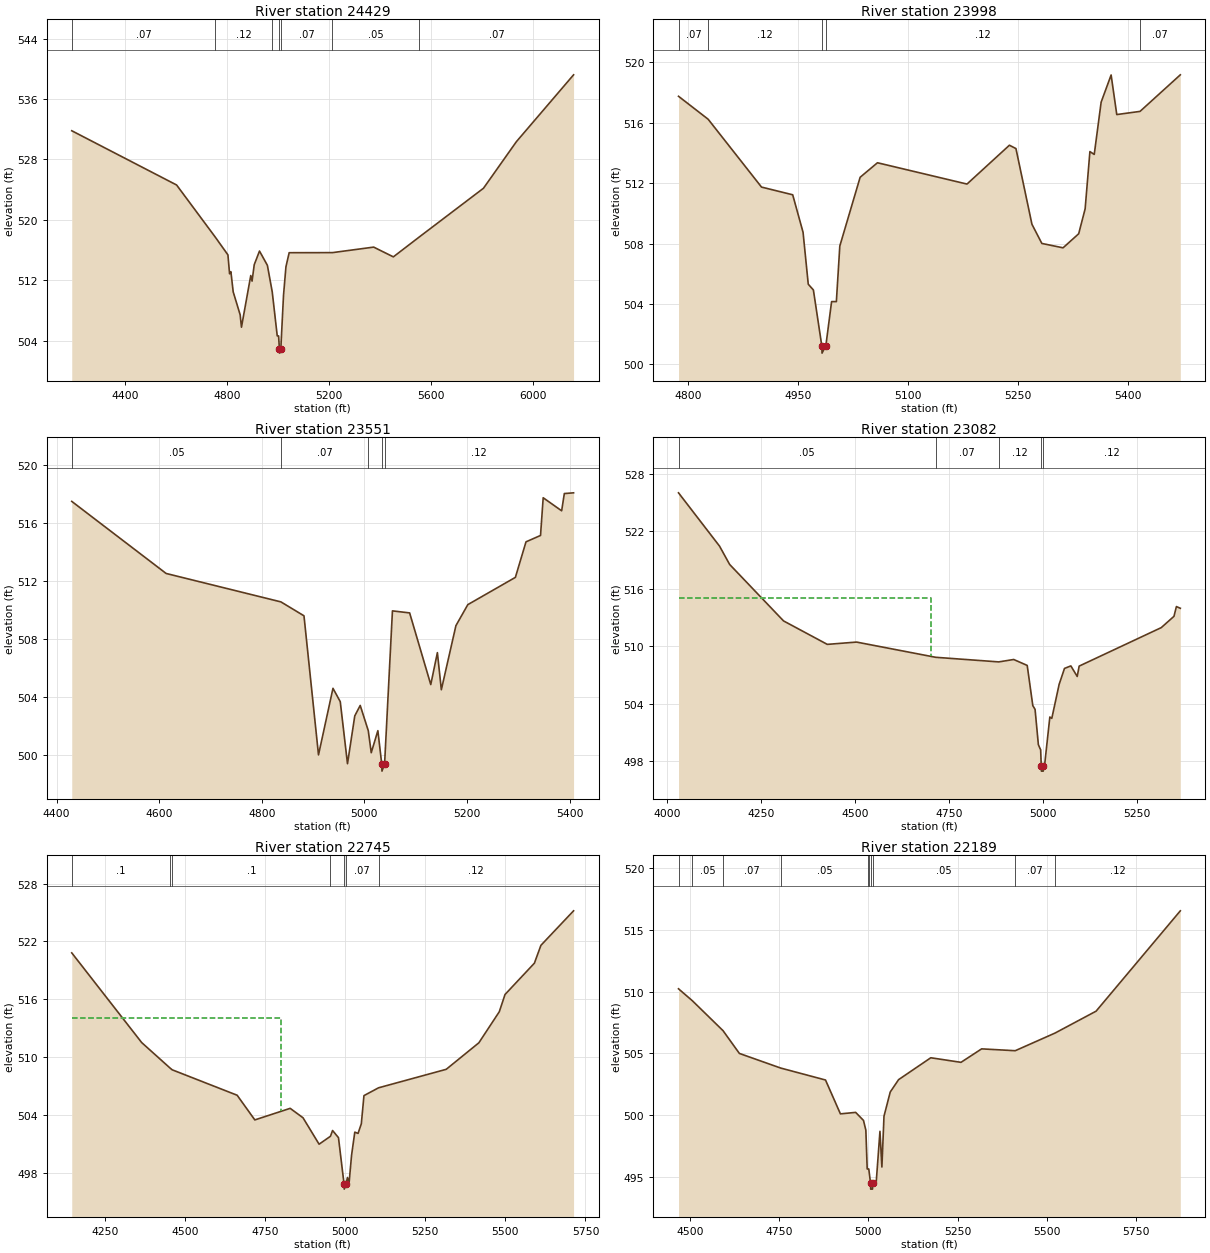
Type RM Length L Ch R = 1 ,24429   ,431,431,431
BEGIN DESCRIPTION:
CANTAU CREEK 45.0
END DESCRIPTION:
XS GIS Cut Line= 3
      2315891.14     13727181.68        2316675.       13727375.
      2317724.87     13727863.73
#Sta/Elev= 30
  4192.6   531.8  4603.3  524.62  4754.8  517.72  4804.3  515.37  4810.7  512.87
  4815.9  513.15  4824.9  510.48  4852.2  507.44  4857.3   505.8  4893.7  512.64
  4898.8   511.9  4907.3  514.07  4927.9  515.88  4958.8  513.99  4977.8  510.48
  4997.4  504.65  5002.7  504.65    5006  502.87  5006.4  502.37  5011.3  502.87
    5022  510.03  5031.5   513.8  5044.1  515.66  5213.8  515.67    5375   516.4
  5452.2  515.11  5554.1  517.75  5805.2  524.19    5934  530.35    6158   539.2
#Mann= 7 ,-1 , 0
  4192.6     .07       0  4754.8     .12       0  4977.8     .07       0
    5006     .05       0  5011.3     .07       0  5213.8     .05       0
  5554.1     .07       0
Bank Sta=5006,5011.3
XS Rating Curve= 0 ,0
Exp/Cntr=0.3,0.1

Type RM Length L Ch R = 1 ,23998   ,447,447,447
BEGIN DESCRIPTION:
CANTAU CREEK 44.0
END DESCRIPTION:
XS GIS Cut Line= 3
        2316325.       13727575.        2316475.       13727725.
      2316874.98     13727974.99
#Sta/Elev= 30
  4787.4  517.75  4827.8  516.23  4900.5  511.74    4943  511.23  4957.1  508.75
  4964.2  505.31  4971.2  504.93  4982.6  501.25    4983  500.75  4988.2  501.25
    4996  504.16  5002.5  504.16  5007.2  507.84  5034.9  512.39  5058.5  513.35
  5180.5  511.94  5238.3  514.51  5247.2  514.29    5269  509.28  5282.5  508.01
  5311.4  507.72  5332.7  508.65  5341.5   510.3    5348  514.09  5353.9   513.9
  5363.3  517.36  5376.9  519.16  5384.6  516.54  5416.3  516.75  5471.2  519.17
#Mann= 5 ,-1 , 0
  4787.4     .07       0  4827.8     .12       0  4982.6     .05       0
  4988.2     .12       0  5416.3     .07       0
Bank Sta=4982.6,4988.2
XS Rating Curve= 0 ,0
Exp/Cntr=0.3,0.1

Type RM Length L Ch R = 1 ,23551   ,469,469,469
BEGIN DESCRIPTION:
CANTAU CREEK 43.0
END DESCRIPTION:
XS GIS Cut Line= 3
      2316024.98     13727724.98        2316425.       13728125.
      2316824.98       13728025.
#Sta/Elev= 30
  4429.7  517.52  4613.6  512.55  4837.3  510.59  4882.3  509.63  4910.6  500.04
  4938.8  504.63    4953  503.71  4967.1  499.43  4981.3  502.73  4991.9  503.45
  5007.6  501.71  5013.4  500.19  5026.3  501.71  5033.8  499.42  5034.3  498.92
  5039.4  499.42  5054.7  509.97  5088.2  509.83  5129.4  504.89  5142.3  507.09
    5150  504.53  5178.4  508.95  5201.6   510.4  5294.3  512.28    5315  514.73
  5343.3  515.17  5348.5  517.77  5384.5  516.87  5389.7  518.06  5407.7  518.11
#Mann= 5 ,-1 , 0
  4429.7     .05       0  4837.3     .07       0  5007.6     .12       0
  5033.8     .05       0  5039.4     .12       0
Bank Sta=5033.8,5039.4
XS Rating Curve= 0 ,0
Exp/Cntr=0.3,0.1

Type RM Length L Ch R = 1 ,23082   ,337,337,337
BEGIN DESCRIPTION:
CANTAU CREEK 42.0
END DESCRIPTION:
XS GIS Cut Line= 3
      2315724.97     13727974.98        2316525.       13728525.
      2316875.03     13728424.99
#Sta/Elev= 30
  4029.6  526.02  4138.6  520.46  4165.6  518.54    4309  512.64  4425.4  510.19
  4503.2  510.43  4713.7  508.84  4881.4  508.36  4921.3  508.61  4957.2  507.99
  4972.1  503.79  4978.1   503.4  4986.9  499.71    4993  499.17  4994.6  497.45
    4995  496.95  4999.8  496.95  5000.3  497.45  5003.1  497.45  5017.4   502.6
  5022.6  502.46  5042.1  506.01  5056.4  507.68  5073.3  507.94  5090.2  506.84
  5095.4  507.92  5313.8  511.94  5347.6  513.12  5354.1  514.14  5364.5  513.96
#Mann= 5 ,-1 , 0
  4029.6     .05       0  4713.7     .07       0  4881.4     .12       0
  4994.6     .05       0  5000.3     .12       0
#XS Ineff= 2 , 0
       0    4700     515               0
Permanent Ineff=
       F       F
Bank Sta=4994.6,5000.3
XS Rating Curve= 0 ,0
Exp/Cntr=0.3,0.1

Type RM Length L Ch R = 1 ,22745   ,556,556,556
BEGIN DESCRIPTION:
CANTAU CREEK 41.0
END DESCRIPTION:
XS GIS Cut Line= 3
      2315674.97       13728925.      2316483.76     13728870.01
      2317224.96     13728725.01
#Sta/Elev= 30
    4147  520.82  4365.3  511.51  4453.8  508.87  4460.3  508.69  4663.1  506.05
  4718.3  503.49  4828.6  504.69  4868.7  503.71  4918.8  500.97  4954.2  501.79
  4960.9  502.39  4979.3  501.65  4996.8  496.81  4997.3  496.31  5002.5  496.81
  5007.3  497.52  5012.4  496.95  5020.1  499.81  5030.2  502.22  5040.4  502.09
  5050.6  503.09  5058.8  506.01  5104.3  506.82  5315.6  508.74  5417.4  511.49
  5481.1  514.71    5499   516.5  5590.7  519.75    5611   521.6  5712.9  525.18
#Mann= 7 ,-1 , 0
    4147      .1       0  4453.8      .1       0  4460.3      .1       0
  4954.2     .07       0  4996.8     .05       0  5002.5     .07       0
  5104.3     .12       0
#XS Ineff= 2 , 0
       0    4800  514.09               0
Permanent Ineff=
       F       F
Bank Sta=4996.8,5002.5
XS Rating Curve= 0 ,0
Exp/Cntr=0.3,0.1

Type RM Length L Ch R = 1 ,22189   ,444,444,444
BEGIN DESCRIPTION:
CANTAU CREEK 40.0
END DESCRIPTION:
XS GIS Cut Line= 3
      2315924.98     13728974.99        2316325.       13729325.
      2317124.96     13728975.02
#Sta/Elev= 30
  4468.5  510.23  4507.4  509.26  4593.2  506.84  4638.9     505  4754.2  503.82
    4880  502.85  4921.7  500.11  4964.4  500.23  4986.3  499.58  4992.9  498.79
  4996.7  495.65  4999.3  495.65  5001.1  495.65    5006  494.52  5006.5  494.02
  5011.5  494.02    5012  494.52  5021.9  494.57  5032.4   498.7  5037.8  495.81
  5043.7  499.92  5061.2  501.88  5084.6  502.88  5174.7  504.65  5259.3  504.28
    5317  505.37  5411.1  505.22  5522.6  506.65  5637.4  508.42  5873.2  516.54
#Mann= 10 ,-1 , 0
  4468.5     .07       0  4507.4     .05       0  4593.2     .07       0
  4754.2     .05       0  4999.3     .07       0  5001.1     .05       0
    5006     .05       0    5012     .05       0  5411.1     .07       0
  5522.6     .12       0
Bank Sta=5006,5012
XS Rating Curve= 0 ,0
Exp/Cntr=0.3,0.1

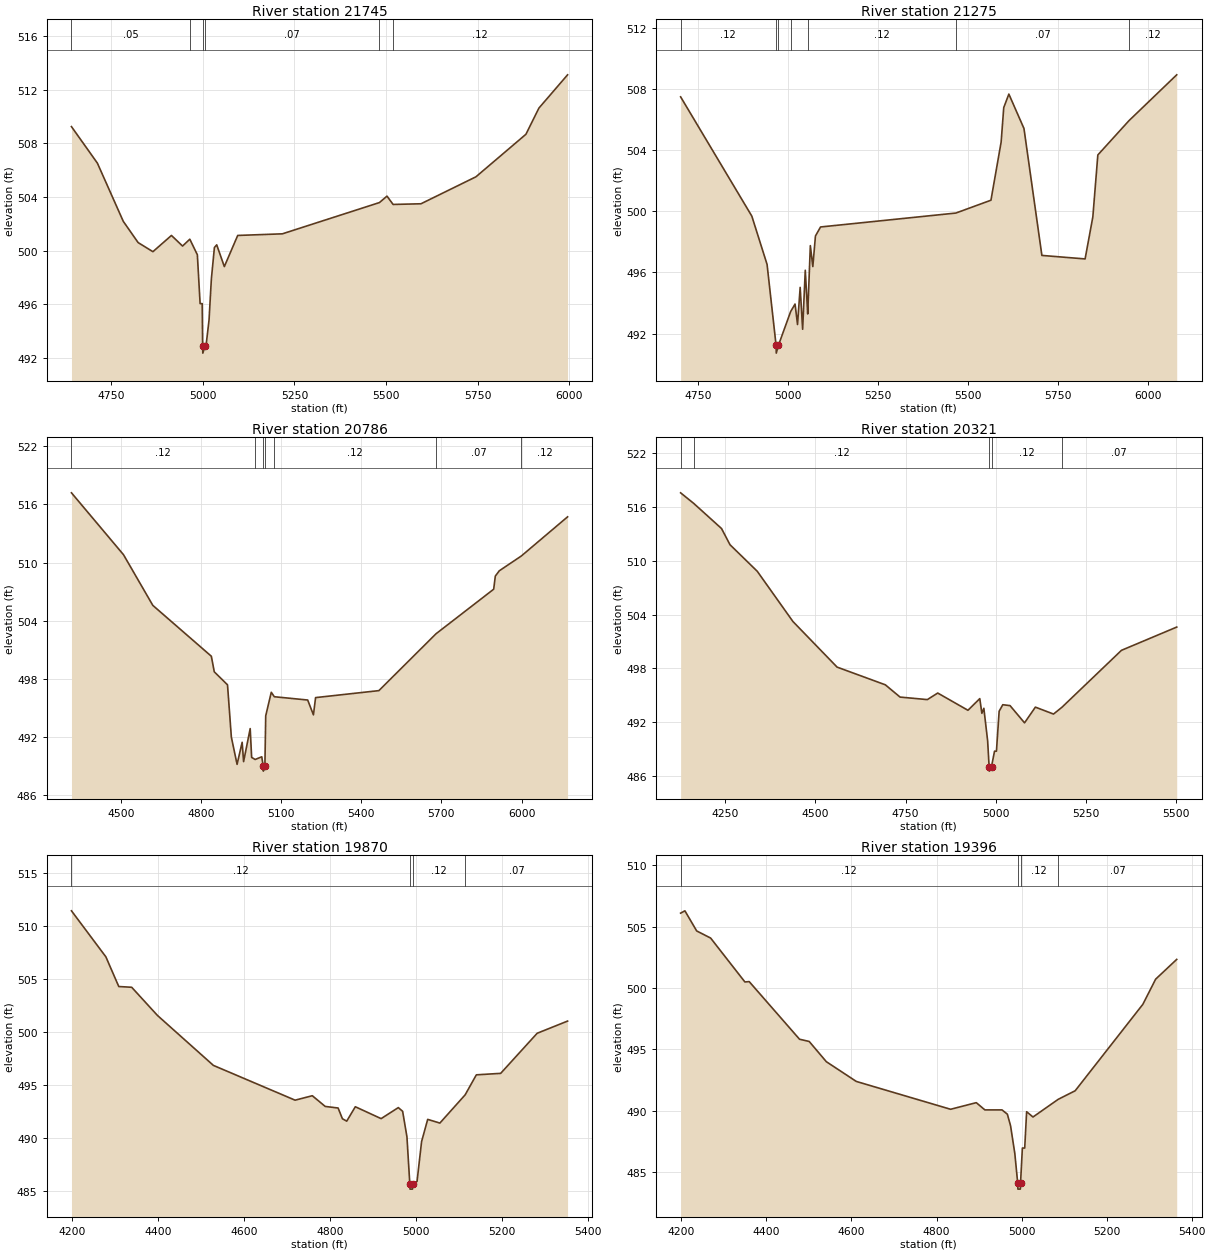
Type RM Length L Ch R = 1 ,21745   ,470,470,470
BEGIN DESCRIPTION:
CANTAU CREEK 39.0
END DESCRIPTION:
XS GIS Cut Line= 3
      2315924.99       13729675.        2316275.       13729725.
      2317075.03     13729124.98
#Sta/Elev= 30
  4641.7  509.24  4712.4  506.52  4783.1  502.18  4823.5   500.6  4863.9  499.92
  4914.5  501.13  4944.8  500.34  4964.6  500.85  4985.2  499.69  4992.7  496.05
  4998.4  496.05  4999.6  492.86  5000.1  492.36  5005.6  492.86  5008.8  492.89
  5017.1  494.84  5023.4  497.88  5031.7  500.23    5038  500.43  5058.8  498.81
  5095.3  501.13  5217.1  501.25    5482  503.58  5502.6  504.06  5519.3  503.44
  5595.3  503.49  5745.3   505.5  5881.7  508.67  5917.1  510.62  5995.3   513.1
#Mann= 6 ,-1 , 0
  4641.7     .05       0  4964.6     .07       0  4999.6     .05       0
  5005.6     .07       0    5482     .05       0  5519.3     .12       0
Bank Sta=4999.6,5005.6
XS Rating Curve= 0 ,0
Exp/Cntr=0.3,0.1

Type RM Length L Ch R = 1 ,21275   ,489,489,489
BEGIN DESCRIPTION:
CANTAU CREEK 38.0
END DESCRIPTION:
XS GIS Cut Line= 3
      2316075.01     13730374.99        2316275.       13730175.
      2317074.99     13729425.01
#Sta/Elev= 30
  4700.6  507.48  4898.6  499.68    4941  496.52  4966.1  491.22  4966.6  490.72
  4972.4  491.22  5006.6  493.44  5018.8  493.93  5025.7  492.59    5033  495.02
  5039.9  492.28  5047.2  496.14    5054  493.28  5055.4  494.14  5061.3  497.75
  5068.2  496.38  5075.5  498.38  5089.7  498.97  5465.9  499.88  5563.5  500.72
  5591.8  504.52  5599.1  506.78  5613.3  507.66  5655.3  505.41  5705.1  497.11
  5825.3  496.88  5846.8  499.63  5860.7  503.68  5947.2  505.92    6080  508.92
#Mann= 7 ,-1 , 0
  4700.6     .12       0  4966.1     .05       0  4972.4     .12       0
  5006.6     .07       0  5055.4     .12       0  5465.9     .07       0
  5947.2     .12       0
Bank Sta=4966.1,4972.4
XS Rating Curve= 0 ,0
Exp/Cntr=0.3,0.1

Type RM Length L Ch R = 1 ,20786   ,465,465,465
BEGIN DESCRIPTION:
CANTAU CREEK 37.0
END DESCRIPTION:
XS GIS Cut Line= 3
      2315935.87     13730718.61        2316575.       13730475.
       2317527.3      13729790.6
#Sta/Elev= 30
  4315.4   517.2  4510.2  510.81  4619.9  505.58  4838.9  500.33  4849.9  498.72
  4899.4  497.38  4913.8  491.98  4935.2  489.17  4954.2  491.45  4959.6  489.45
  4984.3  492.86  4989.7  489.89  5002.8  489.67  5027.6  489.95    5033  488.97
  5033.5  488.47  5039.3  488.97  5042.4  494.18  5063.2  496.61  5074.6  496.15
  5199.5  495.81    5221  494.28    5229  496.06  5465.9  496.78  5679.8  502.65
  5895.6  507.25  5901.7   508.6  5916.5  509.15  5999.1  510.68  6172.1  514.72
#Mann= 7 ,-1 , 0
  4315.4     .12       0  5002.8     .07       0    5033     .05       0
  5039.3     .07       0  5074.6     .12       0  5679.8     .07       0
  5999.1     .12       0
Bank Sta=5033,5039.3
XS Rating Curve= 0 ,0
Exp/Cntr=0.3,0.1

Type RM Length L Ch R = 1 ,20321   ,451,451,451
BEGIN DESCRIPTION:
CANTAU CREEK 36.0
END DESCRIPTION:
XS GIS Cut Line= 3
      2316074.96     13731075.02        2316875.       13730725.
      2317374.95       13730775.
#Sta/Elev= 30
  4126.3  517.57  4162.4   516.4  4239.8  513.59  4263.2  511.79  4338.8  508.83
  4437.8  503.23  4560.2  498.15  4693.9  496.18  4734.9  494.81  4810.5  494.53
  4839.3  495.26  4923.1  493.34  4955.9  494.64  4961.7     493  4967.2  493.56
  4977.7  489.93  4981.8  487.06  4982.3  486.56  4988.4  487.06  4996.8  488.78
  5002.1  488.78  5009.6  493.23  5019.7  493.96  5039.8  493.86    5080  491.94
  5110.1  493.69  5160.4  492.92  5183.6  493.67  5348.8  500.02    5502  502.61
#Mann= 5 ,-1 , 0
  4126.3     .07       0  4162.4     .12       0  4981.8     .05       0
  4988.4     .12       0  5183.6     .07       0
Bank Sta=4981.8,4988.4
XS Rating Curve= 0 ,0
Exp/Cntr=0.3,0.1

Type RM Length L Ch R = 1 ,19870   ,474,474,474
BEGIN DESCRIPTION:
CANTAU CREEK 35.0
END DESCRIPTION:
XS GIS Cut Line= 3
        2316225.       13731075.        2317025.       13731075.
      2317274.96     13730825.04
#Sta/Elev= 30
  4199.3  511.42  4279.3  507.08  4309.3  504.28  4339.3  504.21  4399.3  501.55
  4529.3  496.84  4719.3  493.56  4759.3  493.98  4789.3  492.97  4819.3  492.82
  4829.3  491.81  4839.3  491.58  4859.3  492.94  4919.3  491.82  4959.3  492.86
  4969.3  492.51  4979.3  490.11    4986  485.67  4986.5  485.17  4992.1  485.17
  4992.6  485.67  5002.8  485.89  5013.4  489.66  5027.6  491.75  5055.9   491.4
  5114.6  494.06  5140.7  495.95  5197.3  496.09  5282.1  499.87  5352.8  501.02
#Mann= 4 ,-1 , 0
  4199.3     .12       0    4986     .05       0  4992.6     .12       0
  5114.6     .07       0
Bank Sta=4986,4992.6
XS Rating Curve= 0 ,0
Exp/Cntr=0.3,0.1

Type RM Length L Ch R = 1 ,19396   ,468,468,468
BEGIN DESCRIPTION:
CANTAU CREEK 34.0
END DESCRIPTION:
XS GIS Cut Line= 3
      2316424.95     13731575.01        2317225.       13731475.
      2317524.98     13731275.02
#Sta/Elev= 30
  4198.1   506.1  4208.2  506.29  4235.9  504.65  4268.7  504.07  4349.3  500.49
  4359.4  500.52  4477.8  495.82  4500.5  495.64  4540.8  493.99  4611.3  492.38
  4833.1  490.11  4893.5  490.65  4913.7  490.06    4954  490.06  4966.6  489.71
  4974.1  488.77  4984.2  486.49  4990.9   484.1  4991.4   483.6  4997.1   483.6
  4997.6   484.1  5001.9  486.95  5007.4  486.95  5011.9  489.91  5026.9  489.48
  5086.1  490.92  5126.1  491.62  5285.3  498.67  5315.4  500.72  5364.9  502.33
#Mann= 4 ,-1 , 0
  4198.1     .12       0  4990.9     .05       0  4997.6     .12       0
  5086.1     .07       0
Bank Sta=4990.9,4997.6
XS Rating Curve= 0 ,0
Exp/Cntr=0.3,0.1

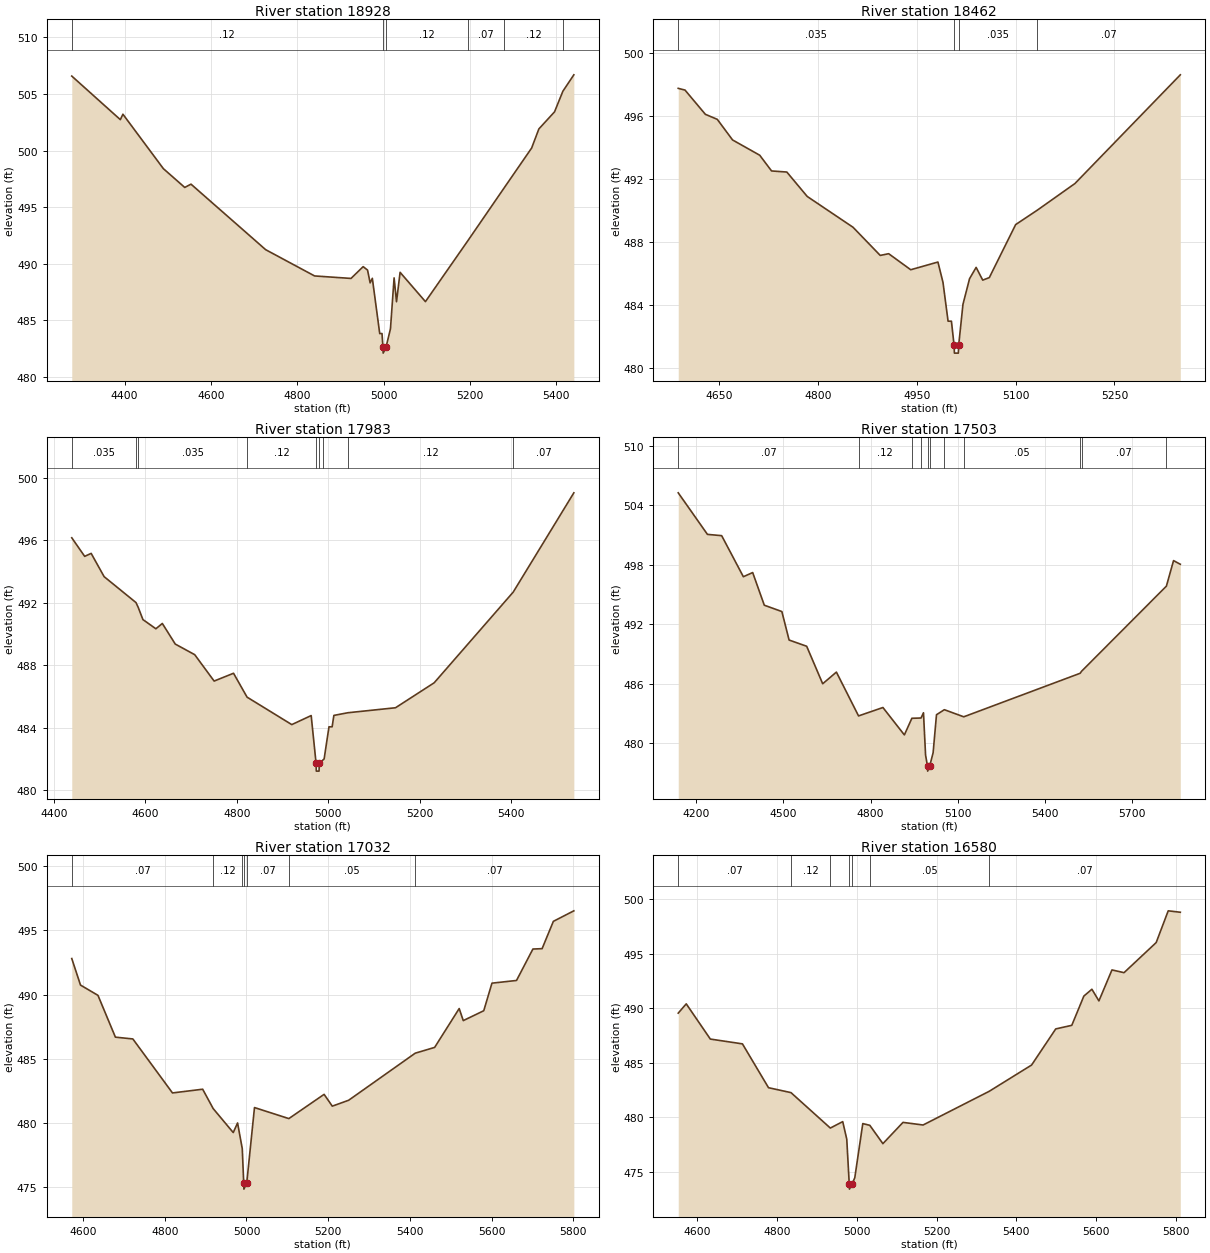
Type RM Length L Ch R = 1 ,18928   ,466,466,466
BEGIN DESCRIPTION:
CANTAU CREEK 33.0
END DESCRIPTION:
XS GIS Cut Line= 3
      2316424.97     13731724.99        2317125.       13731875.
      2317524.97     13732074.99
#Sta/Elev= 30
  4277.5  506.59    4390  502.74    4396  503.22  4489.7  498.41  4539.2  496.75
  4553.7  497.04  4726.7  491.25    4840  488.93  4924.4  488.71  4952.5  489.75
  4962.7  489.45  4968.7  488.32  4973.8  488.72  4990.9  483.84  4996.2  483.84
  4998.4  482.61  4998.9  482.11  5005.3  482.61  5015.8  484.26  5024.2  488.76
  5029.8  486.65  5038.1  489.25  5096.8  486.66  5194.3     492  5279.7  496.74
  5342.8  500.23  5359.6  501.92  5395.9  503.43  5415.2  505.25  5440.6   506.7
#Mann= 6 ,-1 , 0
  4277.5     .12       0  4998.4     .05       0  5005.3     .12       0
  5194.3     .07       0  5279.7     .12       0  5415.2     .07       0
Bank Sta=4998.4,5005.3
XS Rating Curve= 0 ,0
Exp/Cntr=0.3,0.1

Type RM Length L Ch R = 1 ,18462   ,479,479,479
BEGIN DESCRIPTION:
CANTAU CREEK 32.0
END DESCRIPTION:
XS GIS Cut Line= 3
        2316625.       13732175.        2317025.       13732275.
      2317374.99       13732275.
#Sta/Elev= 30
  4587.8  497.78  4598.1  497.67    4629  496.13  4647.1  495.81  4670.3   494.5
  4711.5  493.53  4729.5  492.53  4752.7  492.46  4783.6  490.91  4853.2  488.95
  4894.5  487.16  4907.3  487.27  4940.8  486.25  4982.1  486.74  4989.8  485.44
  4997.5  482.98  5002.6  482.98  5006.6  481.45  5007.1  480.95  5013.1  480.95
  5013.6  481.45  5020.1  484.05  5030.1  485.68  5040.1   486.4  5050.1  485.59
  5060.1  485.75  5100.1  489.12  5133.1  490.04  5190.1  491.73  5350.1  498.64
#Mann= 4 ,-1 , 0
  4587.8    .035       0  5006.6    .035       0  5013.6    .035       0
  5133.1     .07       0
Bank Sta=5006.6,5013.6
XS Rating Curve= 0 ,0
Exp/Cntr=0.3,0.1

Type RM Length L Ch R = 1 ,17983   ,480,480,480
BEGIN DESCRIPTION:
CANTAU CREEK 31.0
END DESCRIPTION:
XS GIS Cut Line= 3
      2316625.03     13732325.03        2317025.       13732725.
      2317425.04     13732374.97
#Sta/Elev= 30
  4439.4  496.17  4467.6  494.98  4481.8  495.17  4510.1  493.68  4579.7  492.02
  4584.5  491.72  4594.9  490.93  4623.2  490.34  4637.3  490.68  4665.6  489.36
  4708.1  488.68  4750.5  486.99  4792.9  487.49  4822.5  485.96  4920.2   484.2
  4962.6  484.78  4973.3  481.72  4973.8  481.22  4979.8  481.22  4980.3  481.72
  4987.8  481.92  4990.9     482  5001.5  484.06  5008.4  484.06  5012.2  484.79
  5042.7  484.96  5146.9  485.28  5231.4  486.88  5404.1  492.69  5536.6  499.05
#Mann= 9 ,-1 , 0
  4439.4    .035       0  4579.7     .07       0  4584.5    .035       0
  4822.5     .12       0  4973.3     .05       0  4980.3     .12       0
  4987.8      .1       0  5042.7     .12       0  5404.1     .07       0
Bank Sta=4973.3,4980.3
XS Rating Curve= 0 ,0
Exp/Cntr=0.3,0.1

Type RM Length L Ch R = 1 ,17503   ,471,471,471
BEGIN DESCRIPTION:
CANTAU CREEK 30.0
END DESCRIPTION:
XS GIS Cut Line= 3
      2316124.97     13733475.01        2316925.       13733175.
      2317675.02     13732724.99
#Sta/Elev= 30
  4137.5  505.28  4238.1  501.08  4287.1  500.95  4361.8   496.8  4393.9  497.22
  4433.9  493.92  4494.4  493.28  4519.3   490.4  4579.9  489.77    4635  485.98
  4682.2  487.16  4758.5  482.73  4842.4  483.58  4916.3  480.81  4942.1  482.49
  4973.7  482.52  4982.1  483.05  4989.3  478.77    4996  477.65  4996.5  477.15
  5003.4  477.65  5015.3  479.01  5026.9  482.85    5054  483.36  5120.8  482.64
  5521.6  487.04  5526.4  487.24  5818.7  495.85  5843.3  498.43  5866.6  498.06
#Mann= 11 ,-1 , 0
  4137.5     .07       0  4758.5     .12       0  4942.1      .1       0
  4973.7     .12       0    4996     .05       0  5003.4     .12       0
    5054      .1       0  5120.8     .05       0  5521.6     .12       0
  5526.4     .07       0  5818.7     .12       0
Bank Sta=4996,5003.4
XS Rating Curve= 0 ,0
Exp/Cntr=0.3,0.1

Type RM Length L Ch R = 1 ,17032   ,452,452,452
BEGIN DESCRIPTION:
CANTAU CREEK 29.0
END DESCRIPTION:
XS GIS Cut Line= 3
        2316475.       13733475.        2316875.       13733625.
      2317675.04       13733675.
#Sta/Elev= 30
  4572.4  492.81  4593.8  490.74  4636.5  489.94  4679.2  486.68  4721.9  486.54
  4818.9  482.33  4892.8  482.62  4918.5  481.11  4967.6  479.24  4978.2  479.99
  4989.7  477.98  4993.2  475.33  4993.7  474.83  5000.7  475.33  5019.6  481.19
  5103.7  480.33    5190  482.22    5210   481.3  5250.1  481.76    5413  485.43
  5460.5  485.88  5520.6  488.91  5530.6  487.97  5580.7  488.74  5600.8  490.89
  5660.9   491.1    5701  493.55  5723.5  493.58  5751.1  495.71  5801.2  496.53
#Mann= 7 ,-1 , 0
  4572.4     .07       0  4918.5     .12       0  4989.7     .07       0
  4993.2     .05       0  5000.7     .07       0  5103.7     .05       0
    5413     .07       0
Bank Sta=4993.2,5000.7
XS Rating Curve= 0 ,0
Exp/Cntr=0.3,0.1

Type RM Length L Ch R = 1 ,16580   ,435,435,435
BEGIN DESCRIPTION:
CANTAU CREEK 28.0
END DESCRIPTION:
XS GIS Cut Line= 3
      2316475.03       13733975.        2316925.       13734025.
      2317725.03       13733925.
#Sta/Elev= 30
  4552.3  489.57  4572.4  490.42  4632.8  487.19  4713.3  486.75  4778.7  482.73
    4835  482.28  4933.7  479.03  4964.8  479.62  4974.9  478.01  4981.1  473.93
  4981.6  473.43  4988.7  473.93    4995  474.47  5015.1  479.44  5032.7  479.28
  5065.5   477.6  5115.9  479.55  5166.3  479.31  5332.1   482.4  5438.4  484.81
  5498.9  488.12  5539.2  488.45  5569.4  491.13  5589.6  491.76  5607.2  490.69
  5639.9  493.53  5670.2  493.28  5750.8  496.04    5781  498.95  5811.3  498.82
#Mann= 7 ,-1 , 0
  4552.3     .07       0    4835     .12       0  4933.7     .07       0
  4981.1     .05       0  4988.7     .07       0  5032.7     .05       0
  5332.1     .07       0
Bank Sta=4981.1,4988.7
XS Rating Curve= 0 ,0
Exp/Cntr=0.3,0.1

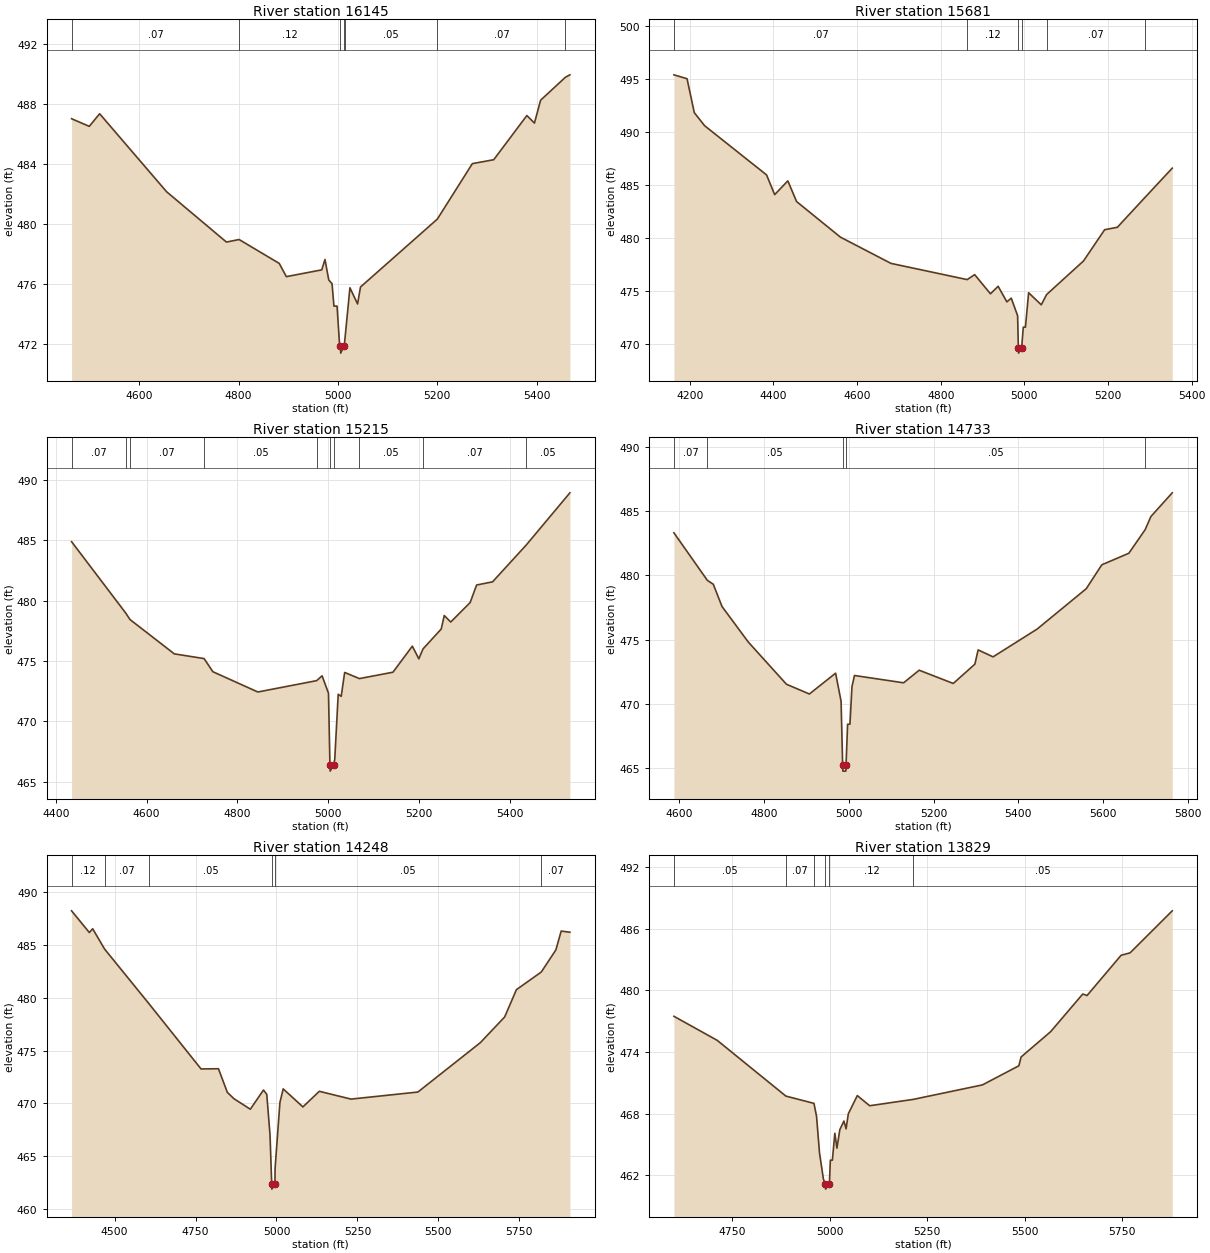
Type RM Length L Ch R = 1 ,16145   ,464,464,464
BEGIN DESCRIPTION:
CANTAU CREEK 27.0
END DESCRIPTION:
XS GIS Cut Line= 3
      2316524.97     13734074.97        2316925.       13734425.
      2317325.04     13734675.03
#Sta/Elev= 30
  4463.8  487.01  4499.4   486.5  4520.3  487.34  4655.1  482.15  4775.6   478.8
  4801.1  478.97  4881.9  477.38  4896.2   476.5  4967.4  476.95    4974  477.64
  4981.6  476.28  4988.2  476.03    4992  474.54  4998.3  474.54    5003  472.15
  5005.1  471.91  5005.6  471.41  5012.7  471.91  5013.4   472.1  5024.2  475.76
  5039.6  474.68  5045.5  475.81  5200.2  480.33  5270.7  484.02  5313.7  484.28
  5380.4  487.22  5395.7  486.72  5408.1  488.24  5458.1  489.77  5467.1  489.93
#Mann= 7 ,-1 , 0
  4463.8     .07       0  4801.1     .12       0  5005.1     .05       0
  5012.7     .12       0  5013.4     .05       0  5200.2     .07       0
  5458.1     .05       0
Bank Sta=5005.1,5012.7
XS Rating Curve= 0 ,0
Exp/Cntr=0.3,0.1

Type RM Length L Ch R = 1 ,15681   ,466,466,466
BEGIN DESCRIPTION:
CANTAU CREEK 26.0
END DESCRIPTION:
XS GIS Cut Line= 3
      2316075.03     13734625.01        2316875.       13734875.
      2317225.03       13734825.
#Sta/Elev= 30
  4161.9  495.43  4193.3  495.06  4210.6  491.86  4235.2  490.63  4383.5  485.98
  4402.8  484.12  4434.3  485.42  4455.2  483.47    4560  480.11    4681  477.63
  4863.2   476.1  4881.1  476.57  4918.8  474.76  4937.2  475.47  4958.1     474
  4968.6  474.35  4983.8  472.69  4985.6  469.66  4986.1  469.16  4993.4  469.66
  4997.4  471.61  5002.5  471.61  5010.1  474.86  5040.4  473.72  5053.1  474.69
  5141.4  477.86  5191.9  480.81  5222.3  481.04  5288.7  483.87  5353.6  486.62
#Mann= 6 ,-1 , 0
  4161.9     .07       0  4863.2     .12       0  4985.6     .05       0
  4993.4     .12       0  5053.1     .07       0  5288.7     .05       0
Bank Sta=4985.6,4993.4
XS Rating Curve= 0 ,0
Exp/Cntr=0.3,0.1

Type RM Length L Ch R = 1 ,15215   ,482,482,482
BEGIN DESCRIPTION:
CANTAU CREEK 25.0
END DESCRIPTION:
XS GIS Cut Line= 3
      2316525.03     13735724.97        2316925.       13735325.
      2317324.96     13734975.03
#Sta/Elev= 30
  4434.9  484.88  4554.2  478.96  4563.4  478.43  4661.1  475.58  4726.6  475.19
    4746   474.1    4845  472.42  4974.4  473.36  4986.4  473.76  5000.5  472.32
  5003.7  466.36  5004.2  465.86  5011.7  466.36  5014.3  466.85  5021.9  472.23
  5028.5  472.06  5036.1  474.04  5068.6  473.53  5142.4  474.06  5185.1  476.22
  5199.4  475.17  5208.6  475.99  5248.7  477.64  5255.4  478.76  5269.6  478.22
  5312.3  479.83  5326.6  481.29  5361.7  481.55    5436  484.61    5532  488.93
#Mann= 10 ,-1 , 0
  4434.9     .07       0  4554.2     .12       0  4563.4     .07       0
  4726.6     .05       0  4974.4     .07       0  5003.7     .05       0
  5011.7     .07       0  5068.6     .05       0  5208.6     .07       0
    5436     .05       0
Bank Sta=5003.7,5011.7
XS Rating Curve= 0 ,0
Exp/Cntr=0.3,0.1

Type RM Length L Ch R = 1 ,14733   ,485,485,485
BEGIN DESCRIPTION:
CANTAU CREEK 24.0
END DESCRIPTION:
XS GIS Cut Line= 3
      2316625.01       13735875.        2317025.       13735775.
      2317424.99     13735125.01
#Sta/Elev= 30
  4587.7  483.32  4666.6  479.62  4680.5  479.32  4701.1  477.59  4762.9  474.83
  4853.1  471.54  4907.2  470.78  4969.1   472.4    4982  470.21  4985.7  465.28
  4986.2  464.78  4993.2  464.78  4993.7  465.28  4997.4  468.43  5002.9  468.43
  5007.7  471.35  5013.6  472.22  5129.5  471.65  5166.2  472.63  5246.6   471.6
  5297.6   473.1  5305.3  474.21  5340.5  473.67  5444.4  475.83  5560.3  478.97
    5597  480.83  5660.8  481.73  5699.2  483.56  5712.9  484.59  5763.2  486.43
#Mann= 5 ,-1 , 0
  4587.7     .07       0  4666.6     .05       0  4985.7     .05       0
  4993.7     .05       0  5699.2     .07       0
Bank Sta=4985.7,4993.7
XS Rating Curve= 0 ,0
Exp/Cntr=0.3,0.1

Type RM Length L Ch R = 1 ,14248   ,419,419,419
BEGIN DESCRIPTION:
X18407
END DESCRIPTION:
XS GIS Cut Line= 2
      2316550.85     13736316.56      2318067.78     13736055.67
#Sta/Elev= 30
  4367.1  488.25    4422  486.19  4432.2  486.55  4469.2  484.62  4607.4  479.39
    4767  473.25  4820.8  473.27  4848.2  471.03  4868.5  470.43  4919.2  469.43
  4959.8  471.25    4970  470.84  4980.1  466.96  4985.2  462.35  4985.7  461.85
  4995.3  462.35  4995.6  463.79  5010.6  470.07  5020.7  471.36  5081.6  469.65
  5132.3  471.13  5230.2  470.39  5436.7  471.06  5629.5  475.74  5704.7  478.18
  5741.1  480.77    5818  482.45  5862.9  484.54  5879.4  486.33  5906.3  486.22
#Mann= 6 ,-1 , 0
  4367.1     .12       0  4469.2     .07       0  4607.4     .05       0
  4985.2     .05       0  4995.3     .05       0    5818     .07       0
Bank Sta=4985.2,4995.3
XS Rating Curve= 0 ,0
Exp/Cntr=0.3,0.1

Type RM Length L Ch R = 1 ,13829   ,463,463,463
BEGIN DESCRIPTION:
CANTAU CREEK 23.0
END DESCRIPTION:
XS GIS Cut Line= 3
      2316925.03       13736625.        2317325.       13736575.
        2318125.       13736925.
#Sta/Elev= 30
  4601.4  477.48  4712.2  475.14  4888.1  469.71  4960.1     469  4966.7  467.73
  4974.3  464.16  4984.3  461.62  4989.3  461.15  4989.8  460.65  4999.6  461.15
    5002  463.47  5007.2  463.47  5013.5  466.09  5018.9  464.64  5026.3  466.44
  5036.8  467.28  5042.3  466.52  5048.1  467.99  5071.1  469.76  5102.7  468.77
  5214.6  469.39  5391.6   470.8  5484.8  472.66  5490.6  473.52  5566.2  475.98
  5648.5  479.65  5659.4   479.5  5746.7  483.42  5769.7  483.66  5877.7  487.75
#Mann= 6 ,-1 , 0
  4601.4     .05       0  4888.1     .07       0  4960.1     .12       0
  4989.3     .05       0  4999.6     .12       0  5214.6     .05       0
Bank Sta=4989.3,4999.6
XS Rating Curve= 0 ,0
Exp/Cntr=0.3,0.1