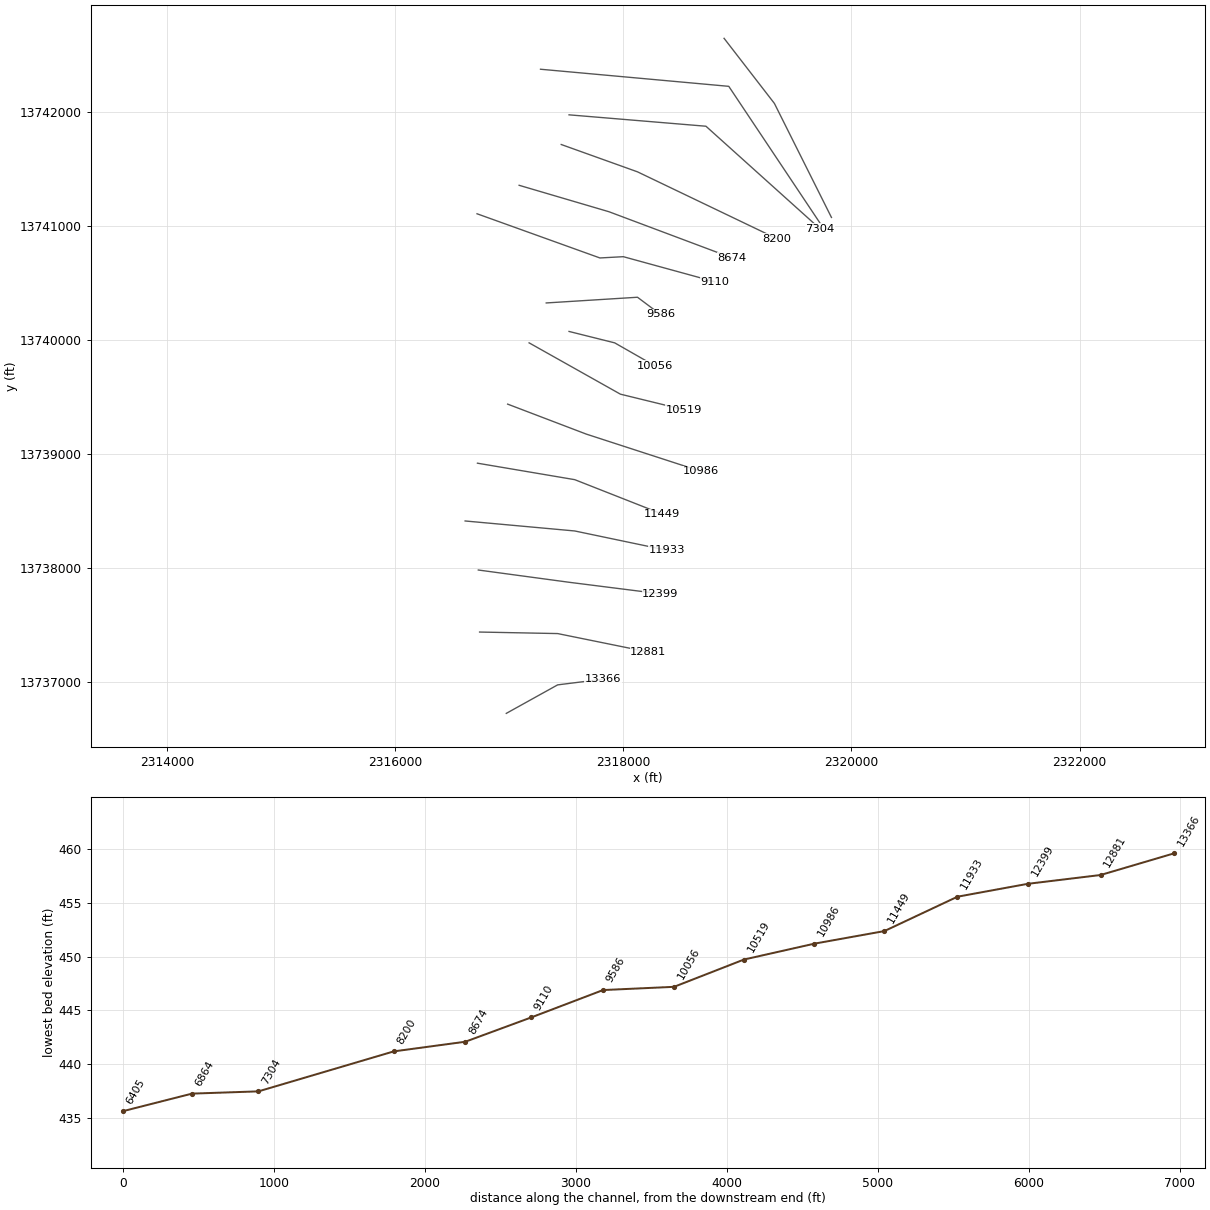
HEC-RAS study CANTAU CREEK.prj: CANTAU CREEK Base Level Engineering

--- CANTAU CREEK.g01 (geometry) --- (continued)

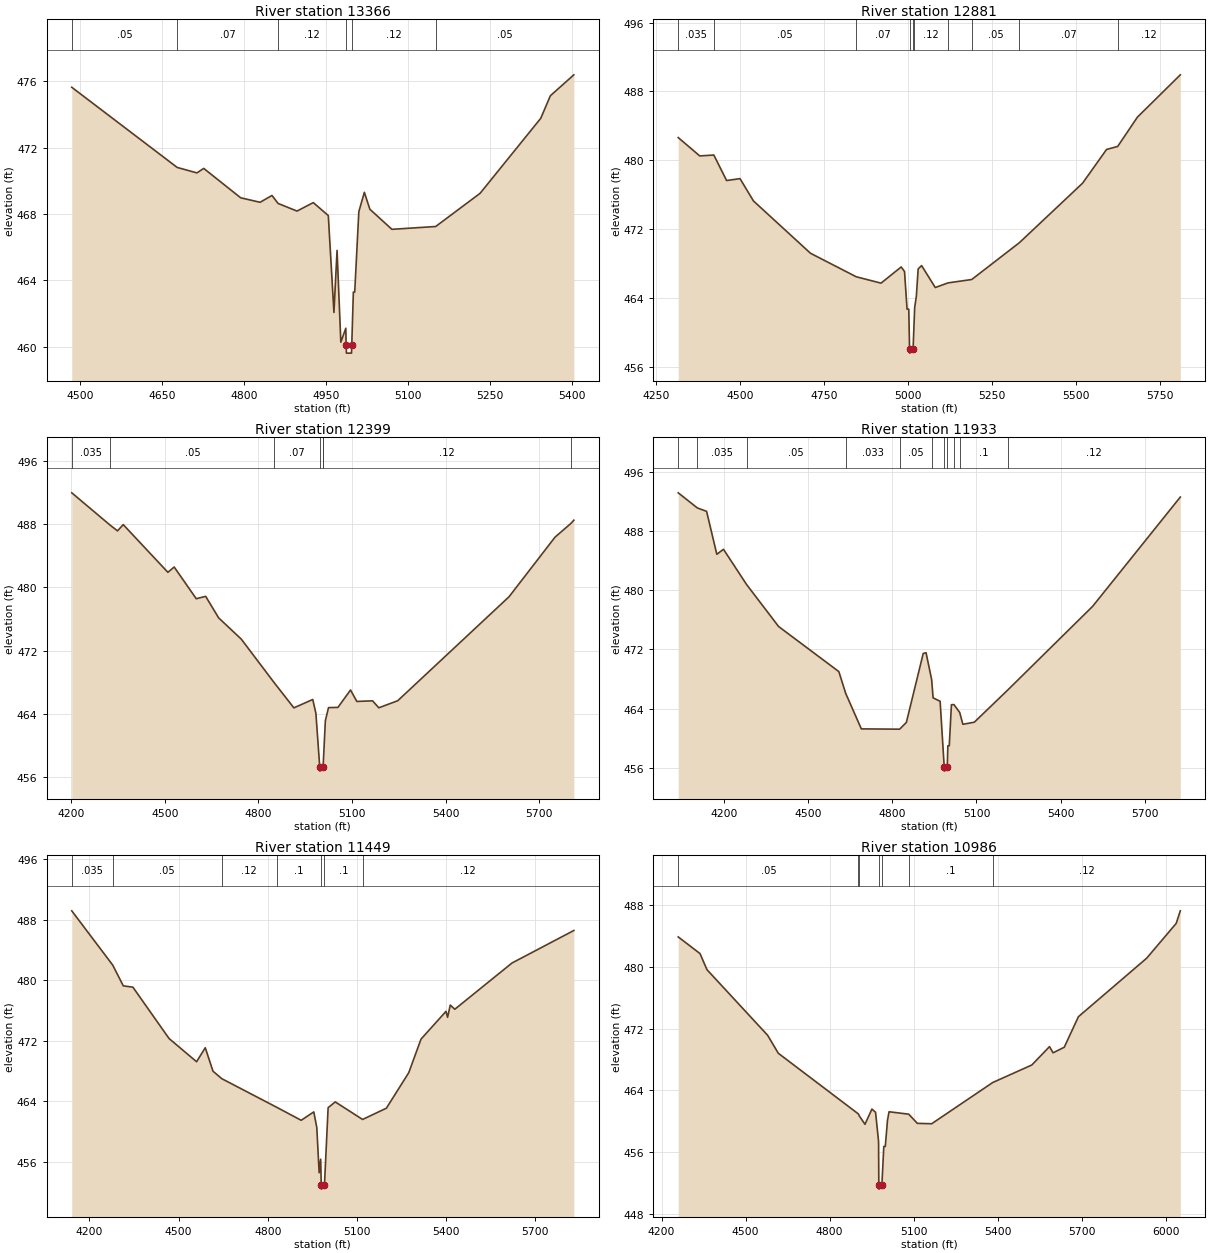
Type RM Length L Ch R = 1 ,13366   ,485,485,485
BEGIN DESCRIPTION:
CANTAU CREEK 22.0
END DESCRIPTION:
XS GIS Cut Line= 3
      2316975.02     13736725.01        2317425.       13736975.
      2317825.03       13737025.
#Sta/Elev= 30
  4485.2  475.63  4677.9   470.8    4714  470.47  4726.5  470.74    4794  468.97
  4829.5   468.7  4851.2  469.11  4862.4  468.63    4897  468.17  4926.7  468.68
  4954.2   467.9  4964.5  462.06  4970.2   465.8  4977.1  460.27  4986.2  461.11
  4986.8  460.11  4987.3  459.61  4996.6  459.61  4997.1  460.11    5000  463.29
  5002.5  463.29    5010  468.13  5020.1   469.3  5030.2  468.28  5070.5  467.07
  5150.5  467.24  5231.7  469.24  5342.6  473.76  5360.2  475.12  5403.1  476.38
#Mann= 6 ,-1 , 0
  4485.2     .05       0  4677.9     .07       0  4862.4     .12       0
  4986.8     .05       0  4997.1     .12       0  5150.5     .05       0
Bank Sta=4986.8,4997.1
XS Rating Curve= 0 ,0
Exp/Cntr=0.3,0.1

Type RM Length L Ch R = 1 ,12881   ,482,482,482
BEGIN DESCRIPTION:
CANTAU CREEK 21.0
END DESCRIPTION:
XS GIS Cut Line= 3
      2316740.93     13737438.39        2317425.       13737425.
      2318220.32     13737263.27
#Sta/Elev= 30
  4315.8  482.64  4379.9  480.51  4421.9  480.61  4459.9  477.65  4499.9  477.87
  4539.9  475.28  4709.9   469.2  4846.1  466.47    4920  465.73    4980  467.61
    4990  467.08  4997.5  462.71  5002.6  462.71    5005   458.1  5005.5   457.6
  5015.5   458.1  5018.5  461.15  5020.2  462.88  5025.3  464.25  5030.6  467.38
  5040.8  467.77  5081.6  465.22  5119.6  465.76  5190.1  466.15  5332.2  470.43
  5520.4  477.34  5591.9  481.26    5625  481.61  5683.7  485.01  5811.6  489.93
#Mann= 10 ,-1 , 0
  4315.8    .035       0  4421.9     .05       0  4846.1     .07       0
    5005     .05       0  5015.5     .07       0  5018.5     .12       0
  5119.6     .07       0  5190.1     .05       0  5332.2     .07       0
    5625     .12       0
Bank Sta=5005,5015.5
XS Rating Curve= 0 ,0
Exp/Cntr=0.3,0.1

Type RM Length L Ch R = 1 ,12399   ,466,466,466
BEGIN DESCRIPTION:
CANTAU CREEK 20.0
END DESCRIPTION:
XS GIS Cut Line= 3
      2316729.74     13737982.53        2317525.       13737875.
      2318324.93     13737773.82
#Sta/Elev= 30
  4201.9  491.97  4325.9  487.85  4348.5  487.16  4366.8  487.95  4509.9  481.92
  4530.1  482.59  4600.8  478.58    4631  478.88  4672.5  476.16  4745.1  473.47
  4850.8  467.95  4913.6  464.78  4974.1  465.84  4984.2  464.08  4996.5  457.28
    4997  456.78  5007.2  457.28  5007.7  457.68  5014.5  463.16  5024.6  464.81
  5054.8  464.84  5095.1  467.04  5115.3  465.59  5165.7  465.67  5185.8  464.79
  5246.3  465.68  5603.1  478.83  5750.3  486.36  5800.7  488.08  5810.7  488.51
#Mann= 7 ,-1 , 0
  4201.9    .035       0  4325.9     .05       0  4850.8     .07       0
  4996.5     .05       0  5007.2     .07       0  5007.7     .12       0
  5800.7     .07       0
Bank Sta=4996.5,5007.2
XS Rating Curve= 0 ,0
Exp/Cntr=0.3,0.1

Type RM Length L Ch R = 1 ,11933   ,484,484,484
BEGIN DESCRIPTION:
CANTAU CREEK 19.0
END DESCRIPTION:
XS GIS Cut Line= 3
       2316614.2     13738412.63        2317575.       13738325.
      2318384.55     13738155.46
#Sta/Elev= 30
  4035.6  493.13  4103.9  491.09  4136.8  490.63  4173.3  484.84  4197.1  485.51
  4279.5  480.76  4393.9  475.09  4608.8  469.01  4633.4  466.06  4689.1  461.28
  4825.7  461.24  4849.8  462.15    4910  471.46  4920.1  471.55    4940  467.94
  4945.2  465.47  4970.3     465    4985  456.08  4985.5  455.58  4995.7  456.08
  4997.9     459  5002.9     459  5010.6  464.54  5019.5  464.56    5040  463.51
  5051.5   461.9  5092.3  462.18  5212.6  466.56  5514.5  477.81  5827.5  492.56
#Mann= 11 ,-1 , 0
  4035.6     .07       0  4103.9    .035       0  4279.5     .05       0
  4633.4    .033       0  4825.7     .05       0    4940     .12       0
    4985     .05       0  4995.7     .12       0  5019.5     .07       0
    5040      .1       0  5212.6     .12       0
Bank Sta=4985,4995.7
XS Rating Curve= 0 ,0
Exp/Cntr=0.3,0.1

Type RM Length L Ch R = 1 ,11449   ,463,463,463
BEGIN DESCRIPTION:
CANTAU CREEK 18.0
END DESCRIPTION:
XS GIS Cut Line= 3
      2316722.25     13738919.51        2317575.       13738775.
      2318341.75     13738472.96
#Sta/Elev= 30
  4140.4  489.17  4278.1     482  4313.8  479.25    4346  479.08  4467.7  472.29
  4560.3  469.22  4589.5  471.07  4615.5  467.97  4644.7  466.99  4830.3  463.19
  4912.2  461.48  4954.6  462.59  4964.7  460.52  4972.6  454.55  4977.7  456.34
  4979.7  452.88  4980.2  452.38  4990.4  452.88  5002.8  463.15  5026.8  463.91
  5118.7  461.59  5198.8  463.08    5274  467.77  5315.3  472.21  5399.3  475.88
  5404.6  475.09  5413.7  476.71    5429  476.16  5621.3  482.27  5829.4  486.57
#Mann= 7 ,-1 , 0
  4140.4    .035       0  4278.1     .05       0  4644.7     .12       0
  4830.3      .1       0  4979.7     .05       0  4990.4      .1       0
  5118.7     .12       0
Bank Sta=4979.7,4990.4
XS Rating Curve= 0 ,0
Exp/Cntr=0.3,0.1

Type RM Length L Ch R = 1 ,10986   ,467,467,467
BEGIN DESCRIPTION:
CANTAU CREEK 17.0
END DESCRIPTION:
XS GIS Cut Line= 3
      2316986.89     13739437.56        2317675.       13739175.
        2318679.     13738848.68
#Sta/Elev= 30
  4259.4  483.88  4337.2  481.72  4361.9  479.64  4578.5  471.14  4616.6  468.81
  4902.5  460.95    4906  460.68    4926  459.61  4950.8  461.58  4963.8  461.16
  4974.5   457.4  4975.4  451.71  4975.9  451.21  4986.3  451.71  4993.2  456.74
  4998.5  456.74  5006.4  460.13  5011.9  461.23    5082  460.92    5113  459.73
  5164.1  459.68    5382  465.02  5521.6  467.29  5584.7  469.67  5597.5  468.87
  5637.3  469.59    5688  473.55  5931.7  481.13  6036.9  485.63  6051.6  487.26
#Mann= 7 ,-1 , 0
  4259.4     .05       0  4902.5     .07       0    4906     .12       0
  4975.4     .05       0  4986.3     .12       0    5082      .1       0
    5382     .12       0
Bank Sta=4975.4,4986.3
XS Rating Curve= 0 ,0
Exp/Cntr=0.3,0.1

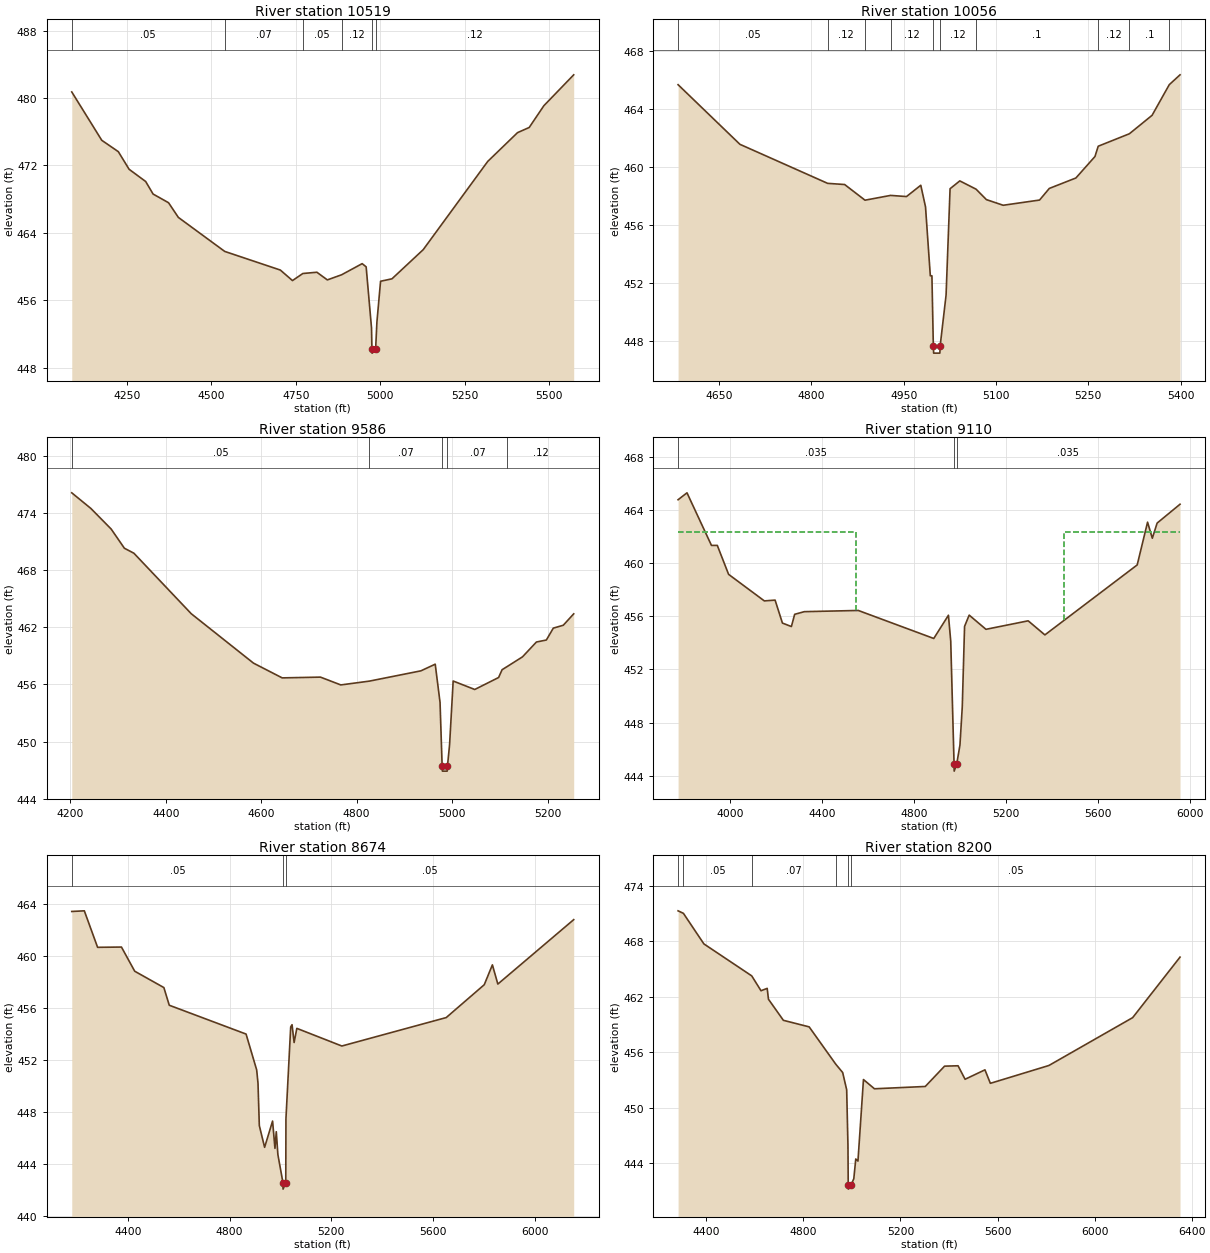
Type RM Length L Ch R = 1 ,10519   ,463,463,463
BEGIN DESCRIPTION:
CANTAU CREEK 16.0
END DESCRIPTION:
XS GIS Cut Line= 3
      2317174.99       13739975.        2317975.       13739525.
      2318528.07     13739389.55
#Sta/Elev= 30
    4086  480.73  4174.9  474.99    4224  473.64  4255.9  471.55    4305   470.1
    4327  468.61  4372.8  467.58  4401.8  465.84  4539.3   461.8    4704  459.59
    4740  458.34  4770.7  459.18  4812.3  459.33  4843.3  458.42  4885.6  459.03
  4946.5  460.35  4958.3  459.97  4974.2  452.71  4975.4  450.23  4975.9  449.73
  4986.4  450.23  4990.2  453.43    5001  458.26  5034.8  458.55  5127.4  462.01
  5318.5  472.48  5406.9   475.9  5441.4  476.51    5485   479.1  5573.3  482.76
#Mann= 6 ,-1 , 0
    4086     .05       0  4539.3     .07       0  4770.7     .05       0
  4885.6     .12       0  4975.4     .05       0  4986.4     .12       0
Bank Sta=4975.4,4986.4
XS Rating Curve= 0 ,0
Exp/Cntr=0.3,0.1

Type RM Length L Ch R = 1 ,10056   ,470,470,470
BEGIN DESCRIPTION:
CANTAU CREEK 15.0
END DESCRIPTION:
XS GIS Cut Line= 3
      2317524.96     13740075.01        2317925.       13739975.
      2318275.03     13739774.98
#Sta/Elev= 30
  4583.5  465.69    4684  461.58  4826.5  458.89  4854.1  458.81  4887.2  457.73
  4928.7  458.06  4954.6  457.98  4977.8  458.76  4985.5  457.27  4993.3  452.52
  4995.9  452.52  4998.2  447.69  4998.7  447.19  5008.8  447.19  5009.3  447.69
  5018.9  451.19  5025.4  458.52  5041.2  459.06  5067.6  458.49  5084.4  457.77
  5111.7  457.38  5170.8  457.74  5186.6  458.54  5229.8  459.26  5260.8  460.74
  5266.1  461.45  5316.8  462.31  5353.6  463.58  5381.5  465.69    5399  466.37
#Mann= 10 ,-1 , 0
  4583.5     .05       0  4826.5     .12       0  4887.2     .05       0
  4928.7     .12       0  4998.2     .05       0  5009.3     .12       0
  5067.6      .1       0  5266.1     .12       0  5316.8      .1       0
  5381.5     .07       0
Bank Sta=4998.2,5009.3
XS Rating Curve= 0 ,0
Exp/Cntr=0.3,0.1

Type RM Length L Ch R = 1 ,9586    ,476,476,476
BEGIN DESCRIPTION:
CANTAU CREEK 14.0
END DESCRIPTION:
XS GIS Cut Line= 3
      2317325.04       13740325.        2318125.       13740375.
      2318324.99     13740225.01
#Sta/Elev= 30
  4203.2  476.14  4243.2   474.5  4285.8  472.33  4313.4  470.32  4333.4  469.79
  4453.6  463.43  4583.9  458.24    4644  456.69  4724.2  456.77  4766.8  455.95
  4826.7  456.35  4934.6  457.43  4964.6  458.13  4974.7  454.11  4979.1  447.39
  4979.6  446.89  4989.7  446.89  4990.2  447.39  4994.7  449.68  5002.2  456.36
  5047.4  455.47  5097.4  456.73  5104.7  457.55  5115.9   457.9  5147.4   458.9
  5176.6  460.46  5197.4  460.67    5212  461.92  5232.8  462.22  5254.7  463.42
#Mann= 5 ,-1 , 0
  4203.2     .05       0  4826.7     .07       0  4979.1     .05       0
  4990.2     .07       0  5115.9     .12       0
Bank Sta=4979.1,4990.2
XS Rating Curve= 0 ,0
Exp/Cntr=0.3,0.1

Type RM Length L Ch R = 1 ,9110    ,436,436,436
BEGIN DESCRIPTION:
X18408
END DESCRIPTION:
XS GIS Cut Line= 4
       2316718.6     13741107.24      2317795.66     13740719.64
      2318000.65     13740730.83      2318800.99      13740511.2
#Sta/Elev= 30
  3775.5  464.78  3814.2   465.3  3920.5  461.34  3945.8  461.34  3994.9  459.16
  4150.1  457.16  4196.8  457.22  4228.7  455.49  4267.6  455.23  4281.8  456.15
  4323.7  456.35  4558.1  456.44  4885.9  454.33  4949.6  456.08  4959.6  454.13
  4974.1  444.84  4974.6  444.34  4985.2  444.84  4999.6   446.3  5009.7  449.18
  5019.7  455.24  5039.7  456.09  5112.6  455.02  5295.9  455.66  5368.5   454.6
  5769.4  459.87  5814.4  463.09  5835.1  461.88  5855.9  463.02  5955.4  464.44
#Mann= 3 ,-1 , 0
  3775.5    .035       0  4974.1    .035       0  4985.2    .035       0
#XS Ineff= 2 , 0
       0    4549  462.35    5451       0  462.35
Permanent Ineff=
       F       F
Bank Sta=4974.1,4985.2
XS Rating Curve= 0 ,0
Exp/Cntr=0.3,0.1

Type RM Length L Ch R = 1 ,8674    ,474,474,474
BEGIN DESCRIPTION:
CANTAU CREEK 13.0
END DESCRIPTION:
XS GIS Cut Line= 3
      2317087.58     13741356.95        2317875.       13741125.
      2318954.28     13740719.83
#Sta/Elev= 30
  4179.2  463.46  4228.6  463.51  4280.8   460.7  4374.6  460.72  4426.7  458.86
  4541.4   457.6  4562.6  456.24  4864.6  454.02  4906.3  451.26  4911.5  450.24
  4916.7  446.97  4937.5   445.3  4968.8  447.32  4978.2  445.22  4983.4   446.5
  4989.7  444.74  5009.6  442.58  5010.1  442.08  5020.7  442.58  5021.4   447.5
  5040.1  454.57  5045.4  454.74  5053.5  453.37  5064.2  454.46  5241.2   453.1
  5651.6  455.29  5801.2  457.82  5833.2  459.35  5854.6  457.87  6152.9  462.83
#Mann= 3 ,-1 , 0
  4179.2     .05       0  5009.6     .05       0  5020.7     .05       0
Bank Sta=5009.6,5020.7
XS Rating Curve= 0 ,0
Exp/Cntr=0.3,0.1

Type RM Length L Ch R = 1 ,8200    ,896,896,896
BEGIN DESCRIPTION:
CANTAU CREEK 12.0
END DESCRIPTION:
XS GIS Cut Line= 3
      2317456.55     13741714.74        2318125.       13741475.
      2319349.79     13740887.38
#Sta/Elev= 30
  4283.6   471.3  4305.5  471.03    4390  467.72  4587.1  464.26  4625.4  462.65
  4650.8  462.91  4656.1  461.73  4717.6  459.45  4823.8  458.74  4933.5   454.7
  4961.9   453.8  4978.4  451.93  4983.7  445.89  4984.8  441.68  4985.3  441.18
  4997.4  441.68  5007.8  442.31  5015.9  444.44  5024.9  444.22  5047.6  453.04
  5092.9  452.04  5302.3  452.29  5381.9  454.49  5437.4  454.53  5466.4  453.07
  5548.3  454.09  5570.5  452.63  5811.7  454.56    6157  459.74  6352.2  466.29
#Mann= 6 ,-1 , 0
  4283.6     .07       0  4305.5     .05       0  4587.1     .07       0
  4933.5     .05       0  4984.8     .05       0  4997.4     .05       0
Bank Sta=4984.8,4997.4
XS Rating Curve= 0 ,0
Exp/Cntr=0.3,0.1

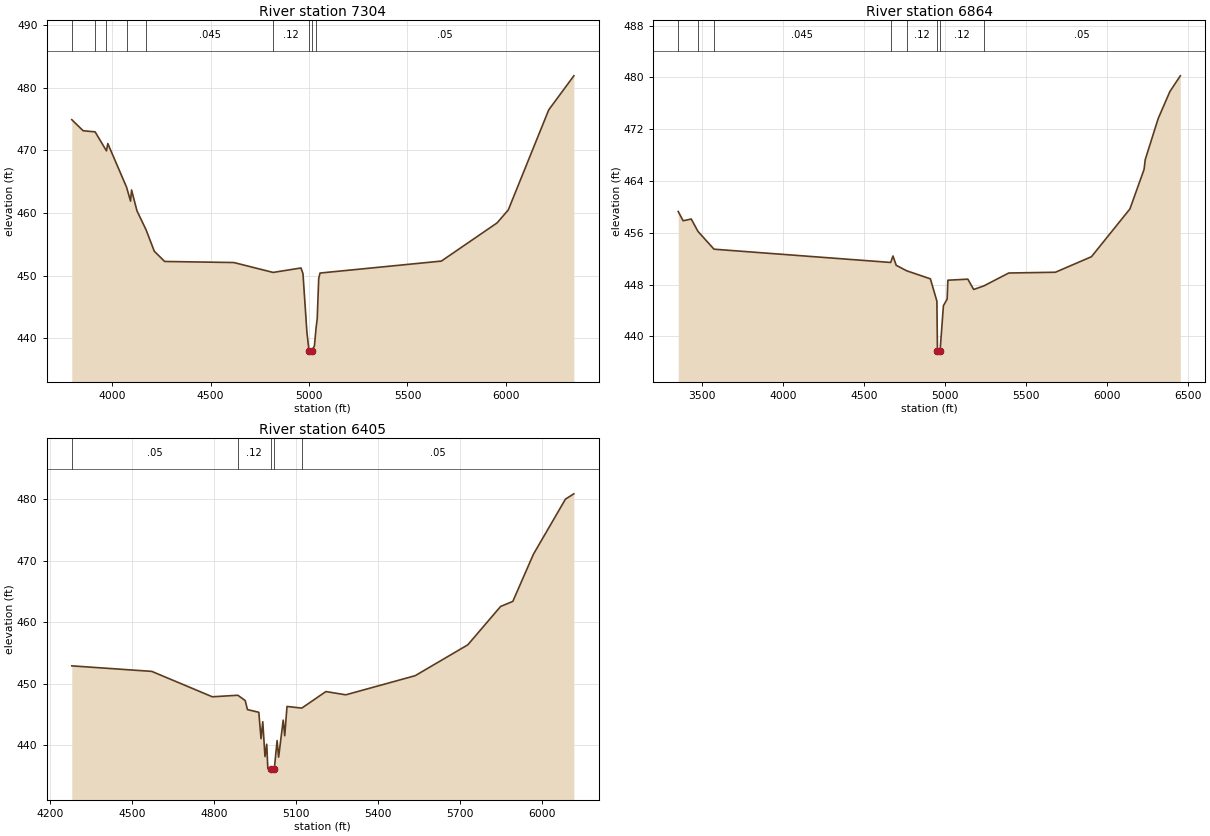
Type RM Length L Ch R = 1 ,7304    ,440,440,440
BEGIN DESCRIPTION:
CANTAU CREEK 11.0
END DESCRIPTION:
XS GIS Cut Line= 3
      2317524.99       13741975.        2318725.       13741875.
      2319724.98     13740975.02
#Sta/Elev= 30
  3795.4  474.91  3853.1  473.14    3914  472.96  3971.5  469.93  3978.5  471.09
  4073.6  464.13  4093.9   461.9    4099  463.68  4126.6  460.34  4172.6  457.33
  4214.4   453.9    4267  452.26  4618.2  452.09  4817.9  450.51  4959.4  451.22
  4969.5   450.3  4989.5  440.92  5000.3  437.96  5000.8  437.46  5013.1  437.96
  5027.6  438.77  5035.9  441.64  5041.8   443.1  5049.3  449.52    5056  450.41
  5672.2  452.32  5955.1  458.42    6012  460.49  6217.5  476.48  6344.9  481.91
#Mann= 9 ,-1 , 0
  3795.4     .12       0    3914     .05       0  3971.5     .07       0
  4073.6     .12       0  4172.6    .045       0  4817.9     .12       0
  5000.3     .05       0  5013.1     .12       0  5035.9     .05       0
Bank Sta=5000.3,5013.1
XS Rating Curve= 0 ,0
Exp/Cntr=0.3,0.1

Type RM Length L Ch R = 1 ,6864    ,459,459,459
BEGIN DESCRIPTION:
CANTAU CREEK 10.0
END DESCRIPTION:
XS GIS Cut Line= 3
      2317274.95       13742375.        2318925.       13742225.
      2319725.02     13741024.98
#Sta/Elev= 30
  3352.2  459.28  3382.4  457.85  3432.6  458.12    3474  456.21  3573.1  453.46
  4663.6  451.41  4677.7  452.41  4697.8  450.97  4762.7  450.12  4908.6  448.88
  4948.8  445.43  4952.2  437.75  4952.7  437.25  4965.4  437.75  4968.9   437.9
    4989  444.73  5012.1  445.75  5016.6  448.67  5139.8  448.83  5175.8  447.24
  5238.8  447.79  5392.1  449.78  5680.6   449.9  5902.9   452.3  6140.3  459.68
  6227.4  465.77  6234.9  467.31  6314.6  473.63  6386.7   477.8  6451.3  480.24
#Mann= 8 ,-1 , 0
  3352.2     .12       0    3474     .07       0  3573.1    .045       0
  4663.6     .05       0  4762.7     .12       0  4952.2     .05       0
  4965.4     .12       0  5238.8     .05       0
Bank Sta=4952.2,4965.4
XS Rating Curve= 0 ,0
Exp/Cntr=0.3,0.1

Type RM Length L Ch R = 1 ,6405    ,883,883,883
BEGIN DESCRIPTION:
CANTAU CREEK 9.0
END DESCRIPTION:
XS GIS Cut Line= 3
      2318883.87     13742646.02        2319325.       13742075.
        2319825.       13741075.
#Sta/Elev= 30
  4278.4  452.89  4571.6  451.99  4793.5  447.86  4886.9  448.11  4913.9  447.25
  4922.1  445.78  4963.7  445.34  4971.9  441.05  4978.2   443.8  4986.4  438.14
  4992.7  440.15  4996.8   436.2  5007.3  436.11  5007.8  435.61  5020.5  436.11
  5030.7  440.74  5036.3  438.05  5053.1  444.07  5058.7  441.53    5067  446.29
  5121.1  446.02  5209.6  448.71  5282.3  448.18  5536.6  451.29  5729.5  456.31
  5849.7  462.55  5894.4  463.37  5969.9  471.04  6087.3     480    6118  480.86
#Mann= 5 ,-1 , 0
  4278.4     .05       0  4886.9     .12       0  5007.3     .05       0
  5020.5     .12       0  5121.1     .05       0
Bank Sta=5007.3,5020.5
XS Rating Curve= 0 ,0
Exp/Cntr=0.3,0.1