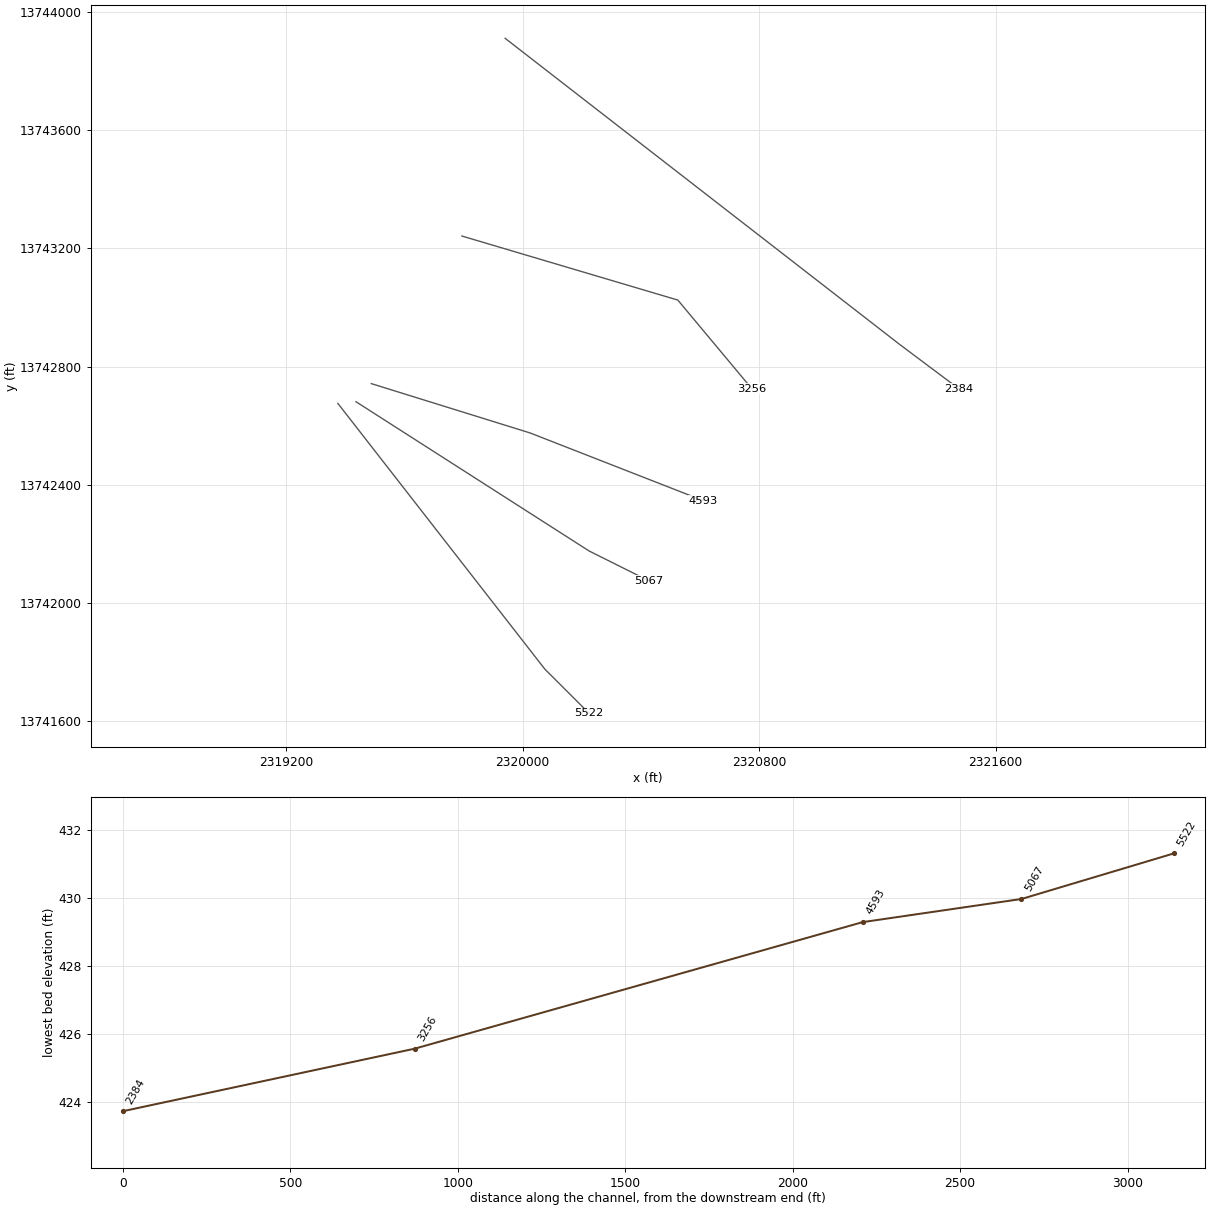
HEC-RAS study CANTAU CREEK.prj: CANTAU CREEK Base Level Engineering

--- CANTAU CREEK.g01 (geometry) --- (continued)

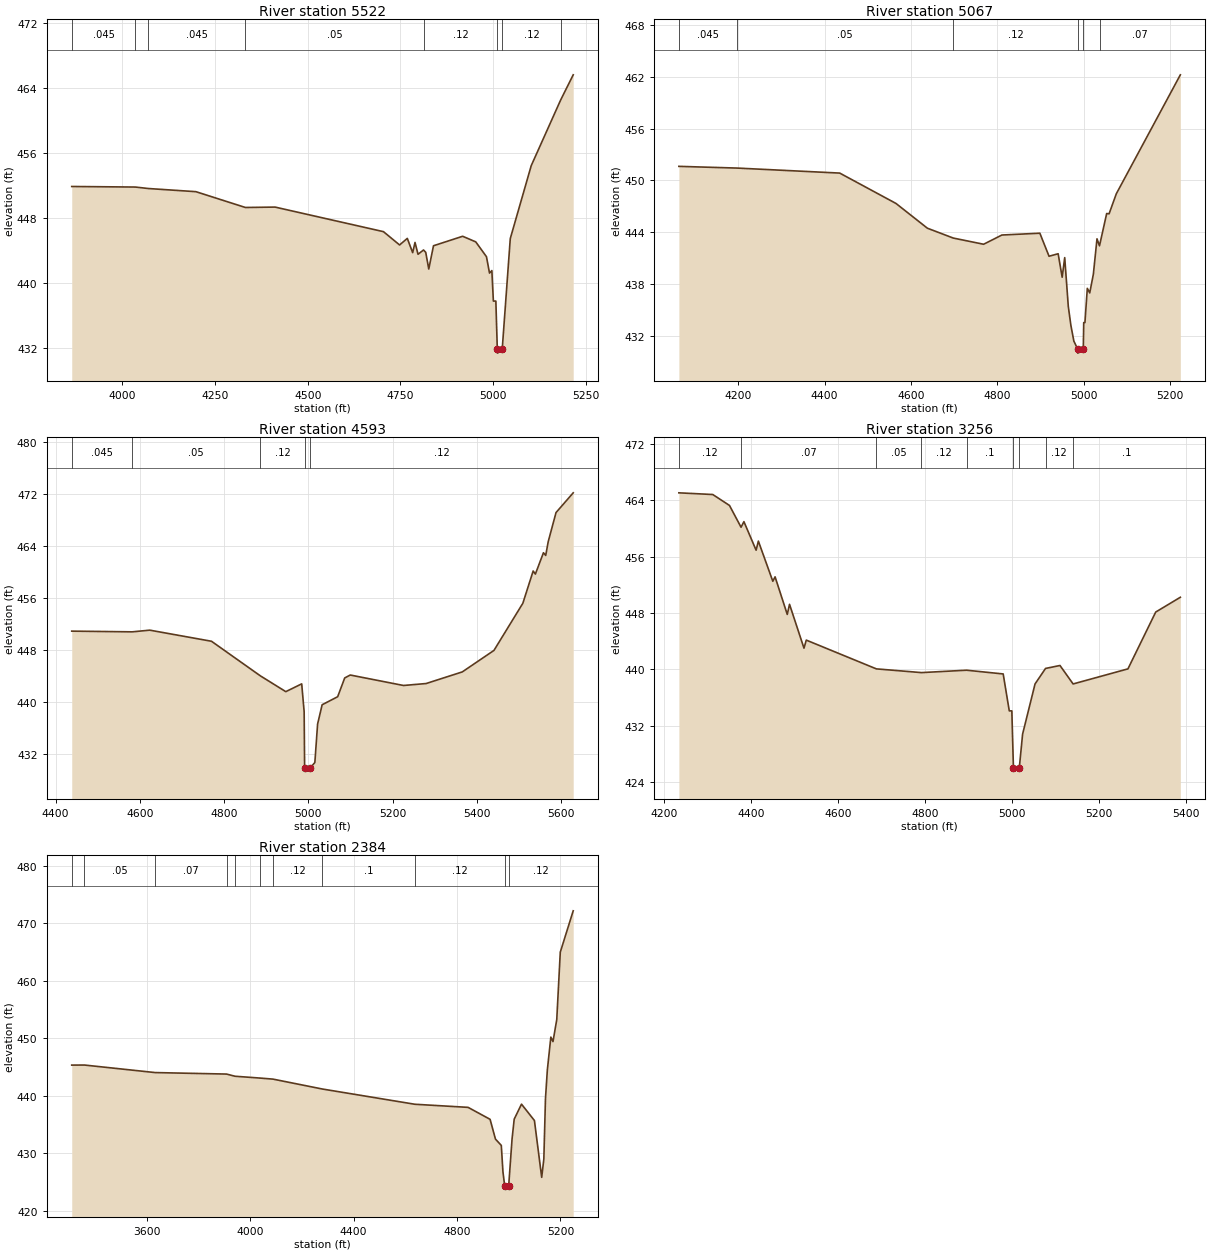
Type RM Length L Ch R = 1 ,5522    ,455,455,455
BEGIN DESCRIPTION:
CANTAU CREEK 8.0
END DESCRIPTION:
XS GIS Cut Line= 3
      2319375.02     13742674.98        2320075.       13741775.
      2320225.01     13741624.99
#Sta/Elev= 30
  3863.5  451.86  4035.2  451.79  4069.9  451.61  4198.3  451.22  4331.9  449.27
  4411.8  449.32  4704.1  446.29  4747.6  444.65  4768.4  445.46  4782.9   443.7
  4789.2  444.96  4797.3   443.5  4812.2  444.03  4818.1  443.74  4826.3  441.68
    4839  444.55  4917.7  445.72    4953  445.03  4981.9   443.2  4990.1  441.18
  4996.4  441.49  5000.5  437.73  5007.2  437.73  5011.1  431.81  5011.6  431.31
  5024.4  431.81  5046.1  445.44  5102.6  454.43    5182  462.53  5215.8  465.63
#Mann= 8 ,-1 , 0
  3863.5    .045       0  4035.2     .05       0  4069.9    .045       0
  4331.9     .05       0  4812.2     .12       0  5011.1     .05       0
  5024.4     .12       0    5182     .05       0
Bank Sta=5011.1,5024.4
XS Rating Curve= 0 ,0
Exp/Cntr=0.3,0.1

Type RM Length L Ch R = 1 ,5067    ,474,474,474
BEGIN DESCRIPTION:
CANTAU CREEK 7.0
END DESCRIPTION:
XS GIS Cut Line= 3
      2319436.22      13742680.7        2320225.       13742175.
      2320425.03     13742074.99
#Sta/Elev= 30
  4062.6  451.62  4197.7  451.42  4434.9  450.84  4565.1  447.32  4637.8  444.45
  4697.6  443.31  4767.9  442.59  4810.2  443.66  4898.1  443.87  4919.3   441.2
  4940.4  441.49  4949.7  438.77  4955.6  441.04  4963.9  435.38  4969.9  433.18
  4976.8  431.36  4985.3  430.47  4985.8  429.97  4998.6  430.47  4999.6  433.51
  5002.4  433.51  5007.9  437.48  5013.5  436.95  5021.9  439.12  5030.3  443.22
  5036.1  442.41  5052.7  446.15  5058.3  446.12    5075  448.44  5223.2  462.23
#Mann= 6 ,-1 , 0
  4062.6    .045       0  4197.7     .05       0  4697.6     .12       0
  4985.3     .05       0  4998.6     .12       0  5036.1     .07       0
Bank Sta=4985.3,4998.6
XS Rating Curve= 0 ,0
Exp/Cntr=0.3,0.1

Type RM Length L Ch R = 1 ,4593    ,1337,1337,1337
BEGIN DESCRIPTION:
CANTAU CREEK 6.0
END DESCRIPTION:
XS GIS Cut Line= 3
      2319488.04     13742742.04        2320025.       13742575.
      2320610.25     13742345.98
#Sta/Elev= 30
  4438.2  450.85  4581.8  450.74  4623.5     451  4770.1  449.29  4886.2  443.96
  4946.5  441.53  4984.3  442.73  4990.1  438.42  4991.2  429.79  4991.7  429.29
  5004.1  429.29  5004.6  429.79  5015.5  430.62    5022  436.53  5032.8  439.51
  5069.7  440.75  5086.4  443.64  5099.6  444.09    5226  442.48  5279.7  442.78
  5365.6  444.57  5440.8  447.88  5509.4  455.14  5533.9  460.11  5539.2  459.64
  5558.3  462.92  5563.7  462.51  5569.7  464.64  5588.2  469.11    5629  472.15
#Mann= 5 ,-1 , 0
  4438.2    .045       0  4581.8     .05       0  4886.2     .12       0
  4991.2     .05       0  5004.6     .12       0
Bank Sta=4991.2,5004.6
XS Rating Curve= 0 ,0
Exp/Cntr=0.3,0.1

Type RM Length L Ch R = 1 ,3256    ,872,872,872
BEGIN DESCRIPTION:
CANTAU CREEK 5.0
END DESCRIPTION:
XS GIS Cut Line= 3
      2319794.63     13743241.96        2320525.       13743025.
      2320774.98     13742725.02
#Sta/Elev= 30
  4233.8  465.06  4311.7  464.82  4350.1  463.27  4376.7  460.18  4383.3  460.97
  4411.3  456.92  4416.5  458.21  4449.7  452.51  4454.9  453.14  4482.9  447.81
  4488.1  449.24  4521.3  443.02  4526.6  444.16  4687.6  440.08  4791.2  439.55
  4894.8  439.89  4979.1  439.36  4993.1  434.12    4999  434.12  5002.6  426.07
  5003.1  425.57  5016.2  426.07  5023.7  430.82  5052.3  437.94  5076.4  440.14
  5109.6  440.56  5139.8  437.94  5265.8  440.08  5329.6  448.14  5386.2  450.24
#Mann= 9 ,-1 , 0
  4233.8     .12       0  4376.7     .07       0  4687.6     .05       0
  4791.2     .12       0  4894.8      .1       0  5002.6     .05       0
  5016.2      .1       0  5076.4     .12       0  5139.8      .1       0
Bank Sta=5002.6,5016.2
XS Rating Curve= 0 ,0
Exp/Cntr=0.3,0.1

Type RM Length L Ch R = 1 ,2384    ,0,0,0
BEGIN DESCRIPTION:
CANTAU CREEK 4.0
END DESCRIPTION:
XS GIS Cut Line= 3
      2319940.84     13743911.66        2321275.       13742875.
      2321475.03     13742724.98
#Sta/Elev= 30
  3309.7   445.3  3358.8  445.31  3632.2     444  3908.7  443.74  3941.4  443.36
  4036.3  443.05  4088.3  442.86  4279.2  441.14  4636.7  438.49  4842.7  437.95
  4927.8  435.87  4948.6  432.43  4971.2  431.33  4977.5  426.76  4984.4  424.23
  4984.9  423.73  4999.6  424.23  5012.8  432.47  5021.1   435.9  5049.3  438.51
  5099.3  435.66  5127.4  425.78  5135.7  428.97    5142  439.45  5149.3  444.47
  5162.8  450.17  5171.1  449.39  5185.7  453.23  5199.3  464.94  5249.3  472.13
#Mann= 11 ,-1 , 0
  3309.7    .035       0  3358.8     .05       0  3632.2     .07       0
  3908.7      .1       0  3941.4     .12       0  4036.3      .1       0
  4088.3     .12       0  4279.2      .1       0  4636.7     .12       0
  4984.4     .05       0  4999.6     .12       0
Bank Sta=4984.4,4999.6
XS Rating Curve= 0 ,0
Exp/Cntr=0.3,0.1

Chan Stop Cuts=-1
Use User Specified Reach Order=0
Composite Channel Slope=5