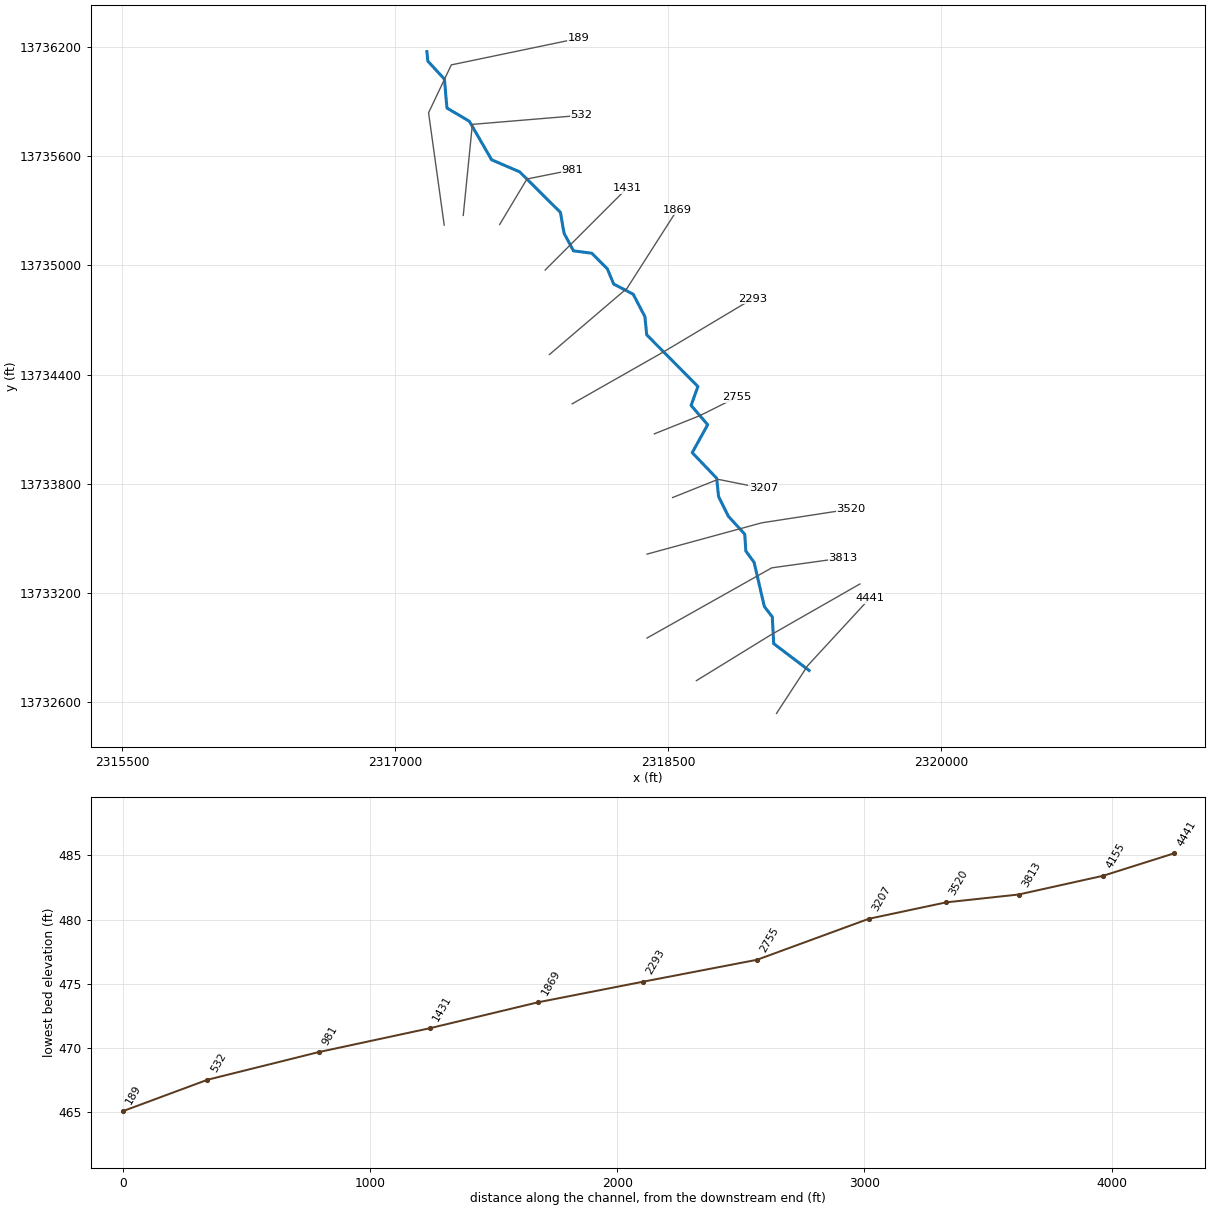
--- CANTAU TRIBUTARY 3.prj (project) ---

Proj Title=CANTAU TRIBUTARY 3 Base Level Engineering
Current Plan=p01
Default Exp/Contr=0.3,0.1
English Units
Geom File=g01
Flow File=f01
Plan File=p01
BEGIN DESCRIPTION:
CANTAU TRIBUTARY 3
END DESCRIPTION:

--- CANTAU TRIBUTARY 3.p01 (plan) ---

Plan Title=Multiple Run
Short Identifier=Multiple
Geom File=g01
Flow File=f01
Subcritical Flow
K Sum by GR= 0
Std Step Tol= 0.01
Critical Tol= 0.01
Num of Std Step Trials= 20
Max Error Tol= 0.3
Flow Tol Ratio= 0.001
Split Flow NTrial= 30
Split Flow Tol= 0.02
Split Flow Ratio= 0.02
Log Output Level= 0
Friction Slope Method= 1
Unsteady Friction Slope Method= 2
Unsteady Bridges Friction Slope Method= 1
Parabolic Critical Depth
Global Vel Dist=  1 , 1 , 1
Global Log Level= 0
CheckData=True
Encroach Param= -1, 0, 0, 0
BEGIN DESCRIPTION:
Multiple Run
END DESCRIPTION:

--- CANTAU TRIBUTARY 3.f01 (steady flow) ---

Flow Title=Multiple
Number of Profiles=7
Profile Names=10-year,25-year,50-year,1pct_min,100-year,1pct_plu,500-year
River Rch & RM= CANTAU TRIBUTARY,Reach-1,4441
     523     836    1115     721    1439    2871    2372
Boundary for River Rch & Prof#=CANTAU TRIBUTARY,Reach-1,1
Up Type=0
Dn Type=3
Dn Slope=0.005
Boundary for River Rch & Prof#=CANTAU TRIBUTARY,Reach-1,2
Up Type=0
Dn Type=3
Dn Slope=0.005
Boundary for River Rch & Prof#=CANTAU TRIBUTARY,Reach-1,3
Up Type=0
Dn Type=3
Dn Slope=0.005
Boundary for River Rch & Prof#=CANTAU TRIBUTARY,Reach-1,4
Up Type=0
Dn Type=3
Dn Slope=0.005
Boundary for River Rch & Prof#=CANTAU TRIBUTARY,Reach-1,5
Up Type=0
Dn Type=3
Dn Slope=0.005
Boundary for River Rch & Prof#=CANTAU TRIBUTARY,Reach-1,6
Up Type=0
Dn Type=3
Dn Slope=0.005
Boundary for River Rch & Prof#=CANTAU TRIBUTARY,Reach-1,7
Up Type=0
Dn Type=3
Dn Slope=0.005

--- CANTAU TRIBUTARY 3.g01 (geometry) ---

Geom Title=Existing Conditions

River Reach=CANTAU TRIBUTARY,Reach-1
Reach XY= 30
      2319275.00     13732775.00      2319080.36     13732922.30
      2319072.73     13733069.06      2319028.86     13733126.60
      2318972.65     13733369.03      2318927.36     13733430.98
      2318921.38     13733523.50      2318830.85     13733622.71
      2318777.33     13733730.97      2318767.14     13733831.17
      2318632.77     13733971.59      2318717.70     13734125.08
      2318626.68     13734231.05      2318663.89     13734335.05
      2318382.86     13734618.83      2318372.67     13734719.03
      2318308.51     13734842.05      2318201.17     13734897.86
      2318166.84     13734981.05      2318081.14     13735067.12
      2317980.44     13735080.25      2317928.81     13735176.55
      2317908.54     13735291.75      2317684.68     13735514.23
      2317530.61     13735580.59      2317408.50     13735792.05
      2317285.35     13735864.88      2317271.46     13736023.53
      2317180.33     13736122.49      2317175.00     13736175.00

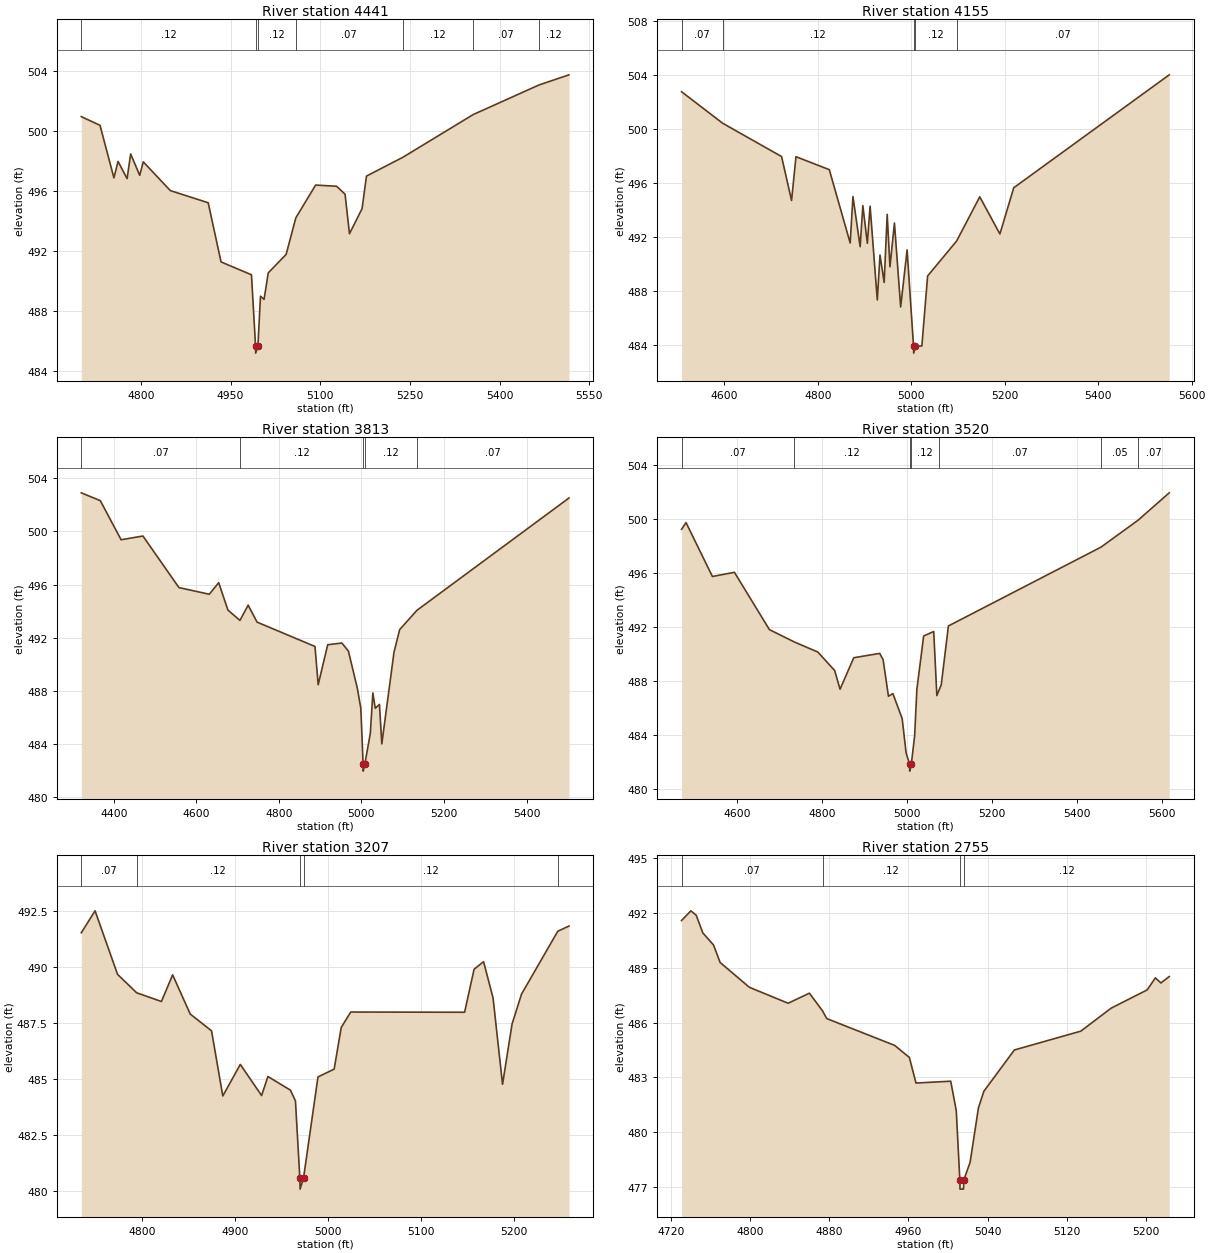
Type RM Length L Ch R = 1,4441,286,286,286
BEGIN DESCRIPTION:
X18409
END DESCRIPTION:
XS GIS Cut Line= 3
      2319095.81     13732539.31      2319267.70     13732802.35
      2319607.87     13733171.08
#Sta/Elev= 30
  4700.2  500.95  4731.5  500.37  4754.8  496.86  4761.7  497.96  4776.8  496.81
  4782.8  498.46  4797.9  497.03  4803.9  497.93  4849.2  496.01  4912.5  495.20
  4934.0  491.25  4984.9  490.39  4991.7  485.66  4991.9  485.16  4995.7  485.66
  5000.0  488.96  5006.0  488.75  5013.0  490.52  5042.9  491.75  5059.1  494.19
  5092.2  496.38  5127.4  496.30  5141.5  495.77  5148.9  493.13  5169.9  494.80
  5177.3  496.98  5238.0  498.23  5356.0  501.09  5465.8  503.06  5516.1  503.74
#Mann=7,-1,0
  4700.2    0.12       0  4991.7    0.05       0  4995.7    0.12       0
  5059.1    0.07       0  5238.0    0.12       0  5356.0    0.07       0
  5465.8    0.12       0
Bank Sta=4991.7,4995.7
Exp/Cntr=0.3,0.1

Type RM Length L Ch R = 1,4155,342,342,342
BEGIN DESCRIPTION:
X18410
END DESCRIPTION:
XS GIS Cut Line= 3
      2318655.68     13732718.99      2319061.97     13732969.02
      2319553.95     13733250.15
#Sta/Elev= 30
  4508.3  502.77  4596.1  500.44  4722.4  497.97  4743.7  494.72  4753.2  497.96
  4824.5  497.00  4869.2  491.57  4875.1  495.01  4890.5  491.30  4896.3  494.34
  4905.9  491.55  4911.8  494.30  4927.2  487.36  4933.0  490.68  4941.9  488.65
  4948.4  493.69  4954.3  489.81  4963.9  493.05  4977.2  486.84  4991.0  491.06
  5004.8  483.92  5005.1  483.42  5008.8  483.92  5022.6  483.95  5034.9  489.13
  5097.0  491.72  5146.5  494.99  5189.6  492.24  5219.2  495.66  5552.0  504.02
#Mann=5,-1,0
  4508.3    0.07       0  4596.1    0.12       0  5004.8    0.05       0
  5008.8    0.12       0  5097.0    0.07       0
Bank Sta=5004.8,5008.8
Exp/Cntr=0.3,0.1

Type RM Length L Ch R = 1,3813,293,293,293
BEGIN DESCRIPTION:
X18411
END DESCRIPTION:
XS GIS Cut Line= 3
      2318384.85     13732953.37      2319069.78     13733338.81
      2319461.48     13733393.28
#Sta/Elev= 30
  4321.4  502.90  4367.5  502.31  4417.8  499.37  4470.7  499.65  4558.0  495.77
  4631.4  495.27  4654.3  496.14  4676.6  494.08  4705.7  493.30  4725.6  494.45
  4747.3  493.17  4887.5  491.34  4895.3  488.46  4918.3  491.47  4952.7  491.60
  4968.5  490.99  4990.1  488.20  4998.6  486.68  5004.1  482.46  5004.3  481.96
  5008.1  482.46  5021.5  484.79  5027.7  487.84  5033.5  486.69  5043.7  486.98
  5049.4  484.01  5078.9  490.91  5092.7  492.61  5134.5  494.06  5502.8  502.51
#Mann=5,-1,0
  4321.4    0.07       0  4705.7    0.12       0  5004.1    0.05       0
  5008.1    0.12       0  5134.5    0.07       0
Bank Sta=5004.1,5008.1
Exp/Cntr=0.3,0.1

Type RM Length L Ch R = 1,3520,313,313,313
BEGIN DESCRIPTION:
X18412
END DESCRIPTION:
XS GIS Cut Line= 3
      2318384.86     13733414.32      2319015.09     13733586.21
      2319504.65     13733661.72
#Sta/Elev= 30
  4469.5  499.24  4480.0  499.74  4542.2  495.75  4594.0  496.06  4676.4  491.82
  4734.8  490.91  4790.5  490.16  4830.2  488.79  4842.8  487.41  4875.1  489.74
  4936.1  490.06  4944.2  489.60  4956.8  486.89  4967.2  487.09  4989.1  485.24
  4998.3  482.72  5006.6  481.85  5006.9  481.35  5010.6  481.85  5018.5  483.97
  5023.7  487.39  5039.7  491.35  5063.4  491.68  5070.8  486.94  5075.5  487.31
  5081.2  487.75  5098.0  492.09  5457.3  497.92  5544.5  499.91  5618.1  501.94
#Mann=7,-1,0
  4469.5    0.07       0  4734.8    0.12       0  5006.6    0.05       0
  5010.6    0.12       0  5075.5    0.07       0  5457.3    0.05       0
  5544.5    0.07       0
Bank Sta=5006.6,5010.6
Exp/Cntr=0.3,0.1

Type RM Length L Ch R = 1,3207,452,452,452
BEGIN DESCRIPTION:
CANTAU TRIBUTARY 3 7.0
END DESCRIPTION:
XS GIS Cut Line= 3
      2318525.04     13733725.02      2318775.00     13733825.00
      2319025.04     13733774.99
#Sta/Elev= 30
  4734.7  491.52  4749.5  492.50  4773.7  489.66  4794.2  488.84  4820.8  488.45
  4832.9  489.64  4851.8  487.89  4874.7  487.14  4886.8  484.23  4905.6  485.64
  4928.5  484.25  4935.3  485.10  4959.5  484.49  4964.9  484.01  4969.6  480.57
  4969.9  480.07  4973.6  480.57  4989.1  485.08  5006.5  485.43  5014.1  487.29
  5024.3  487.98  5146.7  487.97  5156.9  489.89  5167.1  490.23  5177.3  488.61
  5187.5  484.75  5197.7  487.44  5207.9  488.78  5246.9  491.59  5258.9  491.82
#Mann=5,-1,0
  4734.7    0.07       0  4794.2    0.12       0  4969.6    0.05       0
  4973.6    0.12       0  5246.9    0.07       0
Bank Sta=4969.6,4973.6
Exp/Cntr=0.3,0.1

Type RM Length L Ch R = 1,2755,462,462,462
BEGIN DESCRIPTION:
CANTAU TRIBUTARY 3 6.0
END DESCRIPTION:
XS GIS Cut Line= 3
      2318425.05     13734075.02      2318675.00     13734175.00
      2318874.99     13734274.99
#Sta/Elev= 30
  4730.7  491.59  4740.1  492.12  4745.5  491.88  4752.2  490.91  4763.0  490.25
  4769.7  489.29  4799.3  487.93  4838.4  487.06  4859.9  487.61  4873.2  486.64
  4877.4  486.22  4946.1  484.75  4960.9  484.09  4967.6  482.69  5002.7  482.79
  5008.3  481.18  5011.9  477.38  5012.1  476.88  5015.6  476.88  5015.9  477.38
  5022.3  478.35  5030.7  481.33  5036.2  482.24  5067.0  484.50  5134.1  485.53
  5164.8  486.79  5201.2  487.79  5209.5  488.45  5215.1  488.17  5223.5  488.52
#Mann=4,-1,0
  4730.7    0.07       0  4873.2    0.12       0  5011.9    0.05       0
  5015.9    0.12       0
Bank Sta=5011.9,5015.9
Exp/Cntr=0.3,0.1

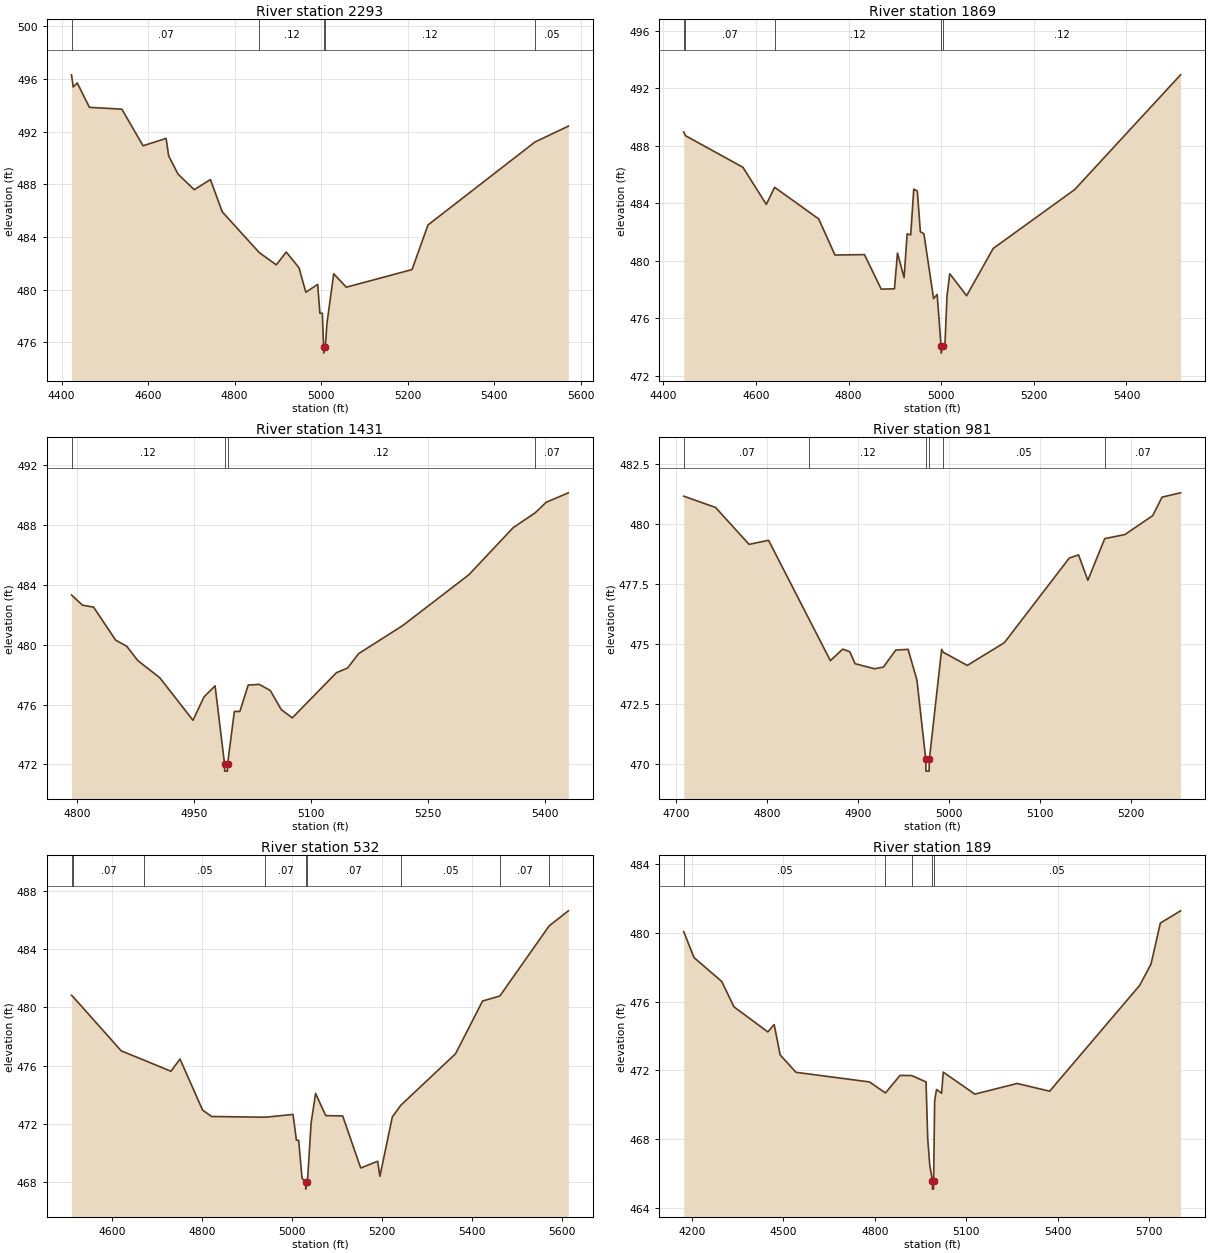
Type RM Length L Ch R = 1,2293,424,424,424
BEGIN DESCRIPTION:
CANTAU TRIBUTARY 3 5.0
END DESCRIPTION:
XS GIS Cut Line= 3
      2317973.46     13734239.87      2318475.00     13734525.00
      2318965.65     13734817.99
#Sta/Elev= 30
  4423.1  496.32  4427.0  495.40  4436.4  495.70  4464.5  493.85  4539.5  493.71
  4588.5  490.93  4641.8  491.49  4647.6  490.17  4669.2  488.78  4706.7  487.59
  4744.2  488.36  4771.5  485.91  4857.1  482.81  4896.5  481.88  4919.5  482.85
  4948.9  481.66  4964.7  479.80  4992.1  480.39  4997.2  478.20  5002.9  478.20
  5005.8  475.67  5006.1  475.17  5009.8  475.67  5013.6  477.45  5029.2  481.20
  5058.3  480.18  5210.2  481.52  5247.1  484.91  5494.2  491.21  5571.5  492.42
#Mann=5,-1,0
  4423.1    0.07       0  4857.1    0.12       0  5005.8    0.05       0
  5009.8    0.12       0  5494.2    0.05       0
Bank Sta=5005.8,5009.8
Exp/Cntr=0.3,0.1

Type RM Length L Ch R = 1,1869,438,438,438
BEGIN DESCRIPTION:
CANTAU TRIBUTARY 3 4.0
END DESCRIPTION:
XS GIS Cut Line= 3
      2317848.41     13734510.67      2318275.00     13734875.00
      2318550.80     13735306.38
#Sta/Elev= 30
  4443.9  488.95  4447.6  488.69  4571.8  486.49  4622.3  483.91  4640.1  485.10
  4735.4  482.90  4770.5  480.39  4834.2  480.42  4870.4  478.02  4899.0  478.04
  4905.5  480.53  4919.8  478.82  4926.4  481.86  4934.1  481.79  4940.7  484.97
  4948.4  484.84  4954.9  482.01  4962.6  481.87  4983.5  477.36  4991.2  477.65
  4999.6  474.07  4999.9  473.57  5003.6  474.07  5007.9  474.07  5012.5  477.54
  5018.4  479.09  5054.8  477.56  5112.3  480.85  5288.2  484.94  5516.9  492.92
#Mann=5,-1,0
  4443.9    0.05       0  4447.6    0.07       0  4640.1    0.12       0
  4999.6    0.05       0  5003.6    0.12       0
Bank Sta=4999.6,5003.6
Exp/Cntr=0.3,0.1

Type RM Length L Ch R = 1,1431,450,450,450
BEGIN DESCRIPTION:
CANTAU TRIBUTARY 3 3.0
END DESCRIPTION:
XS GIS Cut Line= 3
      2317825.00     13734975.00      2317975.00     13735125.00
      2318275.00     13735425.00
#Sta/Elev= 30
  4793.3  483.32  4807.4  482.64  4821.6  482.51  4849.9  480.30  4864.0  479.90
  4878.2  478.94  4906.4  477.79  4948.9  474.95  4963.0  476.51  4977.2  477.25
  4989.3  472.05  4989.5  471.55  4993.0  471.55  4993.3  472.05  5001.9  475.54
  5009.0  475.54  5019.6  477.30  5033.7  477.35  5047.9  476.94  5062.0  475.66
  5076.1  475.11  5132.7  478.13  5146.9  478.44  5161.0  479.40  5217.6  481.28
  5302.4  484.68  5359.0  487.82  5387.1  488.81  5401.4  489.52  5429.7  490.15
#Mann=4,-1,0
  4793.3    0.12       0  4989.3    0.05       0  4993.3    0.12       0
  5387.1    0.07       0
Bank Sta=4989.3,4993.3
Exp/Cntr=0.3,0.1

Type RM Length L Ch R = 1,981,449,449,449
BEGIN DESCRIPTION:
CANTAU TRIBUTARY 3 2.0
END DESCRIPTION:
XS GIS Cut Line= 3
      2317575.01     13735225.02      2317725.00     13735475.00
      2317975.03     13735525.01
#Sta/Elev= 30
  4708.2  481.16  4743.2  480.69  4780.1  479.15  4801.5  479.32  4846.3  476.01
  4869.5  474.30  4883.1  474.78  4890.9  474.67  4896.7  474.17  4918.1  473.96
  4927.8  474.03  4941.4  474.74  4955.0  474.77  4964.7  473.49  4974.4  470.19
  4974.6  469.69  4978.1  469.69  4978.4  470.19  4991.9  474.77  4993.6  474.65
  5020.1  474.10  5060.9  475.05  5132.3  478.58  5142.5  478.71  5152.7  477.65
  5171.3  479.39  5193.5  479.56  5224.1  480.35  5234.3  481.12  5254.7  481.30
#Mann=6,-1,0
  4708.2    0.07       0  4846.3    0.12       0  4974.4    0.05       0
  4978.4    0.12       0  4993.6    0.05       0  5171.3    0.07       0
Bank Sta=4974.4,4978.4
Exp/Cntr=0.3,0.1

Type RM Length L Ch R = 1,532,343,343,343
BEGIN DESCRIPTION:
CANTAU TRIBUTARY 3 1.0
END DESCRIPTION:
XS GIS Cut Line= 3
      2317375.00     13735275.03      2317425.00     13735775.00
      2318024.96     13735825.00
#Sta/Elev= 30
  4509.9  480.83  4513.9  480.71  4620.4  477.02  4672.1  476.37  4731.0  475.62
  4751.1  476.46  4801.3  472.96  4821.4  472.52  4940.4  472.47  5002.3  472.66
  5009.9  470.89  5014.9  470.89  5022.4  468.28  5030.4  468.04  5030.7  467.54
  5034.4  468.04  5042.5  472.06  5052.5  474.10  5075.1  472.58  5112.7  472.56
  5152.8  468.99  5190.5  469.45  5195.5  468.42  5223.1  472.49  5242.0  473.29
  5363.6  476.82  5423.8  480.44  5462.1  480.78  5571.8  485.59  5614.4  486.62
#Mann=9,-1,0
  4509.9    0.05       0  4513.9    0.07       0  4672.1    0.05       0
  4940.4    0.07       0  5030.4    0.05       0  5034.4    0.07       0
  5242.0    0.05       0  5462.1    0.07       0  5571.8    0.05       0
Bank Sta=5030.4,5034.4
Exp/Cntr=0.3,0.1

Type RM Length L Ch R = 1,189,0,0,0
BEGIN DESCRIPTION:
X18413
END DESCRIPTION:
XS GIS Cut Line= 4
      2317270.30     13735221.63      2317184.37     13735838.81
      2317309.37     13736101.83      2318009.90     13736247.67
#Sta/Elev= 30
  4173.3  480.08  4207.0  478.57  4297.9  477.18  4338.2  475.70  4449.3  474.24
  4470.0  474.67  4489.7  472.90  4541.6  471.89  4782.5  471.33  4835.1  470.69
  4882.9  471.71  4921.2  471.70  4968.2  471.33  4973.8  468.00  4980.4  466.48
  4989.0  465.59  4989.2  465.09  4992.7  465.09  4993.0  465.59  4996.5  470.23
  5002.6  470.89  5019.2  470.67  5024.7  471.90  5128.4  470.62  5267.0  471.24
  5373.7  470.79  5669.0  476.95  5706.3  478.19  5736.9  480.58  5803.2  481.29
#Mann=5,-1,0
  4173.3    0.05       0  4835.1    0.07       0  4921.2    0.05       0
  4989.0    0.05       0  4993.0    0.05       0
Bank Sta=4989,4993
Exp/Cntr=0.3,0.1

Chan Stop Cuts=-1