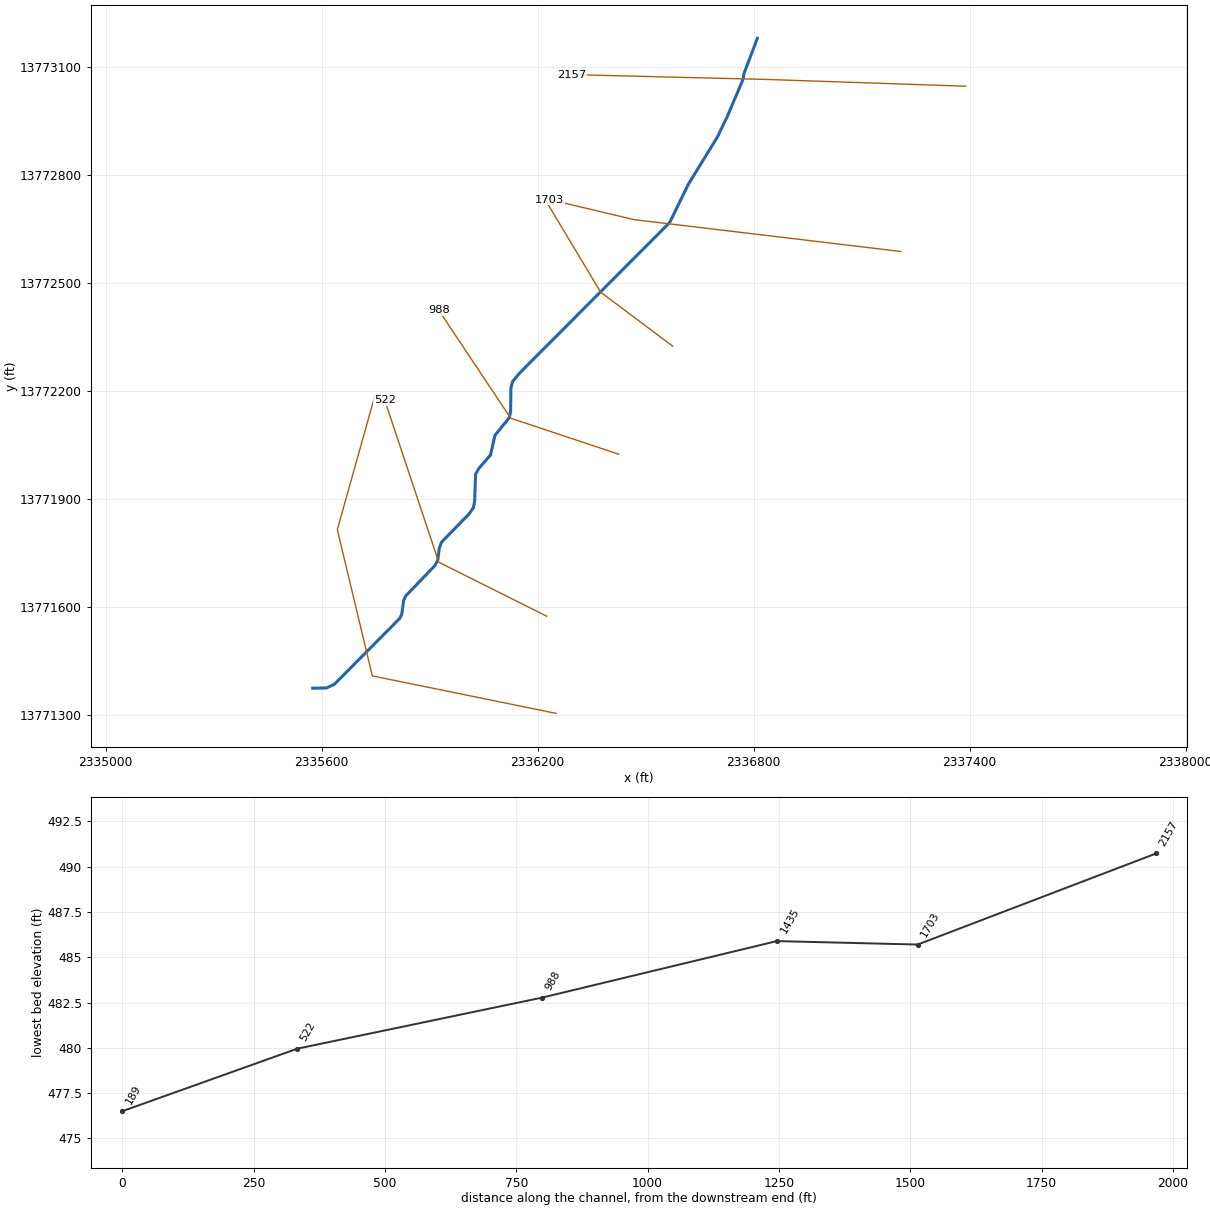
--- CIBOLO TRIBUTARY 14.prj (project) ---

Proj Title=CIBOLO TRIBUTARY 14 Base Level Engineering
Current Plan=p01
Default Exp/Contr=0.3,0.1
English Units
Geom File=g01
Flow File=f01
Plan File=p01
BEGIN DESCRIPTION:
CIBOLO TRIBUTARY 14
END DESCRIPTION:

--- CIBOLO TRIBUTARY 14.p01 (plan) ---

Plan Title=Multiple Run
Short Identifier=Multiple
Geom File=g01
Flow File=f01
Subcritical Flow
K Sum by GR= 0
Std Step Tol= 0.01
Critical Tol= 0.01
Num of Std Step Trials= 20
Max Error Tol= 0.3
Flow Tol Ratio= 0.001
Split Flow NTrial= 30
Split Flow Tol= 0.02
Split Flow Ratio= 0.02
Log Output Level= 0
Friction Slope Method= 1
Unsteady Friction Slope Method= 2
Unsteady Bridges Friction Slope Method= 1
Parabolic Critical Depth
Global Vel Dist=  1 , 1 , 1
Global Log Level= 0
CheckData=True
Encroach Param= -1, 0, 0, 0
BEGIN DESCRIPTION:
Multiple Run
END DESCRIPTION:

--- CIBOLO TRIBUTARY 14.f01 (steady flow) ---

Flow Title=Multiple
Number of Profiles=7
Profile Names=10-year,25-year,50-year,1pct_min,100-year,1pct_plu,500-year
River Rch & RM= CIBOLO TRIBUTARY,Reach-1,2157
     376     589     776     497     991    1978    1598
Boundary for River Rch & Prof#=CIBOLO TRIBUTARY,Reach-1,1
Up Type=0
Dn Type=3
Dn Slope=0.005
Boundary for River Rch & Prof#=CIBOLO TRIBUTARY,Reach-1,2
Up Type=0
Dn Type=3
Dn Slope=0.005
Boundary for River Rch & Prof#=CIBOLO TRIBUTARY,Reach-1,3
Up Type=0
Dn Type=3
Dn Slope=0.005
Boundary for River Rch & Prof#=CIBOLO TRIBUTARY,Reach-1,4
Up Type=0
Dn Type=3
Dn Slope=0.005
Boundary for River Rch & Prof#=CIBOLO TRIBUTARY,Reach-1,5
Up Type=0
Dn Type=3
Dn Slope=0.005
Boundary for River Rch & Prof#=CIBOLO TRIBUTARY,Reach-1,6
Up Type=0
Dn Type=3
Dn Slope=0.005
Boundary for River Rch & Prof#=CIBOLO TRIBUTARY,Reach-1,7
Up Type=0
Dn Type=3
Dn Slope=0.005

--- CIBOLO TRIBUTARY 14.g01 (geometry) ---

Geom Title=Existing Conditions

River Reach=CIBOLO TRIBUTARY,Reach-1
Reach XY= 30
      2336810.23     13773180.32      2336773.31     13773083.32
      2336770.74     13773067.06      2336727.10     13772964.19
      2336699.05     13772906.00      2336618.00     13772774.03
      2336566.86     13772668.94      2336151.18     13772251.87
      2336130.52     13772227.43      2336125.52     13772209.78
      2336124.76     13772145.10      2336121.17     13772126.59
      2336081.11     13772077.18      2336068.89     13772022.82
      2336035.84     13771984.65      2336027.33     13771969.03
      2336024.87     13771895.05      2336021.38     13771876.50
      2336008.51     13771858.26      2335933.18     13771781.04
      2335926.55     13771764.36      2335922.46     13771731.05
      2335914.20     13771715.33      2335833.18     13771631.04
      2335827.54     13771618.95      2335822.47     13771581.05
      2335816.84     13771568.95      2335634.79     13771385.51
      2335613.16     13771375.59      2335575.00     13771375.00

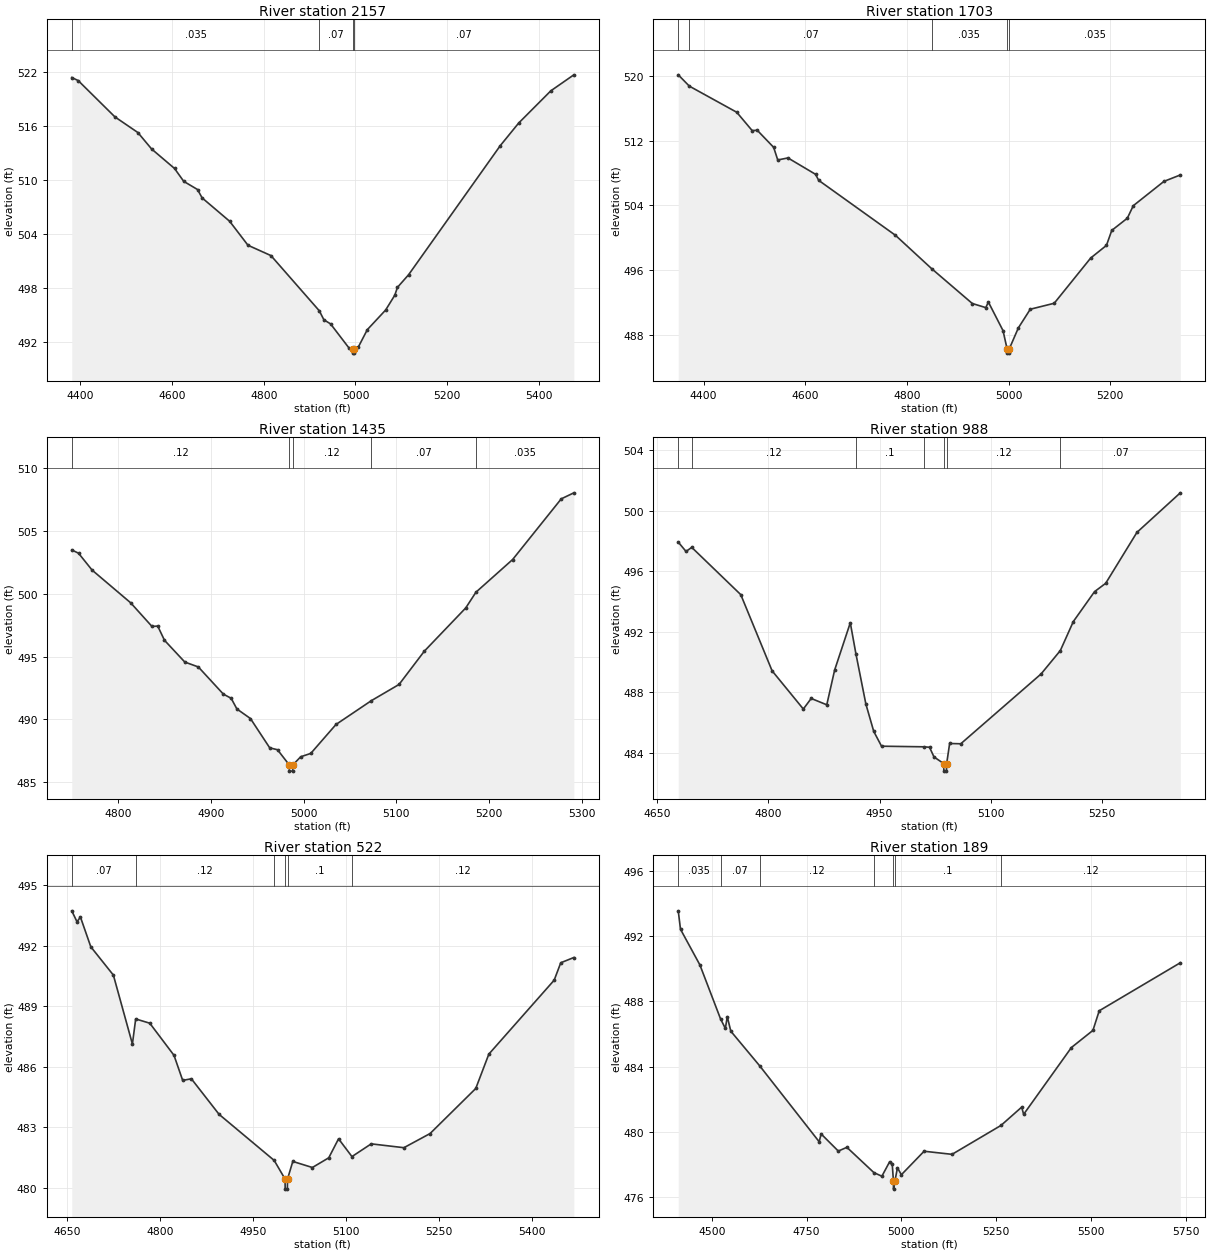
Type RM Length L Ch R = 1,2157,454,454,454
BEGIN DESCRIPTION:
CIBOLO TRIBUTARY 14 4.0
END DESCRIPTION:
XS GIS Cut Line= 3
      2337389.01     13773047.31      2336839.32     13773066.02
      2336294.79     13773079.53
#Sta/Elev= 30
  4381.5  521.39  4395.5  521.05  4475.6  517.01  4525.6  515.27  4555.6  513.44
  4605.6  511.27  4625.6  509.84  4655.7  508.93  4665.7  508.00  4725.7  505.40
  4765.7  502.73  4815.8  501.58  4921.2  495.44  4931.2  494.44  4945.8  493.98
  4985.8  491.31  4993.8  491.23  4994.1  490.73  4997.6  490.73  4997.8  491.23
  5005.8  491.36  5025.9  493.34  5065.9  495.53  5085.9  497.18  5091.5  498.04
  5115.9  499.45  5315.9  513.82  5356.0  516.33  5426.0  519.91  5476.2  521.69
#Mann=4,-1,0
  4381.5   0.035       0  4921.2    0.07       0  4993.8    0.05       0
  4997.8    0.07       0
Bank Sta=4993.8,4997.8
Exp/Cntr=0.3,0.1

Type RM Length L Ch R = 1,1703,268,268,268
BEGIN DESCRIPTION:
X18456
END DESCRIPTION:
XS GIS Cut Line= 3
      2337209.32     13772588.10      2336467.98     13772676.64
      2336233.59     13772732.20
#Sta/Elev= 30
  4350.2  520.19  4372.0  518.79  4465.3  515.55  4495.6  513.28  4505.6  513.32
  4537.9  511.20  4545.9  509.64  4566.0  509.89  4620.3  507.86  4626.5  507.11
  4777.5  500.30  4848.4  496.18  4928.6  491.85  4955.1  491.34  4960.2  492.03
  4989.0  488.49  4997.1  486.20  4997.4  485.70  5000.9  485.70  5001.1  486.20
  5019.2  488.83  5042.6  491.14  5089.7  491.88  5161.5  497.49  5192.4  499.05
  5202.9  500.91  5233.5  502.42  5245.2  503.97  5305.4  506.98  5337.7  507.78
#Mann=5,-1,0
  4350.2   0.035       0  4372.0    0.07       0  4848.4   0.035       0
  4997.1   0.035       0  5001.1   0.035       0
Bank Sta=4997.1,5001.1
Exp/Cntr=0.3,0.1

Type RM Length L Ch R = 1,1435,447,447,447
BEGIN DESCRIPTION:
CIBOLO TRIBUTARY 14 3.0
END DESCRIPTION:
XS GIS Cut Line= 3
      2336575.00     13772325.00      2336375.00     13772475.00
      2336225.02     13772724.96
#Sta/Elev= 30
  4750.0  503.47  4757.3  503.21  4771.9  501.87  4813.5  499.27  4836.5  497.39
  4842.7  497.42  4850.0  496.29  4871.9  494.56  4886.5  494.17  4913.5  492.01
  4921.9  491.68  4928.1  490.83  4942.7  490.07  4963.5  487.74  4971.9  487.59
  4984.5  486.39  4984.7  485.89  4988.2  485.89  4988.5  486.39  4996.9  487.03
  5007.8  487.30  5035.0  489.60  5073.1  491.49  5103.0  492.78  5130.2  495.42
  5174.9  498.86  5185.9  500.11  5225.5  502.71  5277.9  507.53  5291.5  508.01
#Mann=5,-1,0
  4750.0    0.12       0  4984.5    0.05       0  4988.5    0.12       0
  5073.1    0.07       0  5185.9   0.035       0
Bank Sta=4984.5,4988.5
Exp/Cntr=0.3,0.1

Type RM Length L Ch R = 1,988,466,466,466
BEGIN DESCRIPTION:
CIBOLO TRIBUTARY 14 2.0
END DESCRIPTION:
XS GIS Cut Line= 3
      2336424.96     13772025.01      2336125.00     13772125.00
      2335925.02     13772424.96
#Sta/Elev= 30
  4678.6  497.93  4689.1  497.31  4696.8  497.58  4762.9  494.45  4805.1  489.41
  4847.2  486.88  4857.8  487.58  4878.8  487.16  4889.4  489.46  4910.5  492.59
  4918.1  490.53  4931.5  487.21  4942.1  485.40  4952.6  484.42  5009.8  484.38
  5017.3  484.35  5023.3  483.71  5036.4  483.27  5036.6  482.77  5040.1  482.77
  5040.4  483.27  5044.4  484.60  5059.4  484.58  5167.6  489.20  5193.6  490.75
  5211.1  492.67  5239.7  494.65  5254.7  495.20  5296.8  498.57  5355.3  501.19
#Mann=7,-1,0
  4678.6    0.07       0  4696.8    0.12       0  4918.1     0.1       0
  5009.8    0.12       0  5036.4    0.05       0  5040.4    0.12       0
  5193.6    0.07       0
Bank Sta=5036.4,5040.4
Exp/Cntr=0.3,0.1

Type RM Length L Ch R = 1,522,333,333,333
BEGIN DESCRIPTION:
CIBOLO TRIBUTARY 14 1.0
END DESCRIPTION:
XS GIS Cut Line= 3
      2336225.00     13771575.00      2335925.00     13771725.00
      2335774.99     13772175.04
#Sta/Elev= 30
  4657.2  493.72  4665.6  493.18  4671.2  493.41  4687.9  491.94  4724.3  490.54
  4755.0  487.13  4760.3  488.37  4783.0  488.16  4822.1  486.57  4836.1  485.33
  4850.1  485.41  4894.8  483.65  4983.7  481.37  5001.2  480.45  5001.4  479.95
  5004.9  479.95  5005.2  480.45  5013.7  481.32  5045.3  481.02  5071.7  481.50
  5087.5  482.44  5109.1  481.56  5140.2  482.19  5192.9  482.00  5235.1  482.70
  5308.8  484.93  5329.9  486.63  5435.3  490.29  5445.9  491.15  5467.0  491.41
#Mann=6,-1,0
  4657.2    0.07       0  4760.3    0.12       0  4983.7     0.1       0
  5001.2    0.05       0  5005.2     0.1       0  5109.1    0.12       0
Bank Sta=5001.2,5005.2
Exp/Cntr=0.3,0.1

Type RM Length L Ch R = 1,189,0,0,0
BEGIN DESCRIPTION:
X18455
END DESCRIPTION:
XS GIS Cut Line= 4
      2336250.90     13771304.97      2335740.53     13771409.13
      2335643.30     13771815.38      2335747.48     13772186.93
#Sta/Elev= 30
  4411.6  493.54  4417.6  492.41  4468.7  490.23  4523.3  486.92  4535.9  486.34
  4541.0  487.06  4550.3  486.17  4626.1  484.06  4783.4  479.40  4788.5  479.88
  4833.9  478.83  4856.5  479.06  4927.8  477.51  4948.8  477.29  4969.4  478.18
  4976.1  478.05  4979.3  477.00  4979.5  476.50  4983.3  477.00  4989.9  477.81
  5000.2  477.38  5060.2  478.82  5133.9  478.63  5263.0  480.40  5317.6  481.52
  5322.8  481.08  5448.8  485.17  5505.6  486.22  5522.2  487.42  5736.1  490.36
#Mann=7,-1,0
  4411.6   0.035       0  4523.3    0.07       0  4626.1    0.12       0
  4927.8     0.1       0  4979.3    0.05       0  4983.3     0.1       0
  5263.0    0.12       0
Bank Sta=4979.3,4983.3
Exp/Cntr=0.3,0.1

Chan Stop Cuts=-1