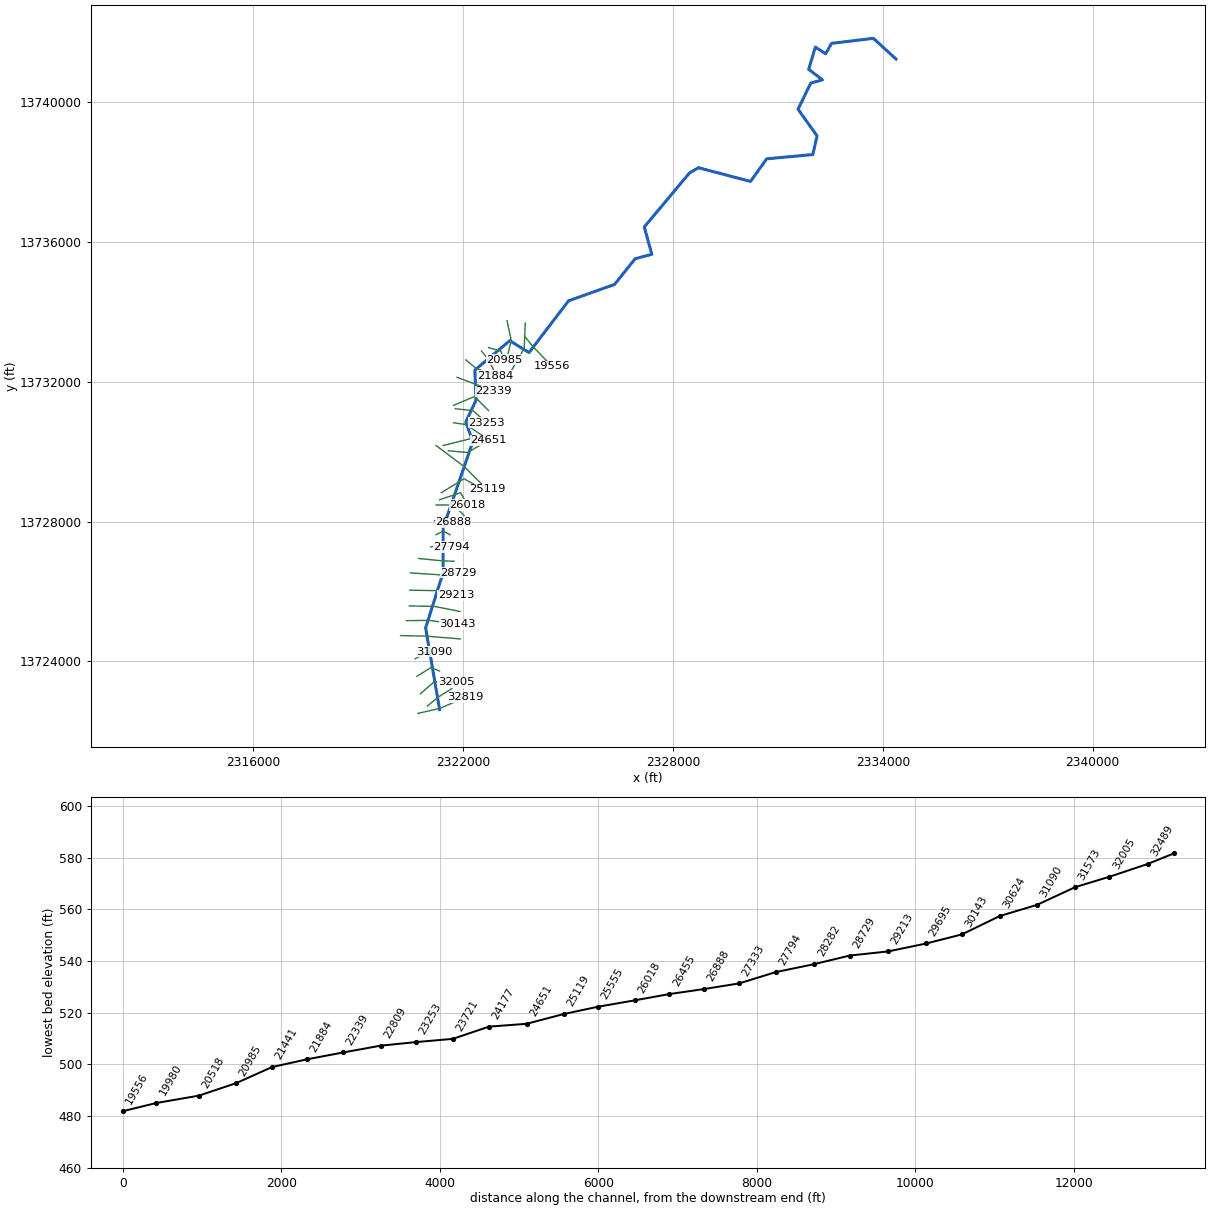
--- CORDELL CREEK.prj (project) ---

Proj Title=CORDELL CREEK Base Level Engineering
Current Plan=p01
Default Exp/Contr=0.3,0.1
English Units
Geom File=g01
Flow File=f01
Plan File=p01
Y Axis Title=Elevation
X Axis Title(PF)=Main Channel Distance
X Axis Title(XS)=Station
BEGIN DESCRIPTION:
CORDELL CREEK
END DESCRIPTION:
DSS Export Rating Curves= 0
DSS Export Rating Curve Sorted= 0
DSS Export Volume Flow Curves= 0
DXF OffsetX= 0
DXF OffsetY= 0
DXF ScaleX= 1
DXF ScaleY= 10

--- CORDELL CREEK.p01 (plan) ---

Plan Title=Multiple Run
Short Identifier=Multiple
Geom File=g01
Flow File=f01
Subcritical Flow
K Sum by GR= 0
Std Step Tol= 0.01
Critical Tol= 0.01
Num of Std Step Trials= 20
Max Error Tol= 0.3
Flow Tol Ratio= 0.001
Split Flow NTrial= 30
Split Flow Tol= 0.02
Split Flow Ratio= 0.02
Log Output Level= 0
Friction Slope Method= 1
Unsteady Friction Slope Method= 2
Unsteady Bridges Friction Slope Method= 1
Parabolic Critical Depth
Global Vel Dist=  1 , 1 , 1
Global Log Level= 0
CheckData=True
Encroach Param= -1, 0, 0, 0
BEGIN DESCRIPTION:
Multiple Run
END DESCRIPTION:

--- CORDELL CREEK.f01 (steady flow) ---

Flow Title=Multiple
Number of Profiles=7
Profile Names=10-year,25-year,50-year,1pct_min,100-year,1pct_plu,500-year
River Rch & RM= CORDELL CREEK,Reach-1,32819
     829    1378    1888    1254    2502    4992    4353
River Rch & RM= CORDELL CREEK,Reach-1,32489
    1277    2165    3008    2021    4033    8047    7189
River Rch & RM= CORDELL CREEK,Reach-1,24177
    1465    2494    3472    2336    4662    9301    8333
River Rch & RM= CORDELL CREEK,Reach-1,19556
    2117    3658    5144    3492    6967   13902   12680
River Rch & RM= CORDELL CREEK,Reach-1,12951
    2362    4095    5770    3922    7826   15615   14285
River Rch & RM= CORDELL CREEK,Reach-1,7956
    2510    4351    6133    4168    8317   16595   15176
Boundary for River Rch & Prof#=CORDELL CREEK,Reach-1,1
Up Type=0
Dn Type=3
Dn Slope=0.005
Boundary for River Rch & Prof#=CORDELL CREEK,Reach-1,2
Up Type=0
Dn Type=3
Dn Slope=0.005
Boundary for River Rch & Prof#=CORDELL CREEK,Reach-1,3
Up Type=0
Dn Type=3
Dn Slope=0.005
Boundary for River Rch & Prof#=CORDELL CREEK,Reach-1,4
Up Type=0
Dn Type=3
Dn Slope=0.005
Boundary for River Rch & Prof#=CORDELL CREEK,Reach-1,5
Up Type=0
Dn Type=3
Dn Slope=0.005
Boundary for River Rch & Prof#=CORDELL CREEK,Reach-1,6
Up Type=0
Dn Type=3
Dn Slope=0.005
Boundary for River Rch & Prof#=CORDELL CREEK,Reach-1,7
Up Type=0
Dn Type=3
Dn Slope=0.005

--- CORDELL CREEK.g01 (geometry) ---

Geom Title=Existing Conditions
Program Version=4.10

River Reach=CORDELL CREEK   ,Reach-1
Reach XY= 30
        2321325.       13722625.      2320925.51     13724959.79
      2321423.78     13726535.51      2321427.24     13727819.07
      2322274.28     13730285.71      2322074.68     13730850.11
      2322366.92      13731471.7      2322333.02     13732331.34
       2323330.9     13733172.77      2323881.07     13732832.36
      2325011.43     13734311.53      2326327.29     13734780.84
       2326915.2     13735514.52      2327391.71     13735641.63
      2327177.99     13736423.59      2328468.66     13737966.98
      2328724.92      13738117.7      2330214.74     13737725.98
      2330676.28     13738371.48      2331995.69     13738494.62
      2332117.33     13739028.66      2331574.28     13739790.06
      2331938.62     13740538.22      2332272.95     13740630.44
      2331876.98     13740930.62      2332068.95     13741567.54
      2332364.51     13741375.48      2332530.65     13741673.03
      2333728.42     13741817.21        2334375.       13741225.

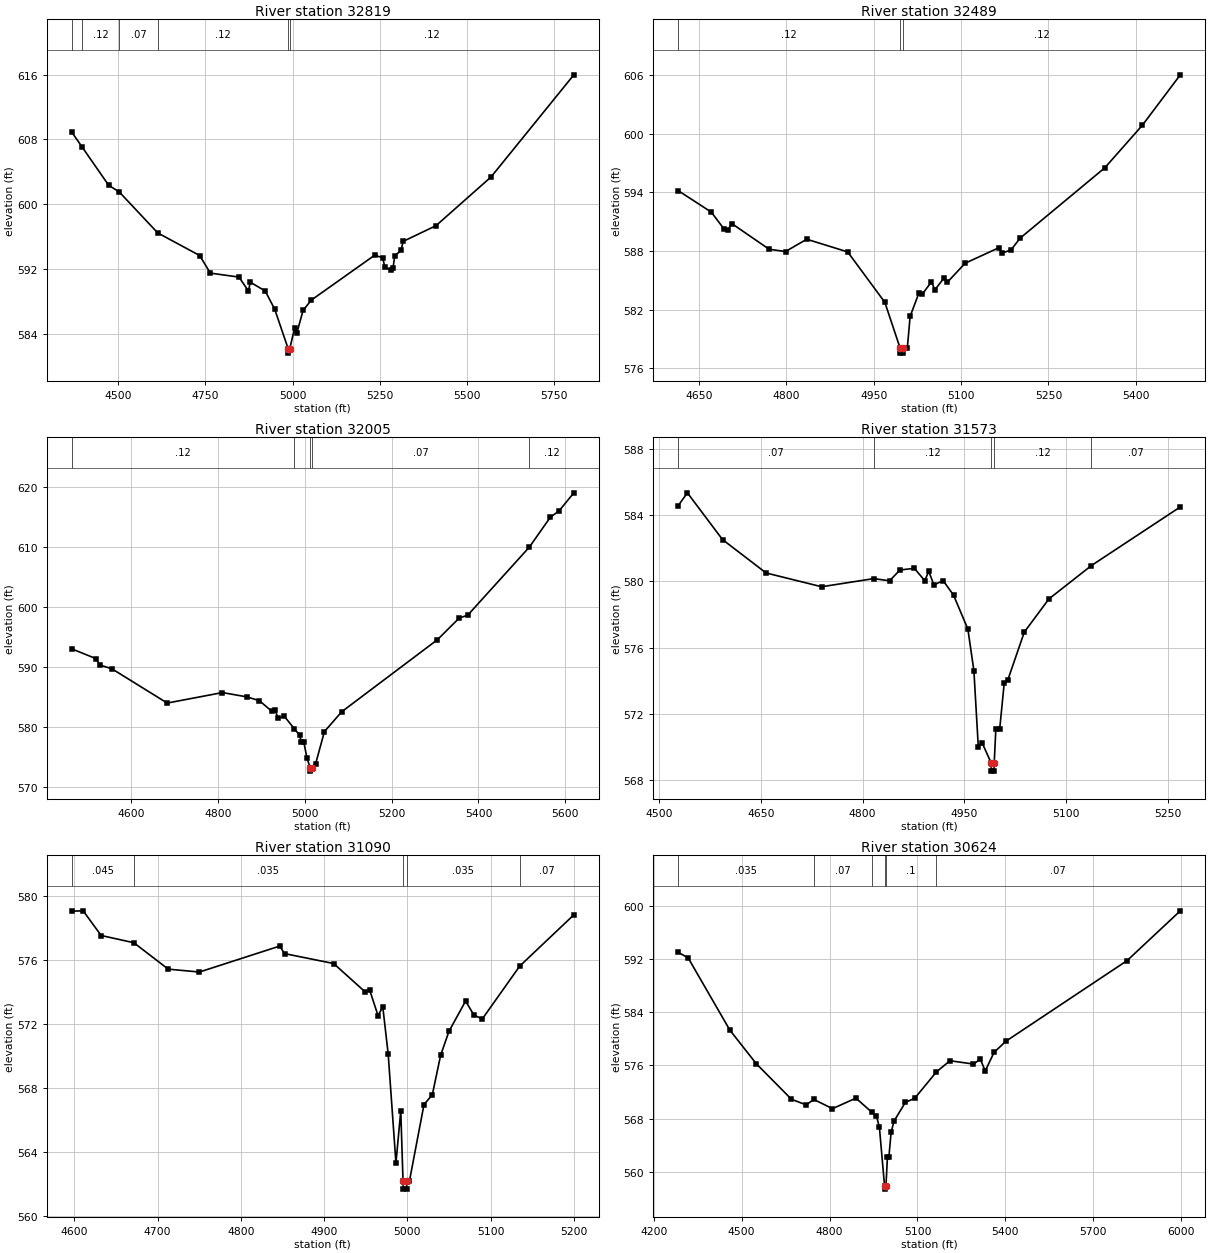
Type RM Length L Ch R = 1 ,32819   ,330,330,330
BEGIN DESCRIPTION:
X18536
END DESCRIPTION:
XS GIS Cut Line= 3
      2320707.08     13722516.13      2321331.52     13722659.45
      2322068.48     13722973.34
#Sta/Elev= 30
    4366  608.89  4396.1  607.03  4472.1  602.33    4502  601.53  4612.8  596.46
  4733.2  593.67    4764   591.5  4846.1  591.01  4873.4  589.29  4878.5  590.38
  4921.4   589.3  4948.7  587.05  4987.7  582.13  4987.9  581.63  4991.8  582.13
  5005.9  584.74    5012  584.06  5030.2   586.9  5053.8  588.17  5235.5   593.7
  5259.1   593.4  5264.6  592.27  5282.2  591.83  5288.2  592.08  5293.6  593.64
  5311.8   594.3  5317.3  595.41  5411.8  597.35  5569.9  603.36  5807.7  615.96
#Mann= 6 ,-1 , 0
    4366    .045       0  4396.1     .12       0    4502     .07       0
  4612.8     .12       0  4987.7     .05       0  4991.8     .12       0
Bank Sta=4987.7,4991.8
XS Rating Curve= 0 ,0
Exp/Cntr=0.3,0.1

Type RM Length L Ch R = 1 ,32489   ,484,484,484
BEGIN DESCRIPTION:
CORDELL CREEK 70.0
END DESCRIPTION:
XS GIS Cut Line= 3
      2320974.97     13722724.98        2321275.       13722975.
      2321674.96     13723224.97
#Sta/Elev= 30
  4614.3  594.18    4671  591.99  4692.4   590.3  4699.6  590.14  4706.1  590.82
  4770.5  588.18  4798.5  587.95    4835  589.21  4905.3  587.91  4969.1  582.75
  4995.4  578.05  4995.7  577.55  4999.6  577.55  4999.9  578.05  5007.8  578.12
  5012.5  581.31  5027.8  583.73  5033.7  583.61  5049.1  584.84    5055  584.03
  5070.3  585.21  5076.2  584.79  5106.9  586.75  5164.6  588.33  5170.5  587.79
  5185.9  588.12  5201.2  589.31  5346.8  596.52  5411.1  600.86  5476.5  606.04
#Mann= 3 ,-1 , 0
  4614.3     .12       0  4995.4     .05       0  4999.9     .12       0
Bank Sta=4995.4,4999.9
XS Rating Curve= 0 ,0
Exp/Cntr=0.3,0.1

Type RM Length L Ch R = 1 ,32005   ,432,432,432
BEGIN DESCRIPTION:
CORDELL CREEK 69.0
END DESCRIPTION:
XS GIS Cut Line= 3
      2320775.03     13723075.02        2321175.       13723425.
      2321798.96     13723406.69
#Sta/Elev= 30
  4463.8  592.97  4520.2  591.32  4527.8  590.29  4556.3  589.64  4683.5  583.93
  4810.7  585.68  4867.6  584.95  4895.6  584.33  4924.6  582.54  4931.2  582.82
  4938.8  581.42    4953  581.73  4976.2  579.63  4988.2  578.59    4992  577.47
  4997.8  577.47  5005.3  574.71    5013  573.08  5013.3  572.58  5017.6  573.08
  5025.3  573.85  5045.3  579.17  5085.3  582.49  5305.4  594.49  5355.4  598.09
  5375.4   598.6  5517.1  609.94  5565.5  614.93  5585.5  615.98  5619.5  618.99
#Mann= 5 ,-1 , 0
  4463.8     .12       0  4976.2     .07       0    5013     .05       0
  5017.6     .07       0  5517.1     .12       0
Bank Sta=5013,5017.6
XS Rating Curve= 0 ,0
Exp/Cntr=0.3,0.1

Type RM Length L Ch R = 1 ,31573   ,483,483,483
BEGIN DESCRIPTION:
CORDELL CREEK 68.0
END DESCRIPTION:
XS GIS Cut Line= 3
      2320675.02     13723575.01        2321075.       13723825.
      2321324.97     13723725.01
#Sta/Elev= 30
  4527.9  584.56  4541.4  585.33  4593.3  582.51  4657.6   580.5  4739.5  579.67
  4816.3  580.16  4839.8  580.03  4855.1  580.68  4876.3  580.78  4891.7  580.04
  4897.6   580.6  4905.2  579.78  4918.8  580.04  4934.1  579.17  4955.3  577.12
  4964.2  574.61  4970.7  570.02  4976.6  570.24  4989.6  569.06  4989.9  568.56
  4993.9  568.56  4994.2  569.06  4996.6  571.11  5002.3  571.11    5009  573.89
  5014.4  574.07  5038.6  576.94    5075  578.94  5137.7  580.95  5268.8  584.48
#Mann= 5 ,-1 , 0
  4527.9     .07       0  4816.3     .12       0  4989.6     .05       0
  4994.2     .12       0  5137.7     .07       0
Bank Sta=4989.6,4994.2
XS Rating Curve= 0 ,0
Exp/Cntr=0.3,0.1

Type RM Length L Ch R = 1 ,31090   ,466,466,466
BEGIN DESCRIPTION:
CORDELL CREEK 67.0
END DESCRIPTION:
XS GIS Cut Line= 3
      2320624.99     13724074.99        2320975.       13724275.
      2321174.98       13724275.
#Sta/Elev= 30
  4596.9  579.03  4610.6  579.05  4632.2  577.51  4671.4  577.06  4712.8  575.41
  4750.2  575.23  4846.7  576.85  4852.5  576.38  4911.5  575.76  4948.9  574.01
  4954.7  574.11  4964.8  572.51  4970.5  573.06    4977   570.1  4986.3  563.31
  4992.1  566.57  4994.8  562.18  4995.1  561.68  4999.1  561.68  4999.4  562.18
  5002.5  562.18    5020  566.96    5030  567.57    5040  570.04    5050  571.53
    5070  573.42    5080  572.54    5090   572.3    5135   575.6    5200   578.8
#Mann= 5 ,-1 , 0
  4596.9    .045       0  4671.4    .035       0  4994.8     .05       0
  4999.4    .035       0    5135     .07       0
Bank Sta=4994.8,4999.4
XS Rating Curve= 0 ,0
Exp/Cntr=0.3,0.1

Type RM Length L Ch R = 1 ,30624   ,481,481,481
BEGIN DESCRIPTION:
CORDELL CREEK 66.0
END DESCRIPTION:
XS GIS Cut Line= 3
      2320208.94      13724740.8        2320925.       13724725.
      2321918.37     13724645.27
#Sta/Elev= 30
  4283.8  592.98  4317.5  592.16  4459.9   581.3  4549.9  576.26    4670  570.91
    4720  570.07  4746.5  570.88    4810   569.5    4890  571.08  4943.5  568.99
    4960   568.4    4970  566.71  4987.6  557.91  4987.9  557.41  4992.5  557.91
  4997.5  562.29  5002.5  562.29  5010.1  565.98  5020.1  567.64  5058.9  570.46
  5090.3  571.04  5164.2     575  5210.7   576.7    5291   576.2  5314.3  576.93
  5331.1  575.17  5361.2  577.95  5401.3  579.62    5815  591.74  5996.6  599.22
#Mann= 6 ,-1 , 0
  4283.8    .035       0  4746.5     .07       0  4943.5      .1       0
  4987.6     .05       0  4992.5      .1       0  5164.2     .07       0
Bank Sta=4987.6,4992.5
XS Rating Curve= 0 ,0
Exp/Cntr=0.3,0.1

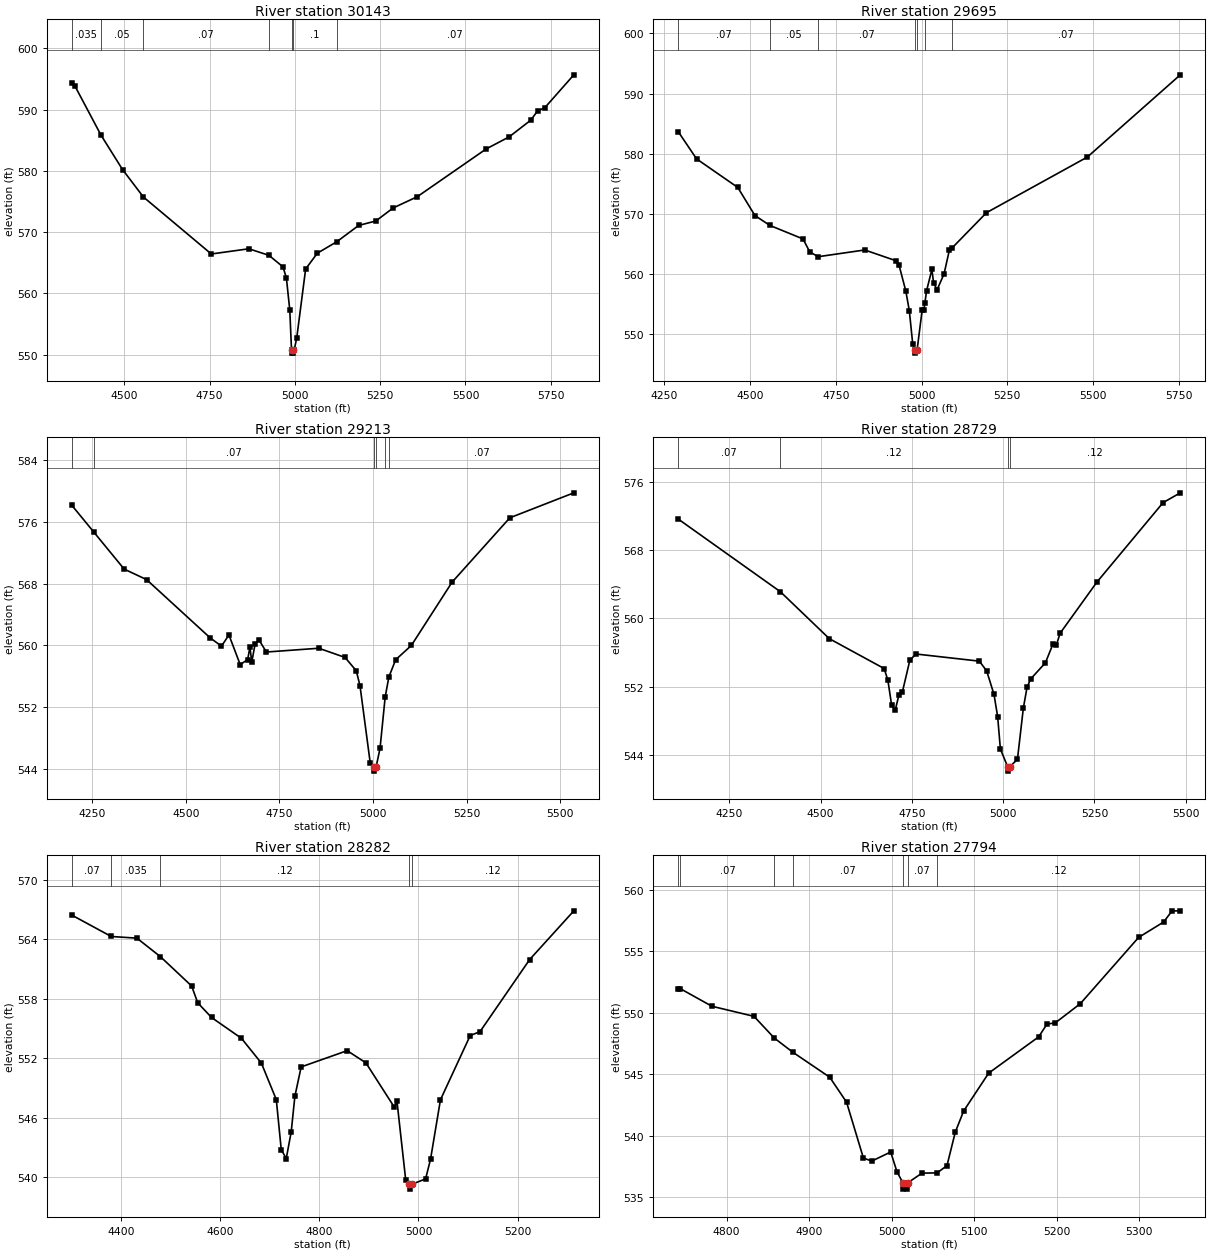
Type RM Length L Ch R = 1 ,30143   ,448,448,448
BEGIN DESCRIPTION:
CORDELL CREEK 65.0
END DESCRIPTION:
XS GIS Cut Line= 3
      2320376.12     13725167.31        2321025.       13725175.
      2321839.87     13725064.95
#Sta/Elev= 30
  4346.3   594.3  4355.2  593.89  4431.9  585.84  4495.2  580.21  4556.2  575.74
  4755.2  566.44  4865.2  567.29    4924  566.22  4965.2  564.34  4975.2  562.53
  4985.2  557.24  4990.2  550.76  4990.6  550.26  4994.9  550.26  4995.3  550.76
  4997.8  550.76  5005.3  552.65  5031.6  563.99  5065.9  566.57  5122.6  568.43
    5187   571.1  5237.4  571.83  5287.9  573.95  5358.5  575.78  5560.5  583.58
  5628.1  585.56  5691.5  588.29  5711.7  589.83  5731.9  590.28  5817.5  595.68
#Mann= 7 ,-1 , 0
  4346.3    .035       0  4431.9     .05       0  4556.2     .07       0
    4924      .1       0  4990.2     .05       0  4995.3      .1       0
  5122.6     .07       0
Bank Sta=4990.2,4995.3
XS Rating Curve= 0 ,0
Exp/Cntr=0.3,0.1

Type RM Length L Ch R = 1 ,29695   ,482,482,482
BEGIN DESCRIPTION:
CORDELL CREEK 64.0
END DESCRIPTION:
XS GIS Cut Line= 3
      2320461.47     13725586.99        2321175.       13725575.
      2321910.75      13725430.2
#Sta/Elev= 30
  4290.9  583.64  4344.4  579.11  4464.5  574.35  4514.5  569.67    4558  568.03
  4654.5  565.78  4674.5   563.6    4699  562.82  4834.5  563.94  4924.5  562.17
  4934.5  561.42  4954.5  557.04  4964.5  553.82  4974.5  548.23    4982  547.26
  4982.4  546.76  4987.1  547.26    5002  553.97  5007.1  553.97    5010  555.17
  5014.7  557.12  5030.2  560.69  5035.3  558.46  5045.3   557.3  5065.7  559.95
  5081.6  564.01  5088.5  564.24  5189.4  570.15  5483.5  579.42  5754.4  593.11
#Mann= 7 ,-1 , 0
  4290.9     .07       0    4558     .05       0    4699     .07       0
    4982     .05       0  4987.1     .07       0    5010     .12       0
  5088.5     .07       0
Bank Sta=4982,4987.1
XS Rating Curve= 0 ,0
Exp/Cntr=0.3,0.1

Type RM Length L Ch R = 1 ,29213   ,484,484,484
BEGIN DESCRIPTION:
CORDELL CREEK 63.0
END DESCRIPTION:
XS GIS Cut Line= 3
      2320475.13     13726037.38        2321275.       13726025.
      2321801.18     13725897.78
#Sta/Elev= 30
  4195.4  578.17  4254.9  574.65  4335.3  569.89  4395.3  568.52  4565.3  560.96
  4595.3  559.89  4615.3  561.34  4645.3   557.5  4665.3  558.15  4671.3  559.76
  4676.3  557.84  4685.3   560.2  4695.3  560.71  4715.3  559.13  4855.3  559.62
  4925.4  558.43  4955.4   556.7  4965.4  554.76  4992.9  544.68  5003.1  544.18
  5003.5  543.68  5008.2  544.18  5018.9  546.62  5032.7  553.31  5042.6   555.9
  5060.7  558.13  5102.6  559.98  5211.4  568.19  5365.7  576.54  5536.7  579.78
#Mann= 6 ,-1 , 0
  4195.4     .12       0  4254.9     .07       0  5003.1     .05       0
  5008.2     .07       0  5032.7     .12       0  5042.6     .07       0
Bank Sta=5003.1,5008.2
XS Rating Curve= 0 ,0
Exp/Cntr=0.3,0.1

Type RM Length L Ch R = 1 ,28729   ,447,447,447
BEGIN DESCRIPTION:
CORDELL CREEK 62.0
END DESCRIPTION:
XS GIS Cut Line= 3
      2320492.15     13726532.13        2321375.       13726475.
      2321861.88     13726531.91
#Sta/Elev= 30
  4110.4  571.67  4390.1  563.14  4524.1  557.63  4674.4  554.12  4684.5  552.74
  4694.5   549.9  4704.5  549.22  4714.5  550.98  4724.5  551.42  4744.6  555.09
  4761.2  555.83    4935  554.99    4955  553.85  4975.1  551.08  4985.1  548.47
  4992.6  544.67  5012.7  542.58    5013  542.08  5017.8  542.58  5039.3  543.46
  5055.5  549.49  5065.6  551.92  5075.6   552.9  5115.9   554.8  5136.1  556.95
  5146.1  556.92  5156.2  558.27  5256.9  564.27  5438.1   573.6  5485.3  574.75
#Mann= 4 ,-1 , 0
  4110.4     .07       0  4390.1     .12       0  5012.7     .05       0
  5017.8     .12       0
Bank Sta=5012.7,5017.8
XS Rating Curve= 0 ,0
Exp/Cntr=0.3,0.1

Type RM Length L Ch R = 1 ,28282   ,488,488,488
BEGIN DESCRIPTION:
CORDELL CREEK 61.0
END DESCRIPTION:
XS GIS Cut Line= 3
      2320724.19     13726944.99        2321425.       13726875.
      2321734.19     13726866.51
#Sta/Elev= 30
  4300.1  566.44  4379.8  564.28  4431.6  564.11  4479.1  562.24  4542.1  559.28
  4554.4  557.58  4582.3   556.1  4642.6     554  4682.8   551.5    4713  547.81
    4723  542.76  4733.1  541.86  4743.1  544.55  4750.5  548.14  4763.2  551.11
  4856.1  552.75  4893.9  551.52  4951.6  547.02  4956.6  547.66  4974.2  539.72
  4981.6  539.27    4982  538.77    4987  539.27  5014.4   539.8  5024.4  541.79
  5044.4  547.79  5104.4  554.27  5124.4  554.68  5224.5  561.95  5313.7  566.87
#Mann= 5 ,-1 , 0
  4300.1     .07       0  4379.8    .035       0  4479.1     .12       0
  4981.6     .05       0    4987     .12       0
Bank Sta=4981.6,4987
XS Rating Curve= 0 ,0
Exp/Cntr=0.3,0.1

Type RM Length L Ch R = 1 ,27794   ,461,461,461
BEGIN DESCRIPTION:
CORDELL CREEK 60.0
END DESCRIPTION:
XS GIS Cut Line= 3
      2321074.97     13727274.99        2321325.       13727325.
      2321674.97       13727275.
#Sta/Elev= 30
  4741.3  551.96  4743.8  551.96  4782.1  550.53  4833.1  549.71  4857.8  547.94
    4880   546.8  4924.9  544.76  4945.3  542.73  4965.7  538.19  4975.9  537.94
  4998.8  538.68  5006.4  537.07  5013.7  536.16  5014.2  535.66  5018.8  535.66
  5019.2  536.16  5036.7  536.96    5055  536.98    5067  537.57  5077.1   540.3
  5087.2  542.01  5117.5  545.09  5178.1  548.04  5188.2  549.08  5198.3  549.18
  5228.6  550.74  5299.3  556.13  5329.6  557.38  5339.7  558.28  5349.8  558.29
#Mann= 7 ,-1 , 0
  4741.3    .035       0  4743.8     .07       0  4857.8     .12       0
    4880     .07       0  5013.7     .05       0  5019.2     .07       0
    5055     .12       0
Bank Sta=5013.7,5019.2
XS Rating Curve= 0 ,0
Exp/Cntr=0.3,0.1

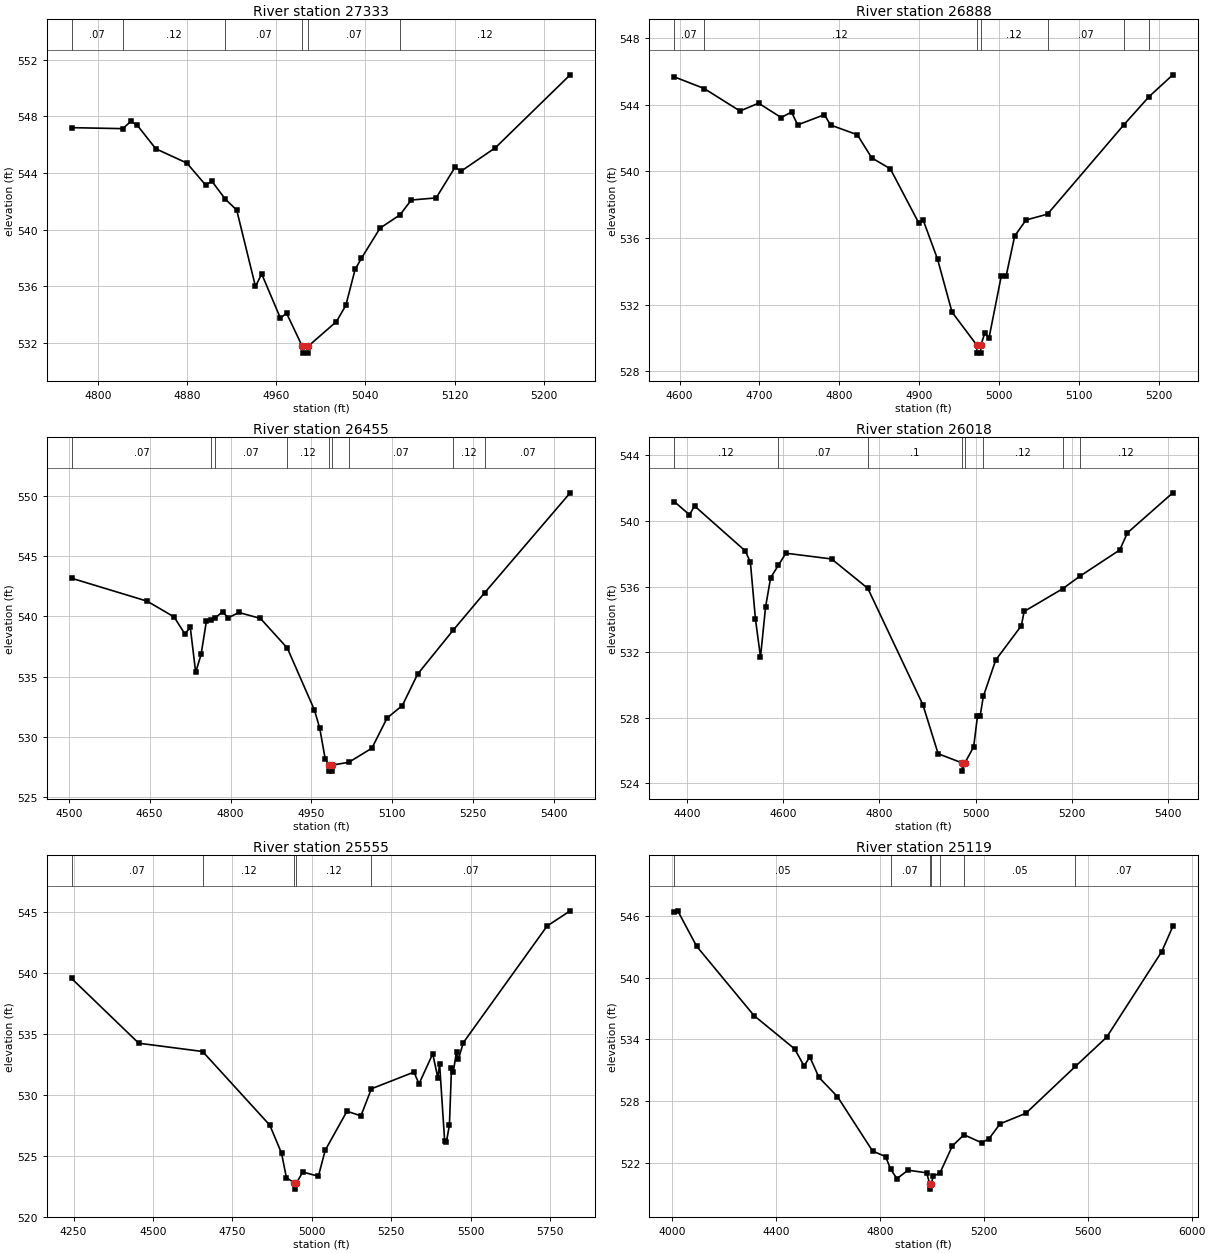
Type RM Length L Ch R = 1 ,27333   ,445,445,445
BEGIN DESCRIPTION:
CORDELL CREEK 59.0
END DESCRIPTION:
XS GIS Cut Line= 3
      2321225.01     13727625.01        2321425.       13727725.
        2321625.       13727625.
#Sta/Elev= 30
  4776.5  547.21  4822.4  547.14  4829.6  547.65  4835.2   547.4    4852  545.72
  4879.9  544.71  4896.7  543.16  4902.3  543.43  4914.4  542.16  4924.6  541.39
  4941.4     536    4947  536.88  4963.8  533.76  4969.3  534.11  4983.3  531.79
  4983.8  531.29  4988.5  531.29  4988.9  531.79  5014.1  533.52  5022.5  534.67
  5030.8   537.2  5036.4  537.98  5053.2  540.12    5071  541.05  5081.2   542.1
  5103.5  542.25  5120.3   544.4  5125.9  544.14  5156.6  545.79  5223.7  550.94
#Mann= 6 ,-1 , 0
  4776.5     .07       0  4822.4     .12       0  4914.4     .07       0
  4983.3     .05       0  4988.9     .07       0    5071     .12       0
Bank Sta=4983.3,4988.9
XS Rating Curve= 0 ,0
Exp/Cntr=0.3,0.1

Type RM Length L Ch R = 1 ,26888   ,433,433,433
BEGIN DESCRIPTION:
CORDELL CREEK 58.0
END DESCRIPTION:
XS GIS Cut Line= 3
      2321175.03     13728025.01        2321575.       13728125.
      2321724.99     13727975.01
#Sta/Elev= 30
  4593.2  545.66  4630.7  544.96  4675.6  543.61  4698.8  544.08  4727.2  543.22
  4740.1  543.55  4747.8  542.78  4781.3  543.39    4789  542.77  4822.5  542.19
  4840.6   540.8  4863.8  540.15  4899.8  536.87    4905  537.07    4923  534.73
  4941.1  531.56  4971.8   529.6  4972.2   529.1  4976.9   529.1  4977.4   529.6
  4982.3  530.33  4987.4     530  5002.9  533.75    5009  533.75  5019.6  536.12
  5033.8  537.08  5060.7  537.43  5156.6   542.8  5187.8  544.47  5217.6  545.78
#Mann= 7 ,-1 , 0
  4593.2     .07       0  4630.7     .12       0  4971.8     .05       0
  4977.4     .12       0  5060.7     .07       0  5156.6     .12       0
  5187.8     .07       0
Bank Sta=4971.8,4977.4
XS Rating Curve= 0 ,0
Exp/Cntr=0.3,0.1

Type RM Length L Ch R = 1 ,26455   ,437,437,437
BEGIN DESCRIPTION:
CORDELL CREEK 57.0
END DESCRIPTION:
XS GIS Cut Line= 3
      2321225.02       13728475.        2321725.       13728475.
      2322024.97     13728175.03
#Sta/Elev= 30
  4505.3  543.17  4645.3  541.27  4695.3  539.96  4715.3  538.55  4725.3   539.1
  4735.3  535.37  4745.3  536.85  4755.3  539.64  4764.3  539.71  4770.5  539.84
  4785.3   540.4  4795.3  539.88  4815.3  540.33  4855.3  539.84  4905.2  537.38
  4955.3  532.26  4965.3  530.73  4975.3  528.22  4982.4  527.68  4982.9  527.18
  4987.6  527.18  4988.1  527.68    5019  527.91  5061.9  529.08  5090.1  531.58
  5118.4  532.62  5146.7  535.22  5212.9  538.88  5270.9  541.96  5429.5  550.25
#Mann= 9 ,-1 , 0
  4505.3     .07       0  4764.3     .12       0  4770.5     .07       0
  4905.2     .12       0  4982.4     .05       0  4988.1     .12       0
    5019     .07       0  5212.9     .12       0  5270.9     .07       0
Bank Sta=4982.4,4988.1
XS Rating Curve= 0 ,0
Exp/Cntr=0.3,0.1

Type RM Length L Ch R = 1 ,26018   ,463,463,463
BEGIN DESCRIPTION:
CORDELL CREEK 56.0
END DESCRIPTION:
XS GIS Cut Line= 3
      2321324.96     13728624.99        2321925.       13728825.
      2322124.99     13728475.01
#Sta/Elev= 30
  4373.8  541.18  4405.5  540.37    4416  540.91  4521.4  538.17    4532  537.48
  4542.5  534.02    4553   531.7  4563.6  534.76  4574.1  536.54  4590.3   537.3
  4605.7  538.03  4700.6  537.68  4775.9  535.89  4890.4  528.79    4922  525.81
  4971.8  525.25  4972.3  524.75  4977.5  525.25  4995.8  526.23  5003.7   528.1
  5009.2   528.1  5015.8   529.3  5041.6  531.52  5094.8  533.61  5100.6  534.48
  5180.4  535.86    5216  536.62  5299.3  538.23  5315.1  539.27  5409.4  541.71
#Mann= 8 ,-1 , 0
  4373.8     .12       0  4590.3     .07       0  4775.9      .1       0
  4971.8     .05       0  4977.5      .1       0  5015.8     .12       0
  5180.4     .07       0    5216     .12       0
Bank Sta=4971.8,4977.5
XS Rating Curve= 0 ,0
Exp/Cntr=0.3,0.1

Type RM Length L Ch R = 1 ,25555   ,436,436,436
BEGIN DESCRIPTION:
CORDELL CREEK 55.0
END DESCRIPTION:
XS GIS Cut Line= 3
      2321375.04     13728825.03        2322025.       13729225.
      2322725.01       13728825.
#Sta/Elev= 30
  4243.9  539.56  4455.2  534.25  4656.3  533.57    4868  527.52  4904.7  525.23
  4920.1  523.22  4945.5  522.78  4945.9  522.28  4951.3  522.78  4971.8  523.68
  5020.7  523.34  5042.3  525.47  5110.7  528.67  5154.6  528.29  5187.5  530.51
  5321.6  531.88  5337.5  530.92  5380.7  533.38  5396.5  531.43  5402.3  532.53
  5418.1  526.25  5423.9  526.18  5433.2  527.54  5439.7   532.2  5445.5   531.9
  5455.5  533.57  5461.3  532.93  5477.1   534.3  5740.6  543.86  5813.3  545.11
#Mann= 5 ,-1 , 0
  4243.9     .07       0  4656.3     .12       0  4945.5     .05       0
  4951.3     .12       0  5187.5     .07       0
Bank Sta=4945.5,4951.3
XS Rating Curve= 0 ,0
Exp/Cntr=0.3,0.1

Type RM Length L Ch R = 1 ,25119   ,468,468,468
BEGIN DESCRIPTION:
CORDELL CREEK 54.0
END DESCRIPTION:
XS GIS Cut Line= 3
      2321225.03     13730174.98        2322025.       13729575.
        2322675.       13728925.
#Sta/Elev= 30
  4008.2  546.36  4021.7  546.52  4094.6  543.07  4315.5  536.32  4471.7  533.08
  4508.2  531.42    4530   532.3  4565.5   530.3  4636.3  528.44  4771.7  523.14
  4821.7   522.6  4841.6  521.36  4865.5  520.45  4908.2  521.27    4980  521.02
  4991.6  519.93  4992.1  519.43  4997.6  519.93    5005  520.69    5031  520.99
  5078.9  523.64  5123.8  524.72    5192  523.94  5220.3  524.35  5262.7  525.79
  5361.7  526.81  5552.2  531.37  5672.8  534.22    5885  542.56  5927.4     545
#Mann= 7 ,-1 , 0
  4008.2     .05       0  4841.6     .07       0  4991.6     .05       0
  4997.6     .07       0    5031      .1       0  5123.8     .05       0
  5552.2     .07       0
Bank Sta=4991.6,4997.6
XS Rating Curve= 0 ,0
Exp/Cntr=0.3,0.1

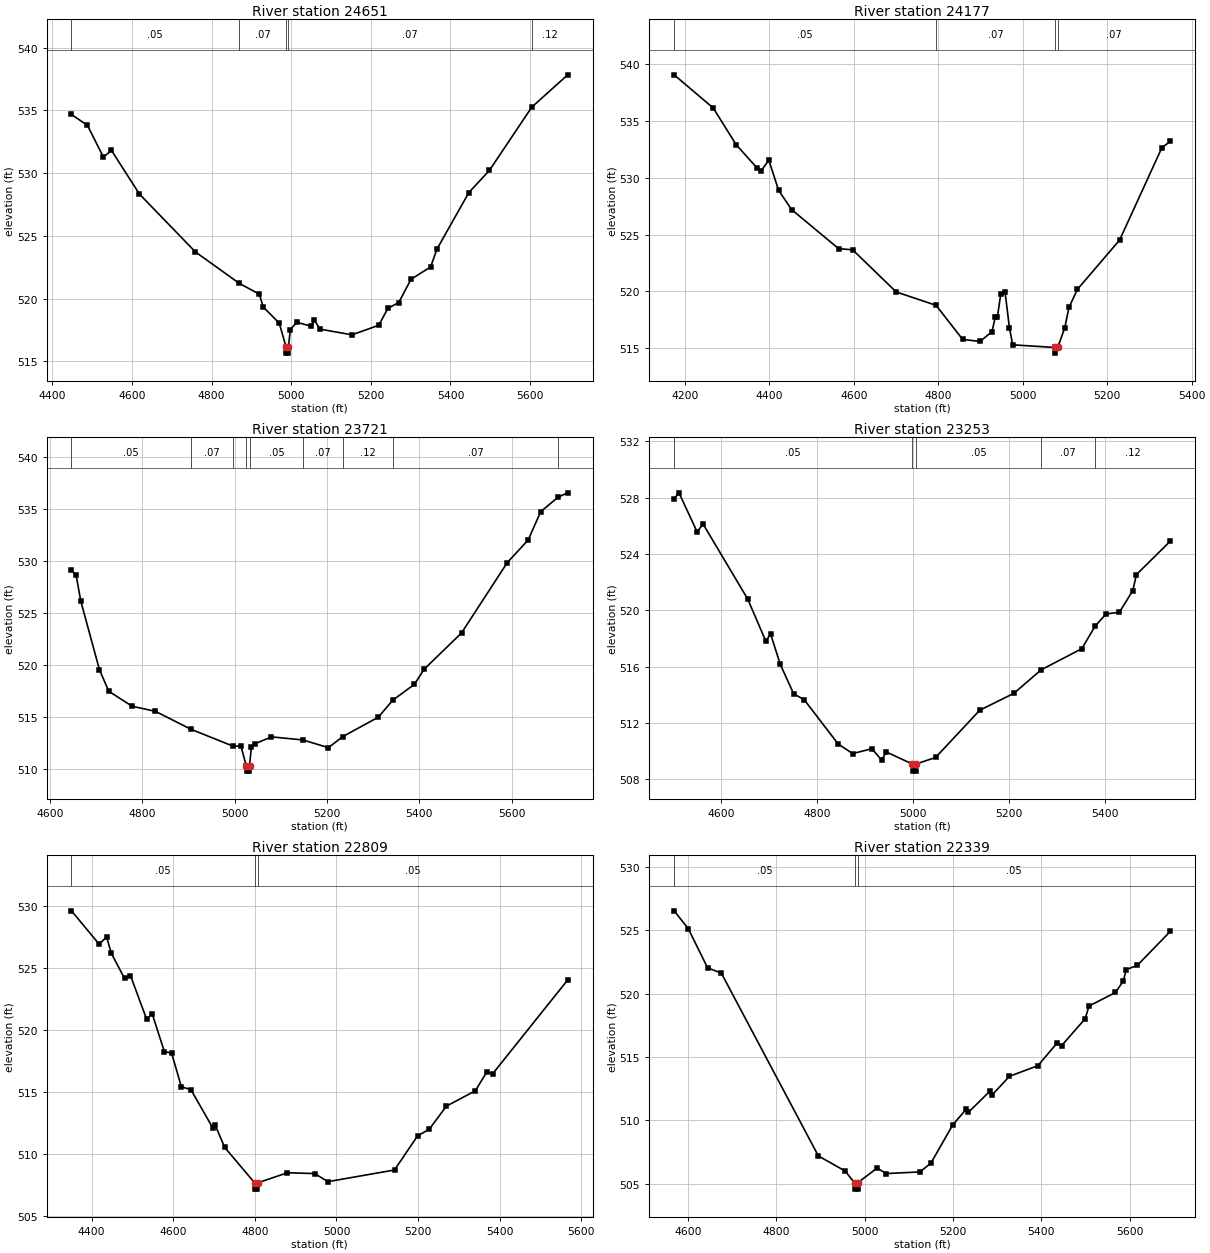
Type RM Length L Ch R = 1 ,24651   ,474,474,474
BEGIN DESCRIPTION:
CORDELL CREEK 53.0
END DESCRIPTION:
XS GIS Cut Line= 3
        2321575.       13730025.        2322125.       13729975.
      2322725.01     13730325.01
#Sta/Elev= 30
  4447.7  534.68  4487.9  533.81    4528  531.28  4548.1  531.82  4618.4  528.34
    4759  523.73  4868.9  521.23  4919.6  520.36  4929.7  519.33  4969.8  518.05
  4986.9  516.16  4987.4  515.66  4992.5  515.66    4993  516.16  4997.5  517.53
  5013.6  518.12  5050.8   517.8  5057.9   518.3  5072.3  517.57  5152.5  517.12
  5219.9  517.88  5242.7  519.23    5270  519.69    5301  521.55  5350.2  522.53
  5365.9  523.94  5446.1  528.45  5497.8  530.22  5604.5  535.27  5694.6  537.84
#Mann= 5 ,-1 , 0
  4447.7     .05       0  4868.9     .07       0  4986.9     .05       0
    4993     .07       0  5604.5     .12       0
Bank Sta=4986.9,4993
XS Rating Curve= 0 ,0
Exp/Cntr=0.3,0.1

Type RM Length L Ch R = 1 ,24177   ,456,456,456
BEGIN DESCRIPTION:
CORDELL CREEK 52.0
END DESCRIPTION:
XS GIS Cut Line= 3
      2321425.03     13730175.01        2322225.       13730375.
      2322575.01       13730375.
#Sta/Elev= 30
    4175  539.08  4267.7  536.15  4321.9  532.92  4370.8  530.89  4381.1  530.64
  4399.2  531.56  4422.4  528.89  4453.3   527.2  4564.1  523.77  4597.6  523.66
  4700.7  519.95    4795  518.77  4857.9  515.77  4899.1  515.59  4927.4  516.45
  4935.2  517.75  4940.3  517.78  4948.1  519.76  4958.4  519.91  4968.7  516.78
  4976.4  515.29  5076.1  515.06  5076.6  514.56    5083  515.06  5099.6  516.79
  5109.6  518.59  5129.6  520.18  5229.6  524.53  5329.6  532.67  5349.6  533.22
#Mann= 4 ,-1 , 0
    4175     .05       0    4795     .07       0  5076.1     .05       0
    5083     .07       0
Bank Sta=5076.1,5083
XS Rating Curve= 0 ,0
Exp/Cntr=0.3,0.1

Type RM Length L Ch R = 1 ,23721   ,468,468,468
BEGIN DESCRIPTION:
CORDELL CREEK 51.0
END DESCRIPTION:
XS GIS Cut Line= 3
      2321724.97       13730825.        2322075.       13730775.
      2322675.01     13730374.99
#Sta/Elev= 30
  4646.9  529.12    4657  528.64  4667.1  526.15  4707.5  519.56  4727.7   517.5
  4778.2  516.06  4828.8  515.57    4905  513.86  4996.2  512.24    5014  512.22
  5025.5  510.33    5026  509.83    5032  509.83  5032.5  510.33  5036.5  512.12
    5044  512.45  5080.1  513.12  5148.6  512.82  5203.3  512.08  5234.6  513.15
  5311.5  515.01    5343  516.65  5389.6  518.16  5410.6  519.61  5491.7   523.1
  5590.9  529.86    5636  532.02    5663  534.73  5700.6  536.13  5721.6  536.55
#Mann= 9 ,-1 , 0
  4646.9     .05       0    4905     .07       0  4996.2     .05       0
  5025.5     .05       0  5032.5     .05       0  5148.6     .07       0
  5234.6     .12       0    5343     .07       0  5700.6     .12       0
Bank Sta=5025.5,5032.5
XS Rating Curve= 0 ,0
Exp/Cntr=0.3,0.1

Type RM Length L Ch R = 1 ,23253   ,444,444,444
BEGIN DESCRIPTION:
CORDELL CREEK 50.0
END DESCRIPTION:
XS GIS Cut Line= 3
      2321774.98       13731225.        2322275.       13731175.
      2322674.98     13730825.02
#Sta/Elev= 30
  4501.9  527.93    4512  528.35  4549.7  525.58  4562.2  526.13  4655.2   520.8
  4692.9  517.81  4702.9  518.32    4723  516.16  4750.7  514.08  4773.3  513.63
  4843.6   510.5  4873.8  509.82    4914  510.16  4934.1  509.36  4944.1  509.93
  4998.4  509.07  4998.9  508.57    5005  508.57  5005.5  509.07  5046.7  509.54
  5138.7   512.9  5209.9   514.1  5266.6  515.77  5351.3  517.27  5378.9  518.86
  5401.6  519.74  5429.6  519.86  5457.6   521.4  5465.2  522.54  5535.9  524.92
#Mann= 5 ,-1 , 0
  4501.9     .05       0  4998.4     .05       0  5005.5     .05       0
  5266.6     .07       0  5378.9     .12       0
Bank Sta=4998.4,5005.5
XS Rating Curve= 0 ,0
Exp/Cntr=0.3,0.1

Type RM Length L Ch R = 1 ,22809   ,470,470,470
BEGIN DESCRIPTION:
CORDELL CREEK 49.0
END DESCRIPTION:
XS GIS Cut Line= 3
      2321724.99     13731324.99        2322325.       13731575.
        2322725.       13731175.
#Sta/Elev= 30
  4350.8  529.58  4418.5   526.9  4436.9  527.48  4448.3  526.17  4480.8  524.14
  4495.4  524.37    4535  520.85  4548.5   521.3  4578.3  518.26  4596.2  518.13
    4620  515.42  4643.3   515.2  4696.9  512.12  4702.4  512.37  4726.2  510.55
  4799.6  507.69  4800.1  507.19  4806.2  507.19  4806.7  507.69    4880  508.51
  4946.6  508.44  4979.1  507.79  5142.2  508.73  5198.8  511.48  5227.1     512
  5269.5  513.87  5340.2   515.1  5368.5  516.63  5382.7  516.47  5566.5  524.02
#Mann= 3 ,-1 , 0
  4350.8     .05       0  4799.6     .05       0  4806.7     .05       0
Bank Sta=4799.6,4806.7
XS Rating Curve= 0 ,0
Exp/Cntr=0.3,0.1

Type RM Length L Ch R = 1 ,22339   ,455,455,455
BEGIN DESCRIPTION:
CORDELL CREEK 48.0
END DESCRIPTION:
XS GIS Cut Line= 3
        2321825.       13732125.        2322225.       13731975.
      2322874.98     13731725.01
#Sta/Elev= 30
  4568.7  526.55  4600.7  525.14  4644.4  522.05  4675.5  521.63  4895.3  507.19
  4955.9     506  4977.1  505.07  4977.6  504.57  4983.9  504.57  4984.4  505.07
    5028  506.23  5049.5   505.8  5125.5  505.93  5150.2  506.63  5199.5  509.64
  5229.5  510.86  5234.8  510.63  5284.1  512.32  5289.5  512.04    5328  513.48
  5392.3  514.32  5435.2  516.08  5445.9   515.9  5499.5  518.03    5508  519.03
    5568   520.1  5585.2  520.98  5592.7  521.91  5617.3  522.24  5692.3  524.93
#Mann= 3 ,-1 , 0
  4568.7     .05       0  4977.1     .05       0  4984.4     .05       0
Bank Sta=4977.1,4984.4
XS Rating Curve= 0 ,0
Exp/Cntr=0.3,0.1

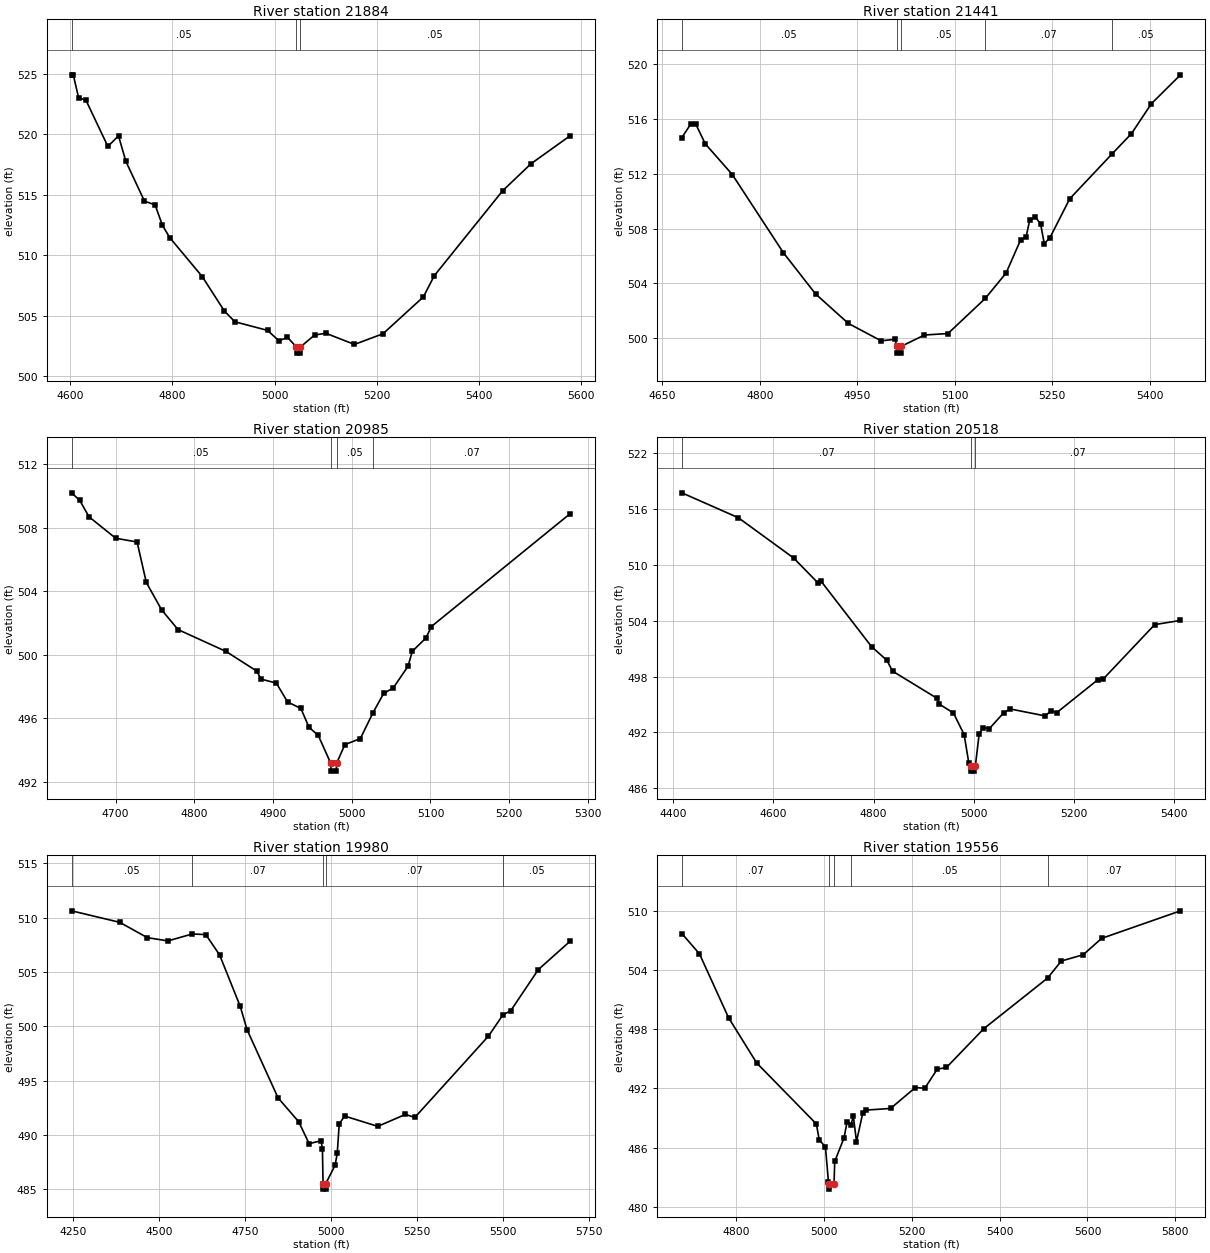
Type RM Length L Ch R = 1 ,21884   ,443,443,443
BEGIN DESCRIPTION:
CORDELL CREEK 47.0
END DESCRIPTION:
XS GIS Cut Line= 3
      2322074.97     13732625.03        2322375.       13732375.
      2322925.01       13732175.
#Sta/Elev= 30
  4602.6  524.93  4605.9  524.93  4616.3  523.03  4630.6  522.84  4673.6  519.01
  4694.4  519.89  4708.7  517.79  4745.2  514.49    4766  514.18  4780.3   512.5
  4794.6  511.48  4858.4  508.25  4901.4  505.42  4922.2  504.52    4986  503.81
  5008.4  502.95  5025.1  503.24  5042.7  502.43  5043.2  501.93  5049.6  501.93
  5050.1  502.43  5078.3  503.43  5100.2  503.57  5156.1  502.65    5212  503.53
  5291.1  506.58  5312.4  508.33    5446  515.34  5501.9  517.59  5578.4   519.9
#Mann= 3 ,-1 , 0
  4602.6     .05       0  5042.7     .05       0  5050.1     .05       0
Bank Sta=5042.7,5050.1
XS Rating Curve= 0 ,0
Exp/Cntr=0.3,0.1

Type RM Length L Ch R = 1 ,21441   ,456,456,456
BEGIN DESCRIPTION:
CORDELL CREEK 46.0
END DESCRIPTION:
XS GIS Cut Line= 3
        2322525.     13732875.01        2322725.       13732625.
      2322925.01     13732224.98
#Sta/Elev= 30
  4679.9  514.63  4693.5  515.62  4701.5   515.6  4715.9  514.18  4757.5  511.94
    4836  506.25  4885.6  503.24    4936  501.09  4986.5  499.82  5008.4  499.93
  5010.3  499.42  5010.8  498.92  5017.3  498.92  5017.8  499.42  5053.2  500.24
  5089.5  500.35  5146.9  502.91  5178.9  504.76  5201.3  507.18  5209.7   507.4
  5215.3  508.62  5223.7  508.87  5232.1  508.32  5237.6  506.91    5246   507.3
  5276.8  510.17  5341.7  513.43  5371.8  514.92  5402.6  517.11  5447.3  519.21
#Mann= 5 ,-1 , 0
  4679.9     .05       0  5010.3     .05       0  5017.8     .05       0
  5146.9     .07       0  5341.7     .05       0
Bank Sta=5010.3,5017.8
XS Rating Curve= 0 ,0
Exp/Cntr=0.3,0.1

Type RM Length L Ch R = 1 ,20985   ,467,467,467
BEGIN DESCRIPTION:
CORDELL CREEK 45.0
END DESCRIPTION:
XS GIS Cut Line= 3
      2322724.96     13732975.01        2323075.       13732875.
        2323175.       13732625.
#Sta/Elev= 30
  4644.2   510.2  4654.6  509.72  4666.3  508.69  4700.1  507.34  4727.4   507.1
  4739.1  504.55  4758.6  502.82  4779.4  501.58  4840.5   500.2  4879.5  498.96
  4884.7  498.46  4904.2  498.21  4918.5  497.02  4935.4  496.61  4945.8  495.42
  4957.5  494.91  4973.3  493.16  4973.8  492.66  4980.3  492.66  4980.8  493.16
  4991.3  494.33  5010.9  494.71  5026.9  496.33  5040.6  497.56  5052.7   497.9
  5071.5  499.27  5076.9  500.21  5094.4  501.06  5101.1  501.77  5277.5  508.89
#Mann= 4 ,-1 , 0
  4644.2     .05       0  4973.3     .05       0  4980.8     .05       0
  5026.9     .07       0
Bank Sta=4973.3,4980.8
XS Rating Curve= 0 ,0
Exp/Cntr=0.3,0.1

Type RM Length L Ch R = 1 ,20518   ,538,538,538
BEGIN DESCRIPTION:
CORDELL CREEK 44.0
END DESCRIPTION:
XS GIS Cut Line= 3
      2323252.51     13733745.21        2323375.       13733175.
      2323275.01     13732775.03
#Sta/Elev= 30
  4417.2  517.71  4529.9  515.04  4640.3  510.72  4689.7     508  4694.8  508.25
  4795.9  501.21  4826.5  499.74  4837.8  498.58  4926.4  495.67  4931.5  495.03
  4959.5  494.08  4980.8  491.76  4990.2  488.68    4994  488.35  4994.5  487.85
  5001.2  487.85  5001.7  488.35    5003  488.35  5010.7   491.8  5018.5  492.52
  5031.3  492.42  5059.7  494.11  5072.6  494.52  5142.1  493.78    5155  494.32
  5165.3  494.11  5247.8  497.66  5258.1  497.71  5361.2  503.57  5412.7  504.02
#Mann= 3 ,-1 , 0
  4417.2     .07       0    4994     .05       0  5001.7     .07       0
Bank Sta=4994,5001.7
XS Rating Curve= 0 ,0
Exp/Cntr=0.3,0.1

Type RM Length L Ch R = 1 ,19980   ,424,424,424
BEGIN DESCRIPTION:
CORDELL CREEK 43.0
END DESCRIPTION:
XS GIS Cut Line= 3
        2323775.     13733674.98      2323743.84     13732950.22
      2323382.15     13732322.38
#Sta/Elev= 30
  4245.4  510.63  4385.5  509.57  4465.6  508.16  4525.6  507.86  4596.4   508.5
  4635.7  508.44  4675.8  506.57  4735.8  501.83  4755.8  499.67  4845.9   493.4
    4906   491.2    4936  489.19  4970.8  489.45  4974.8  488.72  4976.7   485.5
  4977.2     485  4983.9     485  4984.4   485.5  5011.5  487.19  5017.9  488.29
  5023.7  491.01  5039.5  491.73  5135.7  490.78  5216.2  491.88  5243.5   491.6
  5457.6  499.09  5499.8  501.05  5522.2  501.42  5602.7  505.22  5695.4  507.84
#Mann= 5 ,-1 , 0
  4245.4     .05       0  4596.4     .07       0  4976.7     .05       0
  4984.4     .07       0  5499.8     .05       0
Bank Sta=4976.7,4984.4
XS Rating Curve= 0 ,0
Exp/Cntr=0.3,0.1

Type RM Length L Ch R = 1 ,19556   ,443,443,443
BEGIN DESCRIPTION:
CORDELL CREEK 42.0
END DESCRIPTION:
XS GIS Cut Line= 3
      2323775.03     13733274.96        2323975.       13733025.
      2324538.84     13732435.01
#Sta/Elev= 30
  4675.8  507.69  4715.8  505.64  4782.2  499.17  4846.2  494.59  4982.3  488.41
  4988.7  486.82    5003  486.07  5009.9   482.5  5011.7  482.31  5012.2  481.81
  5022.6  482.31  5024.1  484.61  5045.4  487.01  5052.4  488.65  5061.5  488.34
  5066.5  489.23  5073.7  486.63  5087.9  489.49  5094.8  489.81  5151.4  489.98
    5208   492.1  5229.4  492.02  5257.7  493.96  5278.8  494.13  5363.7  498.05
  5509.1  503.18  5540.5  504.91  5590.2  505.54  5632.3   507.2    5812  509.99
#Mann= 5 ,-1 , 0
  4675.8     .07       0  5011.7     .05       0  5022.6     .07       0
  5061.5     .05       0  5509.1     .07       0
Bank Sta=5011.7,5022.6
XS Rating Curve= 0 ,0
Exp/Cntr=0.3,0.1