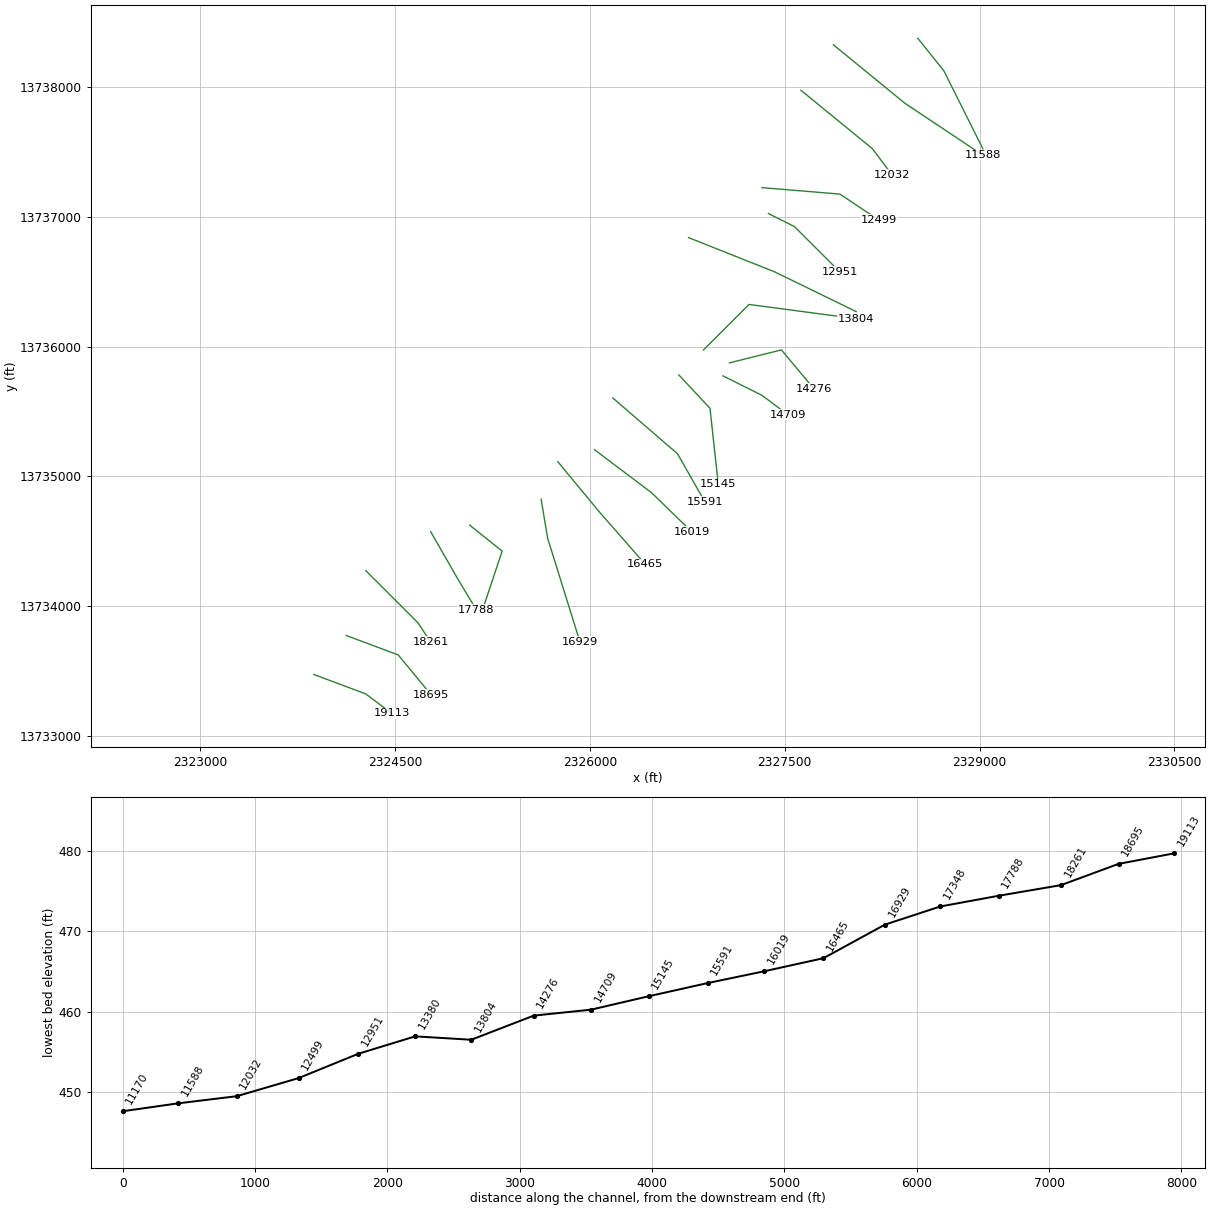
HEC-RAS study CORDELL CREEK.prj: CORDELL CREEK Base Level Engineering

--- CORDELL CREEK.g01 (geometry) --- (continued)

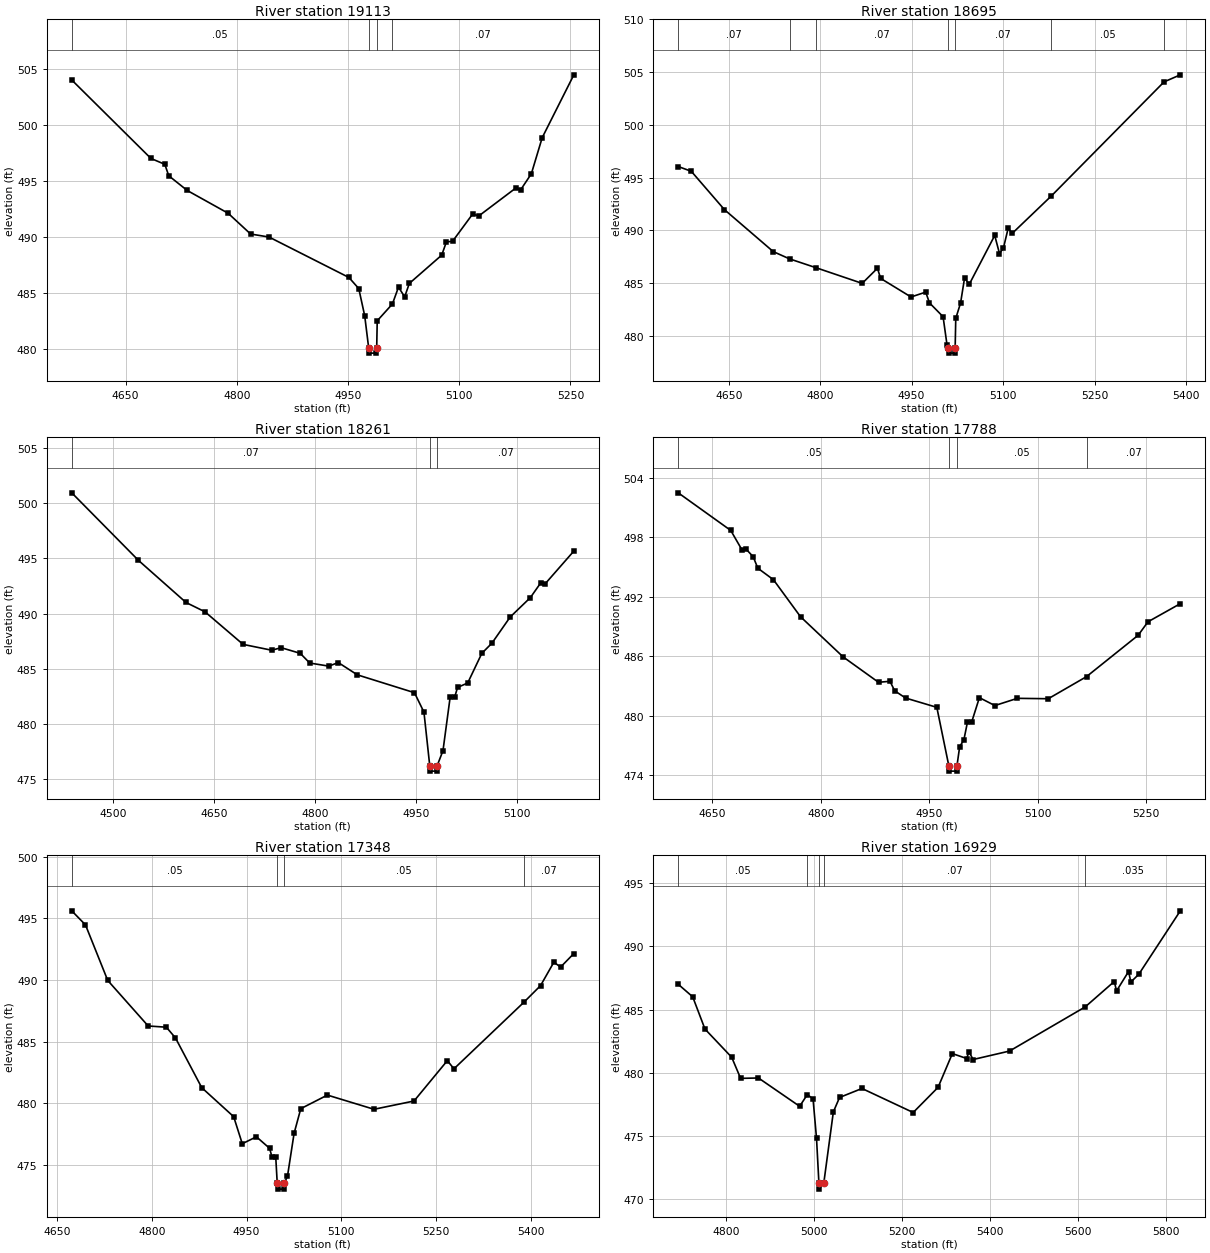
Type RM Length L Ch R = 1 ,19113   ,418,418,418
BEGIN DESCRIPTION:
CORDELL CREEK 41.0
END DESCRIPTION:
XS GIS Cut Line= 3
      2323875.03     13733474.99        2324275.       13733325.
      2324475.02     13733174.98
#Sta/Elev= 30
  4577.4  503.99  4684.2     497  4702.9  496.48  4708.2  495.46  4733.1  494.15
  4788.3  492.12  4818.6  490.27  4843.5     490  4951.2   486.4  4964.5  485.41
  4972.5  482.99  4977.8  480.16  4978.3  479.66  4988.2  479.66  4988.7  480.16
  4989.4  482.54  5009.9  484.04  5018.1  485.54  5026.4  484.67  5032.7  485.87
  5076.4  488.39  5082.7  489.57    5091  489.62  5118.1  492.05  5126.4  491.88
  5176.4  494.37  5182.7  494.19  5197.3  495.64  5211.9  498.85  5254.6  504.45
#Mann= 4 ,-1 , 0
  4577.4     .05       0  4977.8     .05       0  4988.7     .05       0
  5009.9     .07       0
Bank Sta=4977.8,4988.7
XS Rating Curve= 0 ,0
Exp/Cntr=0.3,0.1

Type RM Length L Ch R = 1 ,18695   ,434,434,434
BEGIN DESCRIPTION:
CORDELL CREEK 40.0
END DESCRIPTION:
XS GIS Cut Line= 3
      2324124.98     13733775.01        2324525.       13733625.
      2324777.19     13733319.33
#Sta/Elev= 30
  4567.2  496.04  4588.6  495.59  4642.9  491.96    4723  487.98  4749.8  487.29
  4792.8  486.46  4868.9  484.97  4893.9   486.4  4899.2  485.44    4949  483.68
  4973.1  484.14  4979.3  483.12  5001.6  481.81  5008.1  479.12  5010.4  478.86
  5010.9  478.36  5020.9  478.36  5021.4  478.86  5022.4  481.65  5030.3  483.11
  5036.8  485.47  5044.6  484.89  5086.3  489.51  5094.1   487.8  5100.6  488.32
  5108.4  490.21  5114.9   489.7  5179.3  493.26    5364  504.06  5390.7  504.73
#Mann= 7 ,-1 , 0
  4567.2     .07       0  4749.8     .05       0  4792.8     .07       0
  5010.4     .05       0  5021.4     .07       0  5179.3     .05       0
    5364     .07       0
Bank Sta=5010.4,5021.4
XS Rating Curve= 0 ,0
Exp/Cntr=0.3,0.1

Type RM Length L Ch R = 1 ,18261   ,473,473,473
BEGIN DESCRIPTION:
CORDELL CREEK 39.0
END DESCRIPTION:
XS GIS Cut Line= 3
      2324275.02     13734274.98        2324675.       13733875.
      2324774.98     13733725.03
#Sta/Elev= 30
  4438.7  500.95  4537.7  494.83  4608.4  491.01  4636.7  490.16  4693.2  487.21
  4735.7  486.68  4749.8  486.91  4778.1   486.4  4792.2  485.52  4820.5  485.24
  4834.7  485.56  4862.9  484.45  4947.8  482.83  4961.9  481.07  4970.5  476.22
    4971  475.72  4981.1  475.72  4981.6  476.22  4990.2  477.58  5000.8  482.41
  5007.4  482.41  5011.9  483.31  5026.9  483.71  5047.9   486.4  5062.9  487.32
    5090  489.69    5120  491.45  5135.1  492.76  5141.1  492.64  5184.6  495.67
#Mann= 3 ,-1 , 0
  4438.7     .07       0  4970.5     .05       0  4981.6     .07       0
Bank Sta=4970.5,4981.6
XS Rating Curve= 0 ,0
Exp/Cntr=0.3,0.1

Type RM Length L Ch R = 1 ,17788   ,440,440,440
BEGIN DESCRIPTION:
CORDELL CREEK 38.0
END DESCRIPTION:
XS GIS Cut Line= 3
        2324775.     13734575.01        2324975.       13734225.
      2325125.02     13733974.97
#Sta/Elev= 30
  4602.7  502.49  4675.4  498.69  4691.2  496.69    4697  496.77  4706.4  496.04
  4712.8  494.88  4734.4  493.72  4771.9  489.98  4830.9  485.92  4879.8  483.36
  4895.7  483.46  4902.2   482.5  4917.3  481.77  4960.5  480.83  4977.2  474.89
  4977.7  474.39  4987.8  474.39  4988.3  474.89  4992.1  476.86  4997.9  477.54
  5002.9  479.34  5008.7  479.34  5019.4  481.81  5040.8  481.01  5071.9  481.74
  5114.7   481.7  5167.6  483.93  5239.1  488.11  5252.7  489.47  5297.4   491.3
#Mann= 4 ,-1 , 0
  4602.7     .05       0  4977.2     .05       0  4988.3     .05       0
  5167.6     .07       0
Bank Sta=4977.2,4988.3
XS Rating Curve= 0 ,0
Exp/Cntr=0.3,0.1

Type RM Length L Ch R = 1 ,17348   ,419,419,419
BEGIN DESCRIPTION:
CORDELL CREEK 37.0
END DESCRIPTION:
XS GIS Cut Line= 3
      2325074.96     13734625.03        2325325.       13734425.
      2325175.01     13733975.04
#Sta/Elev= 30
  4673.4  495.61  4695.1  494.47  4730.3  489.97  4794.3  486.28  4823.1  486.18
  4837.5  485.31  4879.1  481.28  4929.6  478.93  4943.2  476.74  4965.6   477.3
  4986.4  476.37  4990.4  475.64  4996.2  475.64  4998.5  473.56    4999  473.06
  5009.2  473.06  5009.7  473.56  5014.7  474.09  5025.2  477.58  5035.8  479.58
  5077.9  480.68  5151.7  479.53    5215   480.2  5267.7  483.47  5278.2  482.81
  5388.6  488.19  5415.2  489.55  5436.3  491.45  5446.9  491.05  5467.9  492.15
#Mann= 4 ,-1 , 0
  4673.4     .05       0  4998.5     .05       0  5009.7     .05       0
  5388.6     .07       0
Bank Sta=4998.5,5009.7
XS Rating Curve= 0 ,0
Exp/Cntr=0.3,0.1

Type RM Length L Ch R = 1 ,16929   ,464,464,464
BEGIN DESCRIPTION:
CORDELL CREEK 36.0
END DESCRIPTION:
XS GIS Cut Line= 3
        2325625.     13734824.98        2325675.       13734525.
      2325924.13      13733724.8
#Sta/Elev= 30
  4691.3     487  4724.2  486.01  4752.1  483.46  4812.9  481.23  4833.2  479.56
  4873.8  479.59  4967.5  477.35    4985  478.28    4998  477.93  5005.9  474.81
  5011.3   471.3  5011.8   470.8  5022.5   471.3  5044.2  476.91  5058.3  478.05
  5109.3  478.76  5225.8  476.86  5282.4  478.85  5314.9  481.52  5347.5  481.13
  5352.7  481.67    5362  481.05    5445  481.72  5617.1  485.21  5683.2  487.22
  5688.5  486.48  5715.8  488.01    5721  487.18    5739  487.79  5833.5  492.81
#Mann= 5 ,-1 , 0
  4691.3     .05       0    4985     .07       0  5011.3     .05       0
  5022.5     .07       0  5617.1    .035       0
Bank Sta=5011.3,5022.5
XS Rating Curve= 0 ,0
Exp/Cntr=0.3,0.1

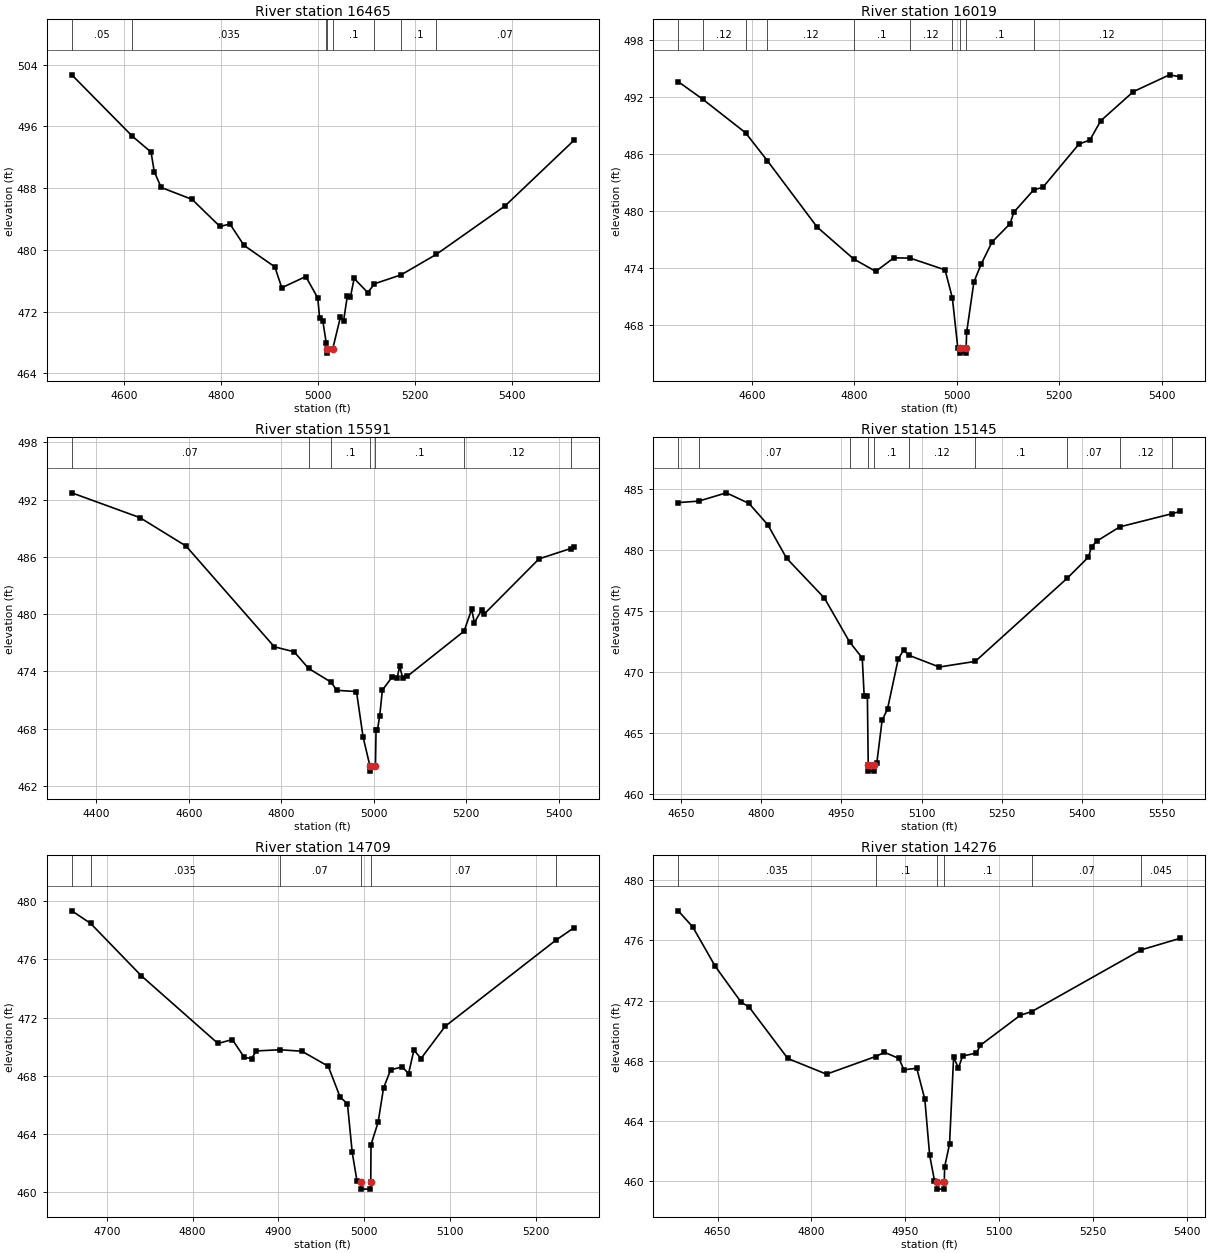
Type RM Length L Ch R = 1 ,16465   ,446,446,446
BEGIN DESCRIPTION:
CORDELL CREEK 35.0
END DESCRIPTION:
XS GIS Cut Line= 3
      2325753.55     13735113.46        2326075.       13734725.
      2326424.98     13734325.02
#Sta/Elev= 30
  4491.4  502.68    4616  494.75    4655  492.66  4661.5  490.15  4675.8  488.09
  4739.7  486.54    4797  483.04  4817.8  483.35  4846.5   480.6  4910.3   477.8
  4924.6   475.1  4974.1  476.55  4998.9  473.77  5002.7  471.15  5009.4  470.75
  5016.4  467.92  5017.8  467.13  5018.3  466.63  5029.5  467.13  5045.4  471.25
  5052.1  470.79  5059.7  473.99  5066.3  473.92  5073.9  476.31  5101.9  474.47
  5115.8  475.61  5171.1  476.78  5243.3  479.42  5385.2   485.7  5527.1  494.18
#Mann= 8 ,-1 , 0
  4491.4     .05       0    4616    .035       0  5016.4      .1       0
  5017.8    .035       0  5029.5      .1       0  5115.8     .12       0
  5171.1      .1       0  5243.3     .07       0
Bank Sta=5017.8,5029.5
XS Rating Curve= 0 ,0
Exp/Cntr=0.3,0.1

Type RM Length L Ch R = 1 ,16019   ,428,428,428
BEGIN DESCRIPTION:
CORDELL CREEK 34.0
END DESCRIPTION:
XS GIS Cut Line= 3
      2326036.73      13735205.6        2326475.       13734875.
      2326783.99     13734574.35
#Sta/Elev= 30
  4456.5  493.58  4504.4  491.73  4587.9   488.2  4630.5  485.26  4727.6  478.28
  4798.7  474.93  4842.1  473.61  4877.4  475.04  4909.2  475.01  4977.4  473.77
  4991.6  470.82  5002.3  465.54  5006.7  465.51  5007.2  465.01  5017.9  465.01
  5018.4  465.51  5019.5   467.2  5033.7  472.51  5047.8  474.37  5069.1   476.7
  5104.4  478.64  5111.6  479.84  5150.7  482.21  5168.2  482.45  5238.9  487.02
    5260  487.43  5281.3  489.46  5344.9  492.53  5415.6   494.3  5436.6  494.08
#Mann= 10 ,-1 , 0
  4456.5    .035       0  4504.4     .12       0  4587.9     .07       0
  4630.5     .12       0  4798.7      .1       0  4909.2     .12       0
  4991.6      .1       0  5006.7     .05       0  5018.4      .1       0
  5150.7     .12       0
Bank Sta=5006.7,5018.4
XS Rating Curve= 0 ,0
Exp/Cntr=0.3,0.1

Type RM Length L Ch R = 1 ,15591   ,446,446,446
BEGIN DESCRIPTION:
CORDELL CREEK 33.0
END DESCRIPTION:
XS GIS Cut Line= 3
      2326176.66     13735604.79        2326675.       13735175.
      2326886.33     13734803.01
#Sta/Elev= 30
  4346.6  492.71    4494  490.11  4593.8  487.13  4784.7  476.57  4827.5  476.05
  4858.7  474.31  4907.6  472.86  4919.6  472.01  4962.4  471.88  4976.7   467.1
  4991.7  464.04  4992.2  463.54  5003.4  464.04  5004.7   467.8  5007.5   467.8
  5012.6  469.33  5018.4  472.04    5040  473.43  5050.1  473.31  5055.9  474.51
  5062.2  473.33  5071.7  473.46  5195.1  478.21  5211.6  480.51  5217.3   479.1
  5233.2  480.43    5239  480.02  5357.2  485.79  5425.6  486.87  5432.5     487
#Mann= 7 ,-1 , 0
  4346.6     .07       0  4858.7     .12       0  4907.6      .1       0
  4991.7     .05       0  5003.4      .1       0  5195.1     .12       0
  5425.6     .07       0
Bank Sta=4991.7,5003.4
XS Rating Curve= 0 ,0
Exp/Cntr=0.3,0.1

Type RM Length L Ch R = 1 ,15145   ,436,436,436
BEGIN DESCRIPTION:
CORDELL CREEK 32.0
END DESCRIPTION:
XS GIS Cut Line= 3
      2326685.07      13735782.2        2326925.       13735525.
      2326988.69     13734939.69
#Sta/Elev= 30
  4644.2   483.9  4682.6  484.02  4734.3   484.7  4776.8  483.83    4812  482.08
  4847.2  479.34    4918  476.08  4965.1  472.49  4988.9  471.17  4992.5  468.06
  4998.5  468.06  5000.1   462.4  5000.6   461.9  5011.3   461.9  5011.8   462.4
  5016.1  462.54  5026.1  466.06  5036.2  466.99  5056.3  471.09  5066.3  471.81
  5076.3  471.39  5133.2  470.43  5200.6  470.89  5372.5  477.69  5412.7  479.44
  5418.4  480.29  5428.5  480.75  5471.2  481.91  5569.9     483  5584.7  483.18
#Mann= 10 ,-1 , 0
  4644.2    .035       0  4682.6     .07       0  4965.1      .1       0
  5000.1     .05       0  5011.8      .1       0  5076.3     .12       0
  5200.6      .1       0  5372.5     .07       0  5471.2     .12       0
  5569.9     .07       0
Bank Sta=5000.1,5011.8
XS Rating Curve= 0 ,0
Exp/Cntr=0.3,0.1

Type RM Length L Ch R = 1 ,14709   ,433,433,433
BEGIN DESCRIPTION:
CORDELL CREEK 31.0
END DESCRIPTION:
XS GIS Cut Line= 3
      2327025.03     13735774.98        2327325.       13735625.
      2327525.02     13735474.98
#Sta/Elev= 30
  4659.1  479.32    4681  478.46  4740.1  474.87  4829.6  470.22  4846.3  470.49
  4860.3  469.26  4868.7  469.19  4874.3  469.71  4901.7  469.79  4927.4  469.69
  4958.1  468.66  4972.1  466.53  4980.5  466.09  4986.1  462.75  4991.7  460.77
  4995.9  460.73  4996.4  460.23  5007.2  460.23  5007.7  460.73    5008  463.28
  5016.3  464.82  5022.6  467.16  5030.9  468.42  5044.5  468.61  5051.8  468.15
    5058  469.77  5066.3  469.19  5094.5   471.4  5223.2  477.29  5244.5  478.15
#Mann= 6 ,-1 , 0
  4659.1     .07       0    4681    .035       0  4901.7     .07       0
  4995.9     .05       0  5007.7     .07       0  5223.2    .045       0
Bank Sta=4995.9,5007.7
XS Rating Curve= 0 ,0
Exp/Cntr=0.3,0.1

Type RM Length L Ch R = 1 ,14276   ,472,472,472
BEGIN DESCRIPTION:
CORDELL CREEK 30.0
END DESCRIPTION:
XS GIS Cut Line= 3
      2327075.01       13735875.        2327475.       13735975.
      2327724.99     13735675.01
#Sta/Elev= 30
  4587.1  477.96  4610.3  476.89  4646.4  474.27  4687.6   471.9  4700.5  471.57
  4762.3  468.16  4824.2  467.12  4902.6  468.29  4916.9  468.57  4940.1  468.16
  4947.9  467.41  4968.5  467.51  4981.4  465.45  4989.1  461.74  4996.8  460.06
  5000.7  459.99  5001.2  459.49    5012  459.49  5012.5  459.99  5013.1  460.98
  5020.9  462.47  5027.4  468.24  5035.2  467.53  5041.7  468.32  5063.8  468.52
  5070.3  469.04  5134.1  471.03  5152.2  471.27  5327.5  475.37  5389.9  476.14
#Mann= 6 ,-1 , 0
  4587.1    .035       0  4902.6      .1       0  5000.7     .05       0
  5012.5      .1       0  5152.2     .07       0  5327.5    .045       0
Bank Sta=5000.7,5012.5
XS Rating Curve= 0 ,0
Exp/Cntr=0.3,0.1

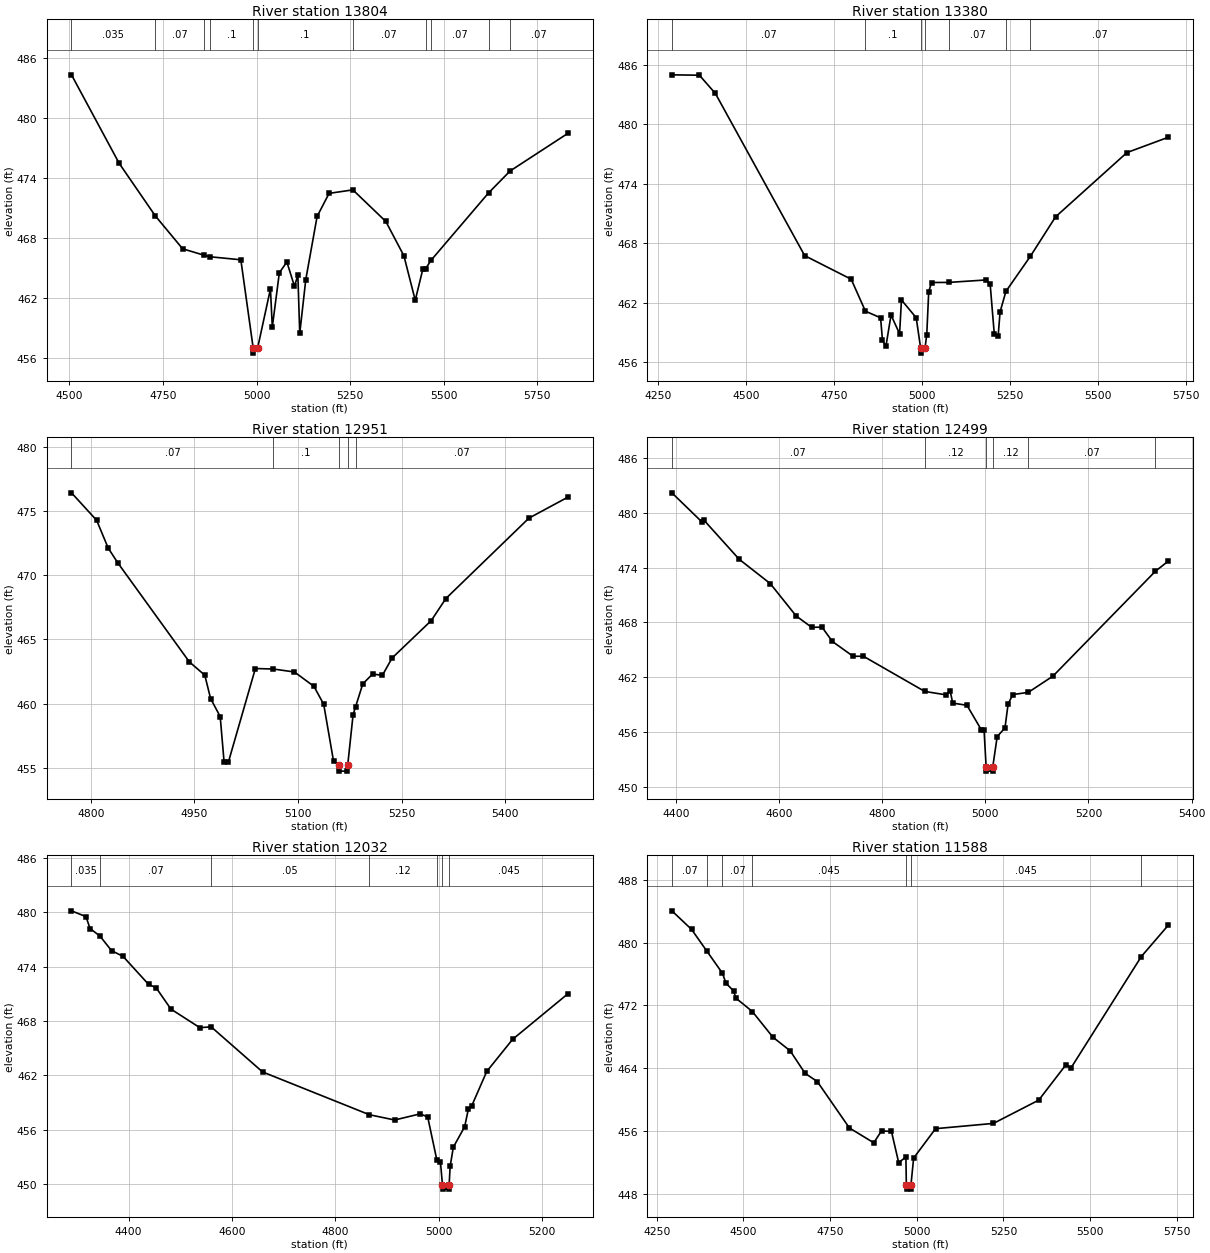
Type RM Length L Ch R = 1 ,13804   ,424,424,424
BEGIN DESCRIPTION:
CORDELL CREEK 29.0
END DESCRIPTION:
XS GIS Cut Line= 3
      2326874.97     13735974.97        2327225.       13736325.
      2328049.85     13736215.56
#Sta/Elev= 30
  4505.5  484.31  4632.8  475.47  4729.3  470.22  4802.5  466.92  4858.7  466.29
  4876.5  466.12  4958.1  465.82  4991.1  456.99  4991.6  456.49  5002.9  456.99
  5037.2  462.91  5042.2  459.09    5061  464.53  5081.2   465.6  5101.4  463.17
  5110.5  464.29  5115.5  458.46  5131.7  463.85  5161.9  470.15  5193.9  472.46
  5257.5  472.81  5345.6  469.65  5393.9  466.22  5424.2  461.77  5444.4  464.87
  5452.1  464.94  5466.2  465.76    5620   472.5  5677.8   474.7  5832.6  478.47
#Mann= 11 ,-1 , 0
  4505.5    .035       0  4729.3     .07       0  4858.7    .035       0
  4876.5      .1       0  4991.1     .05       0  5002.9      .1       0
  5257.5     .07       0  5452.1     .12       0  5466.2     .07       0
    5620     .12       0  5677.8     .07       0
Bank Sta=4991.1,5002.9
XS Rating Curve= 0 ,0
Exp/Cntr=0.3,0.1

Type RM Length L Ch R = 1 ,13380   ,429,429,429
BEGIN DESCRIPTION:
CORDELL CREEK 28.0
END DESCRIPTION:
XS GIS Cut Line= 3
      2326760.14     13736839.95        2327425.       13736575.
      2328049.89     13736270.14
#Sta/Elev= 30
  4288.2  484.97  4366.3  484.93  4411.8  483.09  4665.5  466.74  4797.7  464.36
  4838.1  461.14  4881.2  460.47  4886.6   458.2  4896.3  457.58  4910.9  460.75
  4935.2  458.86  4940.5  462.27  4982.4  460.48  4995.1  457.41  4995.6  456.91
  5007.3  457.41  5012.4  458.76    5018  463.12  5026.2  464.03  5074.8  464.04
  5181.9  464.29  5192.6  463.85  5204.2  458.87  5215.2  458.59  5220.7  461.06
  5237.4  463.14  5306.6  466.66  5378.4  470.65  5581.2  477.13  5699.2  478.68
#Mann= 7 ,-1 , 0
  4288.2     .07       0  4838.1      .1       0  4995.1     .05       0
  5007.3      .1       0  5074.8     .07       0  5237.4      .1       0
  5306.6     .07       0
Bank Sta=4995.1,5007.3
XS Rating Curve= 0 ,0
Exp/Cntr=0.3,0.1

Type RM Length L Ch R = 1 ,12951   ,452,452,452
BEGIN DESCRIPTION:
CORDELL CREEK 27.0
END DESCRIPTION:
XS GIS Cut Line= 3
      2327374.98     13737025.01        2327575.       13736925.
        2327925.       13736575.
#Sta/Elev= 30
  4772.1  476.42  4808.5  474.28  4825.2  472.12  4839.2  470.96  4942.6  463.26
    4965  462.22  4973.4   460.4  4987.3     459  4992.9  455.48  4999.3  455.48
  5038.2  462.74  5064.3   462.7  5094.7  462.47    5123  461.35  5137.1  459.95
  5151.3  455.53    5159  455.25  5159.5  454.75  5171.4  454.75  5171.9  455.25
  5179.6  459.14  5183.2  459.76  5193.7  461.55  5207.9  462.31    5222  462.21
  5236.1  463.56  5292.7  466.47  5313.9  468.19  5434.1  474.45  5490.7  476.09
#Mann= 5 ,-1 , 0
  4772.1     .07       0  5064.3      .1       0    5159     .05       0
  5171.9      .1       0  5183.2     .07       0
Bank Sta=5159,5171.9
XS Rating Curve= 0 ,0
Exp/Cntr=0.3,0.1

Type RM Length L Ch R = 1 ,12499   ,467,467,467
BEGIN DESCRIPTION:
CORDELL CREEK 26.0
END DESCRIPTION:
XS GIS Cut Line= 3
      2327324.99       13737225.        2327925.       13737175.
      2328224.96     13736975.03
#Sta/Elev= 30
  4392.4   482.2  4450.1  479.04  4455.1  479.17  4522.9  474.92  4583.1  472.26
  4633.2  468.72  4663.3  467.47  4683.4  467.49  4703.5  465.92  4743.6   464.3
  4763.7   464.3  4882.5  460.45  4924.3  460.07  4931.8  460.51  4936.8  459.17
  4964.4  458.93    4992  456.27  4997.5  456.27  5001.5  452.22    5002  451.72
    5014  451.72  5014.5  452.22    5023   455.5  5038.1  456.46  5044.1  459.05
  5053.1   460.1  5083.4  460.35  5131.2  462.13  5329.5   473.6    5355  474.74
#Mann= 6 ,-1 , 0
  4392.4     .07       0  4882.5     .12       0  5001.5     .05       0
  5014.5     .12       0  5083.4     .07       0  5329.5    .045       0
Bank Sta=5001.5,5014.5
XS Rating Curve= 0 ,0
Exp/Cntr=0.3,0.1

Type RM Length L Ch R = 1 ,12032   ,444,444,444
BEGIN DESCRIPTION:
CORDELL CREEK 25.0
END DESCRIPTION:
XS GIS Cut Line= 3
      2327625.02     13737974.98        2328175.       13737525.
        2328325.     13737325.01
#Sta/Elev= 30
  4289.6  480.15  4317.6  479.51  4325.5   478.2  4344.6  477.37  4367.1  475.76
  4389.3  475.13  4438.9  472.03  4453.2  471.68  4481.9  469.32  4537.9  467.27
  4559.8  467.36  4659.2  462.39    4866  457.67  4914.8  457.09  4964.3  457.77
  4978.7  457.42  4996.3   452.7  5003.3  452.51  5007.2  449.97  5007.7  449.47
  5019.7  449.47  5020.2  449.97  5022.1  451.99  5028.3   454.1  5050.2  456.35
  5057.5  458.34  5063.7  458.63  5092.9  462.44  5142.9  465.98  5250.2  471.02
#Mann= 7 ,-1 , 0
  4289.6    .035       0  4344.6     .07       0  4559.8     .05       0
    4866     .12       0  4996.3    .045       0  5007.2    .045       0
  5020.2    .045       0
Bank Sta=5007.2,5020.2
XS Rating Curve= 0 ,0
Exp/Cntr=0.3,0.1

Type RM Length L Ch R = 1 ,11588   ,418,418,418
BEGIN DESCRIPTION:
CORDELL CREEK 24.0
END DESCRIPTION:
XS GIS Cut Line= 3
        2327875.       13738325.        2328425.       13737875.
      2329024.96     13737475.03
#Sta/Elev= 30
    4294  484.07  4350.7   481.7  4395.5  478.89  4439.9   476.1  4449.8  474.85
    4472  473.85  4478.5  472.94  4525.9  471.23  4585.4  467.95    4635  466.22
    4678  463.35  4713.2   462.3  4805.8  456.38  4876.1  454.49  4898.4  456.01
  4927.1  455.93  4947.9  451.96  4968.7  452.68    4970  449.08  4970.5  448.58
  4982.7  448.58  4983.2  449.08    4991  452.54  5054.2  456.29    5221  456.96
  5351.7  459.93  5429.8  464.42  5444.8  464.04  5647.5  478.24  5725.7  482.26
#Mann= 7 ,-1 , 0
    4294     .07       0  4395.5    .035       0  4439.9     .07       0
  4525.9    .045       0    4970    .045       0  4983.2    .045       0
  5647.5     .07       0
Bank Sta=4970,4983.2
XS Rating Curve= 0 ,0
Exp/Cntr=0.3,0.1

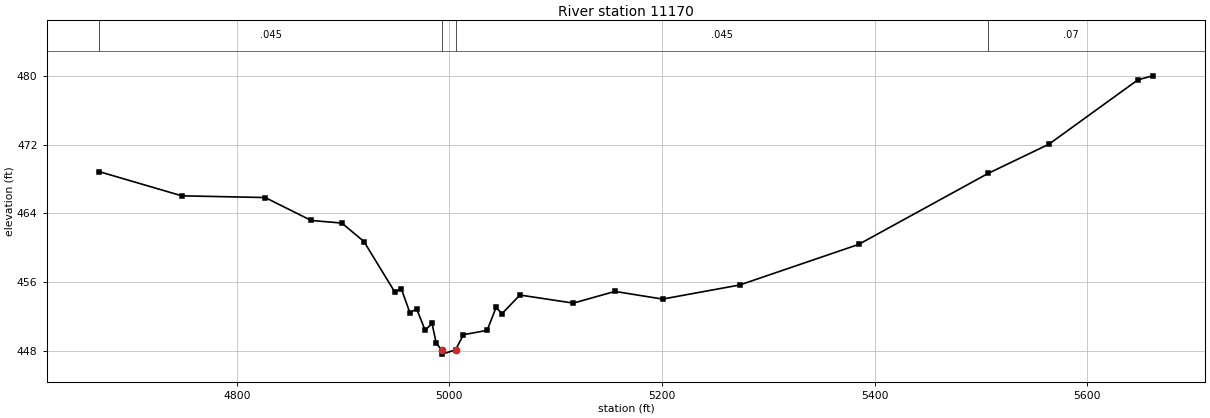
Type RM Length L Ch R = 1 ,11170   ,426,426,426
BEGIN DESCRIPTION:
CORDELL CREEK 23.0
END DESCRIPTION:
XS GIS Cut Line= 3
      2328525.02     13738374.97        2328725.       13738125.
      2329024.98     13737525.04
#Sta/Elev= 30
  4670.7  468.84  4748.3  466.03  4826.7  465.83    4870  463.16  4898.8  462.86
  4919.6  460.71  4948.4  454.87  4954.8   455.2  4962.8  452.42  4969.2  452.86
  4977.2  450.37  4983.6  451.19  4987.6  448.87  4992.6   448.1  4993.1   447.6
  5005.8   448.1  5013.2  449.86  5035.5  450.37  5043.9  453.03  5049.5  452.31
  5066.3  454.48  5116.6  453.54  5155.7   454.9  5200.5  454.01  5273.1  455.65
  5384.9  460.37  5506.6  468.63  5563.8  472.03  5647.7  479.54  5661.6     480
#Mann= 4 ,-1 , 0
  4670.7    .045       0  4992.6    .045       0  5005.8    .045       0
  5506.6     .07       0
Bank Sta=4992.6,5005.8
XS Rating Curve= 0 ,0
Exp/Cntr=0.3,0.1