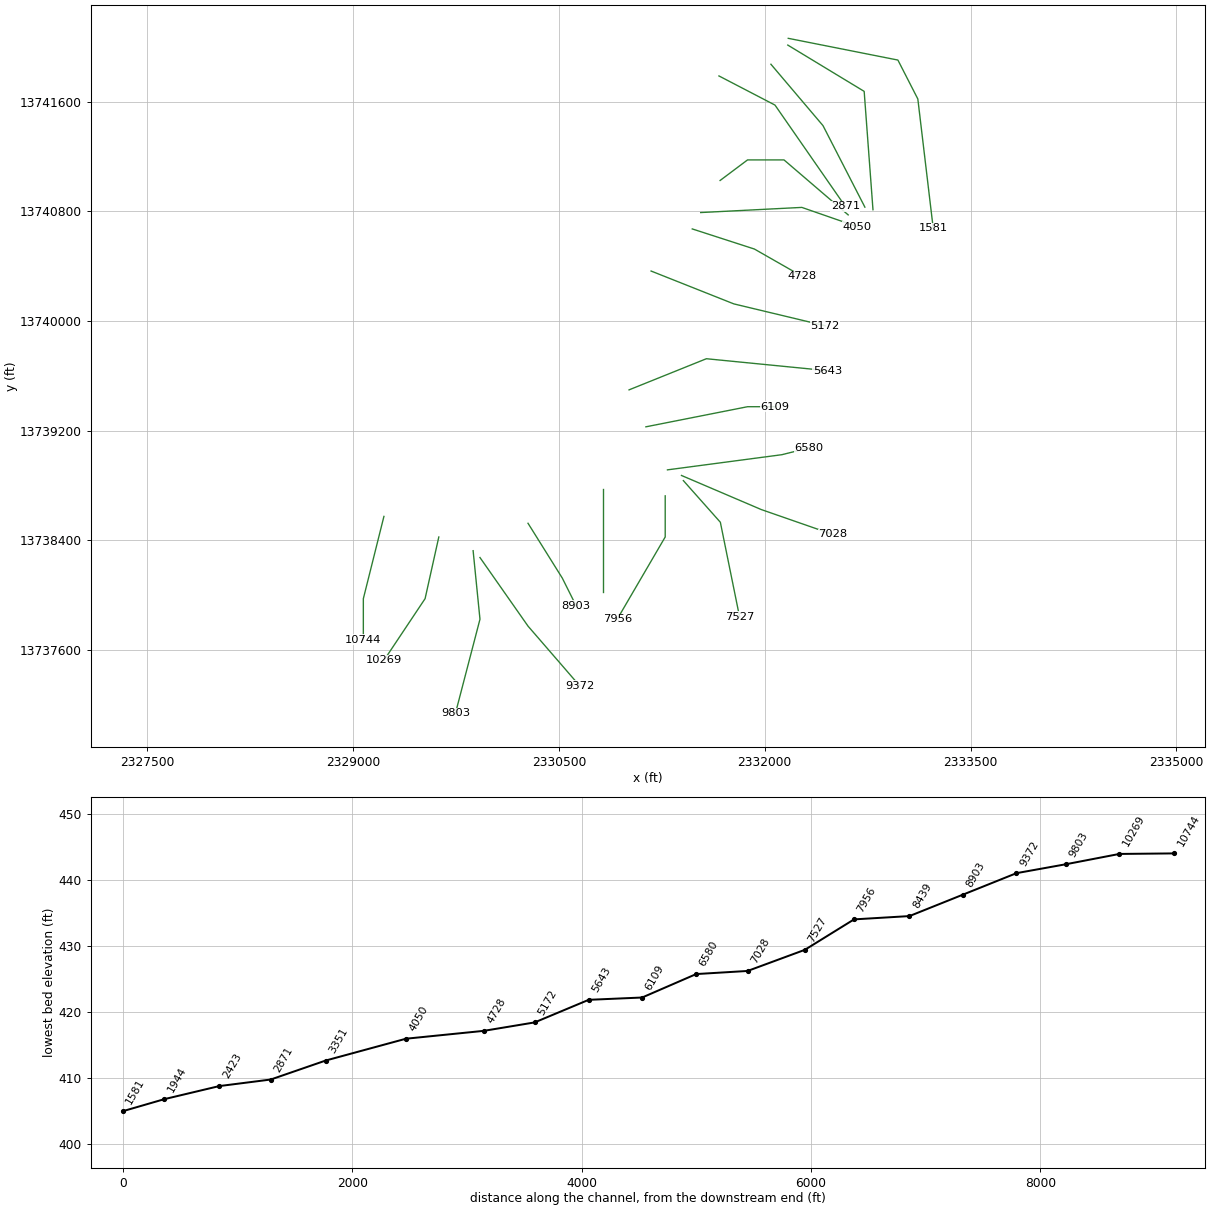
HEC-RAS study CORDELL CREEK.prj: CORDELL CREEK Base Level Engineering

--- CORDELL CREEK.g01 (geometry) --- (continued)

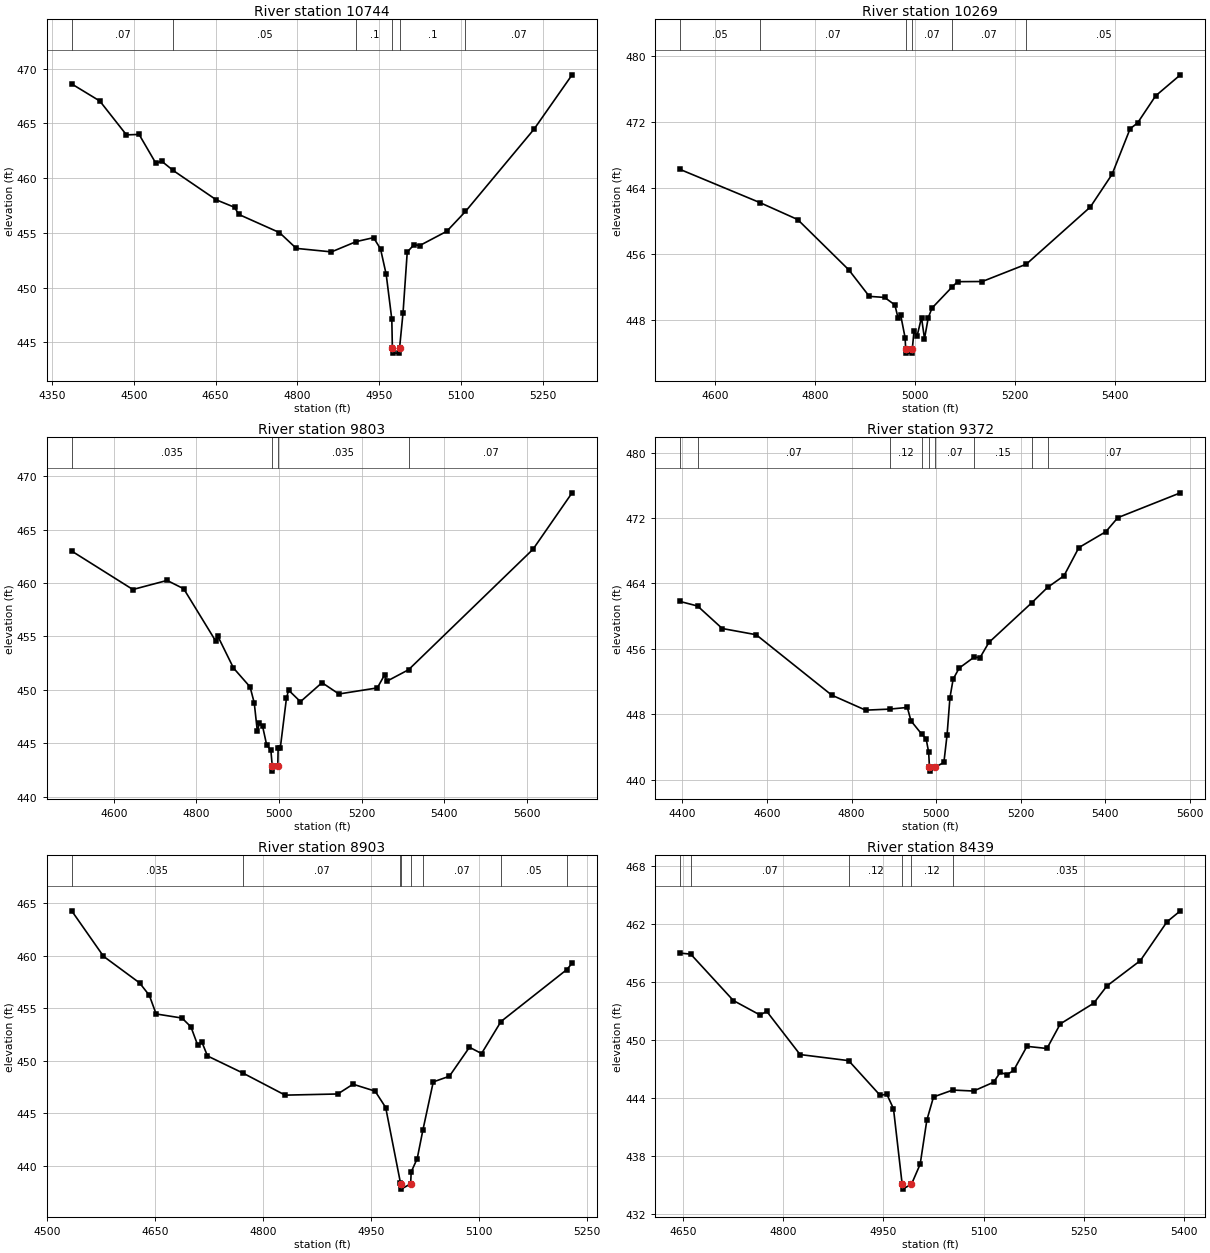
Type RM Length L Ch R = 1 ,10744   ,475,475,475
BEGIN DESCRIPTION:
CORDELL CREEK 22.0
END DESCRIPTION:
XS GIS Cut Line= 3
      2329225.01     13738575.02        2329075.       13737975.
        2329075.     13737674.99
#Sta/Elev= 30
  4385.8   468.6  4437.4  467.04  4486.3  463.95  4509.5  463.99  4540.4  461.35
  4550.7  461.56  4572.1   460.7  4651.2  458.02  4684.7  457.34  4692.5  456.69
  4767.2  455.03  4798.1  453.59  4862.6  453.27  4908.1  454.21  4939.9  454.57
  4952.7  453.54  4963.1  451.21  4973.4  447.12  4974.4  444.53  4974.9  444.03
  4987.2  444.03  4987.7  444.53    4994  447.71  5001.7  453.25  5014.3  453.94
  5024.3  453.84  5074.3  455.15  5108.6  456.96  5234.3  464.46  5304.3  469.43
#Mann= 6 ,-1 , 0
  4385.8     .07       0  4572.1     .05       0  4908.1      .1       0
  4974.4     .05       0  4987.7      .1       0  5108.6     .07       0
Bank Sta=4974.4,4987.7
XS Rating Curve= 0 ,0
Exp/Cntr=0.3,0.1

Type RM Length L Ch R = 1 ,10269   ,466,466,466
BEGIN DESCRIPTION:
CORDELL CREEK 21.0
END DESCRIPTION:
XS GIS Cut Line= 3
        2329625.     13738424.99        2329525.       13737975.
        2329225.       13737525.
#Sta/Elev= 30
  4530.1  466.22  4690.2  462.19  4765.7  460.14  4868.1  454.04  4909.1  450.83
  4939.8   450.7  4960.3  449.79  4966.7   448.2  4971.9  448.56  4980.8  445.81
  4981.9  444.45  4982.4  443.95  4994.7  443.95  4995.2  444.45  4998.6  446.66
  5004.6  445.99  5013.6  448.26  5019.6   445.7  5027.1  448.23  5034.6  449.41
  5074.3  451.93  5085.7  452.61  5135.3  452.63  5223.4  454.73  5351.6  461.66
  5395.2  465.63  5431.2  471.14  5446.3  471.86  5482.3  475.13  5531.9  477.68
#Mann= 6 ,-1 , 0
  4530.1     .05       0  4690.2     .07       0  4981.9     .05       0
  4995.2     .07       0  5074.3     .07       0  5223.4     .05       0
Bank Sta=4981.9,4995.2
XS Rating Curve= 0 ,0
Exp/Cntr=0.3,0.1

Type RM Length L Ch R = 1 ,9803    ,431,431,431
BEGIN DESCRIPTION:
CORDELL CREEK 20.0
END DESCRIPTION:
XS GIS Cut Line= 3
        2329875.     13738324.98        2329925.       13737825.
      2329746.07     13737138.41
#Sta/Elev= 30
  4497.8  462.99    4646  459.39  4728.9  460.24  4769.1  459.46    4847  454.54
    4852     455  4889.7  452.04  4929.9  450.27    4940  448.77  4947.5   446.1
  4952.5  446.88  4960.1   446.6  4970.1  444.83  4980.2  444.36  4983.5  442.89
    4984  442.39    4997  442.89  4997.8  444.51  5002.9  444.51  5017.9  449.19
  5023.1  449.97  5051.9  448.89  5104.1  450.67    5145  449.61    5238  450.18
  5255.7   451.4  5260.9   450.8  5313.7  451.88    5615  463.15  5709.8  468.44
#Mann= 4 ,-1 , 0
  4497.8    .035       0  4983.5    .035       0    4997    .035       0
  5313.7     .07       0
Bank Sta=4983.5,4997
XS Rating Curve= 0 ,0
Exp/Cntr=0.3,0.1

Type RM Length L Ch R = 1 ,9372    ,469,469,469
BEGIN DESCRIPTION:
CORDELL CREEK 19.0
END DESCRIPTION:
XS GIS Cut Line= 3
      2329924.98     13738275.03        2330275.       13737775.
      2330649.84     13737341.56
#Sta/Elev= 30
  4394.3   461.8  4435.9  461.24  4494.2  458.49  4574.4  457.73  4753.1  450.34
  4833.3   448.5  4890.7  448.63  4931.9  448.83  4940.6  447.19  4965.8  445.57
  4976.3  445.01  4982.4  443.35  4984.2  441.54  4984.7  441.04  4998.1  441.54
  5018.4   442.1    5026  445.52  5032.7  450.03  5040.3   452.3  5054.6  453.65
  5089.7  454.98  5103.9  454.93  5124.8  456.78    5226  461.63  5263.6  463.52
  5302.4  464.94  5337.6  468.39  5401.3  470.33  5429.7  472.05  5577.7  475.09
#Mann= 9 ,-1 , 0
  4394.3    .035       0  4435.9     .07       0  4890.7     .12       0
  4965.8     .07       0  4984.2     .05       0  4998.1     .07       0
  5089.7     .15       0    5226     .05       0  5263.6     .07       0
Bank Sta=4984.2,4998.1
XS Rating Curve= 0 ,0
Exp/Cntr=0.3,0.1

Type RM Length L Ch R = 1 ,8903    ,464,464,464
BEGIN DESCRIPTION:
CORDELL CREEK 18.0
END DESCRIPTION:
XS GIS Cut Line= 3
      2330275.01     13738524.98        2330525.       13738125.
      2330625.01     13737924.99
#Sta/Elev= 30
  4533.9  464.27  4578.1  459.94  4628.2  457.41  4641.8  456.22  4651.2  454.45
  4687.2  454.06  4699.6  453.22    4709  451.48  4714.9  451.76  4722.6  450.45
  4771.3  448.84  4830.5  446.72  4903.6  446.83  4924.8  447.76  4955.5   447.1
  4970.2  445.54  4990.7  438.37    4991  438.27  4991.5  437.77  5004.9  438.27
  5005.6   439.4    5014  440.68  5021.9   443.4  5036.3  447.98  5058.7  448.52
  5086.6  451.28  5103.4  450.68  5130.4  453.73  5221.6  458.66  5229.2  459.27
#Mann= 8 ,-1 , 0
  4533.9    .035       0  4771.3     .07       0  4990.7     .12       0
    4991     .05       0  5004.9     .12       0  5021.9     .07       0
  5130.4     .05       0  5221.6     .07       0
Bank Sta=4991,5004.9
XS Rating Curve= 0 ,0
Exp/Cntr=0.3,0.1

Type RM Length L Ch R = 1 ,8439    ,483,483,483
BEGIN DESCRIPTION:
CORDELL CREEK 17.0
END DESCRIPTION:
XS GIS Cut Line= 3
        2330825.     13738774.96        2330825.       13738425.
        2330825.     13738024.96
#Sta/Elev= 30
    4645  459.01  4661.1   458.9    4725  454.09    4765  452.59    4775  452.97
    4825  448.49  4897.8  447.86    4945  444.26    4955  444.38    4965  442.87
    4978  435.04  4978.5  434.54  4991.9  435.04    5005  437.13    5015   441.7
    5025   444.1  5053.8  444.81    5085  444.71    5115  445.62    5125  446.65
    5135   446.4    5145  446.84    5165  449.34    5195  449.12    5215  451.67
    5265  453.81    5285  455.61    5335  458.23    5375  462.26    5395  463.39
#Mann= 6 ,-1 , 0
    4645    .035       0  4661.1     .07       0  4897.8     .12       0
    4978     .05       0  4991.9     .12       0  5053.8    .035       0
Bank Sta=4978,4991.9
XS Rating Curve= 0 ,0
Exp/Cntr=0.3,0.1

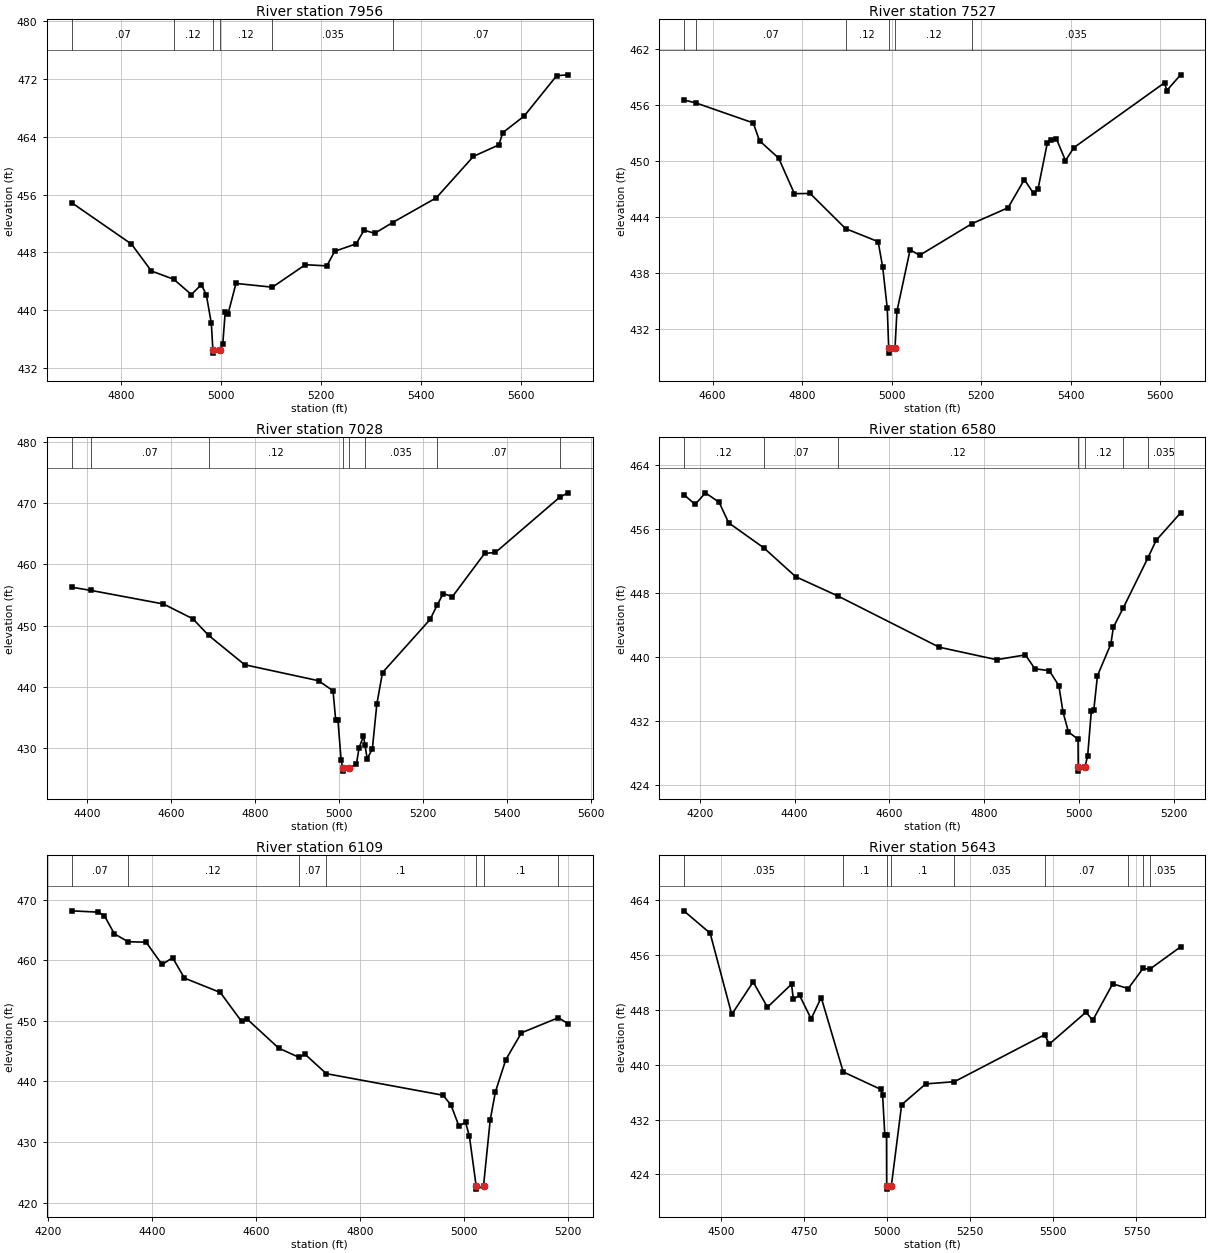
Type RM Length L Ch R = 1 ,7956    ,429,429,429
BEGIN DESCRIPTION:
CORDELL CREEK 16.0
END DESCRIPTION:
XS GIS Cut Line= 3
        2331275.     13738724.97        2331275.       13738425.
      2330924.99     13737824.99
#Sta/Elev= 30
    4700  454.88    4820  449.14    4860  445.41  4904.9  444.26    4940  442.15
    4960  443.53    4970  442.09    4980  438.15    4983  434.54  4983.5  434.04
    4997  434.54  5002.9  435.33  5007.8  439.75  5013.6  439.51  5029.3  443.69
  5102.2  443.17  5168.2  446.28  5211.2  446.12    5227  448.14    5270  449.17
  5285.7  451.06  5307.2  450.63  5342.9  452.12  5430.4  455.54  5504.8  461.28
  5555.7  462.87  5563.5  464.56  5606.5  466.87  5671.4  472.45  5694.6  472.57
#Mann= 6 ,-1 , 0
    4700     .07       0  4904.9     .12       0    4983     .05       0
    4997     .12       0  5102.2    .035       0  5342.9     .07       0
Bank Sta=4983,4997
XS Rating Curve= 0 ,0
Exp/Cntr=0.3,0.1

Type RM Length L Ch R = 1 ,7527    ,499,499,499
BEGIN DESCRIPTION:
CORDELL CREEK 15.0
END DESCRIPTION:
XS GIS Cut Line= 3
      2331407.35       13738836.      2331676.88     13738532.35
      2331816.78     13737843.12
#Sta/Elev= 30
  4535.9  456.55  4562.8  456.23  4690.8  454.09    4705  452.17  4747.6  450.32
  4782.8  446.51    4818  446.53    4897  442.77  4969.8  441.37    4980  438.63
  4990.2  434.22  4993.4  429.93  4993.9  429.43  5007.4  429.93  5011.8  433.92
  5041.2   440.5  5062.4  439.91  5179.4   443.3  5259.9     445  5296.3  448.02
  5316.8  446.54    5327  447.04  5347.4  451.89  5356.1  452.27  5367.8   452.4
  5388.2  450.05  5406.8  451.44  5609.4  458.39  5614.5  457.56  5645.2  459.24
#Mann= 6 ,-1 , 0
  4535.9     .12       0  4562.8     .07       0    4897     .12       0
  4993.4     .05       0  5007.4     .12       0  5179.4    .035       0
Bank Sta=4993.4,5007.4
XS Rating Curve= 0 ,0
Exp/Cntr=0.3,0.1

Type RM Length L Ch R = 1 ,7028    ,448,448,448
BEGIN DESCRIPTION:
CORDELL CREEK 14.0
END DESCRIPTION:
XS GIS Cut Line= 3
      2331393.65     13738873.57        2331975.       13738625.
      2332495.77     13738443.64
#Sta/Elev= 30
  4361.9  456.26  4408.1  455.74  4580.9  453.52  4651.2   451.1  4688.4  448.41
  4774.6   443.6  4950.6  440.99  4985.1  439.35  4991.4  434.61  4996.8  434.61
  5004.4     428  5008.3  426.73  5008.8  426.23  5022.4  426.73  5040.8  427.36
  5047.1  430.02  5057.7  431.95  5061.1  430.53  5066.6  428.23  5078.9   429.9
  5089.5   437.2    5103  442.32  5216.5     451  5233.2  453.34  5247.8  455.23
  5269.5  454.71  5346.4  461.78  5372.1  461.93  5525.8  470.98  5545.6  471.67
#Mann= 8 ,-1 , 0
  4361.9     .12       0  4408.1     .07       0  4688.4     .12       0
  5008.3     .05       0  5022.4     .12       0  5061.1    .035       0
  5233.2     .07       0  5525.8    .035       0
Bank Sta=5008.3,5022.4
XS Rating Curve= 0 ,0
Exp/Cntr=0.3,0.1

Type RM Length L Ch R = 1 ,6580    ,471,471,471
BEGIN DESCRIPTION:
CORDELL CREEK 13.0
END DESCRIPTION:
XS GIS Cut Line= 3
      2331291.31      13738914.5        2332125.       13739025.
      2332324.97     13739074.99
#Sta/Elev= 30
  4166.5  460.33  4190.4   459.1    4212  460.55  4240.8  459.37    4261   456.8
  4335.3  453.66  4402.2  450.07  4492.4  447.62  4704.9  441.25  4825.9  439.69
  4886.4  440.29  4906.6  438.55  4936.9  438.32    4957  436.44  4965.8  433.14
  4977.2  430.65  4997.4  429.75  4997.9  426.26  4998.4  425.76    5012  426.26
  5017.8  427.71  5025.5   433.3  5030.7  433.42  5038.4  437.69  5066.7  441.66
  5071.9  443.74  5092.2  446.09  5144.4  452.38  5162.1  454.61  5213.6  458.04
#Mann= 7 ,-1 , 0
  4166.5     .12       0  4335.3     .07       0  4492.4     .12       0
  4997.9     .05       0    5012     .12       0  5092.2     .07       0
  5144.4    .035       0
Bank Sta=4997.9,5012
XS Rating Curve= 0 ,0
Exp/Cntr=0.3,0.1

Type RM Length L Ch R = 1 ,6109    ,466,466,466
BEGIN DESCRIPTION:
CORDELL CREEK 12.0
END DESCRIPTION:
XS GIS Cut Line= 3
      2331134.32      13739228.4        2331875.       13739375.
      2332074.95       13739375.
#Sta/Elev= 30
  4244.9  468.18  4296.6  467.96  4308.3  467.36  4327.1   464.4  4353.4  463.08
  4388.3     463  4418.9  459.32  4439.3  460.43    4462  457.07    4531  454.69
  4571.8  449.92    4582  450.34  4643.2   445.5  4681.9     444  4694.1  444.47
  4734.8  441.28  4959.2  437.72  4974.3  436.13  4989.8  432.62  5002.4  433.27
  5009.9  430.93  5022.9  422.71  5023.4  422.21    5037  422.71  5049.9  433.65
  5059.9  438.29  5079.9   443.6  5109.9  448.03  5181.1  450.53  5199.9  449.51
#Mann= 7 ,-1 , 0
  4244.9     .07       0  4353.4     .12       0  4681.9     .07       0
  4734.8      .1       0  5022.9     .05       0    5037      .1       0
  5181.1     .07       0
Bank Sta=5022.9,5037
XS Rating Curve= 0 ,0
Exp/Cntr=0.3,0.1

Type RM Length L Ch R = 1 ,5643    ,471,471,471
BEGIN DESCRIPTION:
CORDELL CREEK 11.0
END DESCRIPTION:
XS GIS Cut Line= 3
      2331011.55     13739497.97        2331575.       13739725.
      2332458.24     13739637.86
#Sta/Elev= 30
  4387.8  462.48    4467  459.21    4532  447.36  4596.4   452.1  4639.5  448.41
  4711.9  451.78  4717.3  449.59  4736.1  450.14    4771  446.71  4801.2  449.82
  4867.5  438.97  4980.5  436.42  4985.9  435.66  4992.6  429.81  4997.8  429.81
  4998.2  422.36  4998.7  421.86  5012.4  422.36  5043.3  434.18  5115.9  437.22
  5202.1  437.54  5473.8   444.4  5487.6  443.03  5598.2  447.69  5618.3  446.49
  5678.6  451.83  5725.1  451.13  5769.9  454.08  5789.5  453.94  5882.8  457.22
#Mann= 9 ,-1 , 0
  4387.8    .035       0  4867.5      .1       0  4998.2     .05       0
  5012.4      .1       0  5202.1    .035       0  5473.8     .07       0
  5725.1    .035       0  5769.9     .07       0  5789.5    .035       0
Bank Sta=4998.2,5012.4
XS Rating Curve= 0 ,0
Exp/Cntr=0.3,0.1

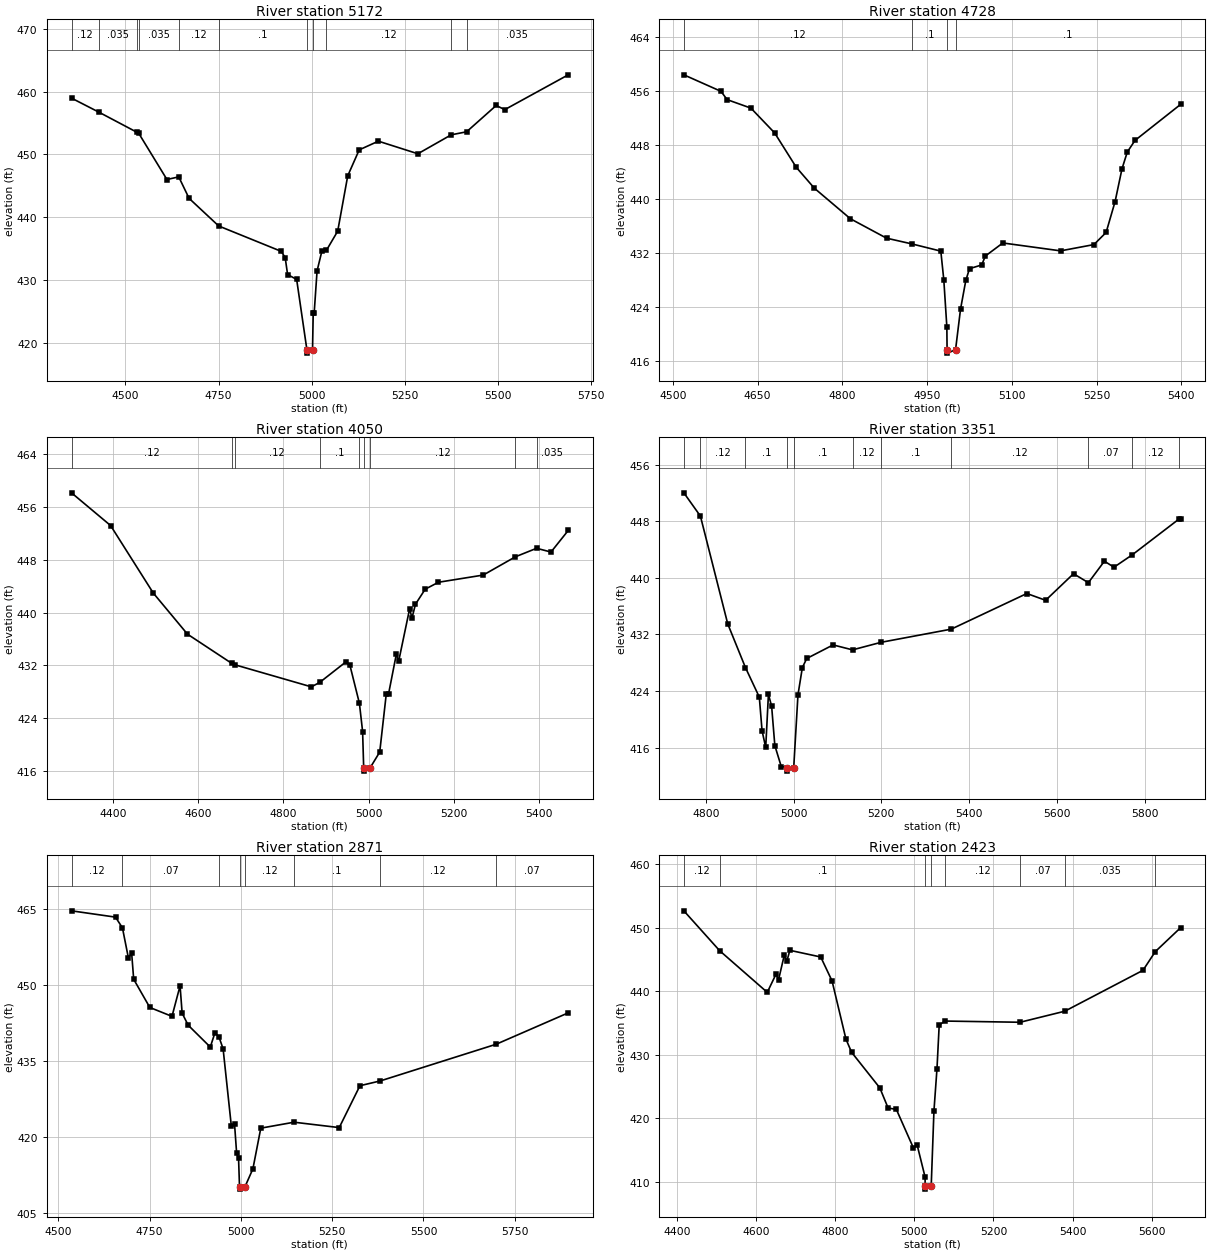
Type RM Length L Ch R = 1 ,5172    ,444,444,444
BEGIN DESCRIPTION:
CORDELL CREEK 10.0
END DESCRIPTION:
XS GIS Cut Line= 3
      2331171.91     13740364.62        2331775.       13740125.
      2332440.62     13739965.55
#Sta/Elev= 30
  4355.2  458.95  4428.7  456.72  4530.7  453.53  4535.9  453.34  4611.4  446.02
  4643.1  446.44  4670.8  443.03  4750.3  438.64  4918.1  434.61  4928.8  433.62
  4935.3  430.92  4959.6  430.15  4987.2  418.94  4987.7  418.44  5002.2  418.94
  5004.1  424.88  5006.7  424.88  5014.4   431.5  5027.7  434.74  5039.3  434.75
  5069.8  437.82  5096.7   446.6  5127.5  450.73    5179  452.11    5285  450.11
  5374.5  453.12  5415.8   453.6  5495.2  457.78  5518.3  457.12  5688.6  462.65
#Mann= 11 ,-1 , 0
  4355.2     .12       0  4428.7    .035       0  4530.7     .12       0
  4535.9    .035       0  4643.1     .12       0  4750.3      .1       0
  4987.2     .05       0  5002.2      .1       0  5039.3     .12       0
  5374.5      .1       0  5415.8    .035       0
Bank Sta=4987.2,5002.2
XS Rating Curve= 0 ,0
Exp/Cntr=0.3,0.1

Type RM Length L Ch R = 1 ,4728    ,678,678,678
BEGIN DESCRIPTION:
CORDELL CREEK 9.0
END DESCRIPTION:
XS GIS Cut Line= 3
      2331472.12     13740671.72        2331925.       13740525.
      2332275.03     13740324.98
#Sta/Elev= 30
  4519.6  458.44  4585.3  455.99  4596.2  454.76  4638.3   453.5  4680.3  449.82
  4718.5  444.73  4750.5  441.63  4814.4  437.09  4878.4  434.21  4923.7  433.35
  4974.4  432.29  4979.7  428.03  4985.1  421.05  4985.5  417.66    4986  417.16
  5000.5  417.66  5009.3  423.68  5018.7  427.96  5025.2  429.69  5046.8  430.24
  5053.2  431.56  5084.2   433.5  5186.4  432.33  5245.4  433.26    5267  435.06
  5282.9  439.65  5295.1   444.5  5304.5  446.99  5318.1  448.71  5398.8  454.05
#Mann= 4 ,-1 , 0
  4519.6     .12       0  4923.7      .1       0  4985.5     .05       0
  5000.5      .1       0
Bank Sta=4985.5,5000.5
XS Rating Curve= 0 ,0
Exp/Cntr=0.3,0.1

Type RM Length L Ch R = 1 ,4050    ,699,699,699
BEGIN DESCRIPTION:
CORDELL CREEK 8.0
END DESCRIPTION:
XS GIS Cut Line= 3
      2331533.54     13740791.13      2332270.58     13740828.66
      2332673.18     13740688.78
#Sta/Elev= 30
  4303.3  458.17  4394.9  453.21    4495  442.97  4575.1  436.74  4679.1   432.3
  4686.6  432.09  4865.5  428.75    4885  429.42  4945.6  432.49  4955.6  432.09
  4978.1  426.25  4985.6  421.97  4988.1  416.47  4988.6  415.97  5003.2  416.47
  5025.7  418.86    5041  427.64  5046.3  427.64  5064.8  433.75  5070.1  432.63
  5095.9  440.62  5101.2  439.16  5109.5  441.28  5132.3  443.56  5163.4  444.61
  5268.3   445.7  5343.7  448.47  5393.4  449.76  5427.1  449.19  5467.5  452.46
#Mann= 9 ,-1 , 0
  4303.3     .12       0  4679.1      .1       0  4686.6     .12       0
    4885      .1       0  4978.1     .12       0  4988.1     .05       0
  5003.2     .12       0  5343.7     .07       0  5393.4    .035       0
Bank Sta=4988.1,5003.2
XS Rating Curve= 0 ,0
Exp/Cntr=0.3,0.1

Type RM Length L Ch R = 1 ,3351    ,480,480,480
BEGIN DESCRIPTION:
CORDELL CREEK 7.0
END DESCRIPTION:
XS GIS Cut Line= 4
      2331674.98     13741024.98        2331875.       13741175.
      2332140.92       13741175.      2332608.39     13740774.06
#Sta/Elev= 30
    4750  452.03  4787.7  448.74    4850  433.49  4890.3  427.32  4921.9  423.14
  4928.2  418.37  4936.5  416.02  4942.7  423.54    4950  421.84  4957.3  416.28
  4971.9  413.32  4985.2  413.17  4985.7  412.67  5000.3  413.17    5010  423.46
    5020  427.32    5030   428.6    5090  430.52  5134.3  429.82  5199.5  430.89
  5359.2  432.75  5531.5  437.79  5574.3  436.83  5637.9  440.59  5671.7  439.32
  5708.2  442.36  5730.1  441.51  5772.1  443.28  5878.4  448.33  5881.8  448.33
#Mann= 11 ,-1 , 0
    4750      .1       0  4787.7     .12       0  4890.3      .1       0
  4985.2     .05       0  5000.3      .1       0  5134.3     .12       0
  5199.5      .1       0  5359.2     .12       0  5671.7     .07       0
  5772.1     .12       0  5878.4    .035       0
Bank Sta=4985.2,5000.3
XS Rating Curve= 0 ,0
Exp/Cntr=0.3,0.1

Type RM Length L Ch R = 1 ,2871    ,448,448,448
BEGIN DESCRIPTION:
CORDELL CREEK 6.0
END DESCRIPTION:
XS GIS Cut Line= 3
      2331666.66     13741787.45        2332075.       13741575.
      2332587.92     13740835.47
#Sta/Elev= 30
  4536.1  464.56  4656.6  463.32  4675.6  461.21    4692  455.26  4700.8  456.26
  4706.4  451.09  4750.6  445.54  4811.3  443.79  4833.4   449.8  4839.1  444.42
  4855.5  442.06  4916.2  437.75  4928.8  440.54  4939.6  439.82  4951.3  437.39
  4973.9  422.14  4982.5   422.7  4988.2  416.98  4993.6  415.86  4996.2  410.29
  4996.7  409.79  5011.4  410.29  5032.9  413.79  5054.5  421.79  5145.6  422.96
  5269.3   421.9    5326  430.14  5381.9  431.09  5699.3  438.31  5896.4  444.48
#Mann= 8 ,-1 , 0
  4536.1     .12       0  4675.6     .07       0  4939.6     .12       0
  4996.2     .05       0  5011.4     .12       0  5145.6      .1       0
  5381.9     .12       0  5699.3     .07       0
Bank Sta=4996.2,5011.4
XS Rating Curve= 0 ,0
Exp/Cntr=0.3,0.1

Type RM Length L Ch R = 1 ,2423    ,479,479,479
BEGIN DESCRIPTION:
CORDELL CREEK 5.0
END DESCRIPTION:
XS GIS Cut Line= 3
      2332045.39     13741872.75        2332425.       13741425.
      2332730.26      13740830.5
#Sta/Elev= 30
  4417.8  452.63  4508.4  446.34  4628.6  439.79  4650.6  442.65  4657.1  441.78
  4671.4   445.6    4678   444.7  4685.7  446.41  4763.7  445.36  4792.3  441.59
  4827.4  432.43  4841.7  430.35    4913  424.75    4934  421.57  4954.8  421.36
  4997.7  415.31  5007.6  415.69  5027.3  410.73  5027.7   409.3  5028.2   408.8
  5042.9   409.3  5049.8  421.11  5057.5  427.78  5063.1  434.67    5078  435.27
  5267.5  435.08  5380.5  436.82  5578.1  443.26  5609.1   446.2  5673.1  449.97
#Mann= 8 ,-1 , 0
  4417.8     .12       0  4508.4      .1       0  5027.7     .05       0
  5042.9      .1       0    5078     .12       0  5267.5     .07       0
  5380.5    .035       0  5609.1     .12       0
Bank Sta=5027.7,5042.9
XS Rating Curve= 0 ,0
Exp/Cntr=0.3,0.1

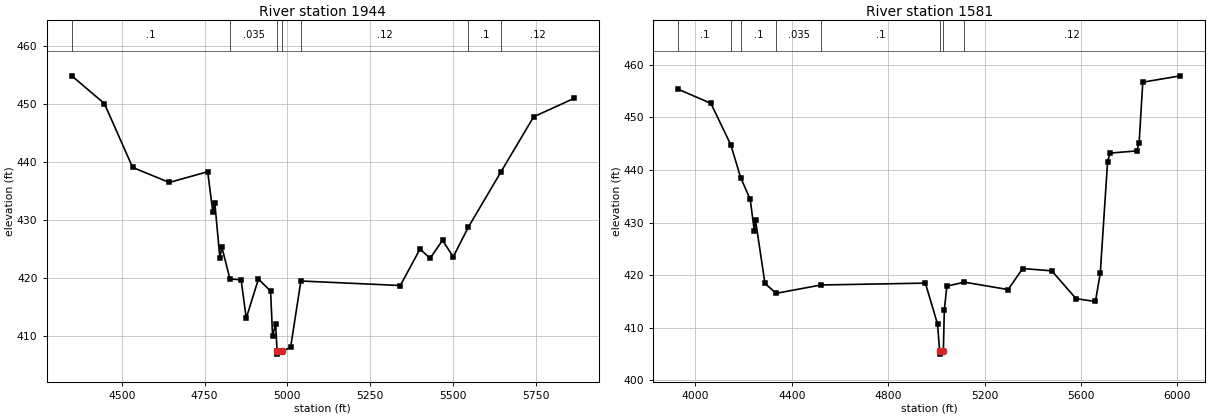
Type RM Length L Ch R = 1 ,1944    ,363,363,363
BEGIN DESCRIPTION:
CORDELL CREEK 4.0
END DESCRIPTION:
XS GIS Cut Line= 3
      2332168.23     13742012.64        2332725.       13741675.
      2332789.21     13740811.63
#Sta/Elev= 30
  4348.9  454.92  4447.5  450.12  4532.8  439.09  4643.3  436.49  4759.6  438.34
  4775.1  431.35    4781  432.99  4796.5  423.38  4802.3  425.33  4826.8   419.8
  4860.5  419.68    4876  413.03  4912.8  419.79  4949.6  417.71  4955.5     410
    4965  411.95  4969.2  407.32  4969.7  406.82  4984.4  407.32  5010.1  407.99
  5041.1  419.46  5341.6  418.68  5401.2     425  5431.2  423.36  5469.1  426.49
  5501.4  423.64  5547.2  428.78  5645.7  438.33  5744.4  447.84  5865.8  451.01
#Mann= 7 ,-1 , 0
  4348.9      .1       0  4826.8    .035       0  4969.2     .05       0
  4984.4    .035       0  5041.1     .12       0  5547.2      .1       0
  5645.7     .12       0
Bank Sta=4969.2,4984.4
XS Rating Curve= 0 ,0
Exp/Cntr=0.3,0.1

Type RM Length L Ch R = 1 ,1581    ,0,0,0
BEGIN DESCRIPTION:
CORDELL CREEK 3.0
END DESCRIPTION:
XS GIS Cut Line= 4
      2332171.88     13742061.76      2332970.84     13741903.29
      2333116.11     13741619.35      2333228.37     13740675.07
#Sta/Elev= 30
  3928.5  455.32  4064.2  452.63  4146.9  444.74  4187.7  438.53  4227.3   434.4
  4244.3  428.45  4249.4   430.4  4288.5  418.43  4334.8  416.54  4521.1  418.13
  4954.5  418.48  5004.9  410.72  5013.9  405.49  5014.4  404.99  5029.1  405.49
  5033.2  413.38  5043.7  417.91  5116.6  418.66    5298  417.26  5358.4  421.25
  5479.2  420.82  5579.9  415.53  5660.5  414.99  5680.6   420.4  5710.9   441.5
  5720.9  443.19  5831.7   443.6  5841.8  445.07  5857.1  456.66  6012.9  457.87
#Mann= 8 ,-1 , 0
  3928.5      .1       0  4146.9     .12       0  4187.7      .1       0
  4334.8    .035       0  4521.1      .1       0  5013.9     .05       0
  5029.1      .1       0  5116.6     .12       0
Bank Sta=5013.9,5029.1
XS Rating Curve= 0 ,0
Exp/Cntr=0.3,0.1

Chan Stop Cuts=-1
Use User Specified Reach Order=0
Composite Channel Slope=5