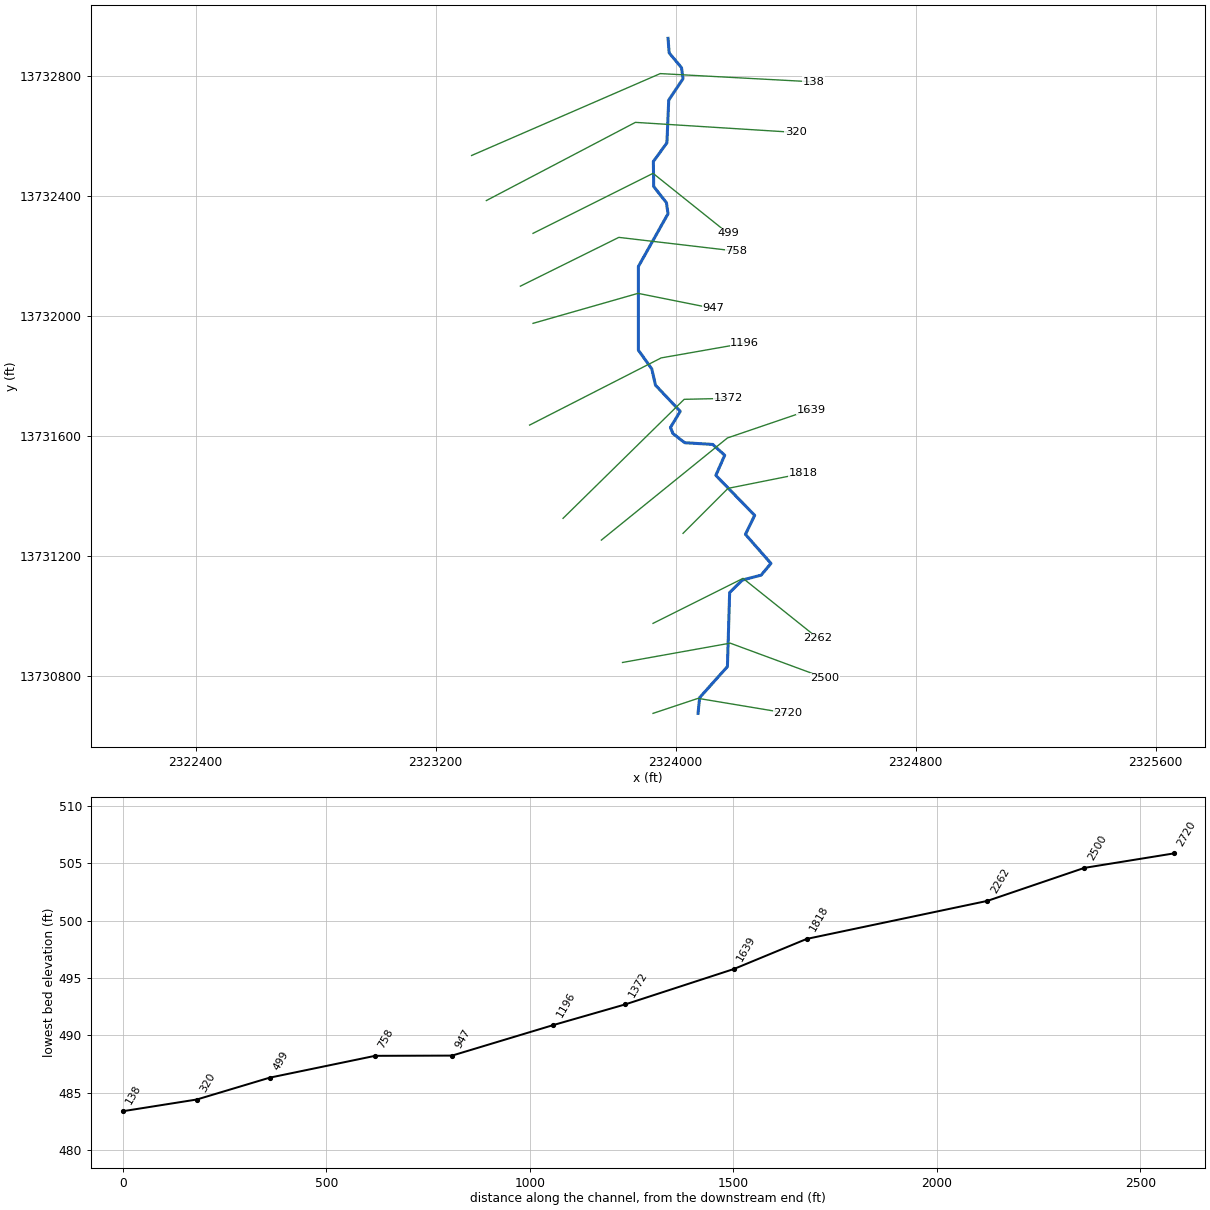
--- CORDELL TRIBUTARY 1.prj (project) ---

Proj Title=CORDELL TRIBUTARY 1 Base Level Engineering
Current Plan=p01
Default Exp/Contr=0.3,0.1
English Units
Geom File=g01
Flow File=f01
Plan File=p01
BEGIN DESCRIPTION:
CORDELL TRIBUTARY 1
END DESCRIPTION:

--- CORDELL TRIBUTARY 1.p01 (plan) ---

Plan Title=Multiple Run
Short Identifier=Multiple
Geom File=g01
Flow File=f01
Subcritical Flow
K Sum by GR= 0
Std Step Tol= 0.01
Critical Tol= 0.01
Num of Std Step Trials= 20
Max Error Tol= 0.3
Flow Tol Ratio= 0.001
Split Flow NTrial= 30
Split Flow Tol= 0.02
Split Flow Ratio= 0.02
Log Output Level= 0
Friction Slope Method= 1
Unsteady Friction Slope Method= 2
Unsteady Bridges Friction Slope Method= 1
Parabolic Critical Depth
Global Vel Dist=  1 , 1 , 1
Global Log Level= 0
CheckData=True
Encroach Param= -1, 0, 0, 0
BEGIN DESCRIPTION:
Multiple Run
END DESCRIPTION:

--- CORDELL TRIBUTARY 1.f01 (steady flow) ---

Flow Title=Multiple
Number of Profiles=7
Profile Names=10-year,25-year,50-year,1pct_min,100-year,1pct_plu,500-year
River Rch & RM= CORDELL TRIBUTAR,Reach-1,2720
     936    1565    2156    1438    2869    5725    5037
Boundary for River Rch & Prof#=CORDELL TRIBUTAR,Reach-1,1
Up Type=0
Dn Type=3
Dn Slope=0.005
Boundary for River Rch & Prof#=CORDELL TRIBUTAR,Reach-1,2
Up Type=0
Dn Type=3
Dn Slope=0.005
Boundary for River Rch & Prof#=CORDELL TRIBUTAR,Reach-1,3
Up Type=0
Dn Type=3
Dn Slope=0.005
Boundary for River Rch & Prof#=CORDELL TRIBUTAR,Reach-1,4
Up Type=0
Dn Type=3
Dn Slope=0.005
Boundary for River Rch & Prof#=CORDELL TRIBUTAR,Reach-1,5
Up Type=0
Dn Type=3
Dn Slope=0.005
Boundary for River Rch & Prof#=CORDELL TRIBUTAR,Reach-1,6
Up Type=0
Dn Type=3
Dn Slope=0.005
Boundary for River Rch & Prof#=CORDELL TRIBUTAR,Reach-1,7
Up Type=0
Dn Type=3
Dn Slope=0.005

--- CORDELL TRIBUTARY 1.g01 (geometry) ---

Geom Title=Existing Conditions

River Reach=CORDELL TRIBUTAR,Reach-1
Reach XY= 30
      2324075.00     13730675.00      2324080.33     13730727.51
      2324172.94     13730830.85      2324180.36     13731077.70
      2324222.48     13731119.26      2324285.41     13731135.79
      2324317.99     13731174.79      2324233.03     13731271.67
      2324263.76     13731335.00      2324134.31     13731468.34
      2324163.91     13731535.37      2324123.96     13731571.39
      2324030.51     13731577.15      2323991.20     13731607.88
      2323983.07     13731628.13      2324015.68     13731681.65
      2323933.18     13731768.94      2323920.78     13731823.25
      2323876.20     13731885.50      2323876.20     13732164.50
      2323974.92     13732340.39      2323969.62     13732377.18
      2323927.19     13732430.97      2323926.10     13732514.45
      2323971.21     13732576.57      2323977.29     13732719.07
      2324024.95     13732790.39      2324019.88     13732827.25
      2323978.69     13732876.49      2323975.00     13732925.00

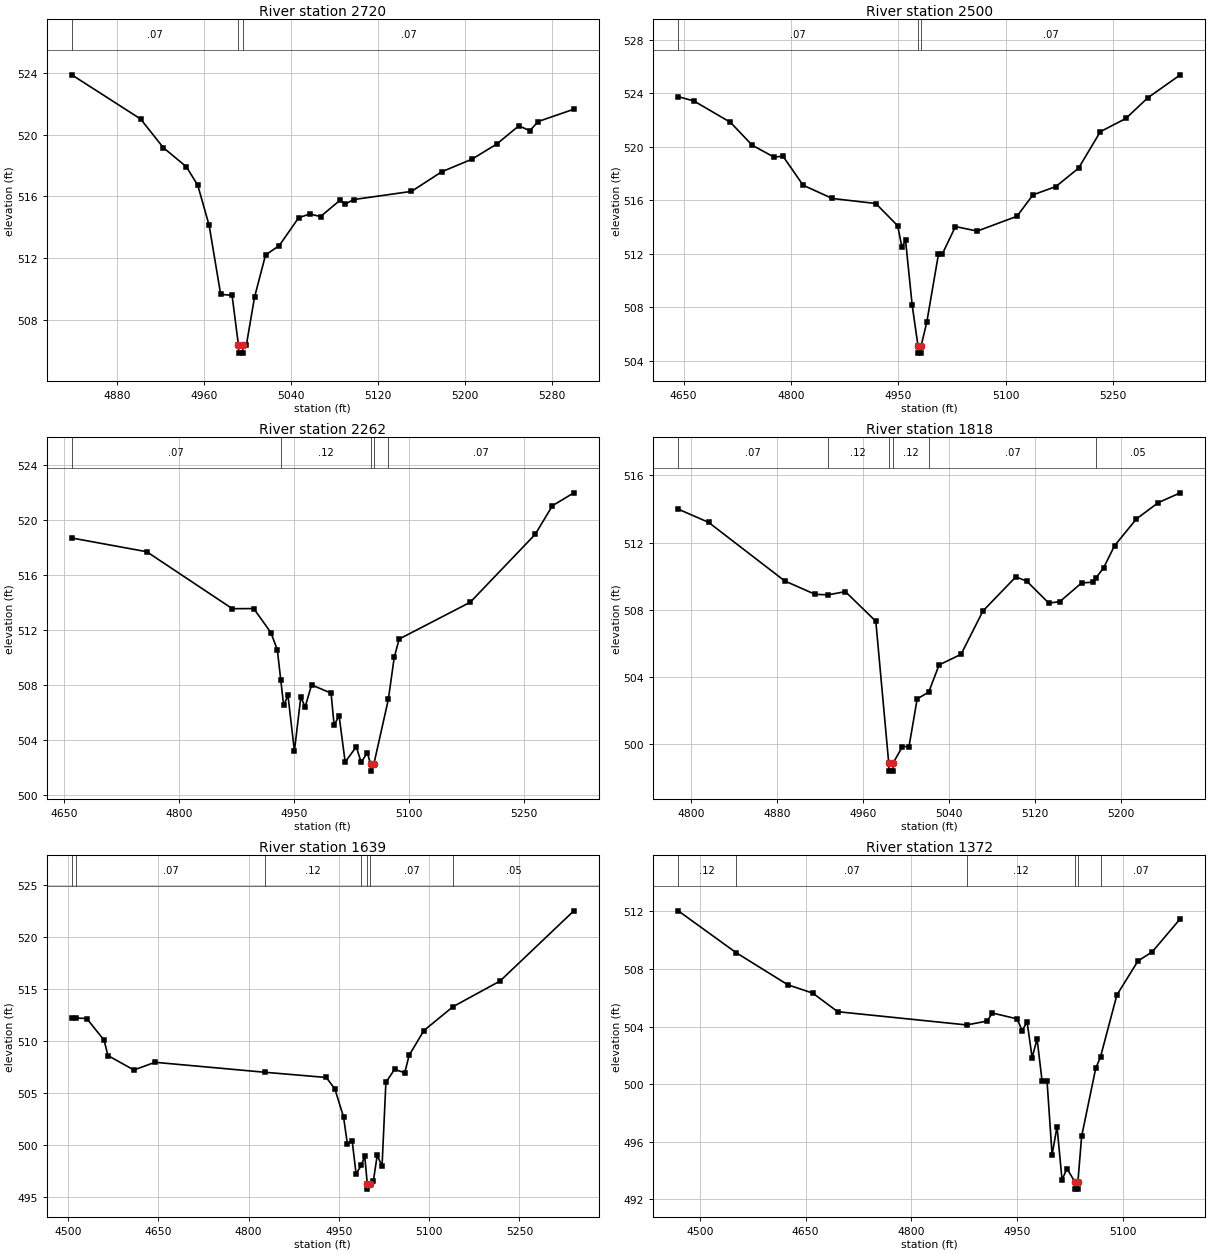
Type RM Length L Ch R = 1,2720,220,220,220
BEGIN DESCRIPTION:
CORDELL TRIBUTARY 1 6.0
END DESCRIPTION:
XS GIS Cut Line= 3
      2323924.95     13730674.98      2324075.00     13730725.00
      2324375.00     13730675.00
#Sta/Elev= 30
  4838.1  523.89  4901.4  521.03  4922.5  519.16  4943.6  517.93  4954.1  516.73
  4964.6  514.12  4975.2  509.65  4985.7  509.59  4991.6  506.34  4991.8  505.84
  4995.4  505.84  4995.7  506.34  4998.8  506.34  5006.4  509.47  5016.5  512.20
  5029.2  512.82  5047.0  514.62  5057.1  514.86  5067.2  514.70  5085.0  515.75
  5090.0  515.51  5097.6  515.80  5150.9  516.33  5178.7  517.60  5206.6  518.42
  5229.4  519.40  5249.7  520.58  5259.9  520.27  5267.5  520.86  5300.4  521.66
#Mann=3,-1,0
  4838.1    0.07       0  4991.6    0.05       0  4995.7    0.07       0
Bank Sta=4991.6,4995.7
Exp/Cntr=0.3,0.1

Type RM Length L Ch R = 1,2500,238,238,238
BEGIN DESCRIPTION:
X18541
END DESCRIPTION:
XS GIS Cut Line= 3
      2323823.29     13730844.65      2324182.14     13730909.06
      2324498.05     13730792.51
#Sta/Elev= 30
  4642.5  523.75  4664.6  523.42  4715.4  521.83  4745.8  520.12  4776.3  519.23
  4788.8  519.30  4816.9  517.13  4857.6  516.14  4918.5  515.76  4949.0  514.10
  4954.9  512.50  4960.0  513.02  4969.3  508.15  4977.5  505.08  4977.7  504.58
  4981.3  504.58  4981.6  505.08  4989.7  506.90  5006.0  511.98  5011.3  511.98
  5029.7  514.04  5060.1  513.70  5115.7  514.81  5138.0  516.41  5170.0  517.03
  5201.6  518.40  5232.1  521.13  5267.8  522.12  5298.3  523.66  5343.8  525.38
#Mann=3,-1,0
  4642.5    0.07       0  4977.5    0.05       0  4981.6    0.07       0
Bank Sta=4977.5,4981.6
Exp/Cntr=0.3,0.1

Type RM Length L Ch R = 1,2262,444,444,444
BEGIN DESCRIPTION:
CORDELL TRIBUTARY 1 5.0
END DESCRIPTION:
XS GIS Cut Line= 3
      2323924.98     13730974.99      2324225.00     13731125.00
      2324475.01     13730924.99
#Sta/Elev= 30
  4659.6  518.69  4757.5  517.69  4869.3  513.54  4897.2  513.55  4919.6  511.80
  4928.0  510.55  4932.5  508.35  4936.3  506.49  4941.9  507.23  4950.3  503.17
  4958.7  507.12  4964.3  506.37  4972.7  507.99  4998.2  507.39  5002.2  505.04
  5008.6  505.76  5016.6  502.37  5031.1  503.48  5037.5  502.35  5045.5  503.06
  5049.8  502.21  5050.1  501.71  5054.0  502.21  5073.0  506.94  5080.7  510.01
  5087.1  511.33  5179.9  514.01  5264.8  518.96  5287.2  521.04  5315.2  521.98
#Mann=5,-1,0
  4659.6    0.07       0  4932.5    0.12       0  5049.8    0.05       0
  5054.0    0.12       0  5073.0    0.07       0
Bank Sta=5049.8,5054
Exp/Cntr=0.3,0.1

Type RM Length L Ch R = 1,1818,179,179,179
BEGIN DESCRIPTION:
CORDELL TRIBUTARY 1 4.0
END DESCRIPTION:
XS GIS Cut Line= 3
      2324025.01     13731275.01      2324175.00     13731425.00
      2324425.03     13731475.01
#Sta/Elev= 30
  4788.2  513.99  4816.5  513.20  4887.2  509.72  4915.5  508.92  4927.5  508.89
  4943.7  509.08  4972.0  507.32  4984.0  498.90  4984.3  498.40  4988.0  498.40
  4988.3  498.90  4996.8  499.86  5002.9  499.86  5010.5  502.70  5021.2  503.10
  5030.9  504.72  5051.3  505.35  5071.7  507.93  5102.3  509.96  5112.5  509.70
  5132.9  508.40  5143.1  508.48  5163.5  509.60  5173.7  509.64  5176.9  509.91
  5183.9  510.49  5194.1  511.81  5214.5  513.41  5234.9  514.38  5255.3  514.96
#Mann=6,-1,0
  4788.2    0.07       0  4927.5    0.12       0  4984.0    0.05       0
  4988.3    0.12       0  5021.2    0.07       0  5176.9    0.05       0
Bank Sta=4984,4988.3
Exp/Cntr=0.3,0.1

Type RM Length L Ch R = 1,1639,267,267,267
BEGIN DESCRIPTION:
X18540
END DESCRIPTION:
XS GIS Cut Line= 3
      2323752.80     13731252.58      2324172.94     13731592.98
      2324451.02     13731687.71
#Sta/Elev= 30
  4506.0  512.20  4513.0  512.24  4530.9  512.19  4559.7  510.11  4566.1  508.63
  4609.2  507.24  4644.4  507.98  4827.1  507.02  4929.0  506.52  4943.3  505.42
  4957.7  502.73  4964.1  500.12  4972.1  500.41  4978.5  497.27  4987.4  498.07
  4992.9  498.99  4997.2  496.28  4997.5  495.78  5001.5  496.28  5007.3  496.57
  5013.7  499.05  5021.7  497.97  5028.1  506.04  5042.5  507.30  5059.5  506.97
  5066.6  508.64  5091.2  511.03  5139.7  513.33  5217.9  515.80  5340.5  522.55
#Mann=7,-1,0
  4506.0    0.12       0  4513.0    0.07       0  4827.1    0.12       0
  4987.4    0.07       0  4997.2    0.05       0  5001.5    0.07       0
  5139.7    0.05       0
Bank Sta=4997.2,5001.5
Exp/Cntr=0.3,0.1

Type RM Length L Ch R = 1,1372,176,176,176
BEGIN DESCRIPTION:
CORDELL TRIBUTARY 1 3.0
END DESCRIPTION:
XS GIS Cut Line= 3
      2323625.02     13731325.02      2324028.80     13731721.79
      2324174.97     13731725.00
#Sta/Elev= 30
  4469.2  512.04  4551.4  509.13  4624.7  506.90  4660.1  506.32  4695.4  505.03
  4878.4  504.11  4907.6  504.38  4914.7  504.94  4950.0  504.53  4957.1  503.72
  4964.1  504.33  4971.3  501.83  4978.3  503.14  4985.4  500.21  4992.4  500.23
  4999.6  495.08  5006.6  497.05  5013.7  493.34  5020.7  494.13  5031.9  493.20
  5032.2  492.70  5035.9  492.70  5036.2  493.20  5041.5  496.37  5061.5  501.10
  5068.3  501.89  5091.5  506.19  5121.5  508.56  5141.5  509.18  5181.5  511.49
#Mann=6,-1,0
  4469.2    0.12       0  4551.4    0.07       0  4878.4    0.12       0
  5031.9    0.05       0  5036.2    0.12       0  5068.3    0.07       0
Bank Sta=5031.9,5036.2
Exp/Cntr=0.3,0.1

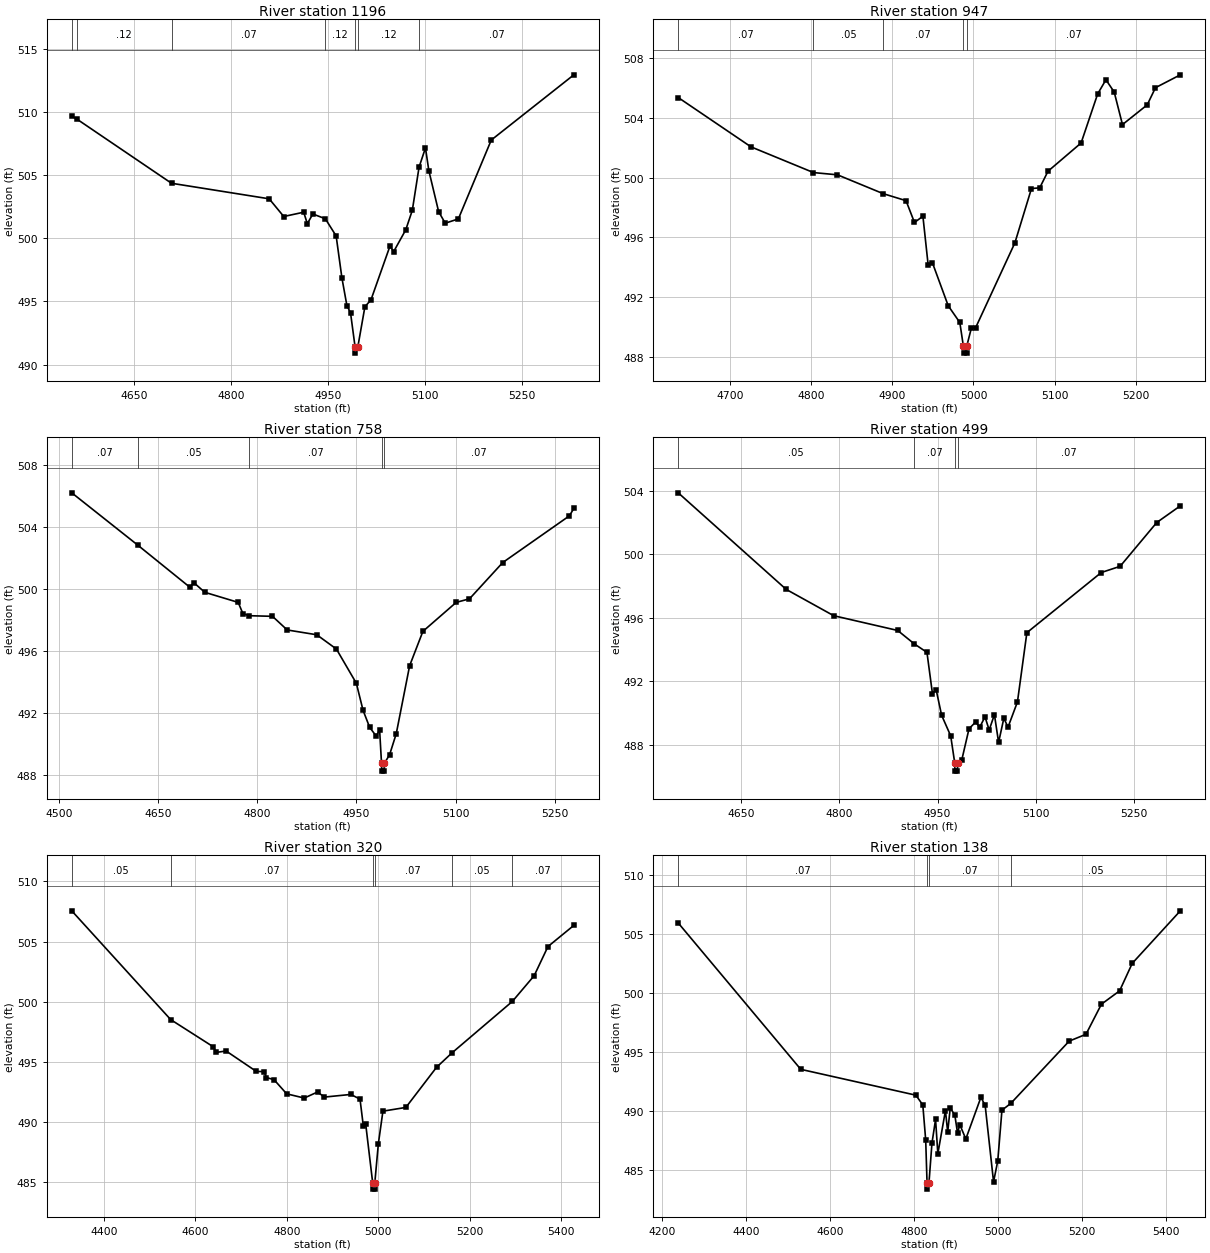
Type RM Length L Ch R = 1,1196,249,249,249
BEGIN DESCRIPTION:
X18539
END DESCRIPTION:
XS GIS Cut Line= 3
      2323513.52     13731635.90      2323952.12     13731859.80
      2324230.60     13731908.77
#Sta/Elev= 30
  4554.3  509.66  4562.1  509.43  4708.3  504.35  4859.1  503.12  4881.6  501.72
  4912.4  502.06  4918.0  501.15  4926.5  501.92  4945.8  501.54  4962.5  500.18
  4971.4  496.86  4979.1  494.67  4984.7  494.10  4991.7  491.41  4991.9  490.91
  4996.0  491.41  5006.9  494.58  5016.3  495.13  5045.6  499.38  5051.3  498.94
  5070.0  500.67  5080.1  502.21  5090.5  505.62  5100.4  507.15  5105.6  505.35
  5120.7  502.11  5130.9  501.19  5151.2  501.53  5202.0  507.77  5329.5  512.93
#Mann=7,-1,0
  4554.3    0.07       0  4562.1    0.12       0  4708.3    0.07       0
  4945.8    0.12       0  4991.7    0.05       0  4996.0    0.12       0
  5090.5    0.07       0
Bank Sta=4991.7,4996
Exp/Cntr=0.3,0.1

Type RM Length L Ch R = 1,947,189,189,189
BEGIN DESCRIPTION:
CORDELL TRIBUTARY 1 2.0
END DESCRIPTION:
XS GIS Cut Line= 3
      2323525.01     13731975.00      2323875.00     13732075.00
      2324124.96     13732025.01
#Sta/Elev= 30
  4636.1  505.35  4725.8  502.05  4802.8  500.33  4832.4  500.18  4888.7  498.92
  4916.9  498.45  4927.3  496.99  4937.7  497.41  4944.2  494.13  4949.4  494.30
  4968.9  491.42  4983.2  490.30  4987.5  488.75  4987.8  488.25  4991.6  488.25
  4991.9  488.75  4997.5  489.94  5002.6  489.94  5051.1  495.63  5071.5  499.26
  5081.7  499.31  5091.9  500.42  5132.7  502.31  5153.1  505.59  5163.3  506.54
  5173.5  505.72  5183.7  503.54  5214.2  504.86  5224.4  506.01  5255.0  506.87
#Mann=5,-1,0
  4636.1    0.07       0  4802.8    0.05       0  4888.7    0.07       0
  4987.5    0.05       0  4991.9    0.07       0
Bank Sta=4987.5,4991.9
Exp/Cntr=0.3,0.1

Type RM Length L Ch R = 1,758,259,259,259
BEGIN DESCRIPTION:
X18542
END DESCRIPTION:
XS GIS Cut Line= 3
      2323482.87     13732099.01      2323811.05     13732261.57
      2324201.84     13732215.77
#Sta/Elev= 30
  4519.2  506.19  4619.2  502.81  4698.1  500.09  4703.7  500.40  4720.5  499.77
  4771.0  499.12  4778.2  498.39  4787.8  498.26  4822.9  498.22  4845.2  497.34
  4889.9  497.03  4919.6  496.11  4949.8  493.90  4959.9  492.16  4970.0  491.05
  4979.9  490.49  4985.0  490.89  4987.9  488.73  4988.2  488.23  4992.0  488.23
  4992.3  488.73  5000.2  489.30  5010.2  490.65  5030.4  495.03  5050.5  497.25
  5100.9  499.12  5121.0  499.35  5171.3  501.69  5272.0  504.70  5278.9  505.18
#Mann=5,-1,0
  4519.2    0.07       0  4619.2    0.05       0  4787.8    0.07       0
  4987.9    0.05       0  4992.3    0.07       0
Bank Sta=4987.9,4992.3
Exp/Cntr=0.3,0.1

Type RM Length L Ch R = 1,499,179,179,179
BEGIN DESCRIPTION:
CORDELL TRIBUTARY 1 1.0
END DESCRIPTION:
XS GIS Cut Line= 3
      2323525.03     13732275.01      2323925.00     13732475.00
      2324174.97     13732275.03
#Sta/Elev= 30
  4553.7  503.86  4718.6  497.78  4791.3  496.12  4889.1  495.19  4914.3  494.35
  4933.8  493.81  4942.2  491.21  4947.8  491.47  4956.2  489.85  4970.1  488.55
  4976.3  486.83  4976.6  486.33  4980.4  486.33  4980.7  486.83  4986.9  487.01
  4998.1  489.00  5008.1  489.42  5014.5  489.10  5022.5  489.75  5028.9  488.92
  5036.9  489.89  5043.3  488.14  5051.3  489.66  5057.7  489.10  5072.1  490.69
  5086.5  495.05  5200.2  498.84  5229.0  499.23  5285.0  501.99  5321.0  503.04
#Mann=4,-1,0
  4553.7    0.05       0  4914.3    0.07       0  4976.3    0.05       0
  4980.7    0.07       0
Bank Sta=4976.3,4980.7
Exp/Cntr=0.3,0.1

Type RM Length L Ch R = 1,320,182,182,182
BEGIN DESCRIPTION:
X18538
END DESCRIPTION:
XS GIS Cut Line= 3
      2323369.40     13732384.24      2323866.25     13732644.93
      2324401.50     13732611.29
#Sta/Elev= 30
  4329.8  507.56  4546.0  498.52  4639.5  496.25  4645.1  495.79  4667.2  495.91
  4733.3  494.21  4749.7  494.20  4755.4  493.70  4771.8  493.53  4799.5  492.35
  4837.9  492.00  4866.9  492.50  4882.1  492.08  4939.7  492.30  4959.8  491.91
  4967.2  489.64  4972.2  489.85  4987.6  484.93  4987.9  484.43  4991.8  484.43
  4992.1  484.93  4999.9  488.20  5009.9  490.91  5060.0  491.22  5127.0  494.55
  5160.4  495.74  5292.8  500.03  5340.5  502.17  5370.6  504.59  5427.2  506.35
#Mann=6,-1,0
  4329.8    0.05       0  4546.0    0.07       0  4987.6    0.05       0
  4992.1    0.07       0  5160.4    0.05       0  5292.8    0.07       0
Bank Sta=4987.6,4992.1
Exp/Cntr=0.3,0.1

Type RM Length L Ch R = 1,138,0,0,0
BEGIN DESCRIPTION:
X18537
END DESCRIPTION:
XS GIS Cut Line= 3
      2323320.31     13732534.51      2323949.06     13732807.48
      2324459.47     13732779.97
#Sta/Elev= 30
  4238.1  505.96  4530.1  493.56  4804.5  491.37  4821.0  490.54  4827.9  487.55
  4831.1  483.91  4831.4  483.41  4835.6  483.91  4842.8  487.31  4851.4  489.31
  4856.8  486.41  4874.9  490.06  4880.3  488.25  4886.4  490.29  4897.3  489.68
  4903.8  488.16  4909.2  488.87  4923.5  487.66  4959.5  491.19  4969.6  490.50
  4989.6  484.03  4999.6  485.79  5009.6  490.10  5030.6  490.67  5169.8  495.95
  5209.9  496.53  5246.7  499.08  5290.0  500.21  5320.1  502.54  5434.7  506.99
#Mann=4,-1,0
  4238.1    0.07       0  4831.1    0.05       0  4835.6    0.07       0
  5030.6    0.05       0
Bank Sta=4831.1,4835.6
Exp/Cntr=0.3,0.1

Chan Stop Cuts=-1