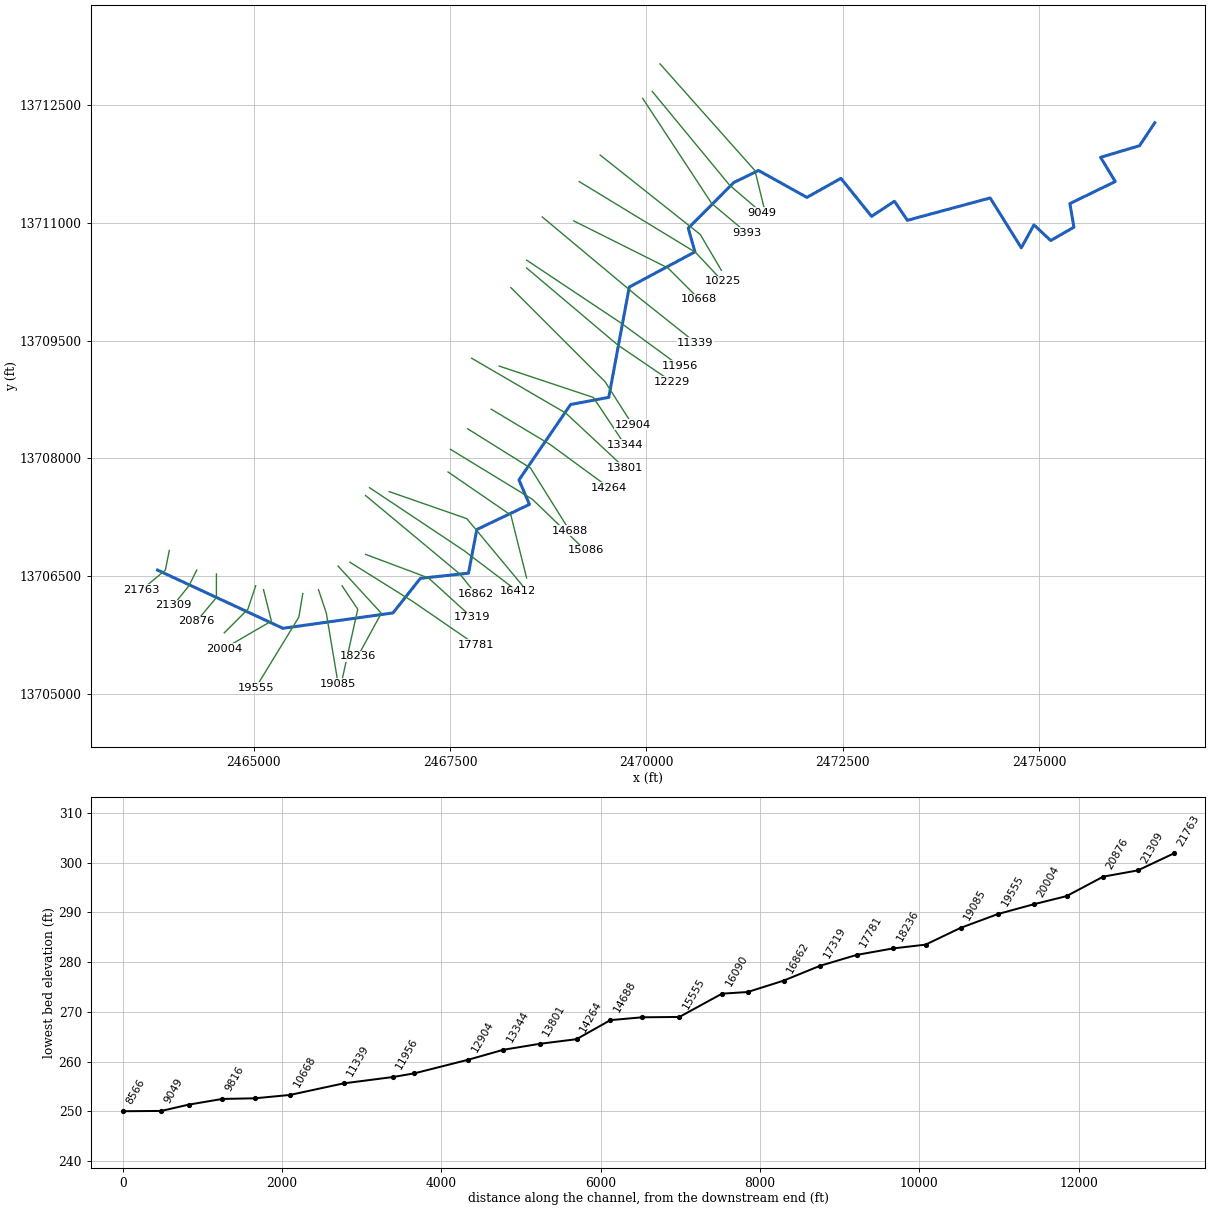
--- COTTLE CREEK.prj (project) ---

Proj Title=COTTLE CREEK Base Level Engineering
Current Plan=p01
Default Exp/Contr=0.3,0.1
English Units
Geom File=g01
Flow File=f01
Plan File=p01
Y Axis Title=Elevation
X Axis Title(PF)=Main Channel Distance
X Axis Title(XS)=Station
BEGIN DESCRIPTION:
COTTLE CREEK
END DESCRIPTION:
DSS Export Rating Curves= 0
DSS Export Rating Curve Sorted= 0
DSS Export Volume Flow Curves= 0
DXF OffsetX= 0
DXF OffsetY= 0
DXF ScaleX= 1
DXF ScaleY= 10

--- COTTLE CREEK.p01 (plan) ---

Plan Title=Multiple Run
Short Identifier=Multiple
Geom File=g01
Flow File=f01
Subcritical Flow
K Sum by GR= 0
Std Step Tol= 0.01
Critical Tol= 0.01
Num of Std Step Trials= 20
Max Error Tol= 0.3
Flow Tol Ratio= 0.001
Split Flow NTrial= 30
Split Flow Tol= 0.02
Split Flow Ratio= 0.02
Log Output Level= 0
Friction Slope Method= 1
Unsteady Friction Slope Method= 2
Unsteady Bridges Friction Slope Method= 1
Parabolic Critical Depth
Global Vel Dist=  1 , 1 , 1
Global Log Level= 0
CheckData=True
Encroach Param= -1, 0, 0, 0
BEGIN DESCRIPTION:
Multiple Run
END DESCRIPTION:

--- COTTLE CREEK.f01 (steady flow) ---

Flow Title=Multiple
Number of Profiles=7
Profile Names=10-year,25-year,50-year,1pct_min,100-year,1pct_plu,500-year
River Rch & RM= COTTLE CREEK,Reach-1,21763
     752    1225    1657    1086    2168    4325    3670
River Rch & RM= COTTLE CREEK,Reach-1,17781
    1101    1821    2487    1642    3277    6538    5637
River Rch & RM= COTTLE CREEK,Reach-1,13801
    1317    2183    2986    1972    3935    7852    6773
River Rch & RM= COTTLE CREEK,Reach-1,7607
    1465    2429    3322    2192    4373    8725    7511
Boundary for River Rch & Prof#=COTTLE CREEK,Reach-1,1
Up Type=0
Dn Type=3
Dn Slope=0.005
Boundary for River Rch & Prof#=COTTLE CREEK,Reach-1,2
Up Type=0
Dn Type=3
Dn Slope=0.005
Boundary for River Rch & Prof#=COTTLE CREEK,Reach-1,3
Up Type=0
Dn Type=3
Dn Slope=0.005
Boundary for River Rch & Prof#=COTTLE CREEK,Reach-1,4
Up Type=0
Dn Type=3
Dn Slope=0.005
Boundary for River Rch & Prof#=COTTLE CREEK,Reach-1,5
Up Type=0
Dn Type=3
Dn Slope=0.005
Boundary for River Rch & Prof#=COTTLE CREEK,Reach-1,6
Up Type=0
Dn Type=3
Dn Slope=0.005
Boundary for River Rch & Prof#=COTTLE CREEK,Reach-1,7
Up Type=0
Dn Type=3
Dn Slope=0.005

--- COTTLE CREEK.g01 (geometry) ---

Geom Title=Existing Conditions
Program Version=4.10

River Reach=COTTLE CREEK    ,Reach-1
Reach XY= 30
        2463775.       13706575.      2465371.77     13705832.84
      2466773.44     13706028.76      2467122.56     13706469.48
      2467735.17     13706535.36      2467841.44     13707091.79
      2468511.59     13707411.66      2468378.13     13707723.37
      2469035.63       13708685.      2469521.64     13708776.25
      2469782.62     13710181.51      2470619.59     13710630.18
      2470533.95     13710931.68      2471114.68     13711514.17
      2471428.35     13711667.42      2472045.04     13711324.39
      2472478.22     13711567.17       2472868.5     13711082.62
      2473159.71     13711275.19       2473324.7      13711032.2
      2474378.41     13711317.18        2474775.     13710682.08
      2474936.21      13710973.5      2475149.87     13710774.45
      2475445.58     13710944.59      2475394.05      13711245.6
      2475971.63     13711526.22      2475785.17     13711834.68
      2476281.06     13711983.14        2476475.       13712275.

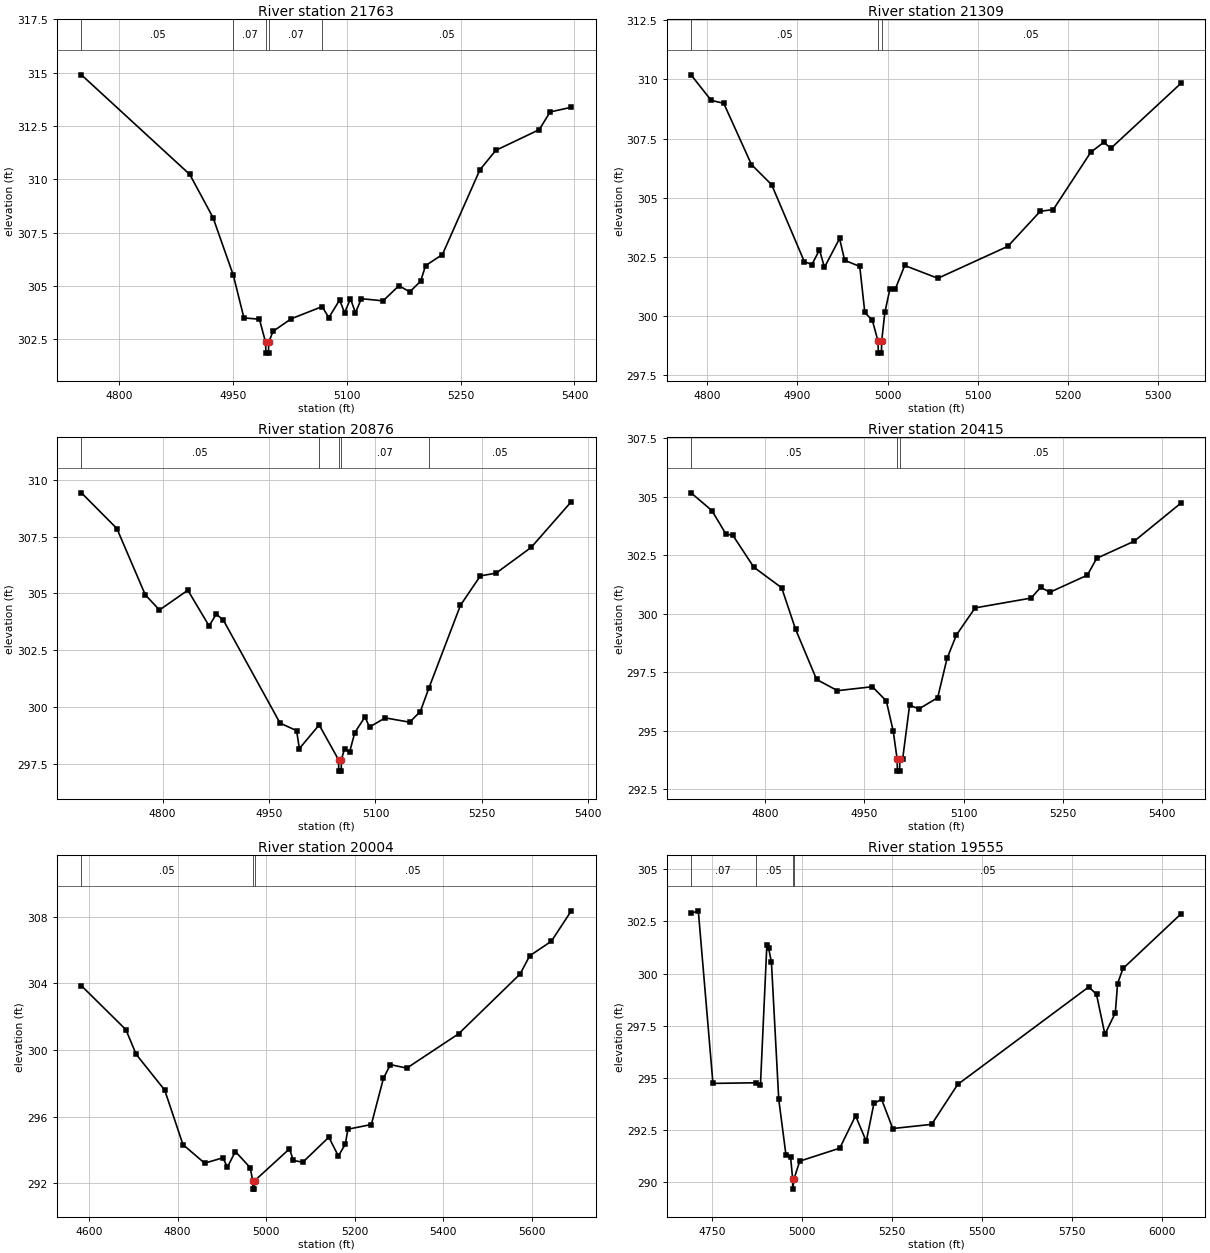
Type RM Length L Ch R = 1 ,21763   ,454,454,454
BEGIN DESCRIPTION:
COTTLE CREEK 48.0
END DESCRIPTION:
XS GIS Cut Line= 3
        2463925.     13706824.98        2463875.       13706575.
      2463575.04     13706325.03
#Sta/Elev= 30
  4750.4   314.9  4893.2  310.23  4923.8  308.21  4950.6   305.5  4964.5  303.51
  4984.9  303.45  4993.1  302.36  4993.4  301.86  4996.9  301.86  4997.1  302.36
  5002.8  302.88  5026.8  303.47  5067.6  304.04  5076.3  303.52  5090.6  304.35
  5097.1  303.75  5104.9  304.41  5111.4  303.75  5119.2  304.41  5147.9  304.31
  5168.7  305.02    5183  304.73  5197.3  305.23  5203.8  305.96    5226  306.48
  5275.4  310.45  5296.3  311.36  5353.5  312.33  5367.9  313.16  5395.8  313.38
#Mann= 5 ,-1 , 0
  4750.4     .05       0  4950.6     .07       0  4993.1     .05       0
  4997.1     .07       0  5067.6     .05       0
Bank Sta=4993.1,4997.1
XS Rating Curve= 0 ,0
Exp/Cntr=0.3,0.1

Type RM Length L Ch R = 1 ,21309   ,433,433,433
BEGIN DESCRIPTION:
COTTLE CREEK 47.0
END DESCRIPTION:
XS GIS Cut Line= 3
        2464275.     13706575.01        2464175.       13706375.
      2463974.98     13706124.98
#Sta/Elev= 30
  4781.9  310.19  4804.3  309.11  4818.2  308.99    4849   306.4  4871.4  305.55
  4907.7   302.3  4916.1  302.18  4924.5   302.8    4930  302.06  4946.8  303.28
  4952.4  302.36  4969.2   302.1  4974.8  300.16  4983.2  299.82  4989.5  298.94
  4989.8  298.44  4993.3  298.44  4993.5  298.94  4997.1  300.17  5002.7  301.15
  5008.7  301.15  5019.1  302.14  5055.9   301.6  5133.6  302.95  5169.6  304.43
    5184   304.5  5225.6  306.92    5240  307.34    5248  307.09  5325.7  309.83
#Mann= 3 ,-1 , 0
  4781.9     .05       0  4989.5     .05       0  4993.5     .05       0
Bank Sta=4989.5,4993.5
XS Rating Curve= 0 ,0
Exp/Cntr=0.3,0.1

Type RM Length L Ch R = 1 ,20876   ,461,461,461
BEGIN DESCRIPTION:
COTTLE CREEK 46.0
END DESCRIPTION:
XS GIS Cut Line= 3
        2464525.       13706525.        2464525.       13706225.
      2464275.01     13705925.01
#Sta/Elev= 30
  4685.5  309.42  4735.5  307.85  4775.5  304.94  4795.5  304.27  4835.5  305.14
  4865.5  303.57  4875.5  304.09  4885.5  303.83  4965.5   299.3  4988.8  298.97
  4992.7  298.18  5020.6  299.22  5047.9  297.69  5048.2  297.19  5051.7  297.19
  5051.9  297.69  5056.4  298.18  5063.6  298.04  5070.8  298.88  5085.1  299.57
  5091.6  299.13  5113.7  299.53  5148.2  299.34  5163.2  299.81  5175.5  300.86
  5219.8  304.48  5247.8  305.77  5269.9  305.89  5319.4  307.02    5376  309.03
#Mann= 5 ,-1 , 0
  4685.5     .05       0  5020.6     .07       0  5047.9     .05       0
  5051.9     .07       0  5175.5     .05       0
Bank Sta=5047.9,5051.9
XS Rating Curve= 0 ,0
Exp/Cntr=0.3,0.1

Type RM Length L Ch R = 1 ,20415   ,411,411,411
BEGIN DESCRIPTION:
COTTLE CREEK 45.0
END DESCRIPTION:
XS GIS Cut Line= 3
      2465025.01     13706375.02        2464925.       13706075.
      2464625.01     13705775.01
#Sta/Elev= 30
  4688.1  305.17  4719.7  304.41  4740.8  303.41  4751.4  303.35    4783  301.99
  4825.1  301.11  4846.2  299.33  4877.9  297.19  4909.5  296.71  4962.2  296.88
  4983.3  296.27  4993.8  294.97  4999.7  293.77    5000  293.27  5003.5  293.27
  5003.7  293.77  5007.9  293.77  5018.5  296.09  5032.6  295.93  5060.9  296.41
  5075.1  298.09  5089.2  299.09  5117.5  300.25  5202.3  300.67  5216.5  301.13
  5230.6  300.92  5287.2  301.65  5301.3  302.37  5357.9   303.1  5428.6  304.73
#Mann= 3 ,-1 , 0
  4688.1     .05       0  4999.7     .05       0  5003.7     .05       0
Bank Sta=4999.7,5003.7
XS Rating Curve= 0 ,0
Exp/Cntr=0.3,0.1

Type RM Length L Ch R = 1 ,20004   ,449,449,449
BEGIN DESCRIPTION:
COTTLE CREEK 44.0
END DESCRIPTION:
XS GIS Cut Line= 3
      2465124.99     13706325.05        2465225.       13705925.
      2464624.98     13705574.99
#Sta/Elev= 30
  4582.7  303.86  4683.2  301.22  4706.4  299.74  4770.9  297.59  4812.1  294.32
  4861.1   293.2  4902.3  293.52  4912.6  292.96  4930.6   293.9  4964.1  292.93
  4969.9  292.14  4970.1  291.64  4973.6  291.64  4973.9  292.14  5052.9  294.06
  5061.6  293.36  5083.1  293.26  5141.8  294.76  5163.3  293.63  5179.1  294.34
  5184.8  295.24  5237.8  295.52  5265.1  298.29  5280.8  299.12    5318  298.91
    5435  300.97  5573.9  304.56  5595.8  305.66  5644.6  306.53  5689.7  308.36
#Mann= 3 ,-1 , 0
  4582.7     .05       0  4969.9     .05       0  4973.9     .05       0
Bank Sta=4969.9,4973.9
XS Rating Curve= 0 ,0
Exp/Cntr=0.3,0.1

Type RM Length L Ch R = 1 ,19555   ,470,470,470
BEGIN DESCRIPTION:
COTTLE CREEK 43.0
END DESCRIPTION:
XS GIS Cut Line= 3
      2465624.99     13706274.95        2465575.       13705975.
      2465025.02     13705075.04
#Sta/Elev= 30
  4692.3  302.88  4712.5     303  4753.1  294.74  4871.3  294.77  4884.9  294.68
  4902.6  301.36  4907.7   301.2  4915.3  300.54  4935.6  293.98  4955.8  291.29
  4968.5   291.2  4974.1  290.18  4974.4  289.68  4978.1  290.18  4993.9  291.02
  5104.8  291.64  5148.7  293.19  5178.3  291.97  5199.6  293.78  5220.9  293.98
  5251.8  292.58  5359.7  292.78  5431.9  294.69  5795.7  299.36    5817     299
  5840.2  297.09  5869.2  298.12  5875.4  299.52  5890.5  300.24  6051.1  302.85
#Mann= 4 ,-1 , 0
  4692.3     .07       0  4871.3     .05       0  4974.1     .05       0
  4978.1     .05       0
Bank Sta=4974.1,4978.1
XS Rating Curve= 0 ,0
Exp/Cntr=0.3,0.1

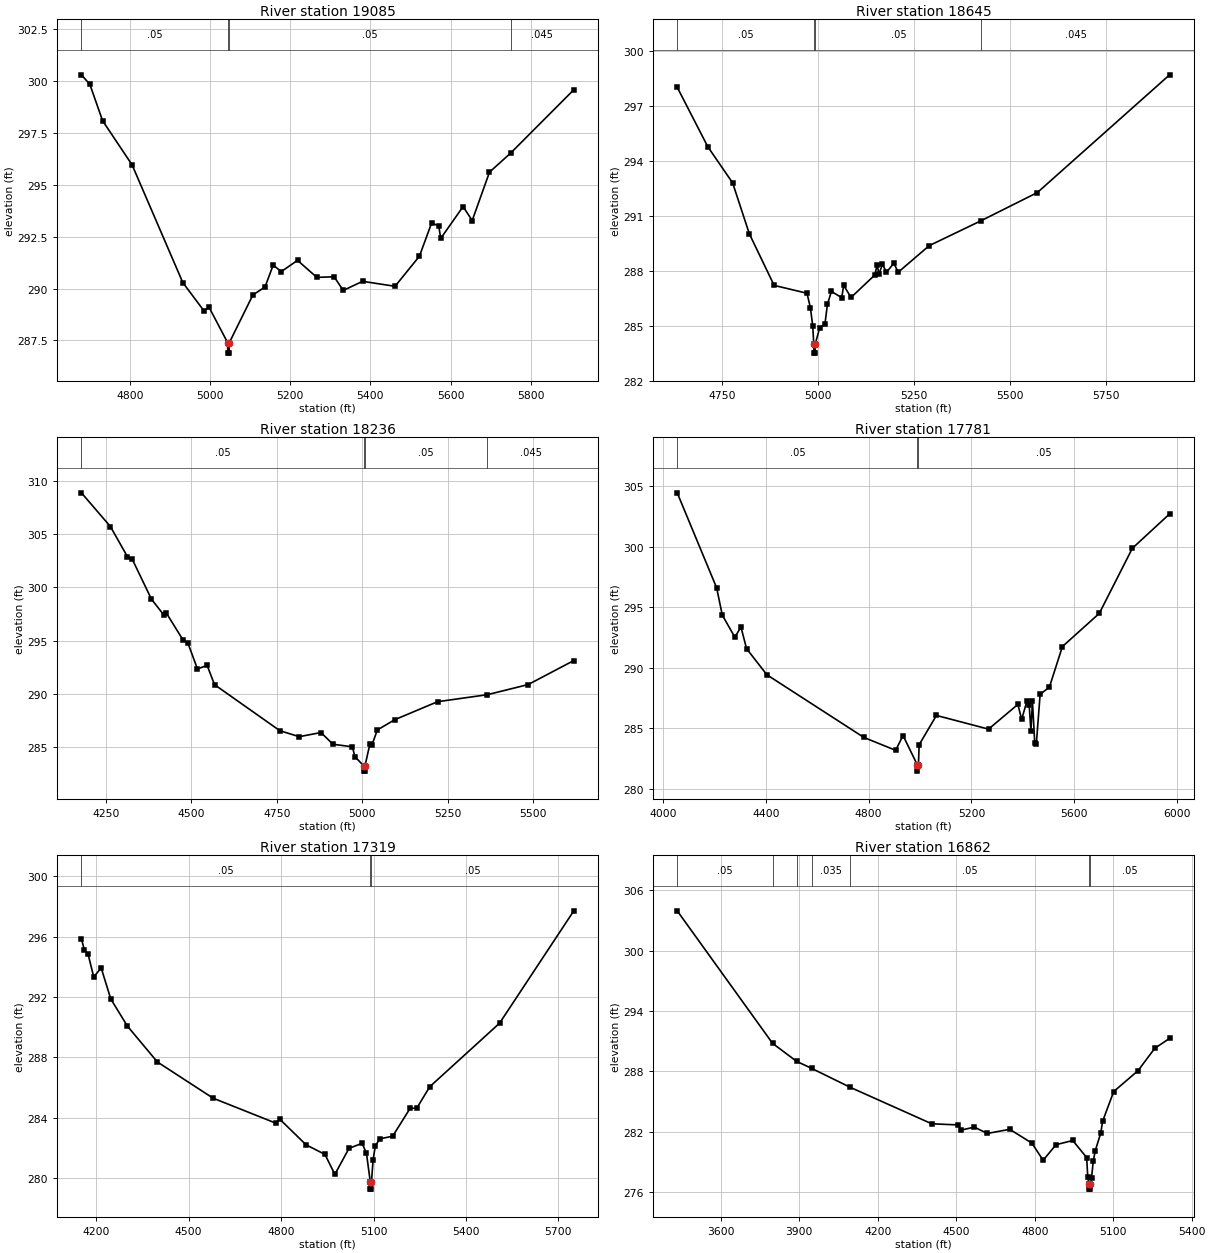
Type RM Length L Ch R = 1 ,19085   ,440,440,440
BEGIN DESCRIPTION:
COTTLE CREEK 42.0
END DESCRIPTION:
XS GIS Cut Line= 3
      2465824.98     13706325.05        2465925.       13706025.
        2466075.     13705124.99
#Sta/Elev= 30
  4678.8   300.3  4699.9  299.84  4731.6  298.09  4805.3  295.96  4931.8  290.29
  4984.5  288.93  4997.6  289.09  5043.8  287.39    5044  286.89  5047.5  286.89
  5047.8  287.39  5106.6  289.69    5137  290.08  5157.3  291.13  5177.6  290.82
  5218.1  291.36  5266.3  290.54  5309.4  290.57  5332.2  289.91  5380.3  290.35
  5461.4  290.11  5522.3  291.56  5552.7  293.16  5570.4  293.02  5575.5  292.42
  5631.2  293.95    5654  293.28  5697.1  295.61  5750.5  296.54  5907.5  299.58
#Mann= 4 ,-1 , 0
  4678.8     .05       0  5043.8     .05       0  5047.8     .05       0
  5750.5    .045       0
Bank Sta=5043.8,5047.8
XS Rating Curve= 0 ,0
Exp/Cntr=0.3,0.1

Type RM Length L Ch R = 1 ,18645   ,409,409,409
BEGIN DESCRIPTION:
COTTLE CREEK 41.0
END DESCRIPTION:
XS GIS Cut Line= 3
      2466124.97     13706375.04        2466325.       13706075.
      2466124.99     13705174.96
#Sta/Elev= 30
  4633.6  298.04  4713.3  294.79  4777.9  292.82  4821.4  290.04    4886  287.22
  4971.7  286.79  4980.7  285.98  4986.7  284.98  4989.2  284.02  4989.4  283.52
  4992.9  283.52  4993.2  284.02  5004.4  284.88  5018.5  285.13  5024.9  286.19
  5035.2  286.89  5062.1  286.55  5067.2  287.22  5086.4  286.56  5147.9  287.78
  5154.3  288.31  5159.4  287.85  5168.3  288.38  5178.6  287.93  5197.8  288.43
  5209.3  287.94    5290  289.39  5425.9  290.76  5571.7  292.29  5916.2  298.72
#Mann= 4 ,-1 , 0
  4633.6     .05       0  4989.2     .05       0  4993.2     .05       0
  5425.9    .045       0
Bank Sta=4989.2,4993.2
XS Rating Curve= 0 ,0
Exp/Cntr=0.3,0.1

Type RM Length L Ch R = 1 ,18236   ,455,455,455
BEGIN DESCRIPTION:
COTTLE CREEK 40.0
END DESCRIPTION:
XS GIS Cut Line= 3
      2466074.99     13706625.01        2466625.       13706025.
      2466324.98     13705474.96
#Sta/Elev= 30
  4178.2  308.86    4263   305.7  4312.9  302.87  4327.1  302.62  4383.2  298.88
    4419  297.42  4425.8  297.63  4475.7  295.05  4489.9  294.76  4517.7  292.34
    4546  292.68  4567.6  290.87  4758.8  286.55  4815.5  285.99    4879  286.38
  4914.2  285.28  4970.9  285.04  4978.3  284.12  5003.9  283.26  5004.2  282.76
  5007.7  282.76  5007.9  283.26  5022.1   285.3  5027.8  285.17  5043.9  286.62
  5094.7  287.58    5220  289.27    5366  289.93  5485.3  290.88  5618.7  293.13
#Mann= 4 ,-1 , 0
  4178.2     .05       0  5003.9     .05       0  5007.9     .05       0
    5366    .045       0
Bank Sta=5003.9,5007.9
XS Rating Curve= 0 ,0
Exp/Cntr=0.3,0.1

Type RM Length L Ch R = 1 ,17781   ,462,462,462
BEGIN DESCRIPTION:
COTTLE CREEK 39.0
END DESCRIPTION:
XS GIS Cut Line= 3
      2466224.97     13706675.02        2467025.       13706175.
      2467825.03     13705624.98
#Sta/Elev= 30
    4056  304.45  4209.3   296.6  4231.2  294.35  4280.1  292.52  4303.7  293.37
  4325.5  291.58  4404.5  289.42  4781.9  284.24  4905.1  283.18    4934   284.4
  4989.8  281.96    4990  281.46  4993.8  281.96  4996.5  283.64  5063.7  286.06
  5266.4  284.93  5380.3  286.97  5395.2  285.74  5416.2  287.29  5424.2  286.95
  5431.1  284.79  5437.1  287.22    5446  283.76    5452  283.67  5466.9  287.81
  5502.8  288.39  5553.5  291.75  5696.9  294.49  5825.5  299.87  5970.3  302.71
#Mann= 3 ,-1 , 0
    4056     .05       0  4989.8     .05       0  4993.8     .05       0
Bank Sta=4989.8,4993.8
XS Rating Curve= 0 ,0
Exp/Cntr=0.3,0.1

Type RM Length L Ch R = 1 ,17319   ,457,457,457
BEGIN DESCRIPTION:
COTTLE CREEK 38.0
END DESCRIPTION:
XS GIS Cut Line= 3
      2466425.01       13706775.        2467225.       13706475.
        2467775.       13705975.
#Sta/Elev= 30
  4152.2  295.87    4162  295.09  4173.6  294.86  4192.2  293.32  4216.3  293.93
  4247.4  291.87  4301.7  290.06  4398.7  287.69  4579.4  285.29  4782.3  283.64
  4795.7   283.9  4881.1   282.2  4942.5  281.56  4974.6  280.24  5020.4  281.96
    5063   282.3  5077.2  281.63  5089.4  279.76  5089.6  279.26  5093.1  279.26
  5093.4  279.76  5098.8  281.22  5105.6   282.1  5119.8  282.59  5162.3  282.77
  5219.1  284.63  5240.1  284.62  5282.6  286.05    5509  290.26  5749.9  297.71
#Mann= 3 ,-1 , 0
  4152.2     .05       0  5089.4     .05       0  5093.4     .05       0
Bank Sta=5089.4,5093.4
XS Rating Curve= 0 ,0
Exp/Cntr=0.3,0.1

Type RM Length L Ch R = 1 ,16862   ,450,450,450
BEGIN DESCRIPTION:
COTTLE CREEK 37.0
END DESCRIPTION:
XS GIS Cut Line= 3
      2466425.01       13707525.        2467625.       13706525.
        2467825.       13706275.
#Sta/Elev= 30
  3433.5  303.97  3798.1  290.78  3890.1  288.99  3946.9   288.3  4095.6   286.4
  4406.5  282.78  4505.4  282.67  4519.8  282.16  4569.2  282.45  4618.7  281.82
  4704.6  282.23  4789.2  280.86  4832.2  279.15  4881.6   280.7  4945.4  281.12
  4998.7  279.42  5002.7   277.5  5006.9  276.78  5007.2  276.28  5011.1  276.28
  5011.4  276.78  5017.2  277.34  5023.6  279.03  5031.6  280.11  5052.4  281.85
  5059.6  283.03    5102  285.99  5194.8  288.06  5258.9  290.29  5315.7  291.28
#Mann= 7 ,-1 , 0
  3433.5     .05       0  3798.1     .07       0  3890.1     .05       0
  3946.9    .035       0  4095.6     .05       0  5006.9     .05       0
  5011.4     .05       0
Bank Sta=5006.9,5011.4
XS Rating Curve= 0 ,0
Exp/Cntr=0.3,0.1

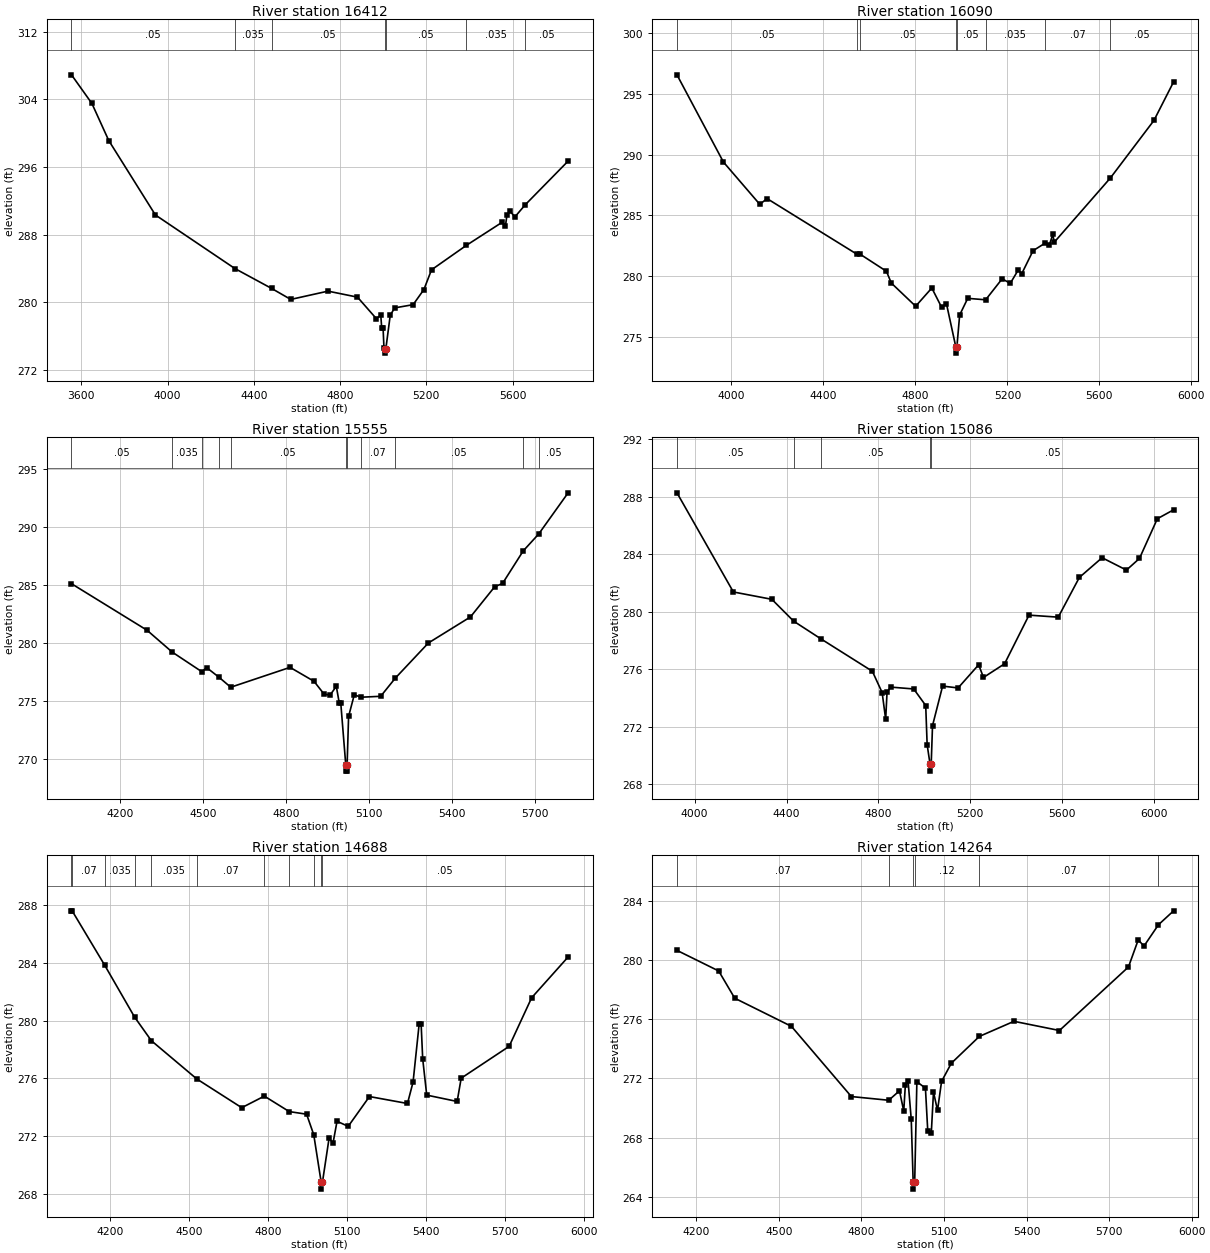
Type RM Length L Ch R = 1 ,16412   ,322,322,322
BEGIN DESCRIPTION:
COTTLE CREEK 36.0
END DESCRIPTION:
XS GIS Cut Line= 3
      2466474.97     13707625.02        2467675.       13706825.
      2468361.24     13706304.27
#Sta/Elev= 30
  3554.1  306.91  3648.8  303.52  3726.9  299.14  3943.2  290.34  4312.2     284
  4482.4  281.65  4571.2  280.35    4744  281.33  4880.7  280.62  4967.8  278.09
  4988.8  278.46  4993.3  276.92  4999.5  276.92  5003.6  274.59  5007.7   274.5
    5008     274  5012.2   274.5  5032.7  278.49  5053.5  279.35  5138.8  279.73
  5188.8  281.52  5224.1  283.85  5386.2  286.75  5552.8  289.49  5567.3  289.06
  5573.8   290.3  5588.1  290.79  5610.9  290.11  5659.2  291.55  5857.8  296.71
#Mann= 7 ,-1 , 0
  3554.1     .05       0  4312.2    .035       0  4482.4     .05       0
  5007.7     .05       0  5012.2     .05       0  5386.2    .035       0
  5659.2     .05       0
Bank Sta=5007.7,5012.2
XS Rating Curve= 0 ,0
Exp/Cntr=0.3,0.1

Type RM Length L Ch R = 1 ,16090   ,535,535,535
BEGIN DESCRIPTION:
COTTLE CREEK 35.0
END DESCRIPTION:
XS GIS Cut Line= 3
      2466724.98     13707575.01      2467714.34     13707230.03
      2468425.01     13706374.99
#Sta/Elev= 30
    3763  296.58    3965   289.4  4123.1  285.92  4154.9  286.39    4544  281.83
  4557.3  281.84  4673.8  280.41    4695  279.44  4800.9  277.53  4871.2  279.03
  4914.2  277.43    4935  277.73  4975.7  274.17    4976  273.67  4980.2  274.17
  4992.3  276.81  5027.4  278.18  5105.3  278.06  5177.2  279.79  5212.3  279.41
  5247.5  280.53  5261.8  280.19  5311.4   282.1  5363.5  282.72  5382.9  282.61
  5397.2  283.44  5403.7   282.8  5647.8  288.09  5837.3  292.83  5922.6     296
#Mann= 8 ,-1 , 0
    3763     .05       0    4544    .035       0  4557.3     .05       0
  4975.7     .05       0  4980.2     .05       0  5105.3    .035       0
  5363.5     .07       0  5647.8     .05       0
Bank Sta=4975.7,4980.2
XS Rating Curve= 0 ,0
Exp/Cntr=0.3,0.1

Type RM Length L Ch R = 1 ,15555   ,469,469,469
BEGIN DESCRIPTION:
COTTLE CREEK 34.0
END DESCRIPTION:
XS GIS Cut Line= 3
      2467474.97     13707825.02        2468275.       13707275.
        2468475.     13706474.99
#Sta/Elev= 30
  4024.9  285.12  4298.3  281.11  4388.7  279.24  4496.4  277.54  4513.4   277.9
  4558.1  277.07  4600.7  276.21  4815.1  277.92  4901.7  276.72  4937.6  275.63
  4959.4  275.52  4982.3  276.29  4992.7  274.89  4998.3  274.89  5016.6  269.49
    5017  268.99    5021  268.99  5021.3  269.49  5026.7   273.7  5047.3  275.56
  5071.3  275.35  5142.7  275.43  5195.5  276.99  5315.3  280.02  5467.3  282.26
    5555  284.86  5583.3  285.14    5658  287.94  5714.1   289.4  5820.4  292.94
#Mann= 11 ,-1 , 0
  4024.9     .05       0  4388.7    .035       0  4496.4     .05       0
  4558.1    .035       0  4600.7     .05       0  5016.6     .05       0
  5021.3     .05       0  5071.3     .07       0  5195.5     .05       0
    5658     .07       0  5714.1     .05       0
Bank Sta=5016.6,5021.3
XS Rating Curve= 0 ,0
Exp/Cntr=0.3,0.1

Type RM Length L Ch R = 1 ,15086   ,398,398,398
BEGIN DESCRIPTION:
COTTLE CREEK 33.0
END DESCRIPTION:
XS GIS Cut Line= 3
      2467505.46     13708113.88      2468549.99     13707476.44
      2469225.03     13706824.97
#Sta/Elev= 30
  3922.9  288.26  4168.4  281.37  4335.9  280.86  4430.9  279.34  4548.7  278.12
  4773.4  275.86    4816  274.38  4831.4  272.52  4837.3  274.39  4852.7  274.76
  4953.5  274.63  5005.7  273.48  5011.9  270.76  5024.4  269.42  5024.8  268.92
  5029.6  269.42  5035.3  272.08  5079.2  274.83  5146.6   274.7  5236.1  276.31
  5257.2  275.43    5349  276.38  5455.3  279.76  5582.6  279.62  5674.5  282.38
  5773.5  283.75  5879.5  282.89  5936.1   283.7    6014  286.46  6084.7  287.08
#Mann= 5 ,-1 , 0
  3922.9     .05       0  4430.9    .035       0  4548.7     .05       0
  5024.4     .05       0  5029.6     .05       0
Bank Sta=5024.4,5029.6
XS Rating Curve= 0 ,0
Exp/Cntr=0.3,0.1

Type RM Length L Ch R = 1 ,14688   ,424,424,424
BEGIN DESCRIPTION:
COTTLE CREEK 32.0
END DESCRIPTION:
XS GIS Cut Line= 3
      2467725.04     13708374.98        2468525.       13707875.
      2469025.02     13707074.96
#Sta/Elev= 30
  4052.2  287.59  4055.3  287.57    4178  283.84  4291.7  280.25  4355.7  278.61
    4528  275.97    4699  273.98  4784.9  274.78  4879.5  273.71  4945.4  273.53
  4972.6  272.11  5000.6  268.85    5001  268.35  5005.8  268.85  5030.9  271.88
  5045.7  271.52    5061  273.04  5103.5  272.69  5184.2  274.75  5328.7  274.27
  5349.9  275.75  5372.9  279.74  5380.6  279.74  5386.5  277.36  5401.8  274.85
  5517.4  274.41  5532.7  276.02  5714.9  278.22  5800.4  281.58    5939   284.4
#Mann= 11 ,-1 , 0
  4052.2    .035       0  4055.3     .07       0    4178    .035       0
  4291.7     .07       0  4355.7    .035       0    4528     .07       0
  4784.9     .05       0  4879.5     .07       0  4972.6     .05       0
  5000.6     .05       0  5005.8     .05       0
Bank Sta=5000.6,5005.8
XS Rating Curve= 0 ,0
Exp/Cntr=0.3,0.1

Type RM Length L Ch R = 1 ,14264   ,463,463,463
BEGIN DESCRIPTION:
COTTLE CREEK 31.0
END DESCRIPTION:
XS GIS Cut Line= 3
      2468024.98     13708625.01        2468775.       13708175.
      2469524.98     13707625.01
#Sta/Elev= 30
  4129.7  280.64  4281.3  279.25  4339.6  277.41  4545.7  275.51  4763.4  270.77
  4899.3  270.52  4938.3  271.16  4953.8  269.79  4959.7  271.56  4969.4  271.84
    4981  269.24    4988  265.02  4988.4  264.52  4993.6  265.02  5001.5  271.77
  5032.6  271.34    5041  268.46    5054  268.34  5061.9  271.08  5076.5  269.83
  5091.2  271.79  5126.7  273.02  5228.5  274.83  5354.4  275.85  5519.6  275.23
  5770.4  279.52  5805.9  281.35  5826.8  280.93  5879.4  282.37  5934.4  283.31
#Mann= 6 ,-1 , 0
  4129.7     .07       0  4899.3     .12       0    4988     .05       0
  4993.6     .12       0  5228.5     .07       0  5879.4     .05       0
Bank Sta=4988,4993.6
XS Rating Curve= 0 ,0
Exp/Cntr=0.3,0.1

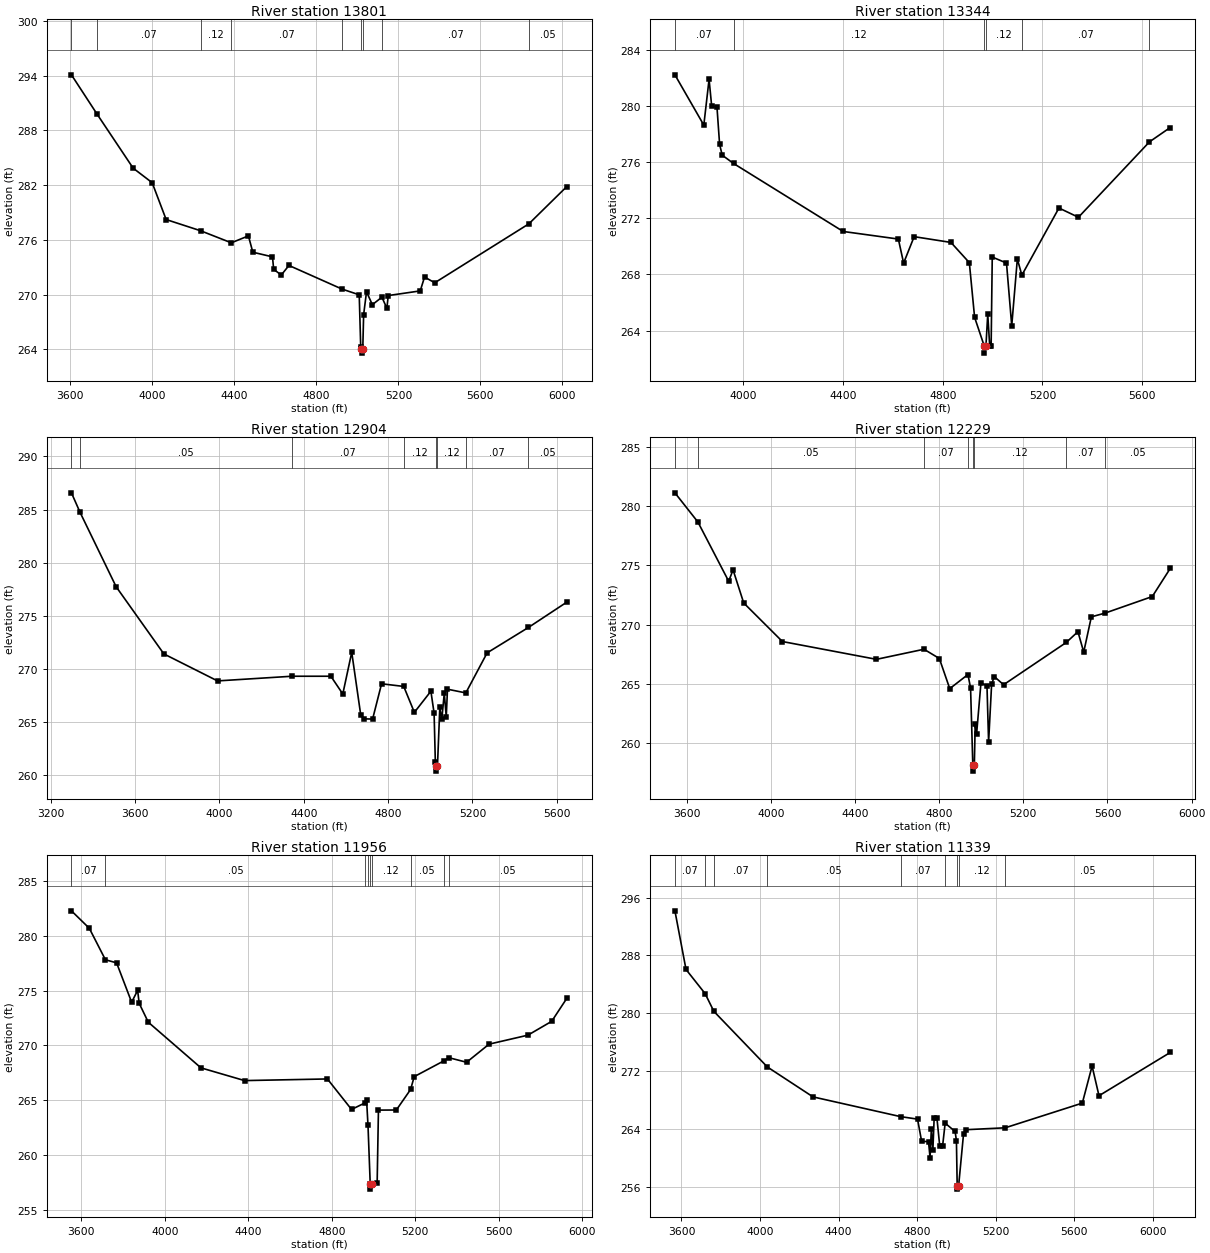
Type RM Length L Ch R = 1 ,13801   ,457,457,457
BEGIN DESCRIPTION:
COTTLE CREEK 30.0
END DESCRIPTION:
XS GIS Cut Line= 3
      2467775.01     13709274.99        2468975.       13708575.
      2469724.97     13707875.03
#Sta/Elev= 30
  3605.8  294.09  3729.4  289.83  3906.8  283.86  3999.4  282.27  4067.6  278.23
  4235.8     277  4385.4  275.68  4468.7  276.44  4490.2  274.65  4586.1  274.14
  4591.9  272.77  4629.1  272.15  4666.3   273.2  4925.1  270.61    5009  269.98
  5016.3  264.27  5019.8  264.09  5020.3  263.59  5026.4  264.09  5030.5   267.8
  5044.6  270.31    5073   268.9  5119.6  269.72  5143.8  268.51  5150.6   269.9
  5306.5  270.41  5327.5  271.93  5377.3   271.3  5836.2  277.76  6020.9  281.84
#Mann= 9 ,-1 , 0
  3605.8     .05       0  3729.4     .07       0  4235.8     .12       0
  4385.4     .07       0  4925.1     .12       0  5019.8     .05       0
  5026.4     .12       0  5119.6     .07       0  5836.2     .05       0
Bank Sta=5019.8,5026.4
XS Rating Curve= 0 ,0
Exp/Cntr=0.3,0.1

Type RM Length L Ch R = 1 ,13344   ,440,440,440
BEGIN DESCRIPTION:
COTTLE CREEK 29.0
END DESCRIPTION:
XS GIS Cut Line= 3
      2468125.04     13709174.99        2469325.       13708775.
      2469725.01     13708174.98
#Sta/Elev= 30
  3726.2   282.2  3842.1  278.62  3863.2  281.88  3873.7  279.96  3894.8  279.92
  3905.4  277.25  3915.9  276.48  3961.3  275.89  4400.8  271.05  4622.1  270.51
  4643.2   268.8  4685.4  270.68    4833  270.27  4906.7  268.83  4927.8  264.94
  4966.6  262.89  4967.1  262.39  4973.3  262.89  4980.5  265.16  4988.4   262.9
  4994.1   262.9  4998.6  269.23  5055.7   268.8  5076.7  264.34  5099.2  269.09
  5117.3  267.94    5266  272.72  5344.1  272.06    5629  277.43  5712.2  278.45
#Mann= 6 ,-1 , 0
  3726.2     .07       0  3961.3     .12       0  4966.6     .05       0
  4973.3     .12       0  5117.3     .07       0    5629     .05       0
Bank Sta=4966.6,4973.3
XS Rating Curve= 0 ,0
Exp/Cntr=0.3,0.1

Type RM Length L Ch R = 1 ,12904   ,675,675,675
BEGIN DESCRIPTION:
COTTLE CREEK 28.0
END DESCRIPTION:
XS GIS Cut Line= 3
      2468275.01     13710174.99        2469475.       13708975.
      2469825.02     13708424.96
#Sta/Elev= 30
  3298.5  286.58  3339.2  284.75  3510.6  277.74  3736.9  271.42  3991.4  268.88
  4344.5  269.32  4528.8  269.32  4585.4  267.65  4627.8  271.57  4670.3   265.7
  4684.4  265.31  4726.8  265.29  4769.3  268.61  4874.4  268.36  4924.8  265.92
  5003.2  267.91  5018.4  265.84  5024.3  261.23  5027.7  260.89  5028.2  260.39
  5034.4  260.89  5045.5  266.38  5054.8  265.26  5066.7  267.73    5076   265.5
  5081.9   268.1  5168.8  267.75  5269.9  271.52  5465.7  273.91  5647.5  276.29
#Mann= 8 ,-1 , 0
  3298.5     .07       0  3339.2     .05       0  4344.5     .07       0
  4874.4     .12       0  5027.7     .05       0  5034.4     .12       0
  5168.8     .07       0  5465.7     .05       0
Bank Sta=5027.7,5034.4
XS Rating Curve= 0 ,0
Exp/Cntr=0.3,0.1

Type RM Length L Ch R = 1 ,12229   ,273,273,273
BEGIN DESCRIPTION:
COTTLE CREEK 27.0
END DESCRIPTION:
XS GIS Cut Line= 3
      2468474.98     13710425.02      2469637.42     13709442.38
      2470324.99       13708975.
#Sta/Elev= 30
  3544.7  281.11    3654  278.65  3800.2  273.66    3821  274.62  3871.6  271.83
  4055.4  268.58  4502.3  267.08  4728.3  267.93  4801.2  267.15  4850.6  264.61
  4937.1   265.8  4949.5  264.66  4960.2  258.16  4960.7  257.66  4967.4  258.16
  4971.5  261.62    4978  260.76  4998.9  265.11  5027.5  264.83  5035.2   260.1
  5049.5  264.97    5062  265.63  5106.4  264.94  5404.1   268.5  5459.6  269.41
  5487.1  267.69  5523.4  270.66  5587.5  270.97  5812.8  272.37  5898.2  274.74
#Mann= 8 ,-1 , 0
  3544.7     .07       0    3654     .05       0  4728.3     .07       0
  4937.1     .12       0  4960.2     .05       0  4967.4     .12       0
  5404.1     .07       0  5587.5     .05       0
Bank Sta=4960.2,4967.4
XS Rating Curve= 0 ,0
Exp/Cntr=0.3,0.1

Type RM Length L Ch R = 1 ,11956   ,617,617,617
BEGIN DESCRIPTION:
COTTLE CREEK 26.0
END DESCRIPTION:
XS GIS Cut Line= 3
      2468475.01     13710524.99        2469675.       13709725.
      2470425.03     13709174.98
#Sta/Elev= 30
  3553.2  282.27  3638.8  280.68    3716  277.81  3769.5  277.53  3841.6  273.94
  3870.2  275.02  3877.7  273.84  3921.3  272.12  4173.6  267.96  4382.5   266.8
  4779.1  266.95  4894.8  264.17  4961.5  264.79  4966.9     265  4973.5  262.74
  4984.2  257.41  4984.7  256.91  4991.5  257.41  5017.4  257.47  5023.6  264.11
  5109.3  264.12  5177.6  265.99  5194.9  267.16  5335.2  268.58  5360.3  268.89
  5445.8  268.47  5553.4  270.12  5739.4  270.94  5853.3   272.2  5925.5  274.29
#Mann= 9 ,-1 , 0
  3553.2     .07       0    3716     .05       0  4961.5     .07       0
  4973.5     .12       0  4984.2     .05       0  4991.5     .12       0
  5177.6     .05       0  5335.2     .12       0  5360.3     .05       0
Bank Sta=4984.2,4991.5
XS Rating Curve= 0 ,0
Exp/Cntr=0.3,0.1

Type RM Length L Ch R = 1 ,11339   ,671,671,671
BEGIN DESCRIPTION:
COTTLE CREEK 25.0
END DESCRIPTION:
XS GIS Cut Line= 3
      2468674.97     13711075.02      2469878.47     13710069.12
        2470625.       13709475.
#Sta/Elev= 30
  3566.6  294.17  3623.2  286.05  3720.4  282.71  3765.1  280.25  4037.5  272.55
    4270  268.41  4715.5  265.68  4802.3  265.33  4823.1  262.25  4858.2  262.22
    4866     260  4872.6  263.95  4880.4  261.06  4886.9  265.48  4901.2  265.42
  4915.5  261.56  4929.8  261.59  4942.9  264.77  4993.6  263.62  5000.3  262.36
  5004.2  256.14  5004.7  255.64  5011.6  256.14  5036.5  263.27  5050.8  263.87
  5248.5  264.13  5641.5  267.55  5691.2  272.68  5726.4  268.57  6089.2  274.56
#Mann= 9 ,-1 , 0
  3566.6     .07       0  3720.4     .05       0  3765.1     .07       0
  4037.5     .05       0  4715.5     .07       0  4942.9     .12       0
  5004.2     .05       0  5011.6     .12       0  5248.5     .05       0
Bank Sta=5004.2,5011.6
XS Rating Curve= 0 ,0
Exp/Cntr=0.3,0.1

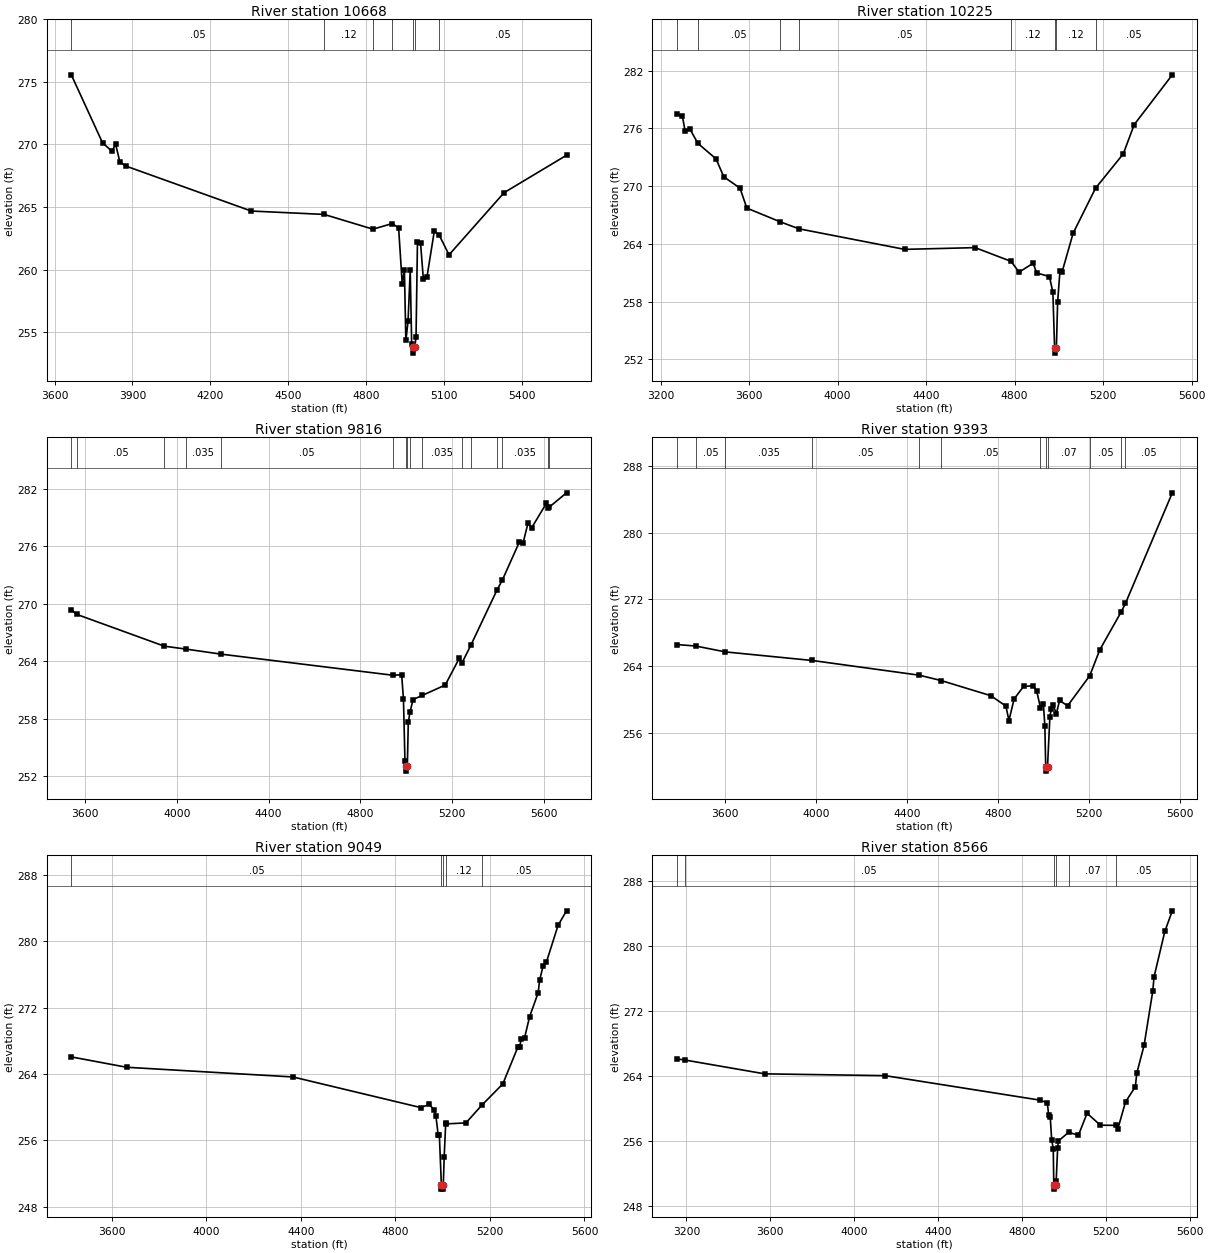
Type RM Length L Ch R = 1 ,10668   ,443,443,443
BEGIN DESCRIPTION:
COTTLE CREEK 24.0
END DESCRIPTION:
XS GIS Cut Line= 3
      2469075.01     13711024.99        2470275.       13710425.
      2470674.99     13710025.01
#Sta/Elev= 30
  3664.5  275.57  3784.7  270.14    3821  269.46    3835  270.03  3851.8  268.59
  3874.1  268.28  4357.7  264.68  4638.2  264.41  4826.2  263.23  4900.8  263.68
  4925.1  263.33    4939  258.86  4947.4  259.95    4953  254.33  4961.4  255.85
  4969.8  259.96  4975.4  254.01  4979.9  253.82  4980.4  253.32  4987.7  253.82
  4992.2  254.64  4997.7  262.22  5009.7  262.09  5020.3  259.26  5034.4  259.42
  5062.7  263.09    5081  262.77  5119.3  261.18  5331.4  266.15  5571.8  269.14
#Mann= 7 ,-1 , 0
  3664.5     .05       0  4638.2     .12       0  4826.2     .05       0
  4900.8     .12       0  4979.9     .05       0  4987.7     .12       0
    5081     .05       0
Bank Sta=4979.9,4987.7
XS Rating Curve= 0 ,0
Exp/Cntr=0.3,0.1

Type RM Length L Ch R = 1 ,10225   ,409,409,409
BEGIN DESCRIPTION:
COTTLE CREEK 23.0
END DESCRIPTION:
XS GIS Cut Line= 3
      2469144.63     13711526.14        2470625.       13710625.
       2470970.6      13710257.3
#Sta/Elev= 30
  3274.9  277.54  3298.7  277.28  3311.1  275.76  3333.9   275.9  3368.6  274.46
  3450.9  272.84  3486.1  270.97  3559.1   269.8    3590  267.72  3741.5  266.29
  3825.3  265.57  4302.9  263.43  4621.6  263.61  4784.3  262.18    4820  261.06
    4884  261.99  4899.5  260.98  4957.6   260.6  4972.9  258.96  4980.8  253.14
  4981.3  252.64  4988.7  253.14  4994.4  257.94    5005  261.21  5015.1  261.12
  5064.4  265.11  5165.7  269.79    5291  273.36  5340.4   276.4  5512.6  281.58
#Mann= 8 ,-1 , 0
  3274.9     .07       0  3368.6     .05       0  3741.5     .07       0
  3825.3     .05       0  4784.3     .12       0  4980.8     .05       0
  4988.7     .12       0  5165.7     .05       0
Bank Sta=4980.8,4988.7
XS Rating Curve= 0 ,0
Exp/Cntr=0.3,0.1

Type RM Length L Ch R = 1 ,9816    ,423,423,423
BEGIN DESCRIPTION:
COTTLE CREEK 22.0
END DESCRIPTION:
XS GIS Cut Line= 3
      2469412.44     13711863.64      2470687.35     13710851.21
       2470955.2     13710395.85
#Sta/Elev= 30
  3540.8  269.37  3563.7  268.89  3945.9  265.56  4039.2  265.26  4192.8  264.73
  4939.5  262.53  4979.2  262.57    4987  260.05  4993.6  253.56  4996.1  253.01
  4996.6  252.51    5004  253.01  5008.1  257.59  5015.9  258.72  5028.9  259.99
  5068.1  260.41  5168.8   261.5  5230.7  264.32  5241.3  263.78  5281.1  265.69
  5393.4  271.38  5417.1  272.44  5492.3  276.47    5508  276.35  5529.5  278.44
  5545.1  277.92  5609.5  280.49  5618.2  280.04  5621.1  280.07  5697.1  281.58
#Mann= 16 ,-1 , 0
  3540.8     .07       0  3563.7     .05       0  3945.9     .07       0
  4039.2    .035       0  4192.8     .05       0  4939.5    .063       0
  4996.1    .063       0    5004    .063       0  5015.9     .12       0
  5068.1    .035       0  5241.3    .063       0  5281.1    .035       0
  5393.4     .12       0  5417.1    .035       0  5618.2     .05       0
  5621.1    .063       0
Bank Sta=4996.1,5004
XS Rating Curve= 0 ,0
Exp/Cntr=0.3,0.1

Type RM Length L Ch R = 1 ,9393    ,344,344,344
BEGIN DESCRIPTION:
COTTLE CREEK 21.0
END DESCRIPTION:
XS GIS Cut Line= 3
      2469953.48     13712586.78      2470831.98     13711247.61
      2471275.01     13710874.99
#Sta/Elev= 30
  3387.2  266.57  3468.6   266.4  3599.7  265.69  3981.9  264.66  4453.8  262.89
  4550.7  262.24  4768.5  260.43  4834.9  259.18  4848.4  257.44  4871.1  260.04
  4913.2  261.55  4956.1  261.61  4970.5     261  4986.9     259    5000  259.46
  5006.5  256.81  5010.3  251.86  5010.8  251.36  5018.2  251.86  5028.6  257.89
  5035.1  258.85  5042.9  259.28  5057.2  258.26  5071.2  259.85  5106.6  259.21
    5204  262.82  5248.4  265.94  5343.4  270.54  5361.3  271.52  5567.7  284.81
#Mann= 12 ,-1 , 0
  3387.2    .035       0  3468.6     .05       0  3599.7    .035       0
  3981.9     .05       0  4453.8    .035       0  4550.7     .05       0
  4986.9     .07       0  5010.3     .05       0  5018.2     .07       0
    5204     .05       0  5343.4     .07       0  5361.3     .05       0
Bank Sta=5010.3,5018.2
XS Rating Curve= 0 ,0
Exp/Cntr=0.3,0.1

Type RM Length L Ch R = 1 ,9049    ,483,483,483
BEGIN DESCRIPTION:
COTTLE CREEK 20.0
END DESCRIPTION:
XS GIS Cut Line= 3
      2470074.99     13712675.01      2471062.32     13711477.95
      2471474.98     13711125.01
#Sta/Elev= 30
  3429.3  266.05  3663.2   264.8  4366.8  263.63    4907  259.94  4942.7  260.31
  4963.5   259.7  4971.4  258.92    4981  256.67    4986  256.67  4994.6   250.6
  4995.1   250.1  5002.3   250.1  5002.8   250.6  5006.4  253.96    5013  258.07
  5015.9  257.97  5098.6  258.09  5165.2  260.21  5254.5  262.79  5318.2  267.24
  5325.9  267.27  5332.5  268.24  5346.7  268.38  5367.6  270.87  5403.8  273.78
  5410.4  275.32  5424.7     277  5438.9  277.48  5488.3  281.93    5524  283.67
#Mann= 5 ,-1 , 0
  3429.3     .05       0  4994.6     .05       0  5002.8     .05       0
  5015.9     .12       0  5165.2     .05       0
Bank Sta=4994.6,5002.8
XS Rating Curve= 0 ,0
Exp/Cntr=0.3,0.1

Type RM Length L Ch R = 1 ,8566    ,527,527,527
BEGIN DESCRIPTION:
COTTLE CREEK 19.0
END DESCRIPTION:
XS GIS Cut Line= 3
      2470174.99     13713025.01      2471383.73     13711665.44
       2471512.3     13711140.45
#Sta/Elev= 30
  3155.3  266.06  3191.3  265.94    3573  264.23  4146.6  264.01  4883.3     261
  4919.3  260.68    4926  259.16  4933.5  258.89  4940.2   256.1  4947.7  255.04
  4950.3  250.54  4950.8  250.04  4958.6  250.54  4961.7  251.04  4968.6  255.11
  4971.7  255.95  5020.9  257.04  5067.6  256.67  5108.8  259.38  5172.4  257.91
  5247.2  257.89  5255.6  257.47    5292  260.77  5338.8  262.65  5345.6  264.29
  5380.4  267.73    5422  274.43  5427.9  276.16  5479.4  281.77    5515   284.3
#Mann= 6 ,-1 , 0
  3155.3    .035       0  3191.3     .05       0  4950.3     .05       0
  4958.6     .05       0  5020.9     .07       0  5247.2     .05       0
Bank Sta=4950.3,4958.6
XS Rating Curve= 0 ,0
Exp/Cntr=0.3,0.1