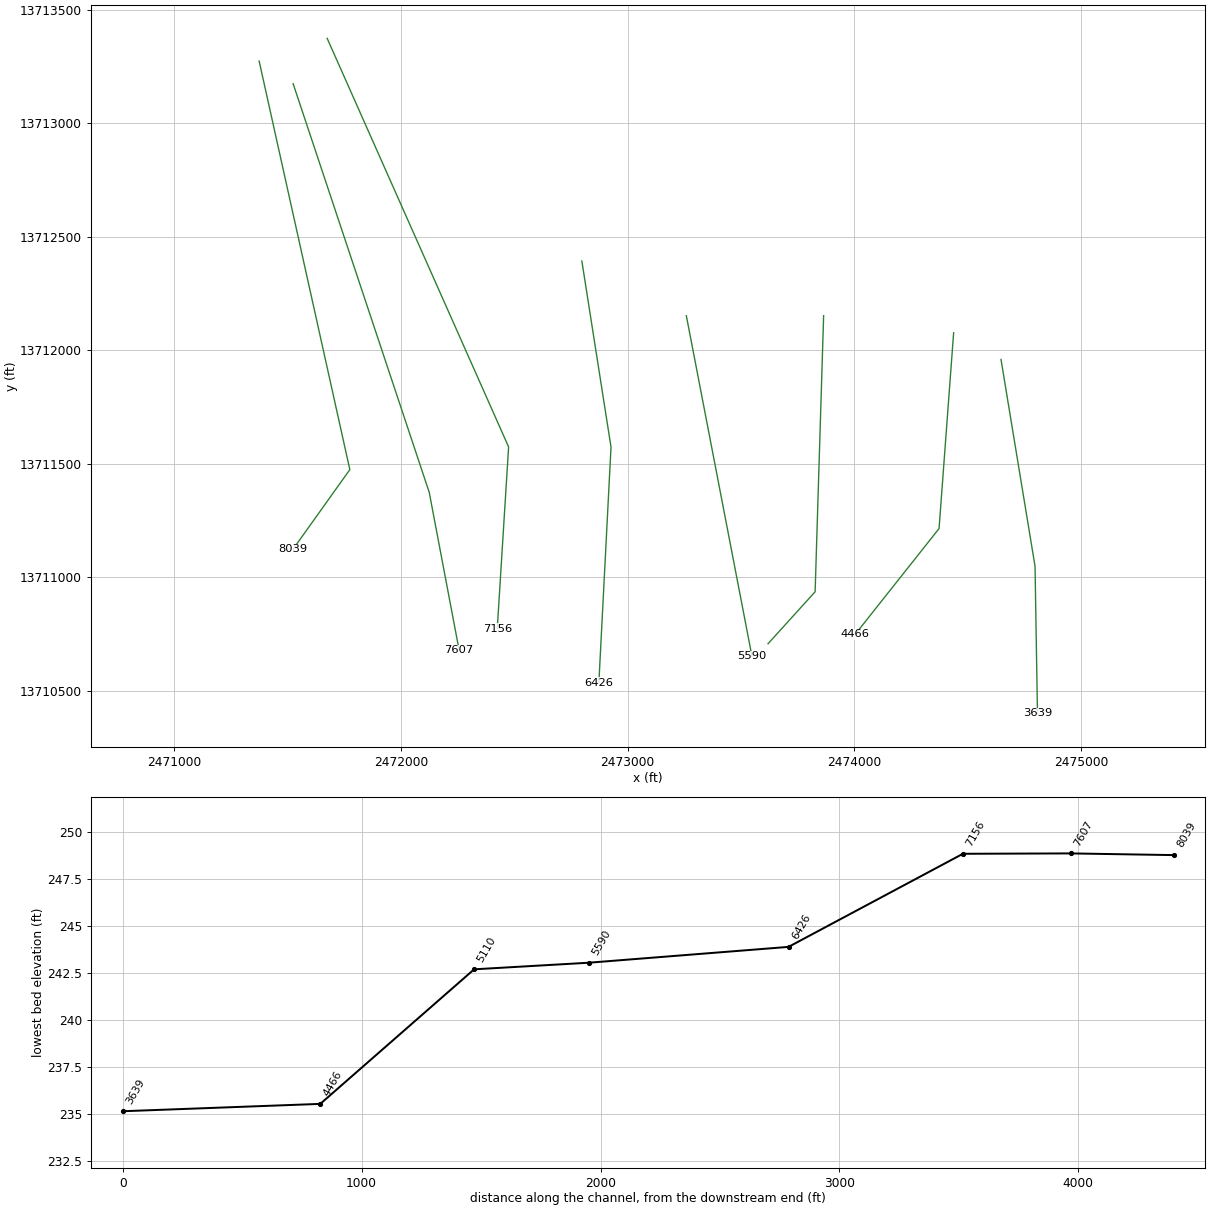
HEC-RAS study COTTLE CREEK.prj: COTTLE CREEK Base Level Engineering

--- COTTLE CREEK.g01 (geometry) --- (continued)

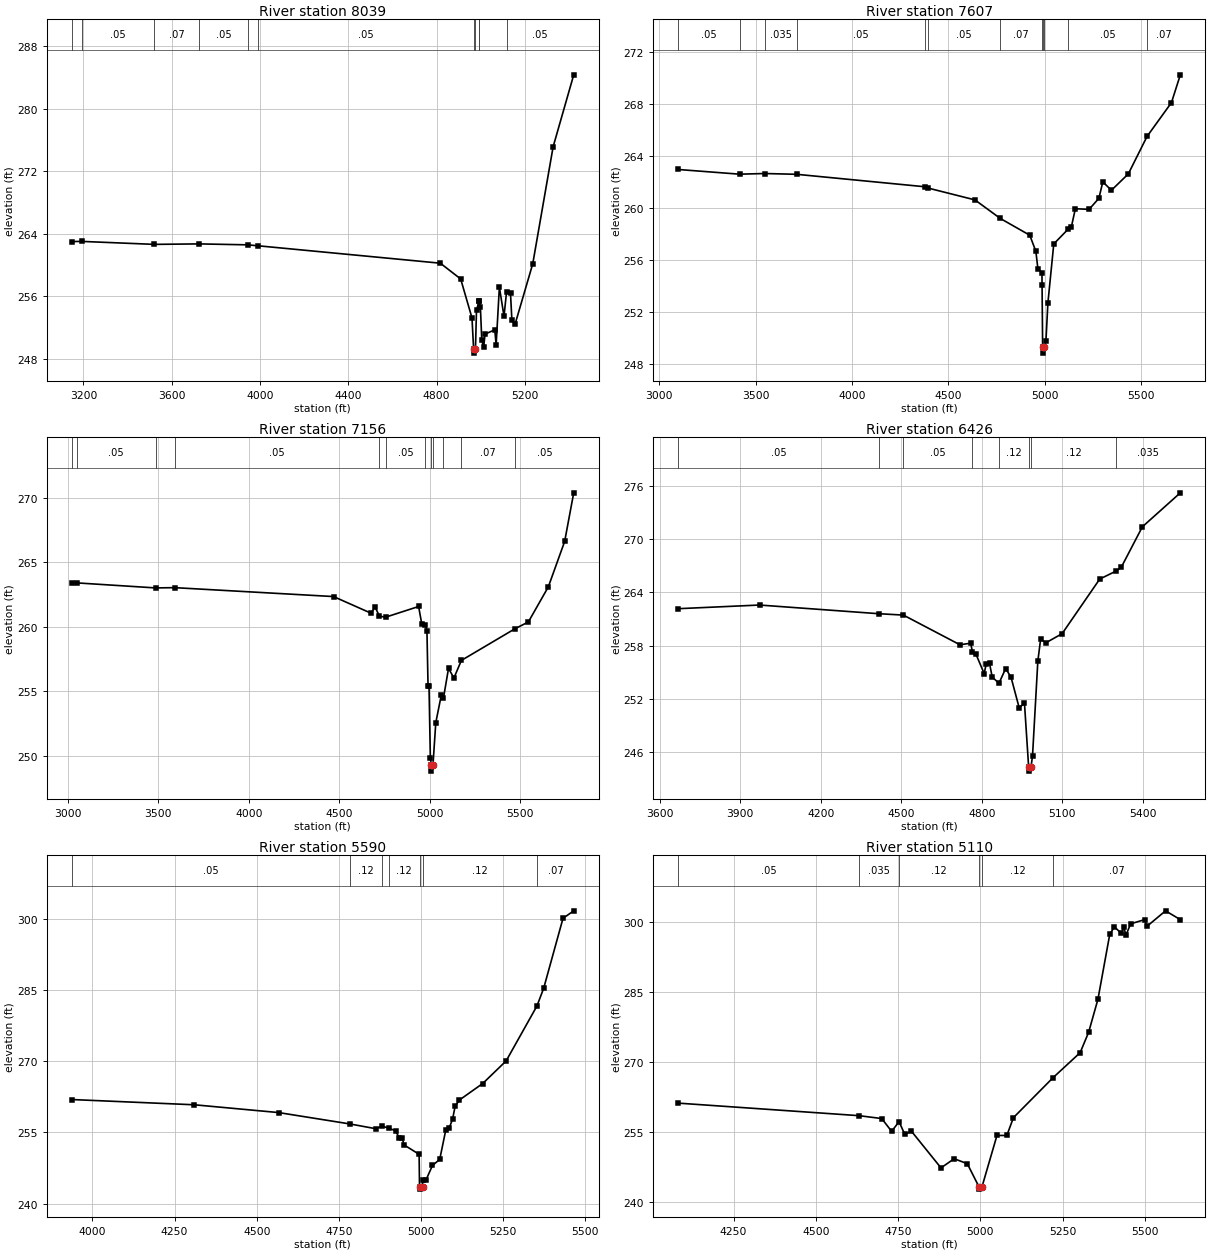
Type RM Length L Ch R = 1 ,8039    ,432,432,432
BEGIN DESCRIPTION:
COTTLE CREEK 18.0
END DESCRIPTION:
XS GIS Cut Line= 3
      2471374.99     13713275.03        2471775.       13711475.
      2471524.97     13711124.96
#Sta/Elev= 30
    3147  263.03  3192.4  263.05  3520.5  262.67  3724.9  262.73  3943.6  262.61
  3990.6  262.49  4816.8  260.26    4909  258.24  4960.2  253.25  4967.6  249.25
  4968.1  248.75  4975.9  249.25  4980.7  254.32  4993.2  255.37  4993.4  255.37
  4998.3  254.65  5004.5  250.42  5013.1  249.49  5019.2  251.18  5063.4  251.74
  5069.6  249.82  5084.3   257.2  5105.2  253.47  5116.9   256.6  5134.7   256.4
  5140.9  252.99  5155.6  252.47  5235.5  260.19  5327.7  275.15  5421.1  284.37
#Mann= 11 ,-1 , 0
    3147     .07       0  3192.4     .05       0  3520.5     .07       0
  3724.9     .05       0  3943.6    .035       0  3990.6     .05       0
  4967.6     .05       0  4975.9     .05       0  4993.2     .07       0
  4993.4     .12       0  5116.9     .05       0
Bank Sta=4967.6,4975.9
XS Rating Curve= 0 ,0
Exp/Cntr=0.3,0.1

Type RM Length L Ch R = 1 ,7607    ,451,451,451
BEGIN DESCRIPTION:
COTTLE CREEK 17.0
END DESCRIPTION:
XS GIS Cut Line= 3
        2471525.     13713174.99        2472125.       13711375.
      2472256.87     13710679.85
#Sta/Elev= 30
  3098.4  262.98  3415.7  262.62  3546.4  262.67  3712.1  262.61  4378.5  261.65
  4394.2  261.55  4637.4  260.64  4769.1  259.21    4922  257.92  4953.6  256.68
  4964.1  255.35  4985.2  255.04  4985.8  254.09  4988.8  249.34  4989.3  248.84
  4997.4  249.34  5005.9  249.77  5016.1   252.7  5046.6  257.25  5121.5  258.39
  5138.2  258.58  5158.6  259.96  5229.9  259.91  5280.7  260.76  5301.1  262.03
  5345.7  261.38  5433.4  262.64  5530.8  265.53  5657.3  268.13  5703.3  270.27
#Mann= 12 ,-1 , 0
  3098.4     .05       0  3415.7     .07       0  3546.4    .035       0
  3712.1     .05       0  4378.5     .07       0  4394.2     .05       0
  4769.1     .07       0  4985.8     .12       0  4988.8     .05       0
  4997.4     .12       0  5121.5     .05       0  5530.8     .07       0
Bank Sta=4988.8,4997.4
XS Rating Curve= 0 ,0
Exp/Cntr=0.3,0.1

Type RM Length L Ch R = 1 ,7156    ,730,730,730
BEGIN DESCRIPTION:
COTTLE CREEK 16.0
END DESCRIPTION:
XS GIS Cut Line= 3
      2471675.01     13713374.98        2472475.       13711575.
        2472425.     13710775.01
#Sta/Elev= 30
  3022.9  263.43  3050.1  263.41  3485.3  263.02  3591.7  263.04  4468.1  262.35
  4675.3  261.06  4697.2  261.54  4721.8  260.83  4755.1  260.75  4937.9  261.58
    4955  260.24  4974.9  260.15  4983.8   259.7  4989.9  255.44  4995.2  255.44
  5002.7   249.8  5008.1  249.32  5008.6  248.82  5017.2  249.32  5032.7  252.58
  5062.8  254.69    5075  254.48  5102.9  256.78  5132.9  256.04  5173.9   257.4
  5470.4  259.86  5543.7  260.38  5653.9   263.1  5744.1  266.62  5794.2  270.39
#Mann= 12 ,-1 , 0
  3022.9     .07       0  3050.1     .05       0  3485.3    .035       0
  3591.7     .05       0  4721.8     .07       0  4755.1     .05       0
  4974.9     .07       0  5008.1     .05       0  5017.2     .07       0
    5075     .12       0  5173.9     .07       0  5470.4     .05       0
Bank Sta=5008.1,5017.2
XS Rating Curve= 0 ,0
Exp/Cntr=0.3,0.1

Type RM Length L Ch R = 1 ,6426    ,836,836,836
BEGIN DESCRIPTION:
X18565
END DESCRIPTION:
XS GIS Cut Line= 3
      2472797.92     13712393.95      2472926.48     13711574.37
      2472872.91     13710535.15
#Sta/Elev= 30
  3669.8  262.15  3972.4  262.56  4418.5  261.58  4508.2  261.43  4719.1  258.09
  4759.1  258.27  4765.7  257.23  4779.1     257  4809.2  254.85  4816.8  255.94
  4829.2  255.99  4839.2  254.45  4864.4  253.77  4889.3  255.42  4909.3  254.44
  4939.4  251.03  4959.4  251.49  4974.8  244.38  4975.3  243.88    4984  244.38
  4989.4  245.63  5009.1  256.24  5019.5  258.72  5039.5  258.32  5099.6  259.34
  5239.7  265.48  5300.7  266.38  5319.9   266.8  5398.6  271.36    5540  275.18
#Mann= 8 ,-1 , 0
  3669.8     .05       0  4418.5     .07       0  4508.2     .05       0
  4765.7    .035       0  4864.4     .12       0  4974.8     .05       0
    4984     .12       0  5300.7    .035       0
Bank Sta=4974.8,4984
XS Rating Curve= 0 ,0
Exp/Cntr=0.3,0.1

Type RM Length L Ch R = 1 ,5590    ,480,480,480
BEGIN DESCRIPTION:
X18564
END DESCRIPTION:
XS GIS Cut Line= 2
      2473258.59     13712152.94      2473547.87     13710652.98
#Sta/Elev= 30
  3937.2  261.95  4310.6  260.84  4566.5   259.2  4782.6  256.81  4861.9   255.8
  4882.3  256.34  4901.6  255.89    4923  255.36  4933.2  253.89  4943.1  253.79
  4948.2  252.38  4994.3  250.39  4995.5  243.54    4996  243.04  5004.7  243.54
  5005.2  245.04  5014.6  244.88    5035  248.04    5057  249.31  5075.7  255.61
  5085.9  255.97  5096.1   257.8  5103.8  260.49  5116.5  261.83  5187.8  265.33
  5259.1   270.1  5352.9   281.7  5373.3  285.42  5432.2   300.2  5464.8  301.78
#Mann= 7 ,-1 , 0
  3937.2     .05       0  4782.6     .12       0  4882.3    .035       0
  4901.6     .12       0  4995.5     .05       0  5004.7     .12       0
  5352.9     .07       0
Bank Sta=4995.5,5004.7
XS Rating Curve= 0 ,0
Exp/Cntr=0.3,0.1

Type RM Length L Ch R = 1 ,5110    ,644,644,644
BEGIN DESCRIPTION:
X18563
END DESCRIPTION:
XS GIS Cut Line= 3
      2473863.91     13712152.91      2473826.42     13710936.92
      2473618.74     13710707.94
#Sta/Elev= 30
  4082.1  261.16    4631  258.47  4700.3  257.85  4730.3   255.1  4752.9  257.18
  4770.3  254.45  4790.3  255.15  4880.4  247.25  4920.4  249.22  4960.4  248.15
  4995.8  243.19  4996.3  242.69    5005  243.19  5050.5  254.22  5080.5  254.21
  5100.5  258.04  5221.4  266.66  5303.3     272  5329.1  276.38  5357.4  283.47
  5393.3  297.42  5407.5  299.05  5428.4  297.61  5435.8  298.97  5442.6  297.25
  5456.8  299.68  5499.4  300.58  5506.1  299.12  5562.9  302.47  5607.8  300.58
#Mann= 6 ,-1 , 0
  4082.1     .05       0    4631    .035       0  4752.9     .12       0
  4995.8     .05       0    5005     .12       0  5221.4     .07       0
Bank Sta=4995.8,5005
XS Rating Curve= 0 ,0
Exp/Cntr=0.3,0.1

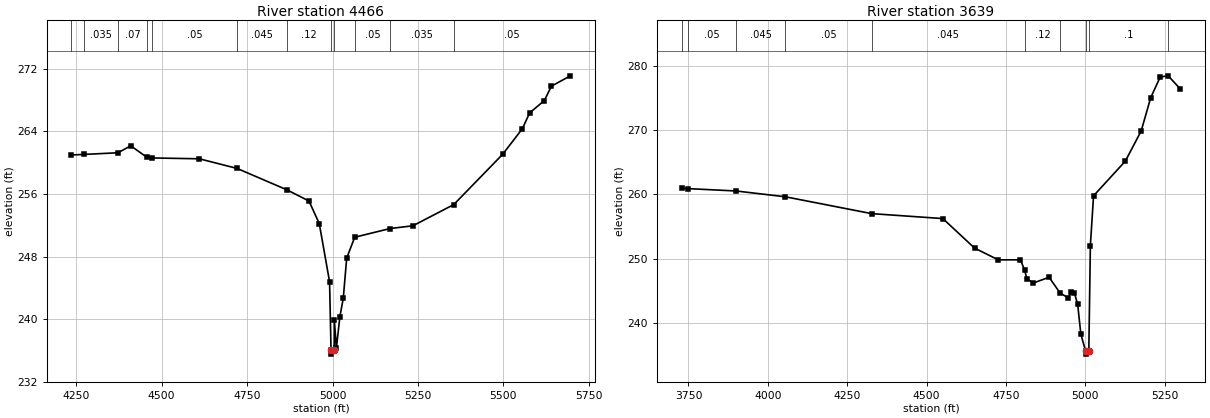
Type RM Length L Ch R = 1 ,4466    ,827,827,827
BEGIN DESCRIPTION:
X18562
END DESCRIPTION:
XS GIS Cut Line= 3
      2474437.09      13712077.9      2474372.81     13711215.47
       2474003.4      13710749.7
#Sta/Elev= 30
  4236.4  260.97  4273.4  261.04  4372.3  261.25  4409.8  262.14  4456.7  260.68
  4471.3  260.59  4610.3  260.48  4720.9  259.25  4867.1  256.51  4931.2  255.09
  4961.3  252.21  4991.4  244.79  4995.7  236.05  4996.2  235.55  5005.1  236.05
  5005.4  239.86  5011.4  236.33  5021.5  240.31  5031.5  242.68  5041.5  247.81
    5065  250.47  5168.5  251.58  5235.2  251.93  5354.8  254.64  5497.9  261.06
  5555.6  264.33  5576.4  266.32  5619.7  267.92  5640.5  269.75  5695.7  271.07
#Mann= 12 ,-1 , 0
  4236.4     .05       0  4273.4    .035       0  4372.3     .07       0
  4456.7    .035       0  4471.3     .05       0  4720.9    .045       0
  4867.1     .12       0  4995.7     .05       0  5005.1     .12       0
    5065     .05       0  5168.5    .035       0  5354.8     .05       0
Bank Sta=4995.7,5005.1
XS Rating Curve= 0 ,0
Exp/Cntr=0.3,0.1

Type RM Length L Ch R = 1 ,3639    ,0,0,0
BEGIN DESCRIPTION:
X18561
END DESCRIPTION:
XS GIS Cut Line= 3
        2474646.     13711960.06      2474795.99     13711049.41
      2474806.71     13710401.21
#Sta/Elev= 30
  3728.5  260.95  3749.3  260.91  3900.7  260.54  4055.3  259.64  4326.8  257.02
  4551.2  256.25  4651.1  251.66  4725.8  249.83  4795.8  249.83  4809.1  248.18
  4815.8   246.9  4835.9  246.22  4885.9  247.12  4920.5  244.67  4945.9  243.92
  4955.9  244.81  4965.9  244.63  4975.9  242.91  4985.9  238.27  5000.8  235.66
  5001.3  235.16    5011  235.66  5015.9  252.06  5025.9  259.79  5125.9  265.18
  5175.9  269.88  5205.9  275.05  5235.9  278.28  5261.1  278.46  5299.7  276.38
#Mann= 10 ,-1 , 0
  3728.5     .07       0  3749.3     .05       0  3900.7    .045       0
  4055.3     .05       0  4326.8    .045       0  4809.1     .12       0
  4920.5      .1       0  5000.8     .05       0    5011      .1       0
  5261.1     .07       0
Bank Sta=5000.8,5011
XS Rating Curve= 0 ,0
Exp/Cntr=0.3,0.1

Chan Stop Cuts=-1
Use User Specified Reach Order=0
Composite Channel Slope=5