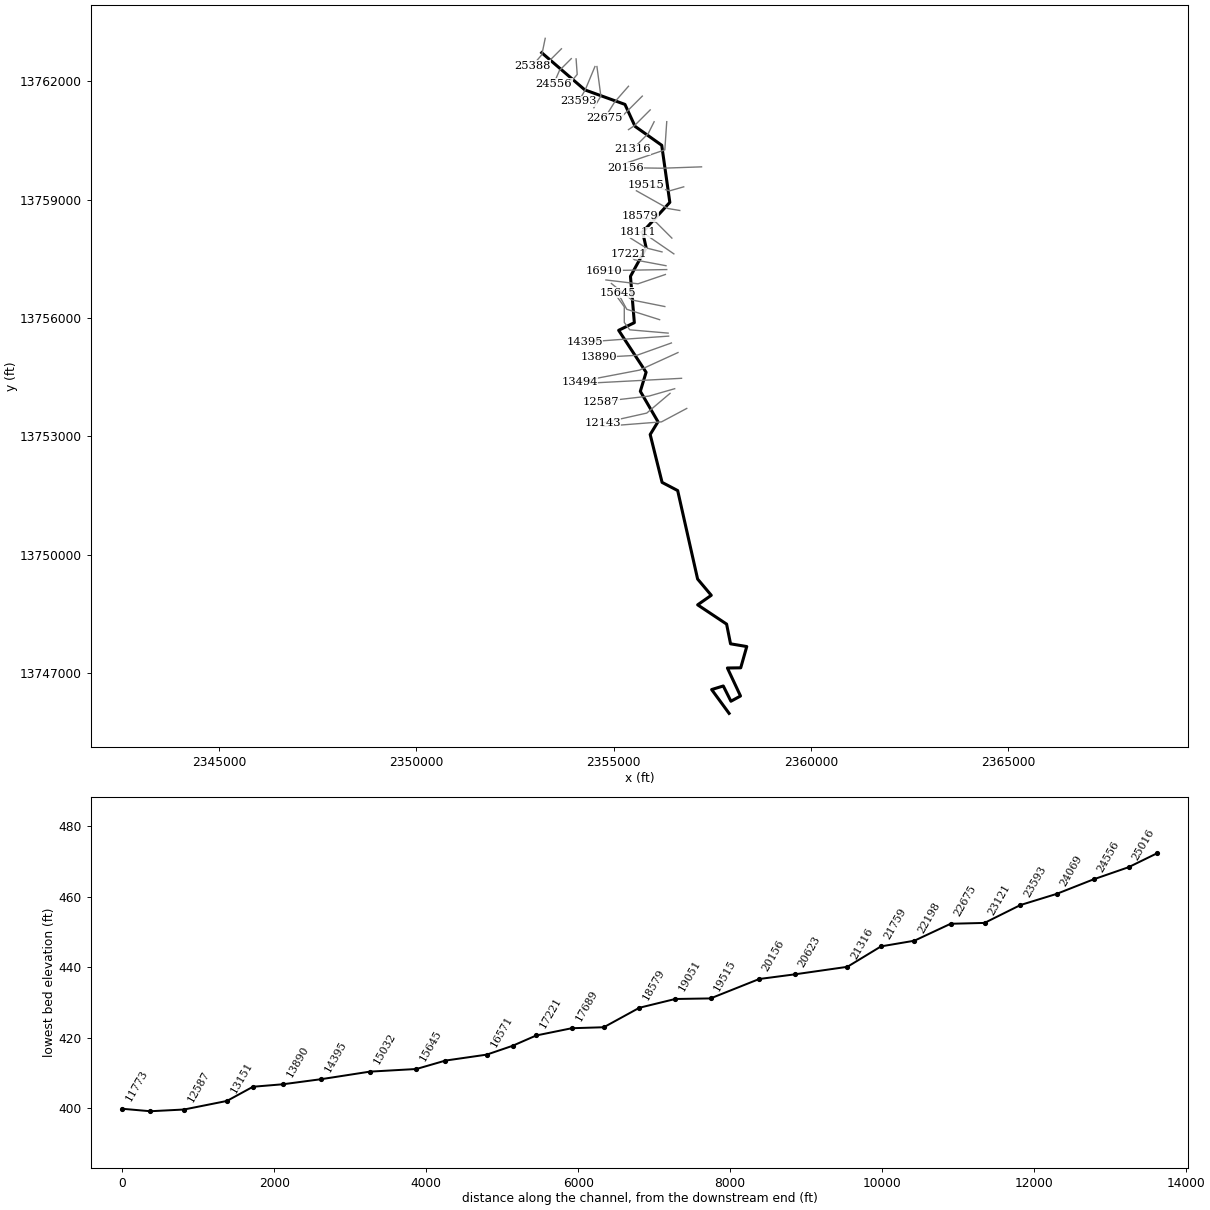
--- DARST CREEK.prj (project) ---

Proj Title=DARST CREEK Base Level Engineering
Current Plan=p01
Default Exp/Contr=0.3,0.1
English Units
Geom File=g01
Flow File=f01
Plan File=p01
Y Axis Title=Elevation
X Axis Title(PF)=Main Channel Distance
X Axis Title(XS)=Station
BEGIN DESCRIPTION:
DARST CREEK
END DESCRIPTION:
DSS Export Rating Curves= 0
DSS Export Rating Curve Sorted= 0
DSS Export Volume Flow Curves= 0
DXF OffsetX= 0
DXF OffsetY= 0
DXF ScaleX= 1
DXF ScaleY= 10

--- DARST CREEK.p01 (plan) ---

Plan Title=Multiple Run
Program Version=4.10
Short Identifier=Multiple
Geom File=g01
Flow File=f01
Subcritical Flow
K Sum by GR= 0
Std Step Tol= 0.01
Critical Tol= 0.01
Num of Std Step Trials= 20
Max Error Tol= 0.3
Flow Tol Ratio= 0.001
Split Flow NTrial= 30
Split Flow Tol= 0.02
Split Flow Ratio= 0.02
Log Output Level= 0
Friction Slope Method= 1
Unsteady Friction Slope Method= 2
Unsteady Bridges Friction Slope Method= 1
Parabolic Critical Depth
Global Vel Dist= 1 , 1 , 1
Global Log Level= 0
CheckData=True
Encroach Param=-1 ,0,0, 0
BEGIN DESCRIPTION:
Multiple Run
END DESCRIPTION:
Computation Interval=1HOUR
Output Interval=1HOUR
Run HTab= 0
Run UNet= 0
Run PostProcess= 0
Run WQNet= 0
UNET Theta= 1
UNET Theta Warmup= 1
UNET ZTol= 0.02
UNET ZSATol= 0.05
UNET MxIter= 20
UNET MaxInSteps= 0
UNET DtIC= 0
UNET DtMin= 0
UNET MaxCRTS= 20
UNET WFStab= 2
UNET SFStab= 1
UNET WFX= 1
UNET SFX= 1
UNET DSS MLevel= 4
UNET DZMax Abort= 100
UNET Convert EG Bridges= 0
UNET Use Existing IB Tables=-1
UNET Froude Reduction=False
UNET Froude Limit= 1
UNET Froude Power= 10
UNET Time Slicing=0,0, 5
UNET Junction Losses=0
Instantaneous Interval=1HOUR
Write IC File= 0
Write IC File at Sim End=0
Echo Input=False
Echo Parameters=False
Echo Output=False
Write Detailed= 0
WQ AD Non Conservative
WQ ULTIMATE=-1
WQ Max Comp Step=1HOUR
WQ Output Interval=15MIN
WQ Output Selected Increments= 0
WQ Output face flow=0
WQ Output face velocity=0
WQ Output face area=0
WQ Output face dispersion=0
WQ Output cell volume=0
WQ Output cell surface area=0
WQ Output cell continuity=0
WQ Output cumulative cell continuity=0
WQ Output face conc=0
WQ Output face dconc_dx=0
WQ Output face courant=0
WQ Output face peclet=0
WQ Output face adv mass=0
WQ Output face disp mass=0
WQ Output cell mass=0
WQ Output cell source sink temp=0
WQ Output cell source sink nsm=0
WQ Output MaxMinRange=-1
WQ Daily Max Min Mean=-1
WQ Daily Range=0
WQ Daily Time=0
WQ Create Restart=0
WQ Fixed Restart=0
WQ System Summary=0
WQ Use Fixed Temperature=0
Sorting and Armoring Iterations= 10
XS Update Threshold= 0.02
Hydraulics Update Threshold= 0.02
Energy Slope Method= 1
Volume Change Method= 0
XS Weighting Method= 0
Number of US Weighted Cross Sections= 1
Number of DS Weighted Cross Sections= 1
Upstream XS Weight=0.25
Main XS Weight=0.5
Downstream XS Weight=0.25
Number of DS XS's Weighted with US Boundary= 1
Upstream Boundary Weight= 1
Weight of XSs Associated with US Boundary= 0
Number of US XS's Weighted with DS Boundary= 1
Downstream Boundary Weight= 0.5
Weight of XSs Associated with DS Boundary= 0.5
Sediment Output Level= 4
Mass or Volume Output= 0
Output Increment Type= 1
Profile and TS Output Increment= 10
XS Output Flag= 0
XS Output Increment= 10
Disregard all LS=0
Disregard all Conn=0
Disregard all Breaches=0
Disregard all Pumps=0

--- DARST CREEK.f01 (steady flow) ---

Flow Title=Multiple
Number of Profiles=7
Profile Names=10-year,25-year,50-year,1pct_min,100-year,1pct_plu,500-year
River Rch & RM= DARST CREEK,Reach-1,25388
     560     903    1213     790    1577    3146    2637
River Rch & RM= DARST CREEK,Reach-1,23593
     700    1144    1551    1018    2032    4054    3455
River Rch & RM= DARST CREEK,Reach-1,22675
     825    1358    1850    1219    2433    4854    4170
River Rch & RM= DARST CREEK,Reach-1,20156
    1226    2062    2848    1901    3794    7569    6676
River Rch & RM= DARST CREEK,Reach-1,16571
    1298    2187    3026    2023    4036    8052    7120
River Rch & RM= DARST CREEK,Reach-1,16027
    1517    2577    3583    2406    4801    9579    8550
River Rch & RM= DARST CREEK,Reach-1,14395
    1967    3375    4723    3190    6364   12698   11464
River Rch & RM= DARST CREEK,Reach-1,10583
    2247    3877    5447    3691    7364   14694   13356
River Rch & RM= DARST CREEK,Reach-1,9698
    2519    4367    6154    4182    8343   16647   15218
River Rch & RM= DARST CREEK,Reach-1,6925
    2547    4395    6173    4180    8340   16640   15100
Boundary for River Rch & Prof#=DARST CREEK,Reach-1,1
Up Type=0
Dn Type=3
Dn Slope=0.005
Boundary for River Rch & Prof#=DARST CREEK,Reach-1,2
Up Type=0
Dn Type=3
Dn Slope=0.005
Boundary for River Rch & Prof#=DARST CREEK,Reach-1,3
Up Type=0
Dn Type=3
Dn Slope=0.005
Boundary for River Rch & Prof#=DARST CREEK,Reach-1,4
Up Type=0
Dn Type=3
Dn Slope=0.005
Boundary for River Rch & Prof#=DARST CREEK,Reach-1,5
Up Type=0
Dn Type=3
Dn Slope=0.005
Boundary for River Rch & Prof#=DARST CREEK,Reach-1,6
Up Type=0
Dn Type=3
Dn Slope=0.005
Boundary for River Rch & Prof#=DARST CREEK,Reach-1,7
Up Type=0
Dn Type=3
Dn Slope=0.005

--- DARST CREEK.g01 (geometry) ---

Geom Title=Existing Conditions
Program Version=4.10

River Reach=DARST CREEK     ,Reach-1
Reach XY= 30
        2353175.       13762725.      2354268.48     13761782.67
      2355285.18     13761414.68      2355541.38     13760857.91
       2356217.4     13760378.34      2356422.74     13758930.94
      2355732.81     13758178.41      2355822.74     13757780.94
      2355425.07     13757054.97      2355523.13     13755880.69
      2355125.81     13755686.94      2355821.33     13754623.42
      2355675.13     13754140.76       2356122.9     13753368.95
      2355924.94     13753044.99      2356226.68     13751831.14
      2356621.57     13751623.78      2357127.05     13749380.86
      2357473.26     13748968.84      2357128.09     13748726.64
      2357861.61     13748238.33      2357961.76     13747738.61
      2358373.04     13747669.35      2358219.89     13747129.96
      2357882.18     13747125.33      2358214.54     13746415.18
      2357971.68     13746283.04      2357777.72     13746669.72
      2357482.68      13746578.7        2357925.       13745975.

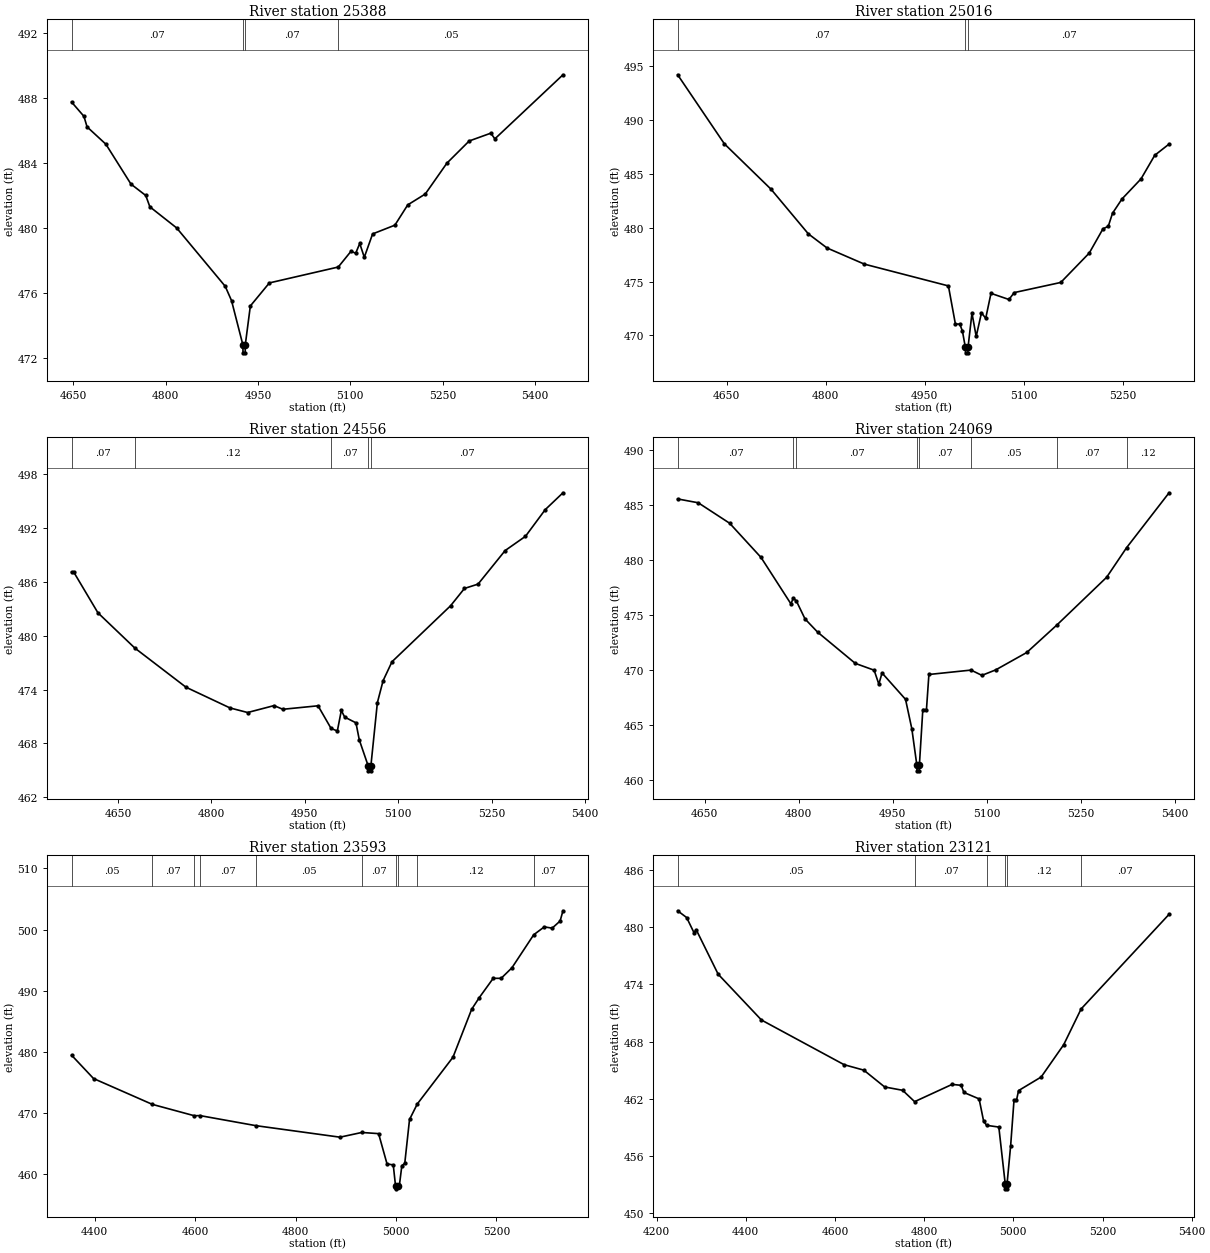
Type RM Length L Ch R = 1 ,25388   ,372,372,372
BEGIN DESCRIPTION:
X18733
END DESCRIPTION:
XS GIS Cut Line= 3
      2353264.08     13763089.63      2353178.25     13762674.22
       2352934.8     13762389.62
#Sta/Elev= 30
    4647  487.77  4667.1  486.89  4672.2  486.24  4702.8  485.17  4743.6  482.71
  4767.6  482.01  4774.3  481.31  4817.8  480.01  4896.8  476.41    4907  475.53
  4925.4  472.81  4925.7  472.31  4929.2  472.31  4929.4  472.81  4937.6   475.2
  4968.5  476.62  5080.5   477.6  5101.2  478.57  5108.8  478.45  5115.4  479.05
  5122.8   478.2  5136.3  479.64  5172.5  480.18  5193.4  481.43  5221.9   482.1
    5257     484  5293.3  485.37  5328.4  485.85    5335   485.5  5445.7  489.45
#Mann= 4 ,-1 , 0
    4647     .07       0  4925.4     .05       0  4929.4     .07       0
  5080.5     .05       0
Bank Sta=4925.4,4929.4
XS Rating Curve= 0 ,0
Exp/Cntr=0.3,0.1

Type RM Length L Ch R = 1 ,25016   ,460,460,460
BEGIN DESCRIPTION:
DARST CREEK 49.0
END DESCRIPTION:
XS GIS Cut Line= 3
      2353675.02     13762825.02        2353375.       13762525.
      2353124.96     13762324.97
#Sta/Elev= 30
  4575.6  494.19  4646.3  487.79  4717.1  483.57  4773.6  479.43  4801.9  478.12
  4858.5  476.62  4985.8   474.6  4996.4  471.06  5003.1  471.06  5007.1  470.39
  5011.5  468.89  5011.8  468.39  5015.3  468.39  5015.5  468.89  5021.5  472.07
  5027.9  469.91  5035.9  472.11  5042.3  471.59  5050.3  473.91  5077.5  473.34
  5085.5  473.98    5156  474.92  5199.2  477.65    5220   479.9    5228  480.13
  5234.4  481.34  5248.8  482.67  5277.6  484.53  5298.4  486.72  5320.1  487.76
#Mann= 3 ,-1 , 0
  4575.6     .07       0  5011.5     .05       0  5015.5     .07       0
Bank Sta=5011.5,5015.5
XS Rating Curve= 0 ,0
Exp/Cntr=0.3,0.1

Type RM Length L Ch R = 1 ,24556   ,487,487,487
BEGIN DESCRIPTION:
DARST CREEK 48.0
END DESCRIPTION:
XS GIS Cut Line= 3
      2353924.97     13762574.97        2353625.       13762275.
      2353480.52     13761939.72
#Sta/Elev= 30
  4575.3   487.1  4578.8   487.1  4617.7  482.56    4677  478.63  4759.1  474.27
  4829.8  471.96  4858.1  471.45  4900.5  472.22  4914.7  471.81  4971.2   472.2
  4992.1  469.68  5002.2  469.39  5008.6  471.68    5014  470.94  5032.1   470.3
  5037.5  468.39    5052  465.45  5052.2  464.95  5055.7  464.95    5056  465.45
  5066.5  472.55  5075.7     475    5090  477.11  5184.1  483.35  5206.4  485.28
  5228.2  485.76  5271.7   489.5  5304.4  491.09  5336.1  494.06  5364.6  495.94
#Mann= 5 ,-1 , 0
  4575.3     .07       0    4677     .12       0  4992.1     .07       0
    5052     .05       0    5056     .07       0
Bank Sta=5052,5056
XS Rating Curve= 0 ,0
Exp/Cntr=0.3,0.1

Type RM Length L Ch R = 1 ,24069   ,476,476,476
BEGIN DESCRIPTION:
DARST CREEK 47.0
END DESCRIPTION:
XS GIS Cut Line= 3
      2354046.92     13762567.81        2354075.       13762175.
      2353825.01     13761875.02
#Sta/Elev= 30
  4606.6  485.53  4639.5  485.18  4689.6  483.32  4739.7  480.21  4787.4  475.99
  4791.2  476.52  4796.2  476.24  4809.9  474.62    4830  473.42  4890.1  470.58
  4920.2  469.96  4927.7  468.69  4932.8  469.71  4970.3  467.31  4980.4  464.62
  4988.4  461.31  4988.6  460.81  4992.1  460.81  4992.4  461.31  4997.9  466.38
  5003.7  466.38  5007.6  469.57  5074.8  469.97  5092.2  469.49  5114.3  469.99
  5163.8  471.57  5211.5  474.05  5291.3  478.41    5323  481.09  5390.9  486.09
#Mann= 8 ,-1 , 0
  4606.6     .07       0  4791.2     .12       0  4796.2     .07       0
  4988.4     .05       0  4992.4     .07       0  5074.8     .05       0
  5211.5     .07       0    5323     .12       0
Bank Sta=4988.4,4992.4
XS Rating Curve= 0 ,0
Exp/Cntr=0.3,0.1

Type RM Length L Ch R = 1 ,23593   ,472,472,472
BEGIN DESCRIPTION:
DARST CREEK 46.0
END DESCRIPTION:
XS GIS Cut Line= 3
      2354524.98     13762374.96        2354275.       13761775.
      2354109.49     13761490.96
#Sta/Elev= 30
  4353.7  479.49  4397.5  475.67  4514.6  471.45  4598.3  469.59  4609.2  469.62
    4721  467.97  4888.3  466.09  4931.7  466.86  4965.2  466.67    4982  461.72
  4994.4  461.56  4998.9  458.15  4999.2  457.65  5002.9  458.15  5006.5  458.15
  5011.5  461.43  5017.3  461.81  5026.8  468.98  5042.3  471.52  5113.3  479.15
  5150.5  486.98  5165.7  488.89  5193.5  492.05  5209.2  492.04  5230.7  493.76
  5274.1  499.16  5295.2  500.45  5310.9  500.24  5326.7  501.41  5332.4  503.08
#Mann= 10 ,-1 , 0
  4353.7     .05       0  4514.6     .07       0  4598.3     .05       0
  4609.2     .07       0    4721     .05       0  4931.7     .07       0
  4998.9     .05       0  5002.9     .07       0  5042.3     .12       0
  5274.1     .07       0
Bank Sta=4998.9,5002.9
XS Rating Curve= 0 ,0
Exp/Cntr=0.3,0.1

Type RM Length L Ch R = 1 ,23121   ,446,446,446
BEGIN DESCRIPTION:
DARST CREEK 45.0
END DESCRIPTION:
XS GIS Cut Line= 3
        2354575.     13762375.01        2354675.       13761625.
      2354497.23     13761329.14
#Sta/Elev= 30
  4247.4   481.7  4267.6  480.99    4284  479.41    4289  479.72  4338.2  475.06
  4435.3  470.26  4620.7  465.58  4664.8  465.01  4711.5  463.25  4751.8   462.9
  4778.7  461.71  4862.8  463.52    4883  463.42  4889.3  462.67  4923.3     462
  4933.4  459.67  4940.1  459.23  4967.5  459.05  4981.9  453.08  4982.1  452.58
  4985.6  452.58  4985.9  453.08    4994  457.09  5001.5  461.84    5007  461.84
  5011.8  462.87  5062.4  464.29  5112.9  467.67    5152  471.42  5349.2  481.33
#Mann= 6 ,-1 , 0
  4247.4     .05       0  4778.7     .07       0  4940.1     .12       0
  4981.9     .05       0  4985.9     .12       0    5152     .07       0
Bank Sta=4981.9,4985.9
XS Rating Curve= 0 ,0
Exp/Cntr=0.3,0.1

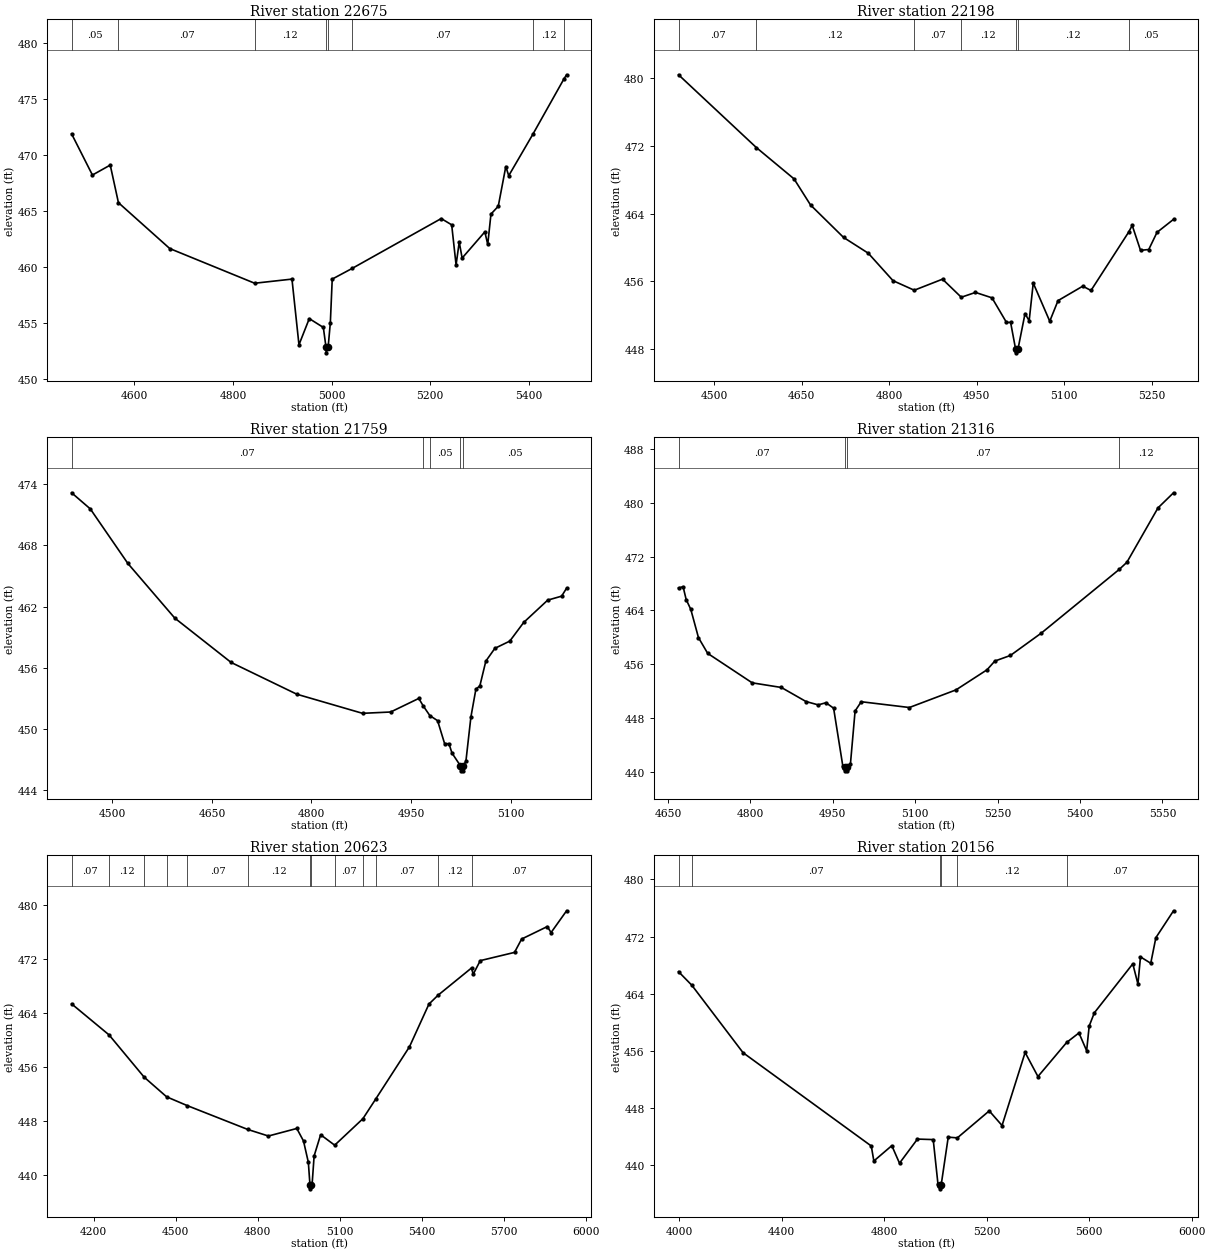
Type RM Length L Ch R = 1 ,22675   ,477,477,477
BEGIN DESCRIPTION:
DARST CREEK 44.0
END DESCRIPTION:
XS GIS Cut Line= 3
      2355375.01     13761875.01        2355025.       13761475.
      2354775.01     13761075.02
#Sta/Elev= 30
  4473.1  471.91  4515.3  468.23  4551.4  469.12    4568  465.76    4672  461.66
  4844.1  458.56  4919.7  458.93  4933.9  453.06  4954.8   455.4  4983.3  454.61
  4988.7  452.84    4989  452.34    4993  452.84  4997.5  455.04  5001.3  458.93
  5041.9  459.89  5222.2  464.34  5243.4  463.78  5252.3   460.2  5258.7  462.24
  5264.6  460.81  5310.6  463.15  5316.5  462.03    5323  464.74  5337.8  465.44
  5353.1  468.99    5359  468.17    5408  471.88  5471.3  476.85  5476.3  477.19
#Mann= 8 ,-1 , 0
  4473.1     .05       0    4568     .07       0  4844.1     .12       0
  4988.7     .05       0    4993     .12       0  5041.9     .07       0
    5408     .12       0  5471.3     .07       0
Bank Sta=4988.7,4993
XS Rating Curve= 0 ,0
Exp/Cntr=0.3,0.1

Type RM Length L Ch R = 1 ,22198   ,439,439,439
BEGIN DESCRIPTION:
DARST CREEK 43.0
END DESCRIPTION:
XS GIS Cut Line= 3
      2355725.02     13761625.02        2355325.       13761225.
      2355124.97     13761024.97
#Sta/Elev= 30
  4438.8  480.44  4572.3  471.82  4636.8  468.12  4665.1  465.03  4721.7  461.19
  4764.1  459.32  4806.5  456.07  4842.9  454.94  4891.4  456.25  4923.5  454.11
  4947.9  454.68  4976.2  454.04    5001  451.13  5008.1  451.13  5016.5  448.03
  5016.8  447.53  5020.9  448.03  5032.8  452.17  5039.9  451.33  5046.9  455.79
  5075.2  451.27  5089.4  453.71  5131.8  455.42  5145.9  454.91  5210.3   461.8
  5216.6  462.61  5230.8  459.66  5244.9  459.76  5259.1  461.79  5287.4  463.33
#Mann= 7 ,-1 , 0
  4438.8     .07       0  4572.3     .12       0  4842.9     .07       0
  4923.5     .12       0  5016.5     .05       0  5020.9     .12       0
  5210.3     .05       0
Bank Sta=5016.5,5020.9
XS Rating Curve= 0 ,0
Exp/Cntr=0.3,0.1

Type RM Length L Ch R = 1 ,21759   ,443,443,443
BEGIN DESCRIPTION:
DARST CREEK 42.0
END DESCRIPTION:
XS GIS Cut Line= 3
      2355924.97     13761274.97        2355525.       13760875.
      2355375.01     13760775.01
#Sta/Elev= 30
  4438.6  473.14  4466.8  471.56  4523.4  466.22  4594.1  460.87    4679  456.53
    4778  453.42    4877  451.55  4919.4  451.68  4961.8  453.01  4968.1  452.31
  4978.4  451.33  4990.1  450.83  5000.7  448.58  5007.2  448.58  5011.8  447.66
  5024.5  446.42  5024.8  445.92  5028.7  445.92    5029  446.42  5032.8  446.87
  5040.3  451.19  5047.8  453.91  5053.8  454.24  5062.8  456.66  5076.4  457.91
  5098.9  458.62  5119.9  460.45    5156  462.63    5177  463.02  5184.5   463.8
#Mann= 5 ,-1 , 0
  4438.6     .07       0  4968.1     .12       0  4978.4     .05       0
  5024.5     .05       0    5029     .05       0
Bank Sta=5024.5,5029
XS Rating Curve= 0 ,0
Exp/Cntr=0.3,0.1

Type RM Length L Ch R = 1 ,21316   ,693,693,693
BEGIN DESCRIPTION:
DARST CREEK 41.0
END DESCRIPTION:
XS GIS Cut Line= 3
      2356024.98     13760974.96        2355875.       13760675.
      2355474.97     13760274.97
#Sta/Elev= 30
  4669.2  467.32  4677.5  467.51  4683.1   465.6  4691.5  464.14  4705.5  459.93
  4722.3  457.59  4803.3  453.21  4856.4  452.52  4901.2  450.43  4923.5  449.93
  4937.5  450.25  4951.5  449.44  4968.2  440.87  4971.6  440.62  4971.9  440.12
  4975.8  440.12  4976.1  440.62  4982.2  441.21  4990.6  449.02  5001.8   450.4
  5089.4  449.54  5174.3  452.16  5230.8  455.15    5245  456.45  5273.3  457.28
  5329.8  460.62  5471.3  470.07  5485.4  471.14    5542  479.23  5570.3  481.48
#Mann= 4 ,-1 , 0
  4669.2     .07       0  4971.6     .05       0  4976.1     .07       0
  5471.3     .12       0
Bank Sta=4971.6,4976.1
XS Rating Curve= 0 ,0
Exp/Cntr=0.3,0.1

Type RM Length L Ch R = 1 ,20623   ,467,467,467
BEGIN DESCRIPTION:
X18732
END DESCRIPTION:
XS GIS Cut Line= 3
      2356344.66     13760977.21      2356296.05     13760261.97
      2355261.28     13759907.78
#Sta/Elev= 30
  4119.7   465.4  4256.7   460.8    4385  454.54  4467.3  451.62  4542.6  450.32
  4764.2  446.78  4839.6  445.81  4943.4  446.93    4968  445.07  4985.7   441.9
  4991.7  438.48  4992.1  437.98  4996.3  438.48  4999.3  438.58  5006.8  442.86
  5030.6     446    5082  444.45  5185.1  448.37  5231.4  451.25  5355.6  459.04
  5426.8  465.37  5460.3  466.69  5582.5  470.72  5588.6  469.79  5614.6  471.81
  5739.8  473.03  5765.8  475.01  5859.7  476.86  5873.5  475.97  5930.3   479.2
#Mann= 13 ,-1 , 0
  4119.7     .07       0  4256.7     .12       0    4385     .07       0
  4467.3     .12       0  4542.6     .07       0  4764.2     .12       0
  4991.7     .05       0  4996.3     .12       0    5082     .07       0
  5185.1     .12       0  5231.4     .07       0  5460.3     .12       0
  5582.5     .07       0
Bank Sta=4991.7,4996.3
XS Rating Curve= 0 ,0
Exp/Cntr=0.3,0.1

Type RM Length L Ch R = 1 ,20156   ,641,641,641
BEGIN DESCRIPTION:
DARST CREEK 40.0
END DESCRIPTION:
XS GIS Cut Line= 3
      2357226.57     13759831.41      2356233.55     13759796.69
      2355296.08     13759810.58
#Sta/Elev= 30
  3998.1  467.08  4050.2  465.17  4249.8  455.73  4750.1  442.66  4760.1  440.56
  4830.2  442.71  4860.2  440.25  4930.2  443.63  4991.7  443.56  5010.3  437.32
    5018  437.16  5018.3  436.66  5022.6  437.16  5050.3   443.9  5085.9   443.8
  5210.3  447.58  5260.3  445.53  5350.3  455.76  5400.3  452.39  5512.5  457.17
  5560.3   458.5  5590.3  456.01  5600.3  459.47  5620.4  461.32  5770.4  468.18
  5790.4  465.35  5800.4  469.15  5840.4  468.26  5860.4  471.84  5929.3  475.61
#Mann= 6 ,-1 , 0
  3998.1     .05       0  4050.2     .07       0    5018     .05       0
  5022.6     .07       0  5085.9     .12       0  5512.5     .07       0
Bank Sta=5018,5022.6
XS Rating Curve= 0 ,0
Exp/Cntr=0.3,0.1

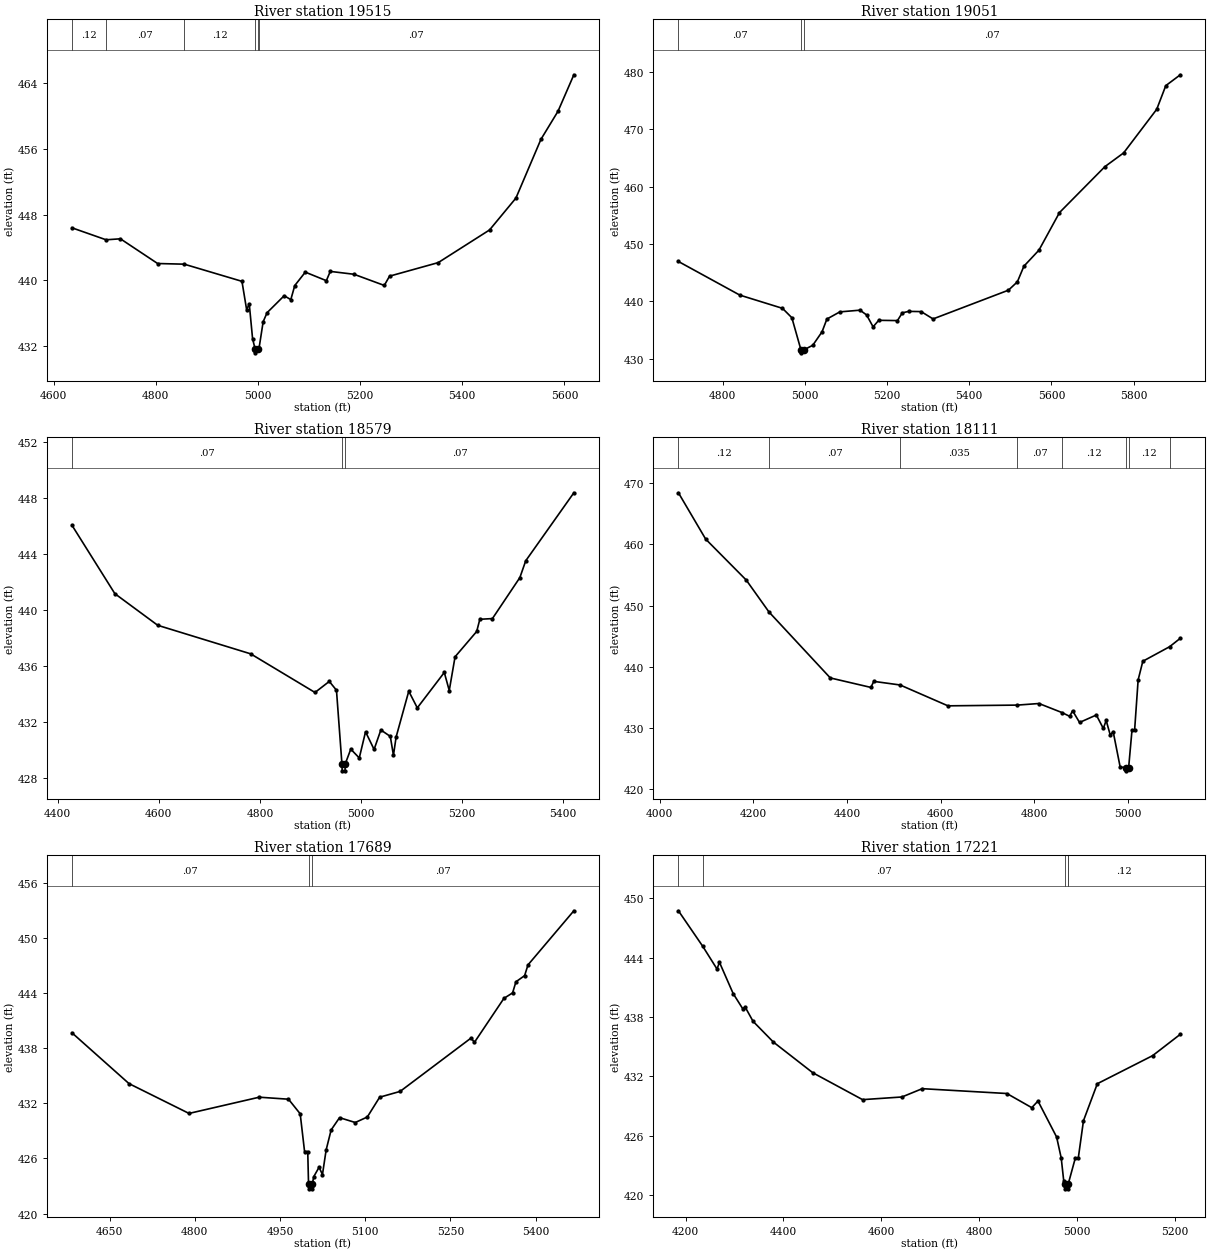
Type RM Length L Ch R = 1 ,19515   ,464,464,464
BEGIN DESCRIPTION:
DARST CREEK 39.0
END DESCRIPTION:
XS GIS Cut Line= 3
        2356775.       13759325.        2356425.       13759225.
      2355824.97     13759375.01
#Sta/Elev= 30
    4636  446.38  4702.8  444.92  4730.9  445.04  4803.7  442.03  4855.8  441.95
  4968.8  439.86  4977.9  436.42  4983.1   437.1  4989.6  432.87  4994.4  431.65
  4994.9  431.15  5000.5  431.65  5002.1  431.65  5010.3  434.94    5018  436.04
  5051.5  438.11  5064.4  437.63  5072.2  439.35  5092.8  440.98    5134  439.94
  5141.7  441.07  5188.1  440.72  5247.4  439.36  5257.7  440.49    5353  442.14
  5453.5  446.12  5505.1     450    5554  457.15  5587.5  460.58  5618.5  465.02
#Mann= 6 ,-1 , 0
    4636     .12       0  4702.8     .07       0  4855.8     .12       0
  4994.4     .05       0  5000.5     .12       0  5002.1     .07       0
Bank Sta=4994.4,5000.5
XS Rating Curve= 0 ,0
Exp/Cntr=0.3,0.1

Type RM Length L Ch R = 1 ,19051   ,472,472,472
BEGIN DESCRIPTION:
DARST CREEK 38.0
END DESCRIPTION:
XS GIS Cut Line= 3
      2356674.99       13758725.        2356375.       13758775.
      2355575.01       13759225.
#Sta/Elev= 30
  4691.9  446.94  4841.4  441.07  4945.3  438.76  4968.1  437.12  4990.3  431.49
  4990.8  430.99  4996.7  431.49    5019  432.31  5041.6  434.66  5053.4  436.89
  5084.9  438.14    5134  438.44    5150  437.61  5165.9  435.53  5179.6  436.67
  5225.2  436.62    5237  437.97  5252.6  438.23  5282.9  438.19  5311.9  436.91
  5495.4  441.93  5517.1  443.38  5533.1  446.12  5569.7  448.92  5619.7  455.48
  5730.3   463.5  5775.9   465.9  5856.5  473.52  5878.5  477.64  5913.9  479.54
#Mann= 3 ,-1 , 0
  4691.9     .07       0  4990.3     .05       0  4996.7     .07       0
Bank Sta=4990.3,4996.7
XS Rating Curve= 0 ,0
Exp/Cntr=0.3,0.1

Type RM Length L Ch R = 1 ,18579   ,468,468,468
BEGIN DESCRIPTION:
DARST CREEK 37.0
END DESCRIPTION:
XS GIS Cut Line= 3
      2356475.01     13758024.99        2356075.       13758425.
        2355675.       13758575.
#Sta/Elev= 30
  4428.1  446.05    4513  441.16  4597.8   438.9  4781.7  436.86  4908.9   434.1
  4937.2  434.89  4951.4  434.26  4962.2     429  4962.7   428.5  4968.3   428.5
  4968.8     429  4979.7  430.05  4996.5  429.42  5008.9  431.29  5025.8  430.03
  5039.2  431.42  5057.9  430.96  5064.1  429.61  5069.4  430.92  5094.4  434.19
  5111.3     433  5164.7  435.53  5174.5  434.24    5186  436.65  5228.8  438.46
    5235  439.33  5259.9  439.38  5314.2  442.31  5325.8  443.51    5421  448.37
#Mann= 3 ,-1 , 0
  4428.1     .07       0  4962.2     .05       0  4968.8     .07       0
Bank Sta=4962.2,4968.8
XS Rating Curve= 0 ,0
Exp/Cntr=0.3,0.1

Type RM Length L Ch R = 1 ,18111   ,422,422,422
BEGIN DESCRIPTION:
DARST CREEK 36.0
END DESCRIPTION:
XS GIS Cut Line= 3
      2356525.03     13757624.98        2355725.       13758175.
      2355624.96       13758175.
#Sta/Elev= 30
  4040.3  468.44  4098.5  460.86  4185.1  454.16  4233.5  448.95  4364.4  438.16
    4451  436.61  4457.1   437.6  4513.3  437.01  4615.4   433.6  4763.4  433.72
  4809.6  433.98  4859.3  432.48  4875.2  431.88  4881.3   432.8  4896.2  430.88
    4932   432.1  4946.9   429.9    4953  431.21  4961.8   428.8  4967.9  429.39
  4982.8  423.61  4994.3  423.47  4994.8  422.97  5000.9  423.47  5008.1  429.64
  5013.7  429.64  5021.2  437.84  5031.2  440.89  5088.4  443.27  5111.2  444.65
#Mann= 8 ,-1 , 0
  4040.3     .12       0  4233.5     .07       0  4513.3    .035       0
  4763.4     .07       0  4859.3     .12       0  4994.3     .05       0
  5000.9     .12       0  5088.4     .07       0
Bank Sta=4994.3,5000.9
XS Rating Curve= 0 ,0
Exp/Cntr=0.3,0.1

Type RM Length L Ch R = 1 ,17689   ,468,468,468
BEGIN DESCRIPTION:
DARST CREEK 35.0
END DESCRIPTION:
XS GIS Cut Line= 3
        2356225.       13757675.        2355825.       13757775.
      2355425.01     13758024.99
#Sta/Elev= 30
  4583.5   439.7    4684  434.16  4789.7  430.91  4913.4  432.68  4964.9  432.46
  4985.5  430.87  4993.2  426.76  4998.8  426.76  5000.2  423.19  5000.7  422.69
  5006.3  422.69  5006.8  423.19  5009.4  424.02  5018.8  425.05  5024.7  424.24
  5031.2  426.93    5040  429.11  5054.8  430.45  5082.5  429.92  5103.7  430.52
  5125.5  432.68  5161.5  433.31  5286.5  439.13  5292.4  438.66  5344.3  443.45
  5359.6  444.05  5365.5  445.26  5380.8  445.93  5386.7   447.1  5467.5     453
#Mann= 3 ,-1 , 0
  4583.5     .07       0  5000.2     .05       0  5006.8     .07       0
Bank Sta=5000.2,5006.8
XS Rating Curve= 0 ,0
Exp/Cntr=0.3,0.1

Type RM Length L Ch R = 1 ,17221   ,311,311,311
BEGIN DESCRIPTION:
DARST CREEK 34.0
END DESCRIPTION:
XS GIS Cut Line= 3
        2356325.       13757325.        2355525.       13757475.
      2355374.98     13757625.02
#Sta/Elev= 30
  4185.5  448.75  4235.2  445.16  4264.4  442.86  4269.4  443.54  4297.4  440.38
  4316.9  438.85    4322  439.01  4338.1  437.57  4379.7  435.47  4460.2  432.37
    4562  429.65  4642.5  429.92    4684  430.76    4857  430.27  4907.9  428.84
  4920.6  429.51  4958.7  425.87  4968.1  423.75  4973.2  421.45  4975.7  421.13
  4976.2  420.63  4981.9  420.63  4982.4  421.13  4982.9   421.2  4996.9  423.74
    5003  423.74  5013.6  427.52  5041.9  431.26    5155   434.1  5211.6  436.26
#Mann= 5 ,-1 , 0
  4185.5     .12       0  4235.2     .07       0  4975.7     .05       0
  4982.4     .07       0  4982.9     .12       0
Bank Sta=4975.7,4982.4
XS Rating Curve= 0 ,0
Exp/Cntr=0.3,0.1

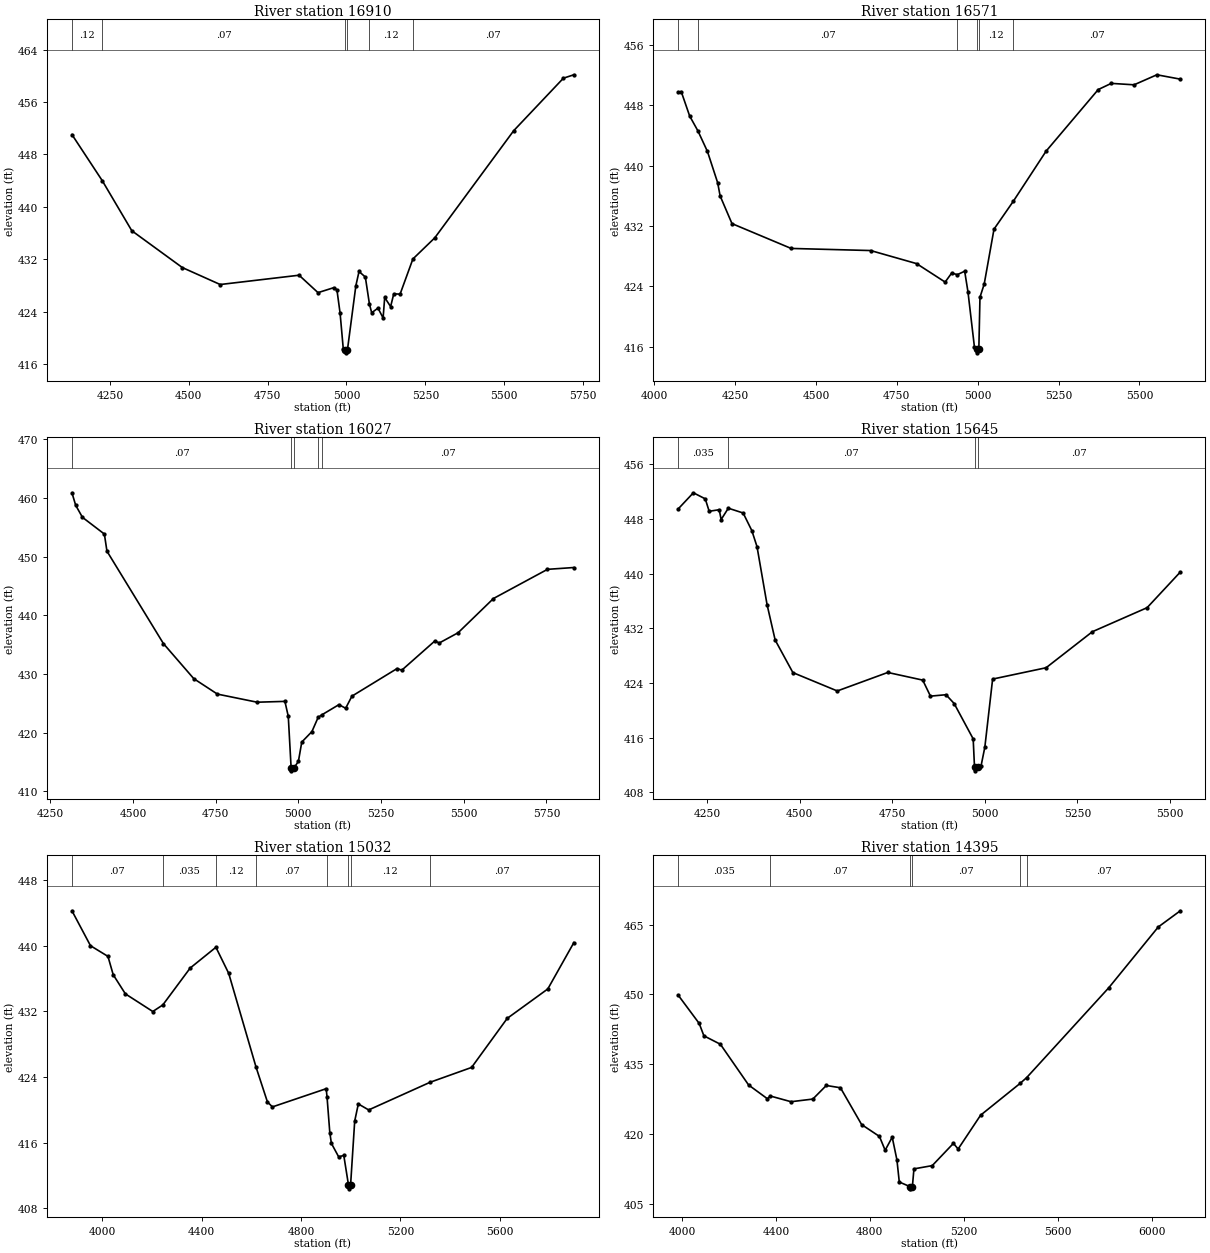
Type RM Length L Ch R = 1 ,16910   ,339,339,339
BEGIN DESCRIPTION:
X18731
END DESCRIPTION:
XS GIS Cut Line= 2
      2356344.71     13757227.25      2354754.35     13757199.47
#Sta/Elev= 30
    4130  451.02  4226.1  443.98  4319.7  436.34  4479.8  430.72  4599.8  428.13
  4849.8  429.55  4909.8  426.89  4959.8  427.65  4969.8  427.31  4979.8  423.75
  4989.8  418.34  4996.5   418.2    4997   417.7  5003.2   418.2  5029.8  427.96
  5039.8  430.12  5059.8  429.27  5072.8  425.14  5079.9  423.82  5099.9  424.53
  5116.1  423.02  5121.1  426.15  5139.9  424.76  5149.9  426.71  5169.9  426.66
  5210.5  432.03  5279.9  435.26  5529.9  451.61  5687.5  459.63  5720.6  460.15
#Mann= 6 ,-1 , 0
    4130     .12       0  4226.1     .07       0  4996.5     .05       0
  5003.2     .07       0  5072.8     .12       0  5210.5     .07       0
Bank Sta=4996.5,5003.2
XS Rating Curve= 0 ,0
Exp/Cntr=0.3,0.1

Type RM Length L Ch R = 1 ,16571   ,544,544,544
BEGIN DESCRIPTION:
X18730
END DESCRIPTION:
XS GIS Cut Line= 3
       2356309.9     13757102.23      2355615.49     13756866.13
      2354803.03     13756963.35
#Sta/Elev= 30
  4074.7  449.75  4083.4  449.83  4109.5  446.59    4135  444.62  4164.4   441.9
  4196.1  437.74  4203.6  436.01  4240.3  432.33  4423.2  429.04    4669  428.76
  4810.9  427.03  4899.3  424.58  4919.4  425.77  4937.3  425.57  4959.7  426.02
  4969.8  423.31  4989.9  415.96  4996.4   415.7  4996.9   415.2  5003.5   415.7
    5007  422.57  5020.1  424.32  5050.4   431.6  5110.5  435.32  5211.5  441.94
  5372.6   450.1  5412.9  450.92  5483.4  450.73  5553.9  452.06  5626.4  451.48
#Mann= 6 ,-1 , 0
  4074.7     .12       0    4135     .07       0  4937.3     .12       0
  4996.4     .05       0  5003.5     .12       0  5110.5     .07       0
Bank Sta=4996.4,5003.5
XS Rating Curve= 0 ,0
Exp/Cntr=0.3,0.1

Type RM Length L Ch R = 1 ,16027   ,382,382,382
BEGIN DESCRIPTION:
X18729
END DESCRIPTION:
XS GIS Cut Line= 3
      2356296.09     13756289.73      2355462.71     13756456.41
      2354941.86     13756873.09
#Sta/Elev= 30
  4315.8  460.87  4327.1  458.74  4347.5  456.69  4413.8  453.84  4421.6  450.92
  4592.3  435.18    4684  429.21  4755.4  426.58  4875.4   425.2  4959.4  425.34
  4969.6  422.79  4978.2  414.01  4978.7  413.51  4986.8  414.01  5000.2  415.12
  5010.4  418.41    5041  420.19  5059.9  422.62  5070.8  423.04  5122.6  424.78
    5143  424.17    5162  426.23  5298.4  430.93  5312.8  430.66    5412   435.6
  5426.4   435.3  5482.9  437.03  5589.7  442.86    5753  447.83  5832.7  448.14
#Mann= 5 ,-1 , 0
  4315.8     .07       0  4978.2     .05       0  4986.8     .07       0
  5059.9     .12       0  5070.8     .07       0
Bank Sta=4978.2,4986.8
XS Rating Curve= 0 ,0
Exp/Cntr=0.3,0.1

Type RM Length L Ch R = 1 ,15645   ,613,613,613
BEGIN DESCRIPTION:
X18728
END DESCRIPTION:
XS GIS Cut Line= 3
      2356164.07     13755956.42      2355330.77      13756220.3
      2355101.61      13756643.9
#Sta/Elev= 30
  4172.4  449.52  4212.8  451.85  4244.9  450.96  4255.5  449.14  4282.6  449.37
  4287.8  447.93  4307.2  449.59  4347.2  448.89  4370.7  446.31  4384.7  443.96
  4411.8  435.48  4433.7  430.28  4481.6  425.51  4601.5  422.82  4737.9  425.53
  4832.3  424.41  4853.2  422.06  4895.2  422.27  4917.2  420.98  4968.6   415.8
  4972.2  411.62  4972.7  411.12  4980.9  411.62  4989.6  411.77  5000.1  414.59
  5021.1  424.56  5165.5  426.22  5290.6   431.5  5438.4  435.02  5528.1  440.24
#Mann= 4 ,-1 , 0
  4172.4    .035       0  4307.2     .07       0  4972.2     .05       0
  4980.9     .07       0
Bank Sta=4972.2,4980.9
XS Rating Curve= 0 ,0
Exp/Cntr=0.3,0.1

Type RM Length L Ch R = 1 ,15032   ,637,637,637
BEGIN DESCRIPTION:
X18727
END DESCRIPTION:
XS GIS Cut Line= 5
      2356379.42     13755616.13      2355407.16     13755699.47
      2355268.27     13755886.97      2355268.27      13756282.8
       2355026.3     13756621.56
#Sta/Elev= 30
  3877.4  444.27  3952.1  440.01  4022.4  438.71  4043.6  436.47  4092.6  434.14
    4203  431.99  4243.3  432.79  4353.6  437.29  4457.2  439.82  4508.7  436.64
  4618.9   425.2  4664.7  420.96  4684.8  420.36  4901.3  422.58  4904.7  421.57
  4915.9  417.21  4922.3  415.91  4951.4  414.28  4972.2  414.44  4990.9  410.87
  4991.4  410.37  4999.6  410.87  5016.1  418.63  5030.7  420.72  5072.4  419.99
  5319.6  423.36  5486.8  425.17  5630.3  431.15  5793.8  434.74  5898.7  440.39
#Mann= 8 ,-1 , 0
  3877.4     .07       0  4243.3    .035       0  4457.2     .12       0
  4618.9     .07       0  4904.7     .12       0  4990.9     .05       0
  4999.6     .12       0  5319.6     .07       0
Bank Sta=4990.9,4999.6
XS Rating Curve= 0 ,0
Exp/Cntr=0.3,0.1

Type RM Length L Ch R = 1 ,14395   ,505,505,505
BEGIN DESCRIPTION:
X18726
END DESCRIPTION:
XS GIS Cut Line= 3
      2356393.28     13755539.75       2355101.6     13755449.47
      2354261.36     13755386.97
#Sta/Elev= 30
  3985.2  449.79  4073.7  443.78  4093.7  441.12  4163.9  439.31  4284.2  430.55
  4364.4  427.59  4376.3  428.19  4464.7  426.96  4557.6  427.53    4615  430.45
  4675.2  429.96  4765.4  422.05  4841.3   419.5  4865.6  416.53  4895.7  419.34
  4915.7  414.47  4925.8  409.71  4970.2  408.74  4970.7  408.24  4981.6  408.74
  4988.2  412.53  5066.1  413.23  5156.3  418.01  5176.4   416.8    5272  424.06
  5439.9  430.88  5468.2  432.14  5818.1  451.46  6028.7  464.51  6122.6  467.99
#Mann= 6 ,-1 , 0
  3985.2    .035       0  4376.3     .07       0  4970.2     .05       0
  4981.6     .07       0  5439.9     .12       0  5468.2     .07       0
Bank Sta=4970.2,4981.6
XS Rating Curve= 0 ,0
Exp/Cntr=0.3,0.1

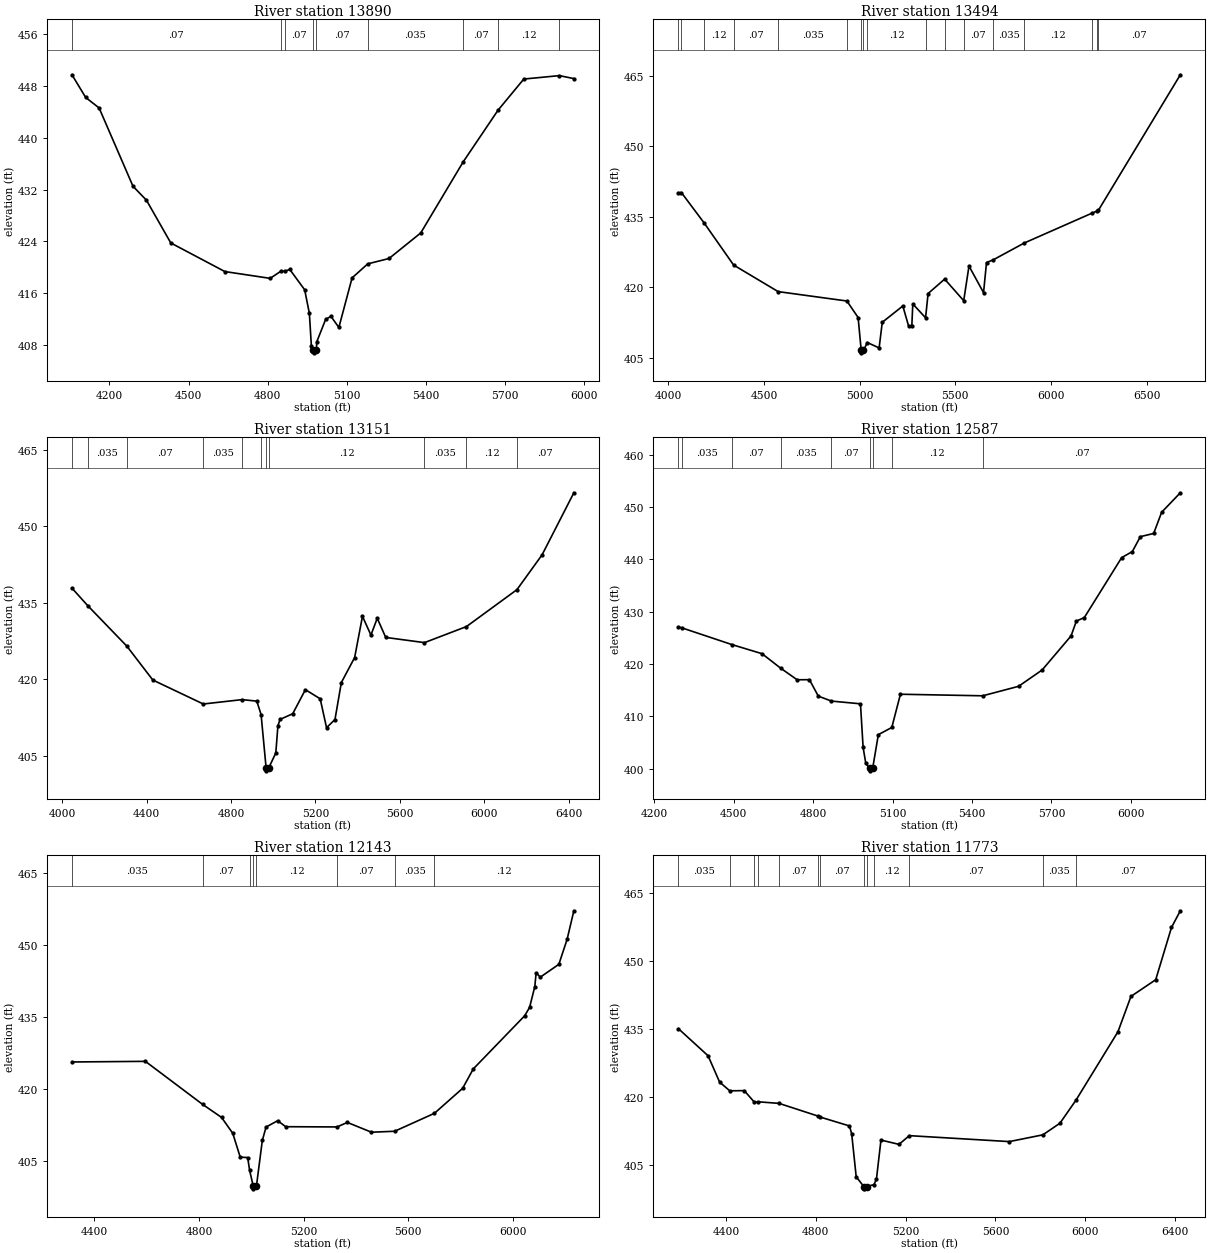
Type RM Length L Ch R = 1 ,13890   ,396,396,396
BEGIN DESCRIPTION:
X18725
END DESCRIPTION:
XS GIS Cut Line= 3
      2356462.75     13755366.15      2355587.71     13755053.63
      2354615.47     13754998.08
#Sta/Elev= 30
  4057.9  449.76  4109.9  446.26  4160.9  444.63  4289.4  432.53  4340.3  430.38
  4432.7  423.77  4637.7  419.35  4809.4   418.3  4849.6  419.39  4864.7   419.4
    4884  419.67  4940.3  416.53  4958.1  412.89  4965.8  407.78  4973.6  407.29
  4974.1  406.79    4985  407.29  4985.9  408.47  5019.8  411.96  5039.9  412.43
  5069.9  410.71    5120  418.37  5179.4  420.54  5260.2  421.37  5380.4  425.32
  5541.3   436.3  5673.3  444.28  5771.1   449.1    5906  449.63  5960.9  449.17
#Mann= 9 ,-1 , 0
  4057.9     .07       0  4849.6     .12       0  4864.7     .07       0
  4973.6     .05       0    4985     .07       0  5179.4    .035       0
  5541.3     .07       0  5673.3     .12       0    5906     .07       0
Bank Sta=4973.6,4985
XS Rating Curve= 0 ,0
Exp/Cntr=0.3,0.1

Type RM Length L Ch R = 1 ,13494   ,343,343,343
BEGIN DESCRIPTION:
X18724
END DESCRIPTION:
XS GIS Cut Line= 3
      2356629.42     13755123.09      2355657.16     13754678.63
      2354129.68     13754387.02
#Sta/Elev= 30
  4052.5  440.14    4068  440.19  4185.5   433.8  4341.2  424.76  4573.8  419.11
  4933.4  417.11    4992   413.6  5008.2  406.58  5008.7  406.08  5019.7  406.58
  5040.2  408.27  5101.9  407.13  5118.3  412.58  5225.8  416.05  5256.1  411.76
  5272.8  411.78  5277.9  416.49  5344.7  413.54  5357.9   418.7  5444.4  421.77
  5544.1  417.18  5571.7  424.55  5647.8  418.89  5663.3  425.29  5697.9  425.86
  5861.1  429.46  6212.8  435.77  6242.7  436.29  6247.8  436.38  6676.6  465.25
#Mann= 17 ,-1 , 0
  4052.5     .12       0    4068     .07       0  4185.5     .12       0
  4341.2     .07       0  4573.8    .035       0  4933.4     .07       0
  5008.2     .05       0  5019.7     .07       0  5040.2     .12       0
  5344.7     .07       0  5444.4     .12       0  5544.1     .07       0
  5697.9    .035       0  5861.1     .12       0  6212.8     .07       0
  6242.7     .12       0  6247.8     .07       0
Bank Sta=5008.2,5019.7
XS Rating Curve= 0 ,0
Exp/Cntr=0.3,0.1

Type RM Length L Ch R = 1 ,13151   ,564,564,564
BEGIN DESCRIPTION:
X18723
END DESCRIPTION:
XS GIS Cut Line= 2
       2356719.7      13754470.3      2354344.69      13754345.3
#Sta/Elev= 30
  4046.2  437.86  4121.6   434.4  4306.5  426.48  4429.4  419.85  4668.5  415.15
  4852.8  416.01  4922.1  415.71  4942.4  413.09  4966.4  402.55  4966.9  402.05
  4977.9  402.55  5012.2  405.56  5022.2  410.88  5032.3  412.13  5092.3  413.24
  5152.4  417.96  5222.5  416.17  5252.6  410.51  5292.6  412.11  5322.7  419.35
  5385.8  424.26  5422.8  432.34  5462.9  428.66  5492.9  431.96    5533   428.2
  5716.7  427.18  5915.7  430.33  6154.8  437.56    6274  444.39  6424.5  456.55
#Mann= 11 ,-1 , 0
  4046.2     .07       0  4121.6    .035       0  4306.5     .07       0
  4668.5    .035       0  4852.8     .07       0  4942.4     .12       0
  4966.4     .05       0  4977.9     .12       0  5716.7    .035       0
  5915.7     .12       0  6154.8     .07       0
Bank Sta=4966.4,4977.9
XS Rating Curve= 0 ,0
Exp/Cntr=0.3,0.1

Type RM Length L Ch R = 1 ,12587   ,444,444,444
BEGIN DESCRIPTION:
X18722
END DESCRIPTION:
XS GIS Cut Line= 3
      2356546.01      13754206.4      2355893.27     13754018.91
      2354684.96     13753880.02
#Sta/Elev= 30
  4291.3  427.11  4304.1  426.93  4493.3  423.73    4607  421.99    4677  419.24
  4739.7  417.01    4786  417.03  4819.7  413.88  4869.3  412.94  4978.8  412.42
  4988.8  404.09  4998.9  401.05  5013.2  400.12  5013.7  399.62  5024.9  400.12
  5046.3  406.53  5097.1   407.9  5129.7  414.25  5440.4  413.95  5575.8  415.76
  5664.9  418.88    5774  425.38  5794.1  428.21  5824.3   428.9  5965.2  440.34
  6005.5  441.49  6035.7  444.34    6086  444.95  6116.2     449  6186.7  452.72
#Mann= 9 ,-1 , 0
  4291.3     .07       0  4304.1    .035       0  4493.3     .07       0
    4677    .035       0  4869.3     .07       0  5013.2     .05       0
  5024.9     .07       0  5097.1     .12       0  5440.4     .07       0
Bank Sta=5013.2,5024.9
XS Rating Curve= 0 ,0
Exp/Cntr=0.3,0.1

Type RM Length L Ch R = 1 ,12143   ,370,370,370
BEGIN DESCRIPTION:
X18721
END DESCRIPTION:
XS GIS Cut Line= 3
      2356427.97     13754088.33      2355837.71     13753588.36
      2354719.87      13753338.4
#Sta/Elev= 30
  4314.3  425.57  4595.1   425.7  4813.9  416.73  4886.2  414.02  4929.1  410.71
  4957.7  405.73  4986.2  405.65  4993.7  402.96  5007.7  399.63  5008.2  399.13
  5019.5  399.63  5042.2  409.22  5056.5  412.01  5100.9  413.33  5131.6  412.08
  5327.9  412.03  5367.3  412.97  5459.5  410.93  5548.1  411.13  5700.2  414.87
  5807.9  420.07  5848.9  424.13  6045.7  435.22  6064.1  436.96    6084  441.28
  6089.1  444.16  6105.1  443.25  6175.9  445.92  6207.5  451.13  6233.3  457.08
#Mann= 8 ,-1 , 0
  4314.3    .035       0  4813.9     .07       0  4993.7     .12       0
  5007.7     .05       0  5019.5     .12       0  5327.9     .07       0
  5548.1    .035       0  5700.2     .12       0
Bank Sta=5007.7,5019.5
XS Rating Curve= 0 ,0
Exp/Cntr=0.3,0.1

Type RM Length L Ch R = 1 ,11773   ,369,369,369
BEGIN DESCRIPTION:
X18720
END DESCRIPTION:
XS GIS Cut Line= 3
      2356851.59     13753706.41      2356212.71     13753366.13
      2354705.78     13753248.08
#Sta/Elev= 30
  4187.9  435.12    4320  429.15  4371.3  423.36  4416.5  421.43  4481.2  421.47
  4526.4  418.91  4543.3  419.01  4636.2  418.66  4811.1  415.84  4817.7  415.67
  4949.6  413.69  4959.6  411.96  4979.7  402.49  5013.7  400.33  5014.2  399.83
  5025.8  400.33  5058.8  400.76  5069.9  401.97    5090  410.58  5170.2  409.63
  5216.4  411.55  5661.8  410.24  5811.1  411.73    5887  414.28  5958.2  419.34
  6145.4  434.43  6203.4  442.23  6313.7  445.91    6384  457.43  6423.3   461.1
#Mann= 13 ,-1 , 0
  4187.9    .035       0  4416.5     .12       0  4526.4     .07       0
  4543.3     .12       0  4636.2     .07       0  4811.1     .12       0
  4817.7     .07       0  5013.7     .05       0  5025.8     .07       0
  5058.8     .12       0  5216.4     .07       0  5811.1    .035       0
  5958.2     .07       0
Bank Sta=5013.7,5025.8
XS Rating Curve= 0 ,0
Exp/Cntr=0.3,0.1