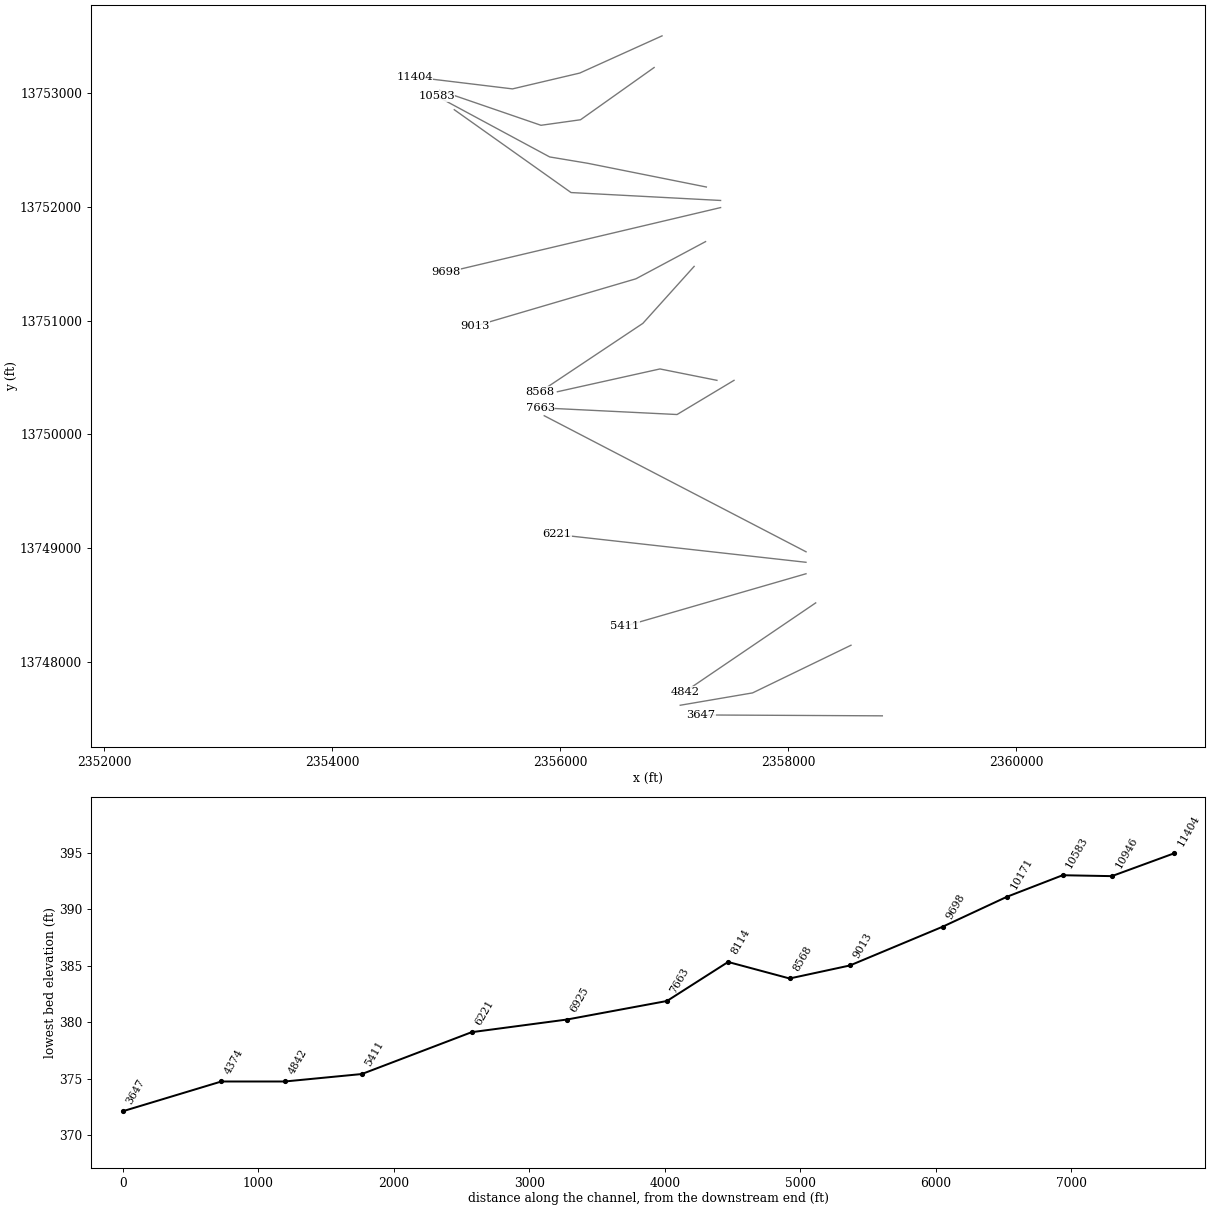
HEC-RAS study DARST CREEK.prj: DARST CREEK Base Level Engineering

--- DARST CREEK.g01 (geometry) --- (continued)

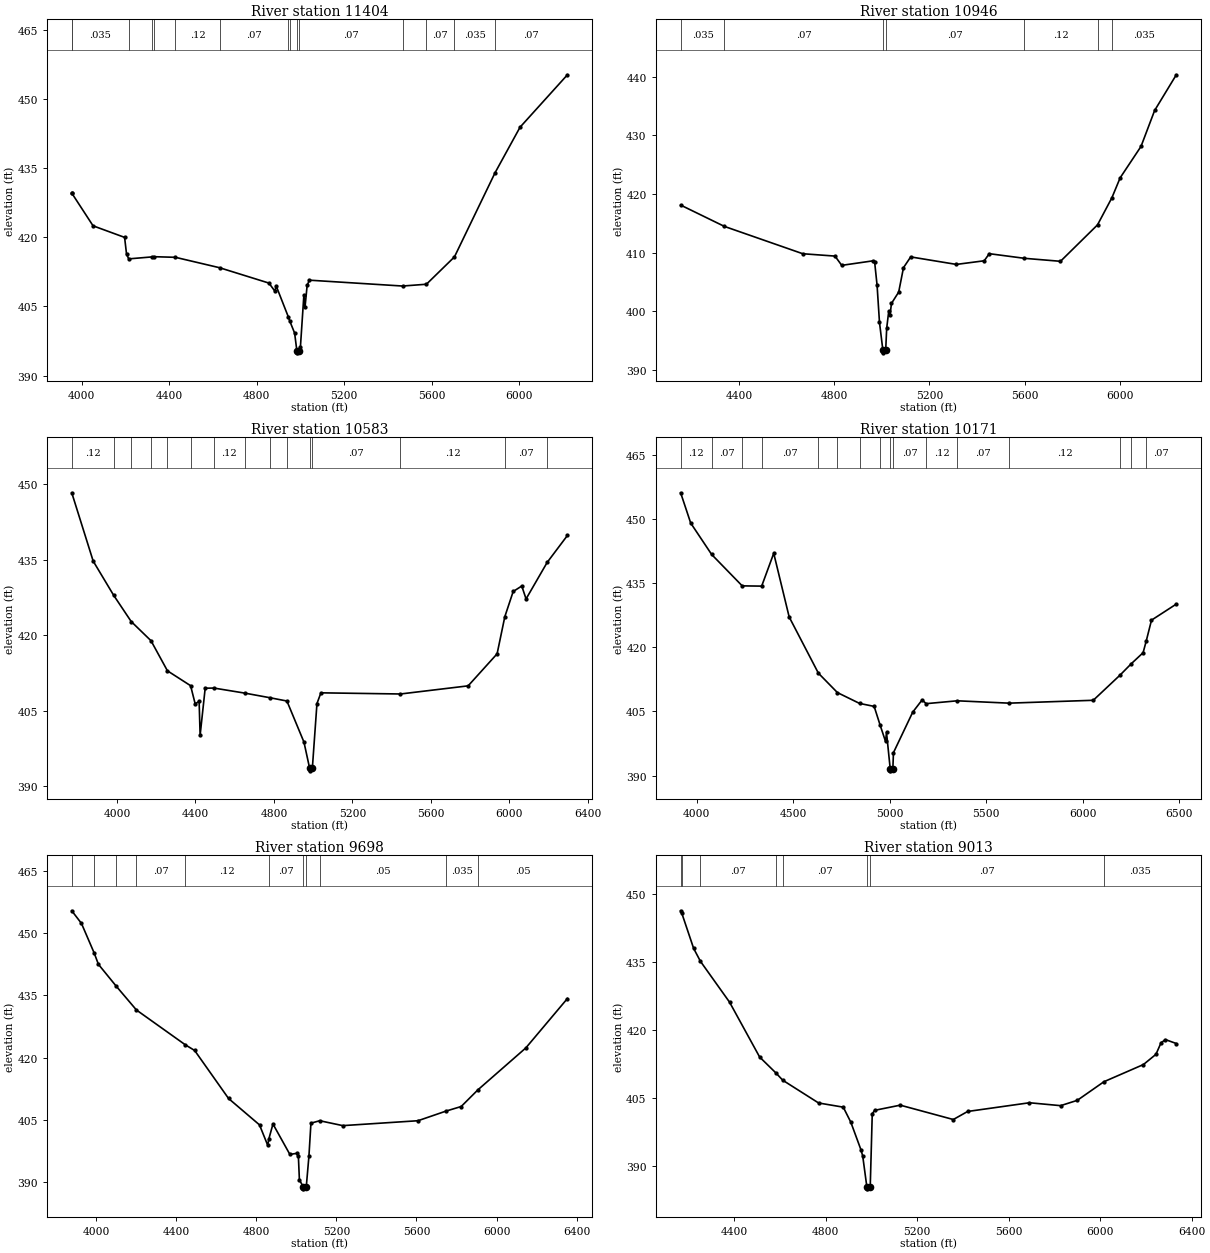
Type RM Length L Ch R = 1 ,11404   ,458,458,458
BEGIN DESCRIPTION:
X18719
END DESCRIPTION:
XS GIS Cut Line= 4
      2356893.27     13753498.08      2356171.05     13753171.69
      2355580.77      13753032.8      2354719.79     13753136.95
#Sta/Elev= 30
  3954.2   429.5  3955.3   429.5  4051.6  422.48  4195.8  419.97  4204.7  416.32
  4214.7  415.31  4321.4  415.74  4331.2  415.78    4428  415.65  4630.1  413.39
  4855.7  410.06  4883.2  408.28  4888.4  409.49  4944.8  402.67  4950.5  401.87
  4973.1  399.22  4983.2  395.43  4983.7  394.93  4995.3  395.43  4999.5  396.12
  5015.5  407.51  5020.6  404.81  5030.3  409.54  5040.6  410.69  5466.7  409.42
  5575.7  409.81  5703.8  415.74  5889.7  434.01  6003.6  443.86  6220.4  455.24
#Mann= 15 ,-1 , 0
  3954.2     .07       0  3955.3    .035       0  4214.7     .07       0
  4321.4     .12       0  4331.2     .07       0    4428     .12       0
  4630.1     .07       0  4944.8     .12       0  4950.5     .07       0
  4983.2     .05       0  4995.3     .07       0  5466.7     .12       0
  5575.7     .07       0  5703.8    .035       0  5889.7     .07       0
Bank Sta=4983.2,4995.3
XS Rating Curve= 0 ,0
Exp/Cntr=0.3,0.1

Type RM Length L Ch R = 1 ,10946   ,363,363,363
BEGIN DESCRIPTION:
X18718
END DESCRIPTION:
XS GIS Cut Line= 4
      2356823.83      13753220.3      2356177.99     13752761.97
      2355830.77     13752713.36      2354941.88     13753018.91
#Sta/Elev= 30
  4154.9  418.12  4338.9  414.48  4668.1  409.82  4803.4  409.42  4831.7  407.84
    4963  408.61  4970.1  408.36  4980.2  404.46  4990.3  398.13  5004.4  393.42
  5004.9  392.92  5016.5  393.42  5020.6  397.11  5029.4  400.08  5034.4  399.29
  5040.7  401.35    5071  403.28  5091.2  407.45  5121.5  409.28  5313.4     408
  5430.4  408.62  5451.6  409.83  5599.5  409.04  5750.8  408.53  5906.3  414.74
  5966.7  419.36  6001.5  422.77  6089.1  428.12  6146.3  434.25  6237.4  440.34
#Mann= 7 ,-1 , 0
  4154.9    .035       0  4338.9     .07       0  5004.4     .05       0
  5016.5     .07       0  5599.5     .12       0  5906.3     .07       0
  5966.7    .035       0
Bank Sta=5004.4,5016.5
XS Rating Curve= 0 ,0
Exp/Cntr=0.3,0.1

Type RM Length L Ch R = 1 ,10583   ,412,412,412
BEGIN DESCRIPTION:
X18717
END DESCRIPTION:
XS GIS Cut Line= 4
       2357282.2     13752171.68      2356240.49     13752380.02
      2355907.16     13752435.58       2354914.4     13752970.14
#Sta/Elev= 30
  3769.1  448.32  3878.4  434.72  3982.4  427.95  4072.1  422.71  4173.1  418.89
    4257   412.9  4375.1  409.94  4398.5  406.32  4418.6  406.83  4423.7  400.08
  4449.5  409.44  4493.9  409.47    4652  408.46  4779.1  407.55  4866.3  406.89
  4953.3  398.71  4982.2   393.5  4982.7     393    4996   393.5  5019.5  406.39
  5039.8  408.52  5445.4  408.29  5790.6  409.91  5938.2  416.28  5977.6  423.67
  6020.2  428.68    6064  429.77  6085.9   427.2  6193.6  434.47  6296.9  439.83
#Mann= 15 ,-1 , 0
  3769.1     .12       0  3982.4     .07       0  4072.1     .12       0
  4173.1     .07       0    4257     .12       0  4375.1     .07       0
  4493.9     .12       0    4652     .07       0  4779.1     .12       0
  4866.3     .07       0  4982.2     .05       0    4996     .07       0
  5445.4     .12       0  5977.6     .07       0  6193.6    .035       0
Bank Sta=4982.2,4996
XS Rating Curve= 0 ,0
Exp/Cntr=0.3,0.1

Type RM Length L Ch R = 1 ,10171   ,473,473,473
BEGIN DESCRIPTION:
X18716
END DESCRIPTION:
XS GIS Cut Line= 3
      2357407.15     13752053.63      2356094.66     13752123.08
      2355070.06     13752849.99
#Sta/Elev= 30
  3915.8  456.12    3968  449.04  4076.7  441.69  4235.1  434.35  4336.1  434.29
  4398.6  441.96  4478.7  427.07  4630.2  413.93  4728.9  409.39  4843.6  406.86
  4919.4  406.16  4950.8  401.72  4978.5  397.96  4983.5  400.07  5002.6  391.59
  5003.1  391.09  5016.4  391.59  5019.5  395.34  5119.6  404.83  5168.3  407.68
    5189   406.8  5350.2  407.47  5618.6  406.92  6055.8  407.59  6195.1   413.5
  6252.4  416.12  6314.2  418.72  6330.4  421.45  6357.7  426.33  6486.4  430.09
#Mann= 16 ,-1 , 0
  3915.8     .12       0  4076.7     .07       0  4235.1     .12       0
  4336.1     .07       0  4630.2     .12       0  4728.9     .07       0
  4843.6     .12       0  4950.8     .07       0  5002.6     .05       0
  5016.4     .07       0    5189     .12       0  5350.2     .07       0
  5618.6     .12       0  6195.1     .07       0  6252.4     .12       0
  6330.4     .07       0
Bank Sta=5002.6,5016.4
XS Rating Curve= 0 ,0
Exp/Cntr=0.3,0.1

Type RM Length L Ch R = 1 ,9698    ,685,685,685
BEGIN DESCRIPTION:
X18715
END DESCRIPTION:
XS GIS Cut Line= 2
      2357407.13     13751991.13      2354998.77       13751422.
#Sta/Elev= 30
  3879.2  455.36  3927.6  452.32  3991.2  445.19  4012.2  442.48  4101.8  437.18
  4202.2  431.48  4446.4   423.1  4492.8  421.74    4662  410.19  4816.5  403.84
  4857.6  398.92  4863.2  400.47  4883.7  404.05  4968.3  396.72  5001.4  396.99
  5010.6   396.3  5015.7   390.6    5035  388.95  5035.5  388.45    5050  388.95
  5063.2  396.27  5073.3  404.25  5117.1  404.84  5232.3  403.66  5607.7  404.84
  5747.2  407.15  5823.4  408.26  5907.5   412.3  6146.2  422.36  6353.9  434.25
#Mann= 11 ,-1 , 0
  3879.2     .12       0  3991.2     .07       0  4101.8     .12       0
  4202.2     .07       0  4446.4     .12       0  4863.2     .07       0
    5035     .05       0    5050     .07       0  5117.1     .05       0
  5747.2    .035       0  5907.5     .05       0
Bank Sta=5035,5050
XS Rating Curve= 0 ,0
Exp/Cntr=0.3,0.1

Type RM Length L Ch R = 1 ,9013    ,445,445,445
BEGIN DESCRIPTION:
X18714
END DESCRIPTION:
XS GIS Cut Line= 3
      2357275.22     13751692.53       2356664.1     13751366.13
      2355249.63     13750950.11
#Sta/Elev= 30
  4165.5  446.23  4170.1  445.77  4222.4  437.94    4252  435.11  4379.3  426.12
    4511  414.03  4581.7  410.55  4612.2  408.92  4768.7  403.92  4876.5     403
  4909.5   399.7  4953.7  393.64  4961.6  392.25  4979.5  385.52    4980  385.02
  4994.5  385.52  5003.3  401.54  5013.7   402.3  5125.7  403.44  5357.7  400.28
  5420.3  402.05  5690.6  403.97  5826.8  403.33  5899.7   404.5  6016.3   408.6
  6188.9  412.38  6243.7  414.63    6266  417.18  6285.4  417.87  6332.7  417.01
#Mann= 8 ,-1 , 0
  4165.5     .07       0  4170.1     .12       0    4252     .07       0
  4581.7     .12       0  4612.2     .07       0  4979.5     .05       0
  4994.5     .07       0  6016.3    .035       0
Bank Sta=4979.5,4994.5
XS Rating Curve= 0 ,0
Exp/Cntr=0.3,0.1

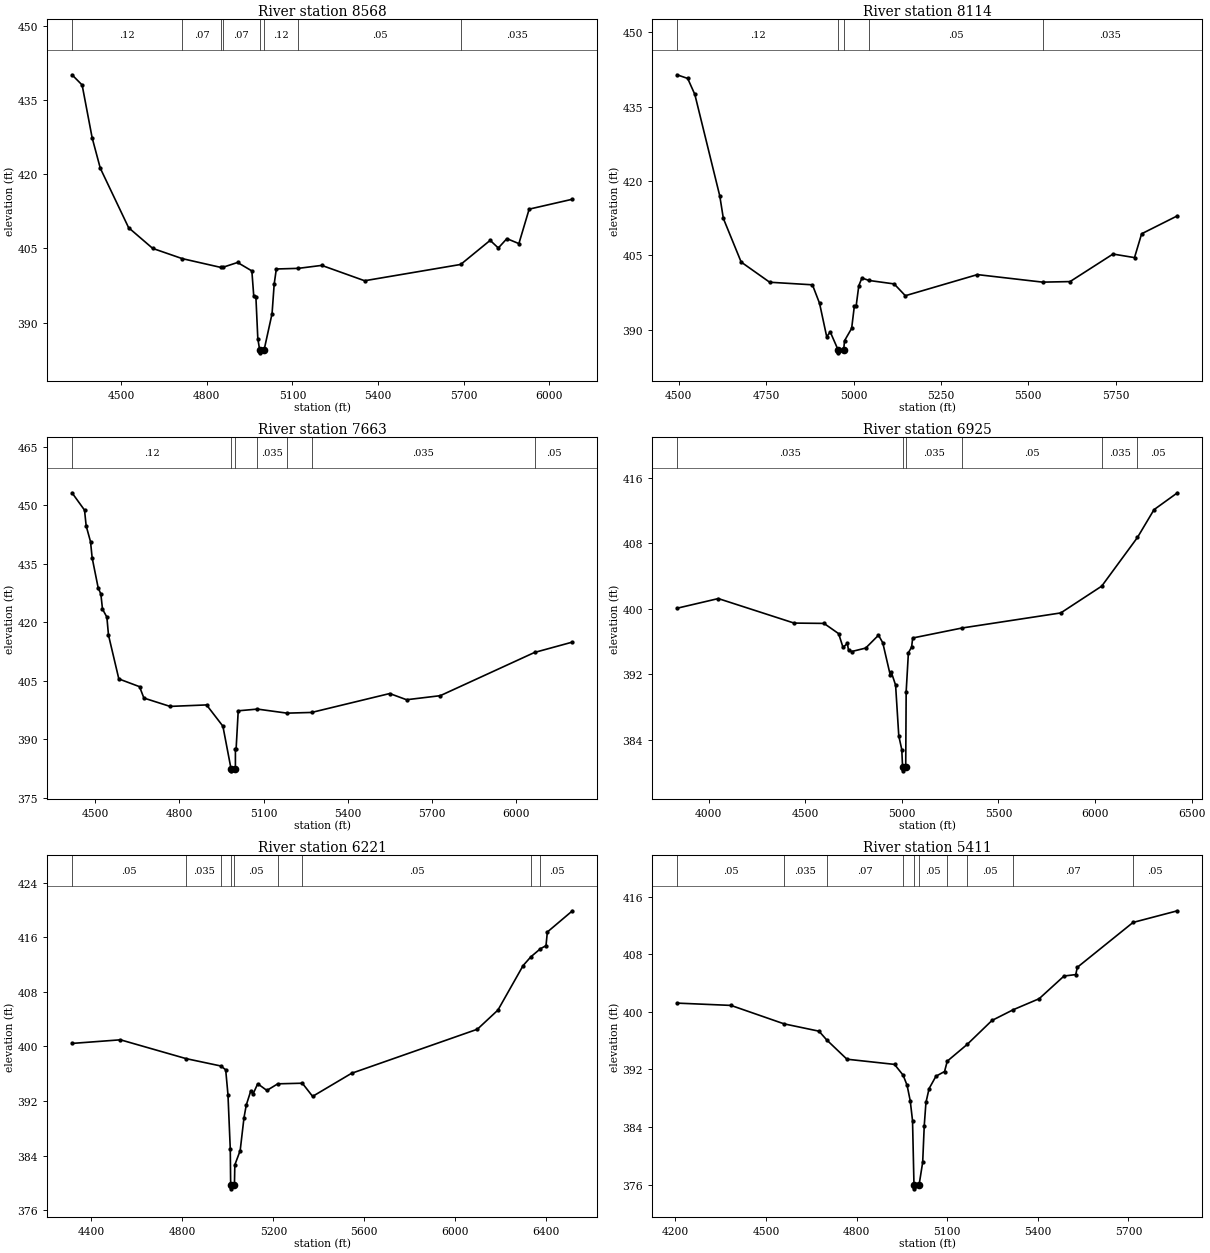
Type RM Length L Ch R = 1 ,8568    ,454,454,454
BEGIN DESCRIPTION:
DARST CREEK 18.0
END DESCRIPTION:
XS GIS Cut Line= 3
      2357175.02     13751475.02        2356725.       13750975.
      2355824.98     13750374.99
#Sta/Elev= 30
  4327.2  440.18  4362.7  438.11  4397.9   427.4  4426.3  421.27  4525.7  409.21
  4610.1  405.02  4713.6  402.95  4849.6  401.16  4855.4  401.18  4907.6  402.17
  4957.7  400.46  4964.4  395.32  4971.9  395.13  4978.6  386.77  4985.3  384.37
  4985.8  383.87  5000.3  384.37  5028.5   391.8    5036  397.81  5043.5  400.85
  5120.8  400.98  5202.7  401.58    5353  398.47  5689.8  401.77  5793.1  406.65
  5821.7   405.1  5851.7     407  5893.8  405.99  5929.8  412.97  6081.6  414.98
#Mann= 8 ,-1 , 0
  4327.2     .12       0  4713.6     .07       0  4849.6     .12       0
  4855.4     .07       0  4985.3     .05       0  5000.3     .12       0
  5120.8     .05       0  5689.8    .035       0
Bank Sta=4985.3,5000.3
XS Rating Curve= 0 ,0
Exp/Cntr=0.3,0.1

Type RM Length L Ch R = 1 ,8114    ,451,451,451
BEGIN DESCRIPTION:
DARST CREEK 17.0
END DESCRIPTION:
XS GIS Cut Line= 3
      2357375.02       13750475.        2356875.       13750575.
      2355974.98       13750375.
#Sta/Elev= 30
    4495  441.45  4525.6  440.71    4546  437.49  4617.4  416.99  4627.6  412.46
  4678.6  403.65  4760.2  399.58  4882.5  399.06  4902.9  395.32  4923.3  388.59
  4933.5  389.55  4956.5  385.83    4957  385.33  4971.8  385.83  4974.3  387.77
  4994.7  390.27  5002.4  394.75  5007.5  394.75  5015.2  398.88  5024.1  400.44
  5044.1  399.94  5116.3  399.24  5148.3  396.86  5354.5  401.12    5541   399.6
  5619.6  399.71  5742.5  405.27    5804  404.55  5824.4  409.36  5926.9  412.99
#Mann= 5 ,-1 , 0
    4495     .12       0  4956.5     .05       0  4971.8     .12       0
  5044.1     .05       0    5541    .035       0
Bank Sta=4956.5,4971.8
XS Rating Curve= 0 ,0
Exp/Cntr=0.3,0.1

Type RM Length L Ch R = 1 ,7663    ,738,738,738
BEGIN DESCRIPTION:
DARST CREEK 16.0
END DESCRIPTION:
XS GIS Cut Line= 3
      2357524.97     13750474.98        2357025.       13750175.
      2355823.82     13750234.19
#Sta/Elev= 30
  4416.5  453.21  4461.2  448.76    4467  444.73  4482.6  440.66  4488.4  436.53
  4509.8  428.85  4519.5  427.22  4525.3  423.36  4540.9  421.32  4546.7   416.7
  4583.6  405.46  4657.5  403.47    4673  400.55  4766.3  398.41  4896.6  398.79
  4954.9  393.34    4984  382.38  4984.5  381.88  4999.5  382.38  4999.6  387.53
  5002.1  387.53  5009.6  397.28  5078.1  397.72  5183.6  396.68  5271.6  396.86
  5550.2  401.71  5610.3  400.12  5730.5  401.16  6066.9  412.25  6202.2  414.91
#Mann= 7 ,-1 , 0
  4416.5     .12       0    4984     .05       0  4999.5     .12       0
  5078.1    .035       0  5183.6     .05       0  5271.6    .035       0
  6066.9     .05       0
Bank Sta=4984,4999.5
XS Rating Curve= 0 ,0
Exp/Cntr=0.3,0.1

Type RM Length L Ch R = 1 ,6925    ,704,704,704
BEGIN DESCRIPTION:
X18713
END DESCRIPTION:
XS GIS Cut Line= 2
      2358157.19     13748970.29      2355859.31     13750164.35
#Sta/Elev= 30
    3837  400.08  4050.6  401.26    4443  398.27  4597.8  398.23  4673.4  396.98
  4695.9  395.31  4718.5  395.78  4724.8  394.94    4741   394.8  4813.3  395.22
  4879.6  396.79  4901.7  395.87  4940.3  391.94    4946  392.27  4968.1   390.7
  4984.6  384.51  5000.2  382.82  5004.1  380.74  5004.6  380.24  5020.5  380.74
  5022.8  389.88  5034.4  394.66  5050.9  395.33  5056.6  396.45    5312  397.67
  5822.9  399.51  6034.8  402.78  6219.7  408.72  6305.3  412.11  6426.6  414.17
#Mann= 6 ,-1 , 0
    3837    .035       0  5004.1    .035       0  5020.5    .035       0
    5312     .05       0  6034.8    .035       0  6219.7     .05       0
Bank Sta=5004.1,5020.5
XS Rating Curve= 0 ,0
Exp/Cntr=0.3,0.1

Type RM Length L Ch R = 1 ,6221    ,810,810,810
BEGIN DESCRIPTION:
X18712
END DESCRIPTION:
XS GIS Cut Line= 2
       2358156.7     13748878.22      2355969.35     13749122.12
#Sta/Elev= 30
  4314.5  400.43  4527.5  400.96  4816.6   398.2  4969.6  397.12  4990.4  396.56
  5000.4  392.93  5010.5  384.99  5012.3  379.62  5012.8  379.12  5028.8  379.62
  5030.6  382.63  5054.1  384.73  5070.9  389.55  5080.9   391.4    5101   393.5
  5111.1  393.05  5131.2  394.52  5171.5  393.54  5219.4  394.51  5327.4   394.6
  5372.7  392.67  5543.8  396.05  6097.2  402.51  6187.7  405.32  6298.4  411.84
  6332.1  413.11  6374.6  414.31    6399  414.75    6405  416.76  6515.4  419.87
#Mann= 9 ,-1 , 0
  4314.5     .05       0  4816.6    .035       0  4969.6     .05       0
  5012.3     .05       0  5028.8     .05       0  5219.4     .12       0
  5327.4     .05       0  6332.1    .035       0  6374.6     .05       0
Bank Sta=5012.3,5028.8
XS Rating Curve= 0 ,0
Exp/Cntr=0.3,0.1

Type RM Length L Ch R = 1 ,5411    ,569,569,569
BEGIN DESCRIPTION:
X18711
END DESCRIPTION:
XS GIS Cut Line= 2
      2358156.69     13748777.56      2356565.16     13748316.75
#Sta/Elev= 30
  4205.5  401.21  4384.2  400.89  4559.9  398.33  4675.7  397.31  4701.1   396.1
  4768.1  393.42  4925.6   392.7    4954  391.21  4967.2  389.81  4977.7  387.64
  4985.3  384.88  4990.1  375.92  4990.6  375.42  5006.8  375.92  5018.9  379.11
  5024.1  384.21  5029.7  387.41  5040.1  389.34  5062.9  391.06  5091.3  391.71
  5100.3  393.15  5166.1  395.47  5248.3   398.8  5318.7  400.29  5404.5  401.82
  5486.9  404.97  5525.7  405.17  5530.9  406.18  5715.3  412.41  5862.4  414.03
#Mann= 10 ,-1 , 0
  4205.5     .05       0  4559.9    .035       0  4701.1     .07       0
    4954     .05       0  4990.1     .05       0  5006.8     .05       0
  5100.3     .07       0  5166.1     .05       0  5318.7     .07       0
  5715.3     .05       0
Bank Sta=4990.1,5006.8
XS Rating Curve= 0 ,0
Exp/Cntr=0.3,0.1

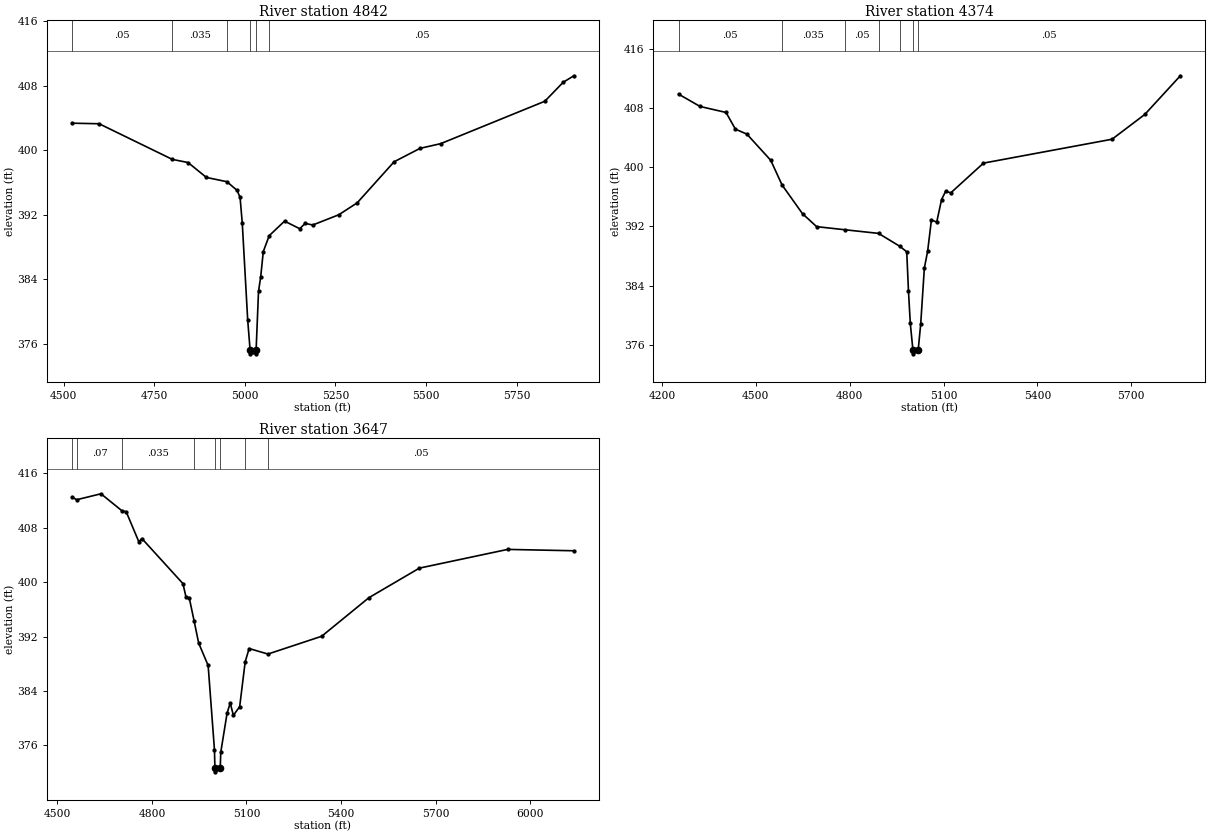
Type RM Length L Ch R = 1 ,4842    ,468,468,468
BEGIN DESCRIPTION:
X18710
END DESCRIPTION:
XS GIS Cut Line= 2
      2358241.82     13748521.95      2357095.61     13747743.61
#Sta/Elev= 30
  4522.7  403.37  4597.4   403.3  4799.5  398.88  4842.9  398.49  4893.6  396.64
  4950.3  396.11  4978.2  395.04  4986.6  394.17  4992.7  390.93  5007.6  378.98
  5014.2  375.26  5014.7  374.76  5030.4  374.76  5030.9  375.26  5037.5  382.51
  5043.5   384.3  5050.7  387.45  5067.1  389.42  5109.4  391.22  5151.3  390.28
  5166.3  390.94  5187.3  390.74  5259.1  392.01    5310  393.49  5411.8  398.58
  5483.6  400.25  5540.5  400.83    5828  406.09  5878.9  408.45  5908.2  409.25
#Mann= 6 ,-1 , 0
  4522.7     .05       0  4799.5    .035       0  4950.3     .07       0
  5014.2     .05       0  5030.9     .07       0  5067.1     .05       0
Bank Sta=5014.2,5030.9
XS Rating Curve= 0 ,0
Exp/Cntr=0.3,0.1

Type RM Length L Ch R = 1 ,4374    ,727,727,727
BEGIN DESCRIPTION:
X18709
END DESCRIPTION:
XS GIS Cut Line= 3
      2358551.62     13748150.22       2357688.1     13747732.01
      2357053.05     13747623.59
#Sta/Elev= 30
  4253.1  409.88    4322  408.21  4404.9   407.4  4434.9  405.14  4471.6  404.47
  4547.8  400.93    4584  397.59  4649.3  393.71  4694.4  391.96  4784.4  391.54
  4892.2  391.05  4960.7  389.29  4982.4  388.56    4988  383.23  4993.8  378.88
  5002.2  375.26  5002.7  374.76    5019  375.26  5027.1  378.81  5038.7  386.35
  5049.3  388.66  5061.3  392.86  5078.3  392.58  5093.8  395.63  5106.5  396.72
  5123.5  396.54  5227.7  400.55  5638.6  403.78  5743.2  407.13  5856.8  412.36
#Mann= 7 ,-1 , 0
  4253.1     .05       0    4584    .035       0  4784.4     .05       0
  4892.2     .12       0  4960.7     .05       0  5002.2     .05       0
    5019     .05       0
Bank Sta=5002.2,5019
XS Rating Curve= 0 ,0
Exp/Cntr=0.3,0.1

Type RM Length L Ch R = 1 ,3647    ,824,824,824
BEGIN DESCRIPTION:
X18708
END DESCRIPTION:
XS GIS Cut Line= 2
      2358826.58     13747530.64        2357235.     13747538.39
#Sta/Elev= 30
  4546.8  412.45  4561.8   412.1  4638.4  412.97  4705.9  410.44  4718.4  410.34
  4758.4  405.94  4768.4  406.39  4898.4  399.78  4908.4  397.76  4918.4   397.7
  4933.8  394.31  4948.4  391.03  4978.4  387.75  4998.4   375.4  4999.9  372.63
  5000.4  372.13  5016.8  372.63  5018.4  374.99  5038.4  380.72  5048.4  382.25
  5058.4  380.43  5078.4   381.7  5095.9  388.29  5108.4  390.24  5168.1  389.43
  5338.4  392.04  5488.4  397.71  5648.4  402.05  5928.4   404.8  6138.4   404.6
#Mann= 8 ,-1 , 0
  4546.8     .05       0  4561.8     .07       0  4705.9    .035       0
  4933.8      .1       0  4999.9     .05       0  5016.8      .1       0
  5095.9     .12       0  5168.1     .05       0
Bank Sta=4999.9,5016.8
XS Rating Curve= 0 ,0
Exp/Cntr=0.3,0.1