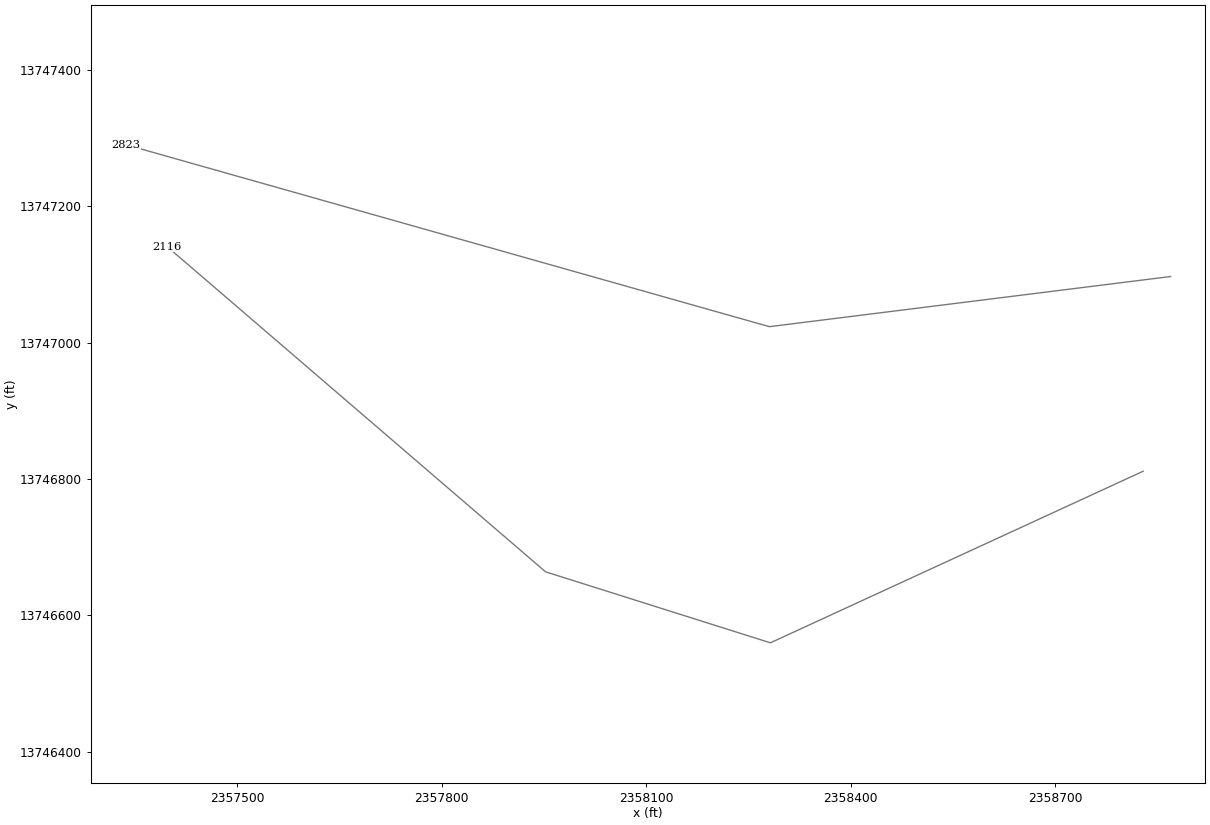
HEC-RAS study DARST CREEK.prj: DARST CREEK Base Level Engineering

--- DARST CREEK.g01 (geometry) --- (continued)

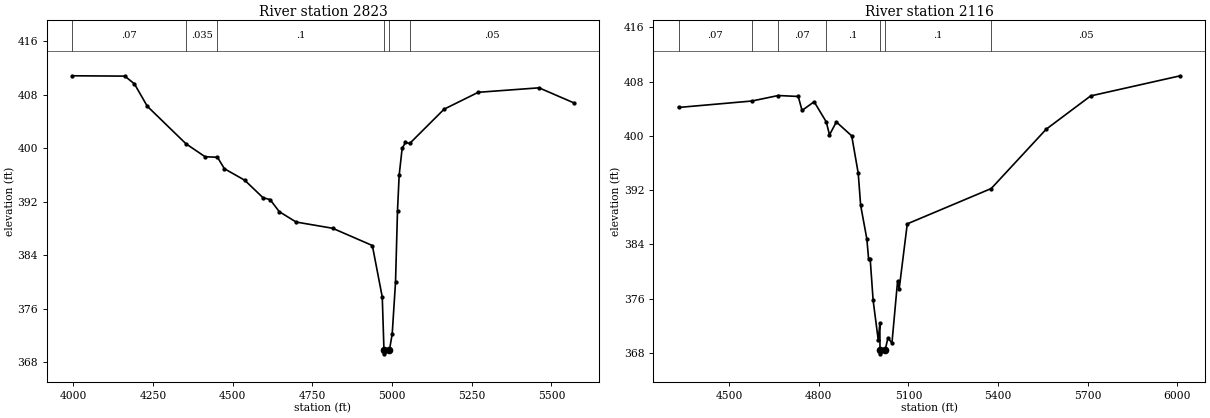
Type RM Length L Ch R = 1 ,2823    ,707,707,707
BEGIN DESCRIPTION:
X18707
END DESCRIPTION:
XS GIS Cut Line= 3
      2358869.13     13747096.93      2358280.57     13747023.36
      2357336.72     13747290.27
#Sta/Elev= 30
  3996.5  410.83  4161.9  410.78  4192.1  409.62  4232.4  406.28  4353.7  400.67
  4413.8  398.73  4452.6  398.65  4474.3  396.94    4538  395.22  4595.4  392.61
  4617.7  392.32  4646.5  390.52  4699.3  388.97  4813.7  388.04  4938.4  385.46
  4969.5  377.76  4974.9  369.77  4975.4  369.27  4991.8  369.77  5000.7  372.25
  5011.1  379.99  5017.3  390.65  5022.5  395.96  5031.9  399.99  5042.3  400.86
  5055.5  400.71  5163.5  405.84  5270.6  408.36  5461.2  409.03  5570.5  406.78
#Mann= 6 ,-1 , 0
  3996.5     .07       0  4353.7    .035       0  4452.6      .1       0
  4974.9     .05       0  4991.8      .1       0  5055.5     .05       0
Bank Sta=4974.9,4991.8
XS Rating Curve= 0 ,0
Exp/Cntr=0.3,0.1

Type RM Length L Ch R = 1 ,2116    ,0,0,0
BEGIN DESCRIPTION:
X18706
END DESCRIPTION:
XS GIS Cut Line= 4
      2358828.97      13746811.3      2358282.07     13746559.55
      2357952.21     13746663.72      2357397.33     13747140.57
#Sta/Elev= 30
  4330.4  404.18  4575.9  405.13  4664.2  405.94  4731.1   405.8  4743.8  403.74
  4784.3  405.02  4824.9  402.05  4835.7  400.14  4858.7  402.04  4910.1  399.99
  4931.9  394.47  4939.9  389.78  4960.8  384.77  4966.6  381.83  4971.9  381.83
  4981.8  375.73    4999  369.85  5004.2  372.36  5004.8  368.36  5005.3  367.86
  5021.7  368.36  5031.3  370.21  5044.7  369.44  5063.6  378.57  5068.9  377.42
    5096  387.02  5377.1  392.23  5561.2  400.98  5709.8  405.88    6010  408.85
#Mann= 7 ,-1 , 0
  4330.4     .07       0  4575.9    .035       0  4664.2     .07       0
  4824.9      .1       0  5004.8     .05       0  5021.7      .1       0
  5377.1     .05       0
Bank Sta=5004.8,5021.7
XS Rating Curve= 0 ,0
Exp/Cntr=0.3,0.1

Chan Stop Cuts=-1
Use User Specified Reach Order=0
Composite Channel Slope=5