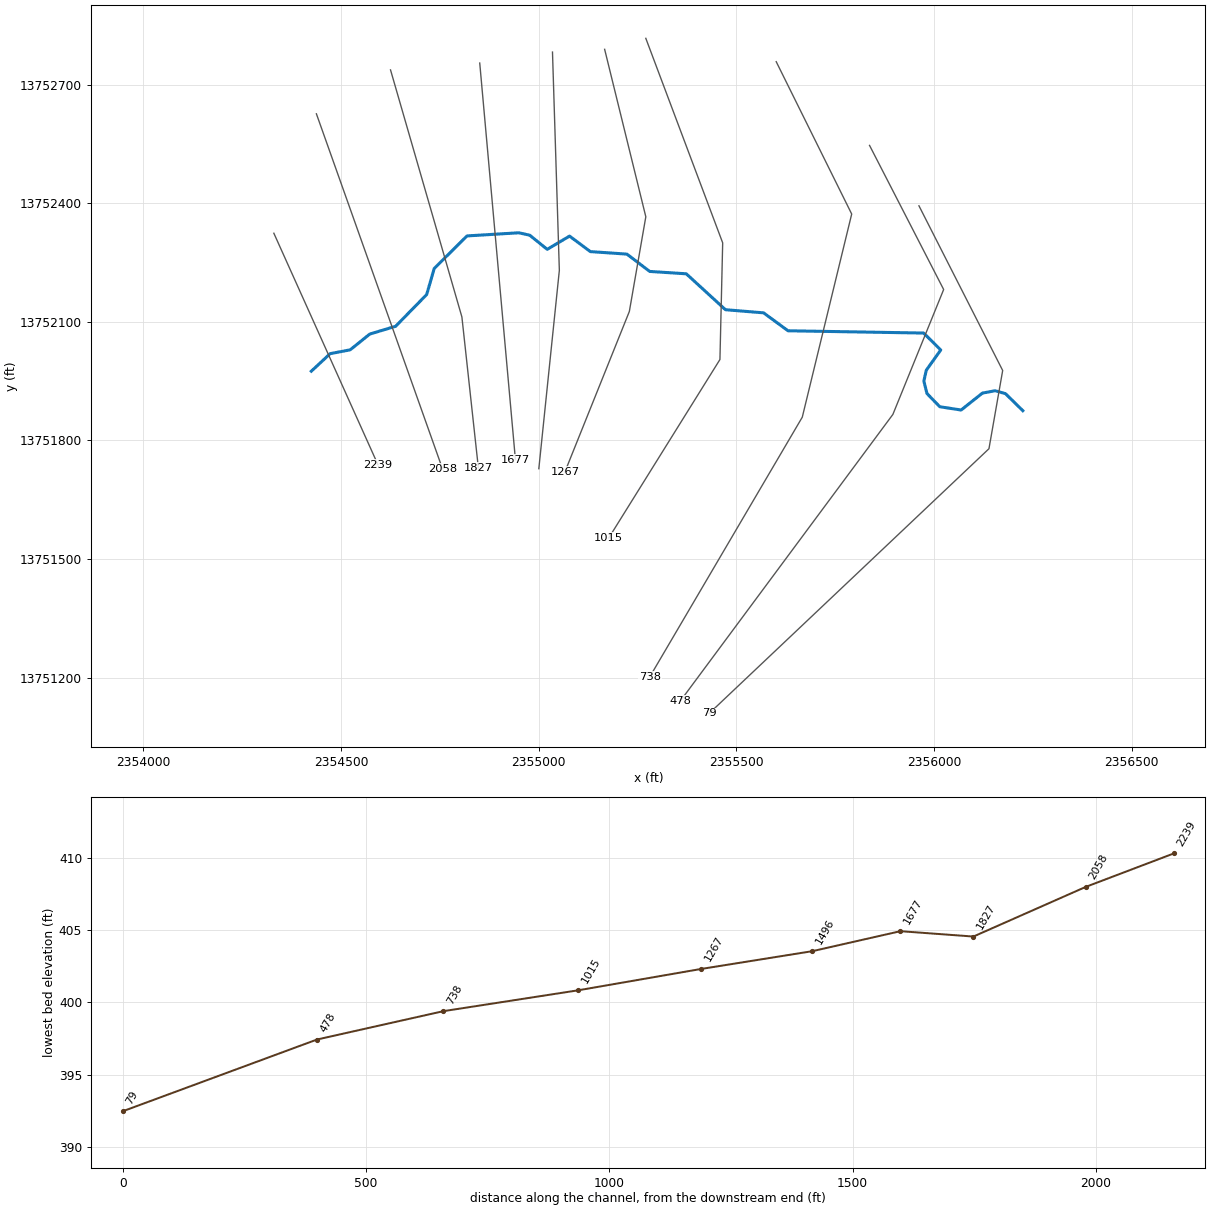
--- DARST TRIBUTARY 2.prj (project) ---

Proj Title=DARST TRIBUTARY 2 Base Level Engineering
Current Plan=p01
Default Exp/Contr=0.3,0.1
English Units
Geom File=g01
Flow File=f01
Plan File=p01
BEGIN DESCRIPTION:
DARST TRIBUTARY 2
END DESCRIPTION:

--- DARST TRIBUTARY 2.p01 (plan) ---

Plan Title=Multiple Run
Short Identifier=Multiple
Geom File=g01
Flow File=f01
Subcritical Flow
K Sum by GR= 0
Std Step Tol= 0.01
Critical Tol= 0.01
Num of Std Step Trials= 20
Max Error Tol= 0.3
Flow Tol Ratio= 0.001
Split Flow NTrial= 30
Split Flow Tol= 0.02
Split Flow Ratio= 0.02
Log Output Level= 0
Friction Slope Method= 1
Unsteady Friction Slope Method= 2
Unsteady Bridges Friction Slope Method= 1
Parabolic Critical Depth
Global Vel Dist=  1 , 1 , 1
Global Log Level= 0
CheckData=True
Encroach Param= -1, 0, 0, 0
BEGIN DESCRIPTION:
Multiple Run
END DESCRIPTION:

--- DARST TRIBUTARY 2.f01 (steady flow) ---

Flow Title=Multiple
Number of Profiles=7
Profile Names=10-year,25-year,50-year,1pct_min,100-year,1pct_plu,500-year
River Rch & RM= DARST TRIBUTARY ,Reach-1,2239
     490     781    1041     673    1342    2678    2211
Boundary for River Rch & Prof#=DARST TRIBUTARY ,Reach-1,1
Up Type=0
Dn Type=3
Dn Slope=0.005
Boundary for River Rch & Prof#=DARST TRIBUTARY ,Reach-1,2
Up Type=0
Dn Type=3
Dn Slope=0.005
Boundary for River Rch & Prof#=DARST TRIBUTARY ,Reach-1,3
Up Type=0
Dn Type=3
Dn Slope=0.005
Boundary for River Rch & Prof#=DARST TRIBUTARY ,Reach-1,4
Up Type=0
Dn Type=3
Dn Slope=0.005
Boundary for River Rch & Prof#=DARST TRIBUTARY ,Reach-1,5
Up Type=0
Dn Type=3
Dn Slope=0.005
Boundary for River Rch & Prof#=DARST TRIBUTARY ,Reach-1,6
Up Type=0
Dn Type=3
Dn Slope=0.005
Boundary for River Rch & Prof#=DARST TRIBUTARY ,Reach-1,7
Up Type=0
Dn Type=3
Dn Slope=0.005

--- DARST TRIBUTARY 2.g01 (geometry) ---

Geom Title=Existing Conditions

River Reach=DARST TRIBUTARY ,Reach-1
Reach XY= 30
      2354425.00     13751975.00      2354472.64     13752019.33
      2354523.33     13752029.04      2354572.81     13752068.90
      2354638.24     13752088.61      2354716.85     13752168.94
      2354735.77     13752234.70      2354818.79     13752317.20
      2354950.11     13752325.14      2354977.45     13752319.00
      2355021.78     13752283.28      2355078.22     13752316.72
      2355130.89     13752277.54      2355223.40     13752271.15
      2355280.98     13752227.36      2355373.50     13752221.38
      2355472.58     13752130.54      2355569.02     13752122.64
      2355630.94     13752077.26      2355974.01     13752071.47
      2356017.30     13752028.69      2355980.63     13751977.28
      2355974.56     13751949.90      2355982.38     13751918.57
      2356014.88     13751885.06      2356068.83     13751876.78
      2356122.76     13751919.59      2356154.78     13751925.54
      2356181.15     13751918.05      2356225.00     13751875.00

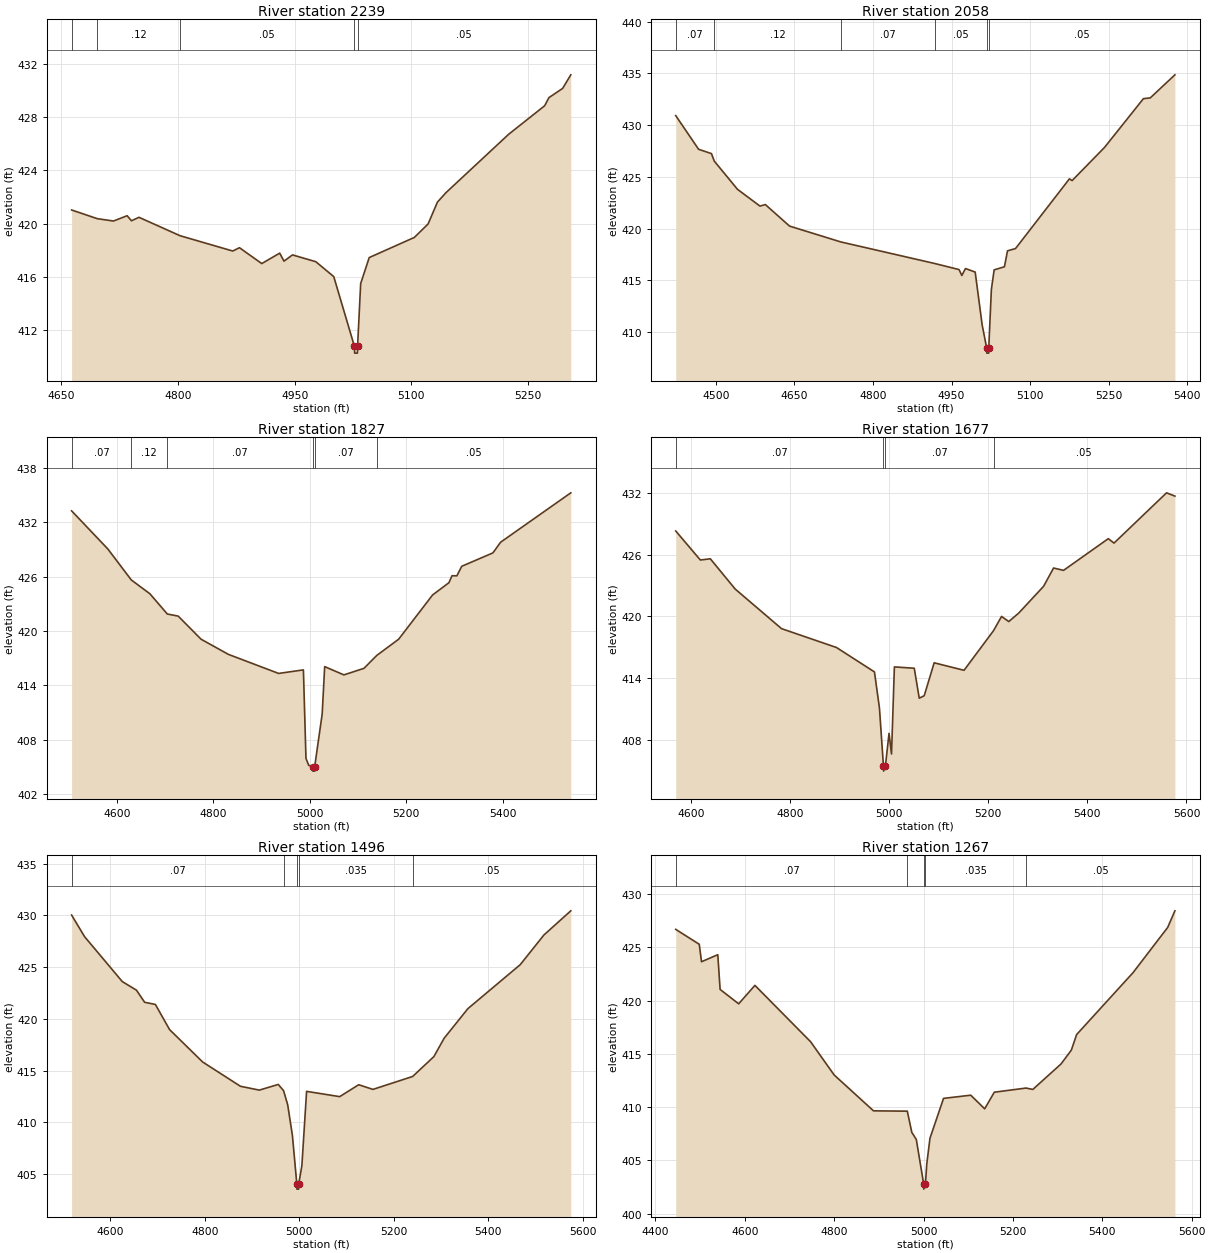
Type RM Length L Ch R = 1,2239,181,181,181
BEGIN DESCRIPTION:
X18735
END DESCRIPTION:
XS GIS Cut Line= 2
      2354330.19     13752324.01      2354593.46     13751738.58
#Sta/Elev= 30
  4663.1  421.03  4696.0  420.38  4716.9  420.20  4734.5  420.60  4740.0  420.22
  4749.7  420.48  4802.5  419.10  4870.3  417.95  4878.9  418.20  4907.6  417.01
  4930.7  417.79  4936.2  417.19  4947.1  417.66  4977.1  417.15  5000.2  416.03
  5026.8  410.79  5027.1  410.29  5030.6  410.29  5030.8  410.79  5034.8  415.51
  5045.8  417.46  5103.8  418.97  5121.5  419.98  5133.5  421.62  5144.5  422.33
  5225.1  426.71  5271.4  428.85  5276.9  429.46  5294.5  430.15  5305.0  431.17
#Mann=5,-1,0
  4663.1    0.07       0  4696.0    0.12       0  4802.5    0.05       0
  5026.8    0.05       0  5030.8    0.05       0
Bank Sta=5026.8,5030.8
Exp/Cntr=0.3,0.1

Type RM Length L Ch R = 1,2058,231,231,231
BEGIN DESCRIPTION:
X18743
END DESCRIPTION:
XS GIS Cut Line= 2
      2354437.83     13752626.10      2354756.72     13751728.35
#Sta/Elev= 30
  4423.6  430.92  4467.2  427.67  4491.8  427.25  4497.1  426.53  4541.5  423.80
  4584.4  422.18  4594.6  422.33  4640.8  420.25  4738.6  418.72  4918.4  416.63
  4964.3  416.05  4969.6  415.48  4976.6  416.15  4995.1  415.81  5008.4  410.71
  5017.0  408.48  5017.3  407.98  5020.8  407.98  5021.0  408.48  5026.0  414.13
  5031.3  416.02  5050.9  416.32  5056.8  417.86  5072.1  418.08  5174.9  424.81
  5180.2  424.65  5242.0  427.85  5316.2  432.56  5329.2  432.63  5376.3  434.86
#Mann=6,-1,0
  4423.6    0.07       0  4497.1    0.12       0  4738.6    0.07       0
  4918.4    0.05       0  5017.0    0.05       0  5021.0    0.05       0
Bank Sta=5017,5021
Exp/Cntr=0.3,0.1

Type RM Length L Ch R = 1,1827,150,150,150
BEGIN DESCRIPTION:
X18742
END DESCRIPTION:
XS GIS Cut Line= 3
      2354625.34     13752737.20      2354805.90     13752112.16
      2354847.57     13751730.22
#Sta/Elev= 30
  4506.4  433.24  4581.5  429.04  4630.0  425.63  4668.7  424.10  4704.8  421.87
  4727.3  421.64  4774.8  419.09  4831.4  417.42  4935.5  415.32  4986.9  415.71
  4992.2  405.96  4997.9  405.19  5006.3  405.05  5006.6  404.55  5010.1  404.55
  5010.3  405.05  5025.8  410.84  5031.0  416.07  5070.8  415.16  5112.4  415.88
  5139.1  417.31  5184.3  419.09  5254.7  423.97  5288.5  425.32  5295.0  426.09
  5305.0  426.08  5315.1  427.13  5379.8  428.61  5395.6  429.78  5541.2  435.23
#Mann=6,-1,0
  4506.4    0.07       0  4630.0    0.12       0  4704.8    0.07       0
  5006.3    0.05       0  5010.3    0.07       0  5139.1    0.05       0
Bank Sta=5006.3,5010.3
Exp/Cntr=0.3,0.1

Type RM Length L Ch R = 1,1677,181,181,181
BEGIN DESCRIPTION:
X18741
END DESCRIPTION:
XS GIS Cut Line= 2
      2354851.04     13752754.51      2354941.32     13751751.07
#Sta/Elev= 30
  4569.2  428.33  4618.9  425.50  4639.0  425.62  4689.2  422.67  4782.7  418.81
  4893.7  416.97  4970.3  414.59  4980.4  411.05  4988.4  405.42  4988.7  404.92
  4992.4  405.42  4999.7  408.60  5004.7  406.59  5010.5  415.08  5050.6  414.95
  5060.7  412.03  5070.7  412.27  5090.8  415.48  5151.1  414.75  5210.7  418.62
  5226.8  420.00  5241.4  419.50  5261.5  420.33  5311.7  422.94  5331.8  424.72
  5351.9  424.49  5442.2  427.58  5453.8  427.15  5559.8  432.05  5576.7  431.73
#Mann=4,-1,0
  4569.2    0.07       0  4988.4    0.05       0  4992.4    0.07       0
  5210.7    0.05       0
Bank Sta=4988.4,4992.4
Exp/Cntr=0.3,0.1

Type RM Length L Ch R = 1,1496,229,229,229
BEGIN DESCRIPTION:
X18740
END DESCRIPTION:
XS GIS Cut Line= 3
      2355035.07     13752782.28      2355052.43     13752230.22
      2355000.51     13751728.33
#Sta/Elev= 30
  4517.7  430.03  4545.0  427.95  4625.0  423.60  4655.0  422.77  4672.3  421.60
  4695.1  421.39  4725.1  418.96  4795.1  415.83  4875.2  413.48  4915.2  413.11
  4955.2  413.66  4966.4  413.06  4975.2  411.69  4985.2  408.72  4994.5  404.04
  4994.7  403.54  4998.2  403.54  4998.5  404.04  5005.2  405.80  5015.2  412.99
  5085.3  412.48  5125.5  413.63  5155.7  413.18  5239.8  414.43  5284.7  416.35
  5306.5  418.13  5356.8  420.99  5467.4  425.23  5517.6  428.10  5574.6  430.44
#Mann=5,-1,0
  4517.7    0.07       0  4966.4   0.035       0  4994.5   0.035       0
  4998.5   0.035       0  5239.8    0.05       0
Bank Sta=4994.5,4998.5
Exp/Cntr=0.3,0.1

Type RM Length L Ch R = 1,1267,252,252,252
BEGIN DESCRIPTION:
X18739
END DESCRIPTION:
XS GIS Cut Line= 4
      2355167.01     13752789.28      2355271.18     13752365.63
      2355229.51     13752126.05      2355066.37     13751719.94
#Sta/Elev= 30
  4445.5  426.70  4498.1  425.30  4503.2  423.66  4539.6  424.32  4544.8  421.06
  4586.3  419.71  4622.7  421.44  4747.3  416.15  4800.0  413.03  4888.1  409.66
  4963.7  409.63  4973.8  407.64  4983.9  406.97  5000.3  402.81  5000.5  402.31
  5004.3  402.81  5007.3  404.67  5014.4  407.08  5044.8  410.83  5105.7  411.13
  5136.9  409.85  5158.4  411.41  5229.4  411.80  5244.6  411.67  5307.7  414.06
  5330.8  415.36  5342.6  416.82  5469.0  422.64  5546.4  426.88  5562.6  428.44
#Mann=5,-1,0
  4445.5    0.07       0  4963.7   0.035       0  5000.3   0.035       0
  5004.3   0.035       0  5229.4    0.05       0
Bank Sta=5000.3,5004.3
Exp/Cntr=0.3,0.1

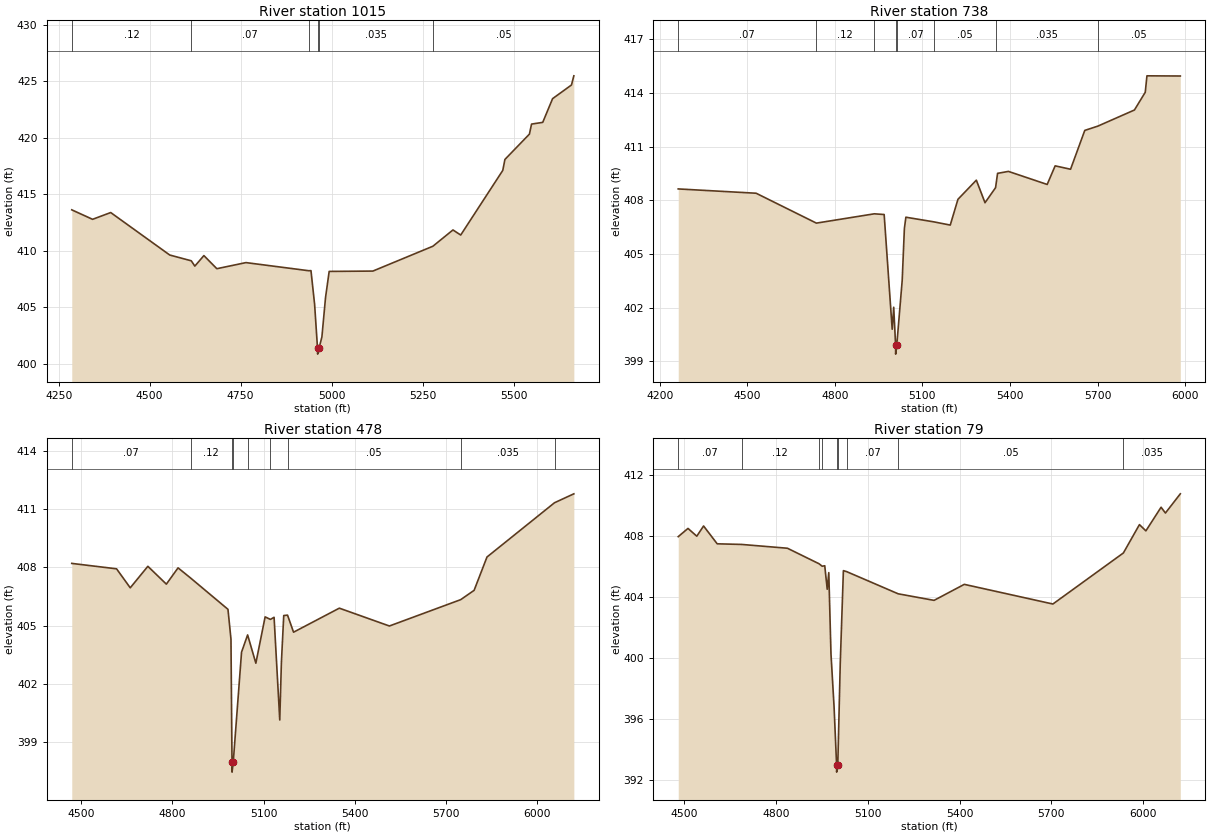
Type RM Length L Ch R = 1,1015,277,277,277
BEGIN DESCRIPTION:
X18738
END DESCRIPTION:
XS GIS Cut Line= 4
      2355271.17     13752817.05      2355465.63     13752299.66
      2355458.68     13752004.52      2355177.42     13751553.12
#Sta/Elev= 30
  4285.9  413.61  4343.1  412.77  4392.9  413.37  4555.2  409.61  4614.3  409.10
  4624.1  408.63  4649.0  409.56  4684.6  408.40  4764.6  408.94  4937.5  408.22
  4943.3  408.23  4953.3  405.24  4961.3  401.34  4961.6  400.84  4965.3  401.34
  4973.3  402.36  4983.3  405.85  4993.3  408.16  5113.4  408.19  5278.4  410.39
  5333.5  411.83  5354.8  411.38  5470.4  417.10  5476.3  418.07  5543.6  420.31
  5549.5  421.20  5580.2  421.35  5607.3  423.45  5659.2  424.66  5665.7  425.47
#Mann=6,-1,0
  4285.9    0.12       0  4614.3    0.07       0  4937.5   0.035       0
  4961.3   0.035       0  4965.3   0.035       0  5278.4    0.05       0
Bank Sta=4961.3,4965.3
Exp/Cntr=0.3,0.1

Type RM Length L Ch R = 1,738,260,260,260
BEGIN DESCRIPTION:
X18737
END DESCRIPTION:
XS GIS Cut Line= 4
      2355601.04     13752757.99      2355792.01     13752372.58
      2355667.01     13751858.69      2355281.58     13751202.41
#Sta/Elev= 30
  4263.5  408.63  4530.3  408.39  4736.8  406.72  4935.3  407.24  4969.0  407.20
  4996.5  400.79  5001.7  402.02  5008.2  399.90  5008.4  399.40  5012.2  399.90
  5030.8  403.52  5038.3  406.42  5043.4  407.05  5139.4  406.79  5195.4  406.61
  5221.8  408.05  5284.8  409.12  5314.5  407.86  5350.7  408.70  5357.5  409.50
  5394.6  409.61  5527.5  408.88  5554.8  409.92  5607.6  409.73  5656.3  411.90
  5701.1  412.14  5826.4  413.04  5863.5  414.03  5869.3  414.95  5983.6  414.94
#Mann=8,-1,0
  4263.5    0.07       0  4736.8    0.12       0  4935.3    0.07       0
  5008.2    0.05       0  5012.2    0.07       0  5139.4    0.05       0
  5350.7   0.035       0  5701.1    0.05       0
Bank Sta=5008.2,5012.2
Exp/Cntr=0.3,0.1

Type RM Length L Ch R = 1,478,399,399,399
BEGIN DESCRIPTION:
X18736
END DESCRIPTION:
XS GIS Cut Line= 4
      2355837.16     13752546.18      2356024.65     13752181.61
      2355896.18     13751865.63      2355359.02     13751141.33
#Sta/Elev= 30
  4468.5  408.21  4616.0  407.93  4661.0  406.95  4719.0  408.06  4779.9  407.14
  4818.4  407.98  4860.1  407.45  4982.7  405.84  4992.6  404.30  4996.0  397.94
  4996.2  397.44  5000.0  397.94  5027.4  403.63  5047.4  404.52  5074.5  403.06
  5105.0  405.45  5122.5  405.32  5134.5  405.43  5153.2  400.13  5158.6  403.11
  5166.3  405.52  5178.8  405.54  5198.6  404.66  5349.3  405.90  5514.1  404.98
  5748.9  406.34  5793.0  406.82  5835.4  408.54  6057.7  411.34  6121.3  411.80
#Mann=9,-1,0
  4468.5    0.07       0  4860.1    0.12       0  4996.0    0.05       0
  5000.0    0.12       0  5047.4    0.07       0  5122.5    0.12       0
  5178.8    0.05       0  5748.9   0.035       0  6057.7    0.05       0
Bank Sta=4996,5000
Exp/Cntr=0.3,0.1

Type RM Length L Ch R = 1,79,0,0,0
BEGIN DESCRIPTION:
X18734
END DESCRIPTION:
XS GIS Cut Line= 4
      2355962.15     13752393.42      2356173.96     13751976.75
      2356139.24     13751778.83      2355431.60     13751109.35
#Sta/Elev= 30
  4479.6  407.94  4511.5  408.48  4540.3  407.97  4562.5  408.64  4607.1  407.47
  4686.6  407.43  4836.8  407.18  4940.4  406.16  4950.5  406.00  4958.9  406.03
  4967.0  404.49  4972.1  405.58  4979.3  400.25  4989.4  396.78  4997.6  392.99
  4997.8  392.49  5001.6  392.99  5009.7  399.67  5019.9  405.71  5031.2  405.64
  5199.1  404.19  5316.5  403.76  5415.4  404.81  5705.3  403.52  5935.9  406.87
  5988.4  408.73  6009.5  408.32  6059.2  409.87  6073.4  409.49  6122.1  410.75
#Mann=9,-1,0
  4479.6    0.07       0  4686.6    0.12       0  4940.4    0.07       0
  4950.5    0.12       0  4997.6    0.05       0  5001.6    0.12       0
  5031.2    0.07       0  5199.1    0.05       0  5935.9   0.035       0
Bank Sta=4997.6,5001.6
Exp/Cntr=0.3,0.1

Chan Stop Cuts=-1