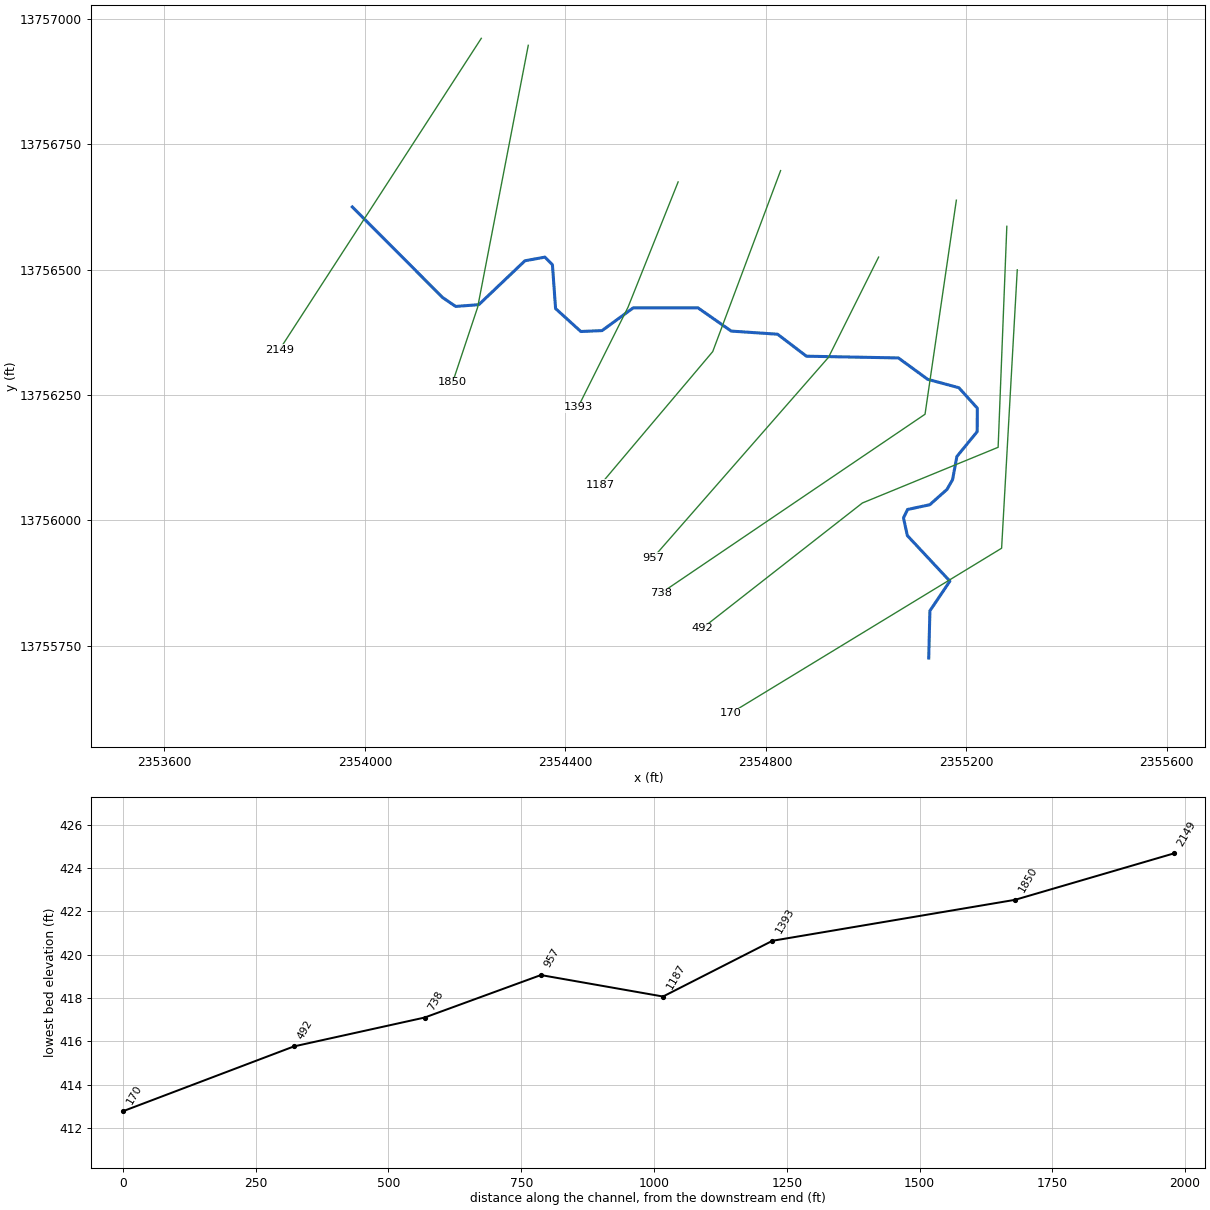
--- DARST TRIBUTARY 3.prj (project) ---

Proj Title=DARST TRIBUTARY 3 Base Level Engineering
Current Plan=p01
Default Exp/Contr=0.3,0.1
English Units
Geom File=g01
Flow File=f01
Plan File=p01
BEGIN DESCRIPTION:
DARST TRIBUTARY 3
END DESCRIPTION:

--- DARST TRIBUTARY 3.p01 (plan) ---

Plan Title=Multiple Run
Short Identifier=Multiple
Geom File=g01
Flow File=f01
Subcritical Flow
K Sum by GR= 0
Std Step Tol= 0.01
Critical Tol= 0.01
Num of Std Step Trials= 20
Max Error Tol= 0.3
Flow Tol Ratio= 0.001
Split Flow NTrial= 30
Split Flow Tol= 0.02
Split Flow Ratio= 0.02
Log Output Level= 0
Friction Slope Method= 1
Unsteady Friction Slope Method= 2
Unsteady Bridges Friction Slope Method= 1
Parabolic Critical Depth
Global Vel Dist=  1 , 1 , 1
Global Log Level= 0
CheckData=True
Encroach Param= -1, 0, 0, 0
BEGIN DESCRIPTION:
Multiple Run
END DESCRIPTION:

--- DARST TRIBUTARY 3.f01 (steady flow) ---

Flow Title=Multiple
Number of Profiles=7
Profile Names=10-year,25-year,50-year,1pct_min,100-year,1pct_plu,500-year
River Rch & RM= DARST TRIBUTARY ,Reach-1,2149
     765    1258    1713    1129    2253    4496    3865
Boundary for River Rch & Prof#=DARST TRIBUTARY ,Reach-1,1
Up Type=0
Dn Type=3
Dn Slope=0.005
Boundary for River Rch & Prof#=DARST TRIBUTARY ,Reach-1,2
Up Type=0
Dn Type=3
Dn Slope=0.005
Boundary for River Rch & Prof#=DARST TRIBUTARY ,Reach-1,3
Up Type=0
Dn Type=3
Dn Slope=0.005
Boundary for River Rch & Prof#=DARST TRIBUTARY ,Reach-1,4
Up Type=0
Dn Type=3
Dn Slope=0.005
Boundary for River Rch & Prof#=DARST TRIBUTARY ,Reach-1,5
Up Type=0
Dn Type=3
Dn Slope=0.005
Boundary for River Rch & Prof#=DARST TRIBUTARY ,Reach-1,6
Up Type=0
Dn Type=3
Dn Slope=0.005
Boundary for River Rch & Prof#=DARST TRIBUTARY ,Reach-1,7
Up Type=0
Dn Type=3
Dn Slope=0.005

--- DARST TRIBUTARY 3.g01 (geometry) ---

Geom Title=Existing Conditions

River Reach=DARST TRIBUTARY ,Reach-1
Reach XY= 30
      2353975.00     13756625.00      2354154.91     13756444.42
      2354181.05     13756426.58      2354227.28     13756430.08
      2354319.30     13756517.66      2354359.22     13756524.93
      2354374.19     13756509.69      2354380.45     13756422.32
      2354430.83     13756376.54      2354473.22     13756378.33
      2354535.50     13756423.77      2354664.49     13756423.80
      2354730.98     13756377.36      2354823.40     13756371.14
      2354880.94     13756327.26      2355064.50     13756323.80
      2355122.86     13756281.15      2355185.12     13756264.37
      2355221.96     13756223.58      2355221.70     13756176.76
      2355181.19     13756127.16      2355172.56     13756080.86
      2355161.45     13756061.46      2355127.08     13756030.89
      2355082.75     13756021.44      2355074.63     13756004.63
      2355082.38     13755969.25      2355167.23     13755878.41
      2355127.35     13755819.23      2355125.00     13755725.00

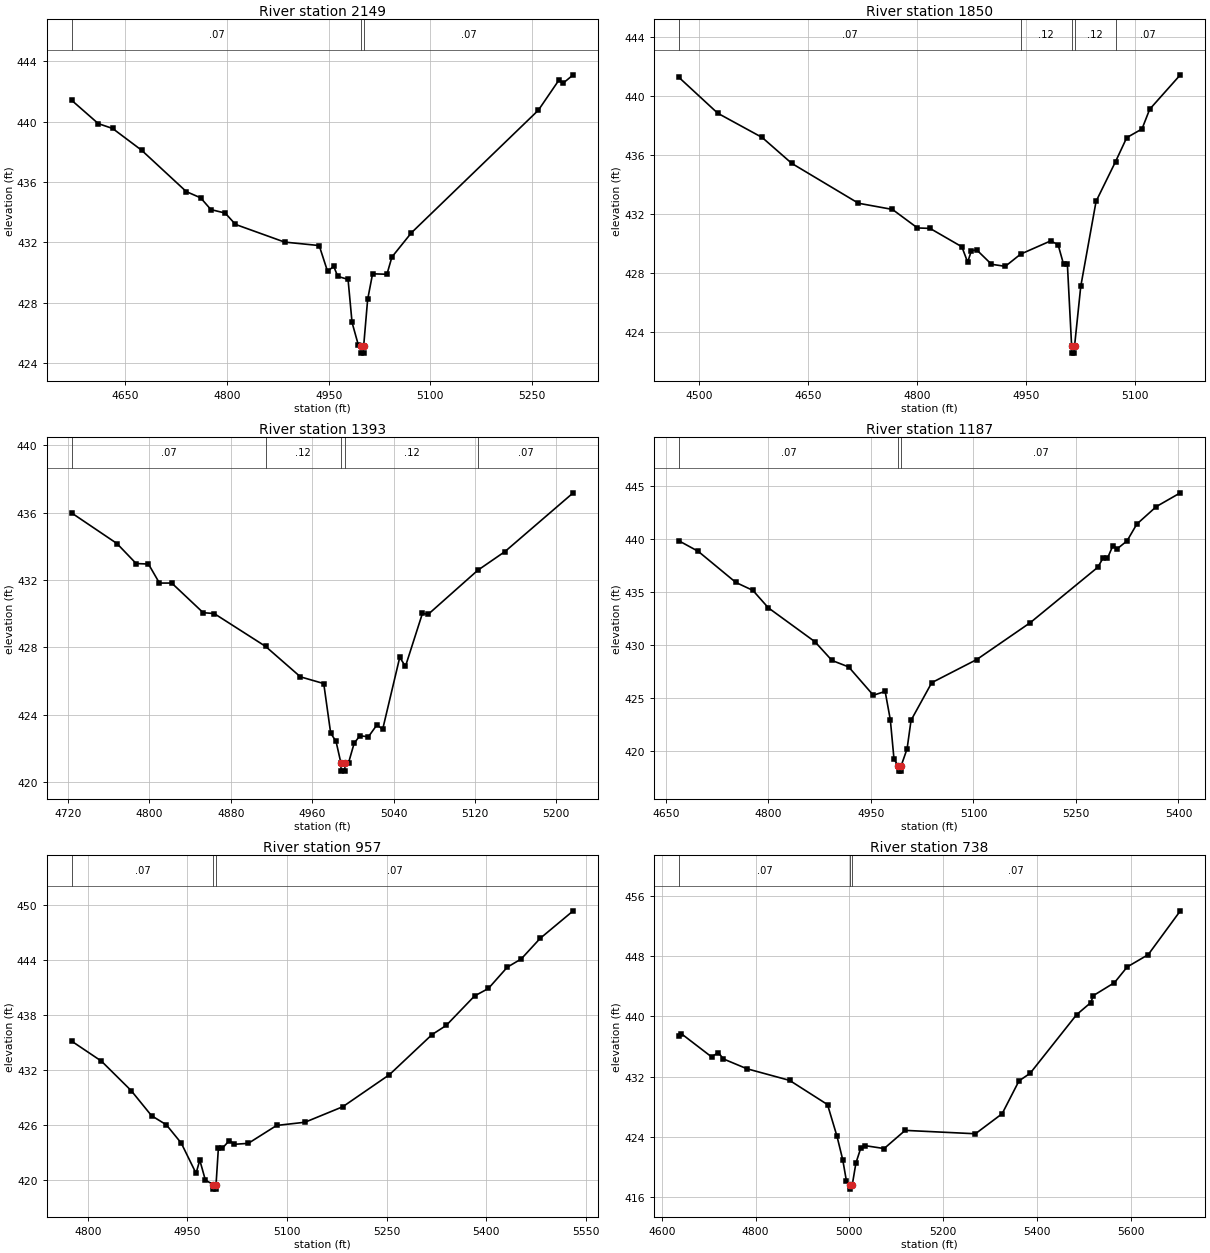
Type RM Length L Ch R = 1,2149,299,299,299
BEGIN DESCRIPTION:
X18748
END DESCRIPTION:
XS GIS Cut Line= 2
      2354232.23     13756961.49      2353829.74     13756340.40
#Sta/Elev= 30
  4570.7  441.40  4609.9  439.86  4631.0  439.54  4673.8  438.10  4739.8  435.36
  4760.9  434.95  4776.1  434.17  4797.2  433.94  4812.3  433.19  4884.8  432.02
  4935.9  431.79  4948.2  430.09  4957.4  430.41  4963.3  429.75  4978.5  429.55
  4984.4  426.70  4993.6  425.22  4997.5  425.17  4997.8  424.67  5001.3  424.67
  5001.6  425.17  5007.4  428.22  5014.7  429.92  5035.9  429.89  5043.2  431.03
  5072.1  432.64  5259.4  440.75  5289.7  442.74  5295.7  442.53  5310.8  443.09
#Mann=3,-1,0
  4570.7    0.07       0  4997.5    0.05       0  5001.6    0.07       0
Bank Sta=4997.5,5001.6
Exp/Cntr=0.3,0.1

Type RM Length L Ch R = 1,1850,457,457,457
BEGIN DESCRIPTION:
DARST TRIBUTARY 3 3.0
END DESCRIPTION:
XS GIS Cut Line= 3
      2354325.97     13756947.57      2354225.00     13756425.00
      2354174.99     13756274.96
#Sta/Elev= 30
  4472.2  441.28  4525.7  438.84  4586.9  437.19  4627.6  435.43  4719.4  432.72
  4766.2  432.30  4800.7  431.04  4818.0  431.01  4861.8  429.76  4869.8  428.71
  4874.9  429.49  4882.2  429.55  4902.6  428.57  4921.6  428.43  4942.7  429.26
  4984.1  430.16  4994.3  429.90  5001.9  428.56  5007.1  428.56  5012.9  423.03
  5013.2  422.53  5016.8  422.53  5017.0  423.03  5025.5  427.07  5046.6  432.85
  5073.4  435.55  5088.8  437.18  5109.8  437.77  5120.4  439.11  5162.6  441.45
#Mann=5,-1,0
  4472.2    0.07       0  4942.7    0.12       0  5012.9    0.05       0
  5017.0    0.12       0  5073.4    0.07       0
Bank Sta=5012.9,5017
Exp/Cntr=0.3,0.1

Type RM Length L Ch R = 1,1393,206,206,206
BEGIN DESCRIPTION:
DARST TRIBUTARY 3 2.0
END DESCRIPTION:
XS GIS Cut Line= 3
      2354625.00     13756675.00      2354525.00     13756425.00
      2354424.99     13756224.97
#Sta/Elev= 30
  4723.7  435.97  4768.1  434.16  4787.0  432.97  4799.1  432.94  4809.9  431.81
  4822.0  431.81  4852.9  430.05  4863.7  430.00  4914.2  428.05  4948.5  426.24
  4971.4  425.84  4978.2  422.90  4983.5  422.40  4988.2  421.14  4988.5  420.64
  4992.1  420.64  4992.3  421.14  4995.8  421.14  5001.3  422.30  5006.9  422.74
  5015.3  422.68  5023.7  423.39  5029.3  423.12  5046.1  427.40  5051.7  426.86
  5068.4  430.01  5074.0  429.95  5122.8  432.57  5149.5  433.68  5216.6  437.17
#Mann=5,-1,0
  4723.7    0.07       0  4914.2    0.12       0  4988.2    0.05       0
  4992.3    0.12       0  5122.8    0.07       0
Bank Sta=4988.2,4992.3
Exp/Cntr=0.3,0.1

Type RM Length L Ch R = 1,1187,230,230,230
BEGIN DESCRIPTION:
X18747
END DESCRIPTION:
XS GIS Cut Line= 3
      2354829.45     13756697.61      2354694.02     13756336.46
      2354469.55     13756070.55
#Sta/Elev= 30
  4669.0  439.86  4697.2  438.87  4752.4  435.92  4777.3  435.17  4799.9  433.52
  4868.1  430.31  4893.0  428.54  4917.4  427.93  4953.5  425.25  4970.8  425.61
  4978.4  422.92  4983.8  419.18  4990.1  418.57  4990.4  418.07  4994.0  418.07
  4994.2  418.57  5002.9  420.18  5008.7  422.88  5039.0  426.44  5104.9  428.63
  5183.0  432.11  5281.8  437.35  5289.6  438.22  5296.1  438.22  5303.9  439.38
  5310.4  439.11  5324.7  439.85  5339.0  441.44  5367.6  443.10  5402.7  444.40
#Mann=3,-1,0
  4669.0    0.07       0  4990.1    0.05       0  4994.2    0.07       0
Bank Sta=4990.1,4994.2
Exp/Cntr=0.3,0.1

Type RM Length L Ch R = 1,957,219,219,219
BEGIN DESCRIPTION:
DARST TRIBUTARY 3 1.0
END DESCRIPTION:
XS GIS Cut Line= 3
      2355024.99     13756524.97      2354925.00     13756325.00
      2354574.99     13755924.99
#Sta/Elev= 30
  4775.9  435.16  4820.6  432.99  4865.3  429.79  4896.1  427.05  4918.4  426.06
  4940.8  424.07  4963.1  420.78  4968.7  422.22  4977.1  420.04  4989.0  419.56
  4989.3  419.06  4992.9  419.06  4993.2  419.56  4996.7  423.52  5002.8  423.52
  5013.2  424.35  5020.8  423.94  5041.7  424.04  5084.4  425.99  5127.1  426.34
  5184.1  428.03  5254.3  431.52  5318.4  435.88  5339.7  436.87  5382.4  440.08
  5403.3  440.90  5431.8  443.22  5452.7  444.11  5481.2  446.35  5531.0  449.35
#Mann=3,-1,0
  4775.9    0.07       0  4989.0    0.05       0  4993.2    0.07       0
Bank Sta=4989,4993.2
Exp/Cntr=0.3,0.1

Type RM Length L Ch R = 1,738,246,246,246
BEGIN DESCRIPTION:
X18746
END DESCRIPTION:
XS GIS Cut Line= 3
      2355180.13     13756638.56      2355117.63     13756211.46
      2354589.93     13755853.87
#Sta/Elev= 30
  4636.6  437.40  4641.4  437.73  4706.2  434.64  4721.0  435.21  4731.2  434.37
  4781.7  433.06  4872.6  431.52  4953.5  428.31  4973.7  424.11  4985.9  421.01
  4993.9  418.15  5001.9  417.60  5002.2  417.10  5006.1  417.60  5014.1  420.57
  5024.2  422.50  5034.3  422.86  5074.2  422.48  5119.0  424.89  5268.8  424.44
  5325.8  427.10  5361.7  431.45  5385.5  432.46  5484.5  440.23  5514.4  441.81
  5520.5  442.77  5565.3  444.48  5592.4  446.56  5637.2  448.19  5705.7  454.00
#Mann=3,-1,0
  4636.6    0.07       0  5001.9    0.05       0  5006.1    0.07       0
Bank Sta=5001.9,5006.1
Exp/Cntr=0.3,0.1

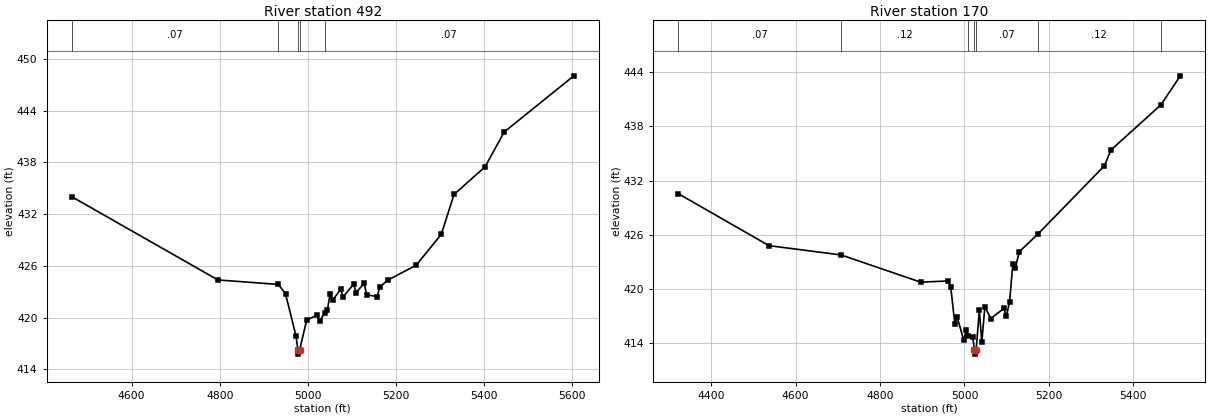
Type RM Length L Ch R = 1,492,322,322,322
BEGIN DESCRIPTION:
X18745
END DESCRIPTION:
XS GIS Cut Line= 4
      2355280.83     13756586.47      2355263.47     13756145.49
      2354992.63     13756034.38      2354673.19     13755784.38
#Sta/Elev= 30
  4464.2  434.02  4795.9  424.37  4933.1  423.85  4949.4  422.78  4973.4  417.83
  4977.4  416.27  4977.7  415.77  4981.6  416.27  4997.4  419.72  5021.4  420.30
  5026.8  419.56  5038.1  420.53  5044.4  420.89  5050.7  422.78  5056.2  422.01
  5074.7  423.29  5080.1  422.38  5104.1  423.90  5109.5  422.91  5128.1  423.98
  5133.5  422.64  5157.5  422.45  5163.3  423.55  5181.5  424.34  5246.1  426.08
  5303.0  429.66  5331.9  434.28  5402.4  437.48  5445.8  441.52  5603.9  448.03
#Mann=5,-1,0
  4464.2    0.07       0  4933.1    0.12       0  4977.4    0.05       0
  4981.6    0.12       0  5038.1    0.07       0
Bank Sta=4977.4,4981.6
Exp/Cntr=0.3,0.1

Type RM Length L Ch R = 1,170,0,0,0
BEGIN DESCRIPTION:
X18744
END DESCRIPTION:
XS GIS Cut Line= 3
      2355301.66     13756499.62      2355270.41     13755944.10
      2354729.35     13755614.60
#Sta/Elev= 30
  4321.7  430.55  4536.7  424.79  4707.8  423.76  4896.1  420.75  4961.7  420.88
  4967.6  420.18  4977.2  416.14  4983.0  416.84  4998.5  414.31  5004.4  415.42
  5009.5  414.81  5019.8  414.66  5023.6  413.28  5023.9  412.78  5027.8  413.28
  5035.3  417.67  5041.1  414.07  5048.4  418.03  5062.5  416.72  5093.4  417.84
  5099.3  416.97  5106.9  418.54  5114.7  422.75  5120.6  422.34  5130.2  424.13
  5173.7  426.05  5331.7  433.63  5347.2  435.38  5465.5  440.37  5511.6  443.59
#Mann=7,-1,0
  4321.7    0.07       0  4707.8    0.12       0  5009.5    0.07       0
  5023.6    0.05       0  5027.8    0.07       0  5173.7    0.12       0
  5465.5    0.07       0
Bank Sta=5023.6,5027.8
Exp/Cntr=0.3,0.1

Chan Stop Cuts=-1