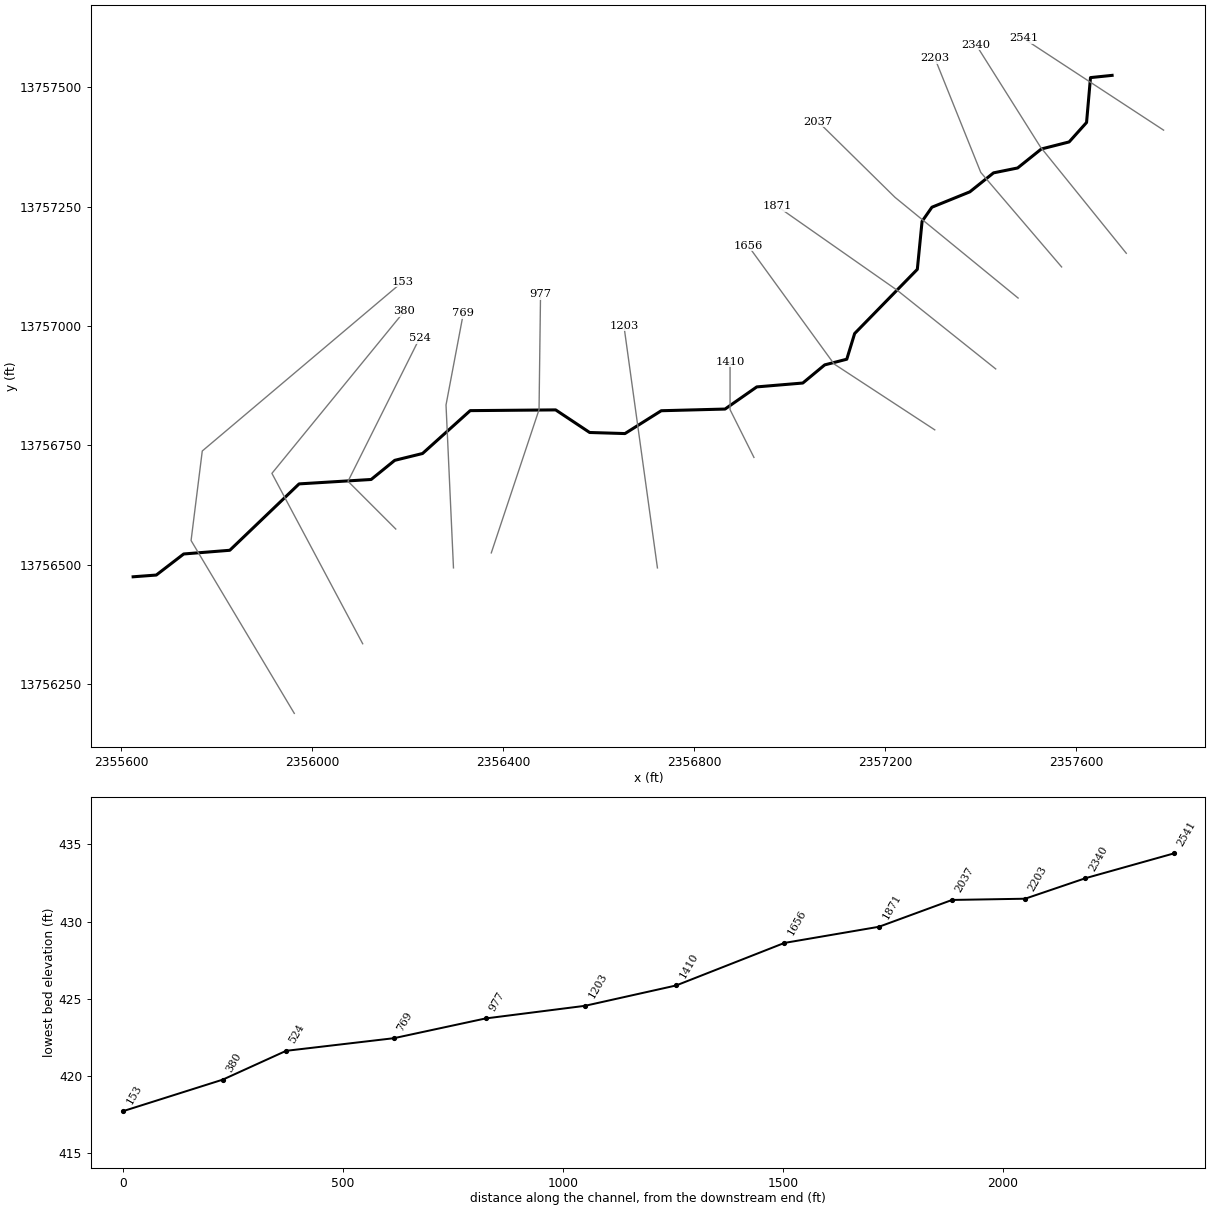
--- DARST TRIBUTARY 4.prj (project) ---

Proj Title=DARST TRIBUTARY 4 Base Level Engineering
Current Plan=p01
Default Exp/Contr=0.3,0.1
English Units
Geom File=g01
Flow File=f01
Plan File=p01
BEGIN DESCRIPTION:
DARST TRIBUTARY 4
END DESCRIPTION:

--- DARST TRIBUTARY 4.p01 (plan) ---

Plan Title=Multiple Run
Short Identifier=Multiple
Geom File=g01
Flow File=f01
Subcritical Flow
K Sum by GR= 0
Std Step Tol= 0.01
Critical Tol= 0.01
Num of Std Step Trials= 20
Max Error Tol= 0.3
Flow Tol Ratio= 0.001
Split Flow NTrial= 30
Split Flow Tol= 0.02
Split Flow Ratio= 0.02
Log Output Level= 0
Friction Slope Method= 1
Unsteady Friction Slope Method= 2
Unsteady Bridges Friction Slope Method= 1
Parabolic Critical Depth
Global Vel Dist=  1 , 1 , 1
Global Log Level= 0
CheckData=True
Encroach Param= -1, 0, 0, 0
BEGIN DESCRIPTION:
Multiple Run
END DESCRIPTION:

--- DARST TRIBUTARY 4.f01 (steady flow) ---

Flow Title=Multiple
Number of Profiles=7
Profile Names=10-year,25-year,50-year,1pct_min,100-year,1pct_plu,500-year
River Rch & RM= DARST TRIBUTARY ,Reach-1,2541
     456     726     967     625    1248    2490    2055
Boundary for River Rch & Prof#=DARST TRIBUTARY ,Reach-1,1
Up Type=0
Dn Type=3
Dn Slope=0.005
Boundary for River Rch & Prof#=DARST TRIBUTARY ,Reach-1,2
Up Type=0
Dn Type=3
Dn Slope=0.005
Boundary for River Rch & Prof#=DARST TRIBUTARY ,Reach-1,3
Up Type=0
Dn Type=3
Dn Slope=0.005
Boundary for River Rch & Prof#=DARST TRIBUTARY ,Reach-1,4
Up Type=0
Dn Type=3
Dn Slope=0.005
Boundary for River Rch & Prof#=DARST TRIBUTARY ,Reach-1,5
Up Type=0
Dn Type=3
Dn Slope=0.005
Boundary for River Rch & Prof#=DARST TRIBUTARY ,Reach-1,6
Up Type=0
Dn Type=3
Dn Slope=0.005
Boundary for River Rch & Prof#=DARST TRIBUTARY ,Reach-1,7
Up Type=0
Dn Type=3
Dn Slope=0.005

--- DARST TRIBUTARY 4.g01 (geometry) ---

Geom Title=Existing Conditions

River Reach=DARST TRIBUTARY ,Reach-1
Reach XY= 30
      2357675.00     13757525.00      2357629.75     13757520.32
      2357621.52     13757426.30      2357585.05     13757385.61
      2357526.77     13757370.80      2357477.20     13757331.08
      2357426.72     13757320.84      2357377.16     13757281.12
      2357297.72     13757248.90      2357277.08     13757219.29
      2357267.14     13757118.83      2357135.89     13756984.41
      2357119.39     13756930.59      2357073.16     13756918.72
      2357027.36     13756880.75      2356930.98     13756872.64
      2356864.49     13756826.23      2356730.94     13756822.73
      2356654.90     13756774.91      2356580.98     13756777.17
      2356509.78     13756824.48      2356330.86     13756822.94
      2356231.05     13756733.16      2356172.83     13756718.86
      2356123.44     13756678.76      2355972.55     13756669.53
      2355827.43     13756530.52      2355730.92     13756522.77
      2355673.49     13756478.64      2355625.00     13756475.00

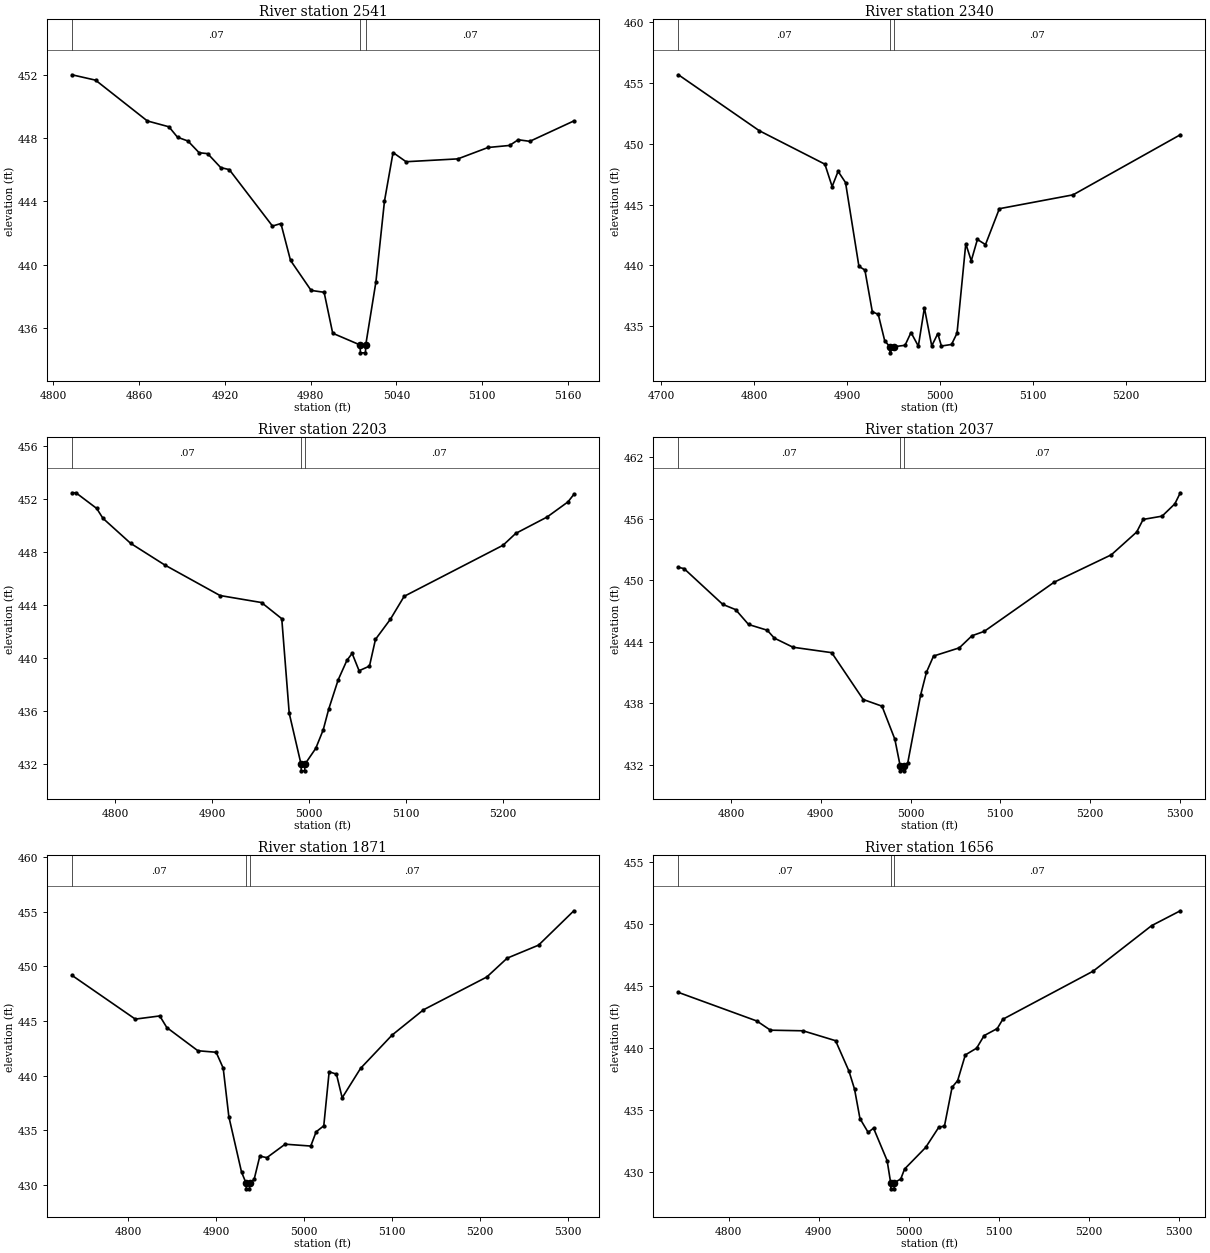
Type RM Length L Ch R = 1,2541,201,201,201
BEGIN DESCRIPTION:
X18756
END DESCRIPTION:
XS GIS Cut Line= 2
      2357782.81     13757410.30      2357489.26     13757602.54
#Sta/Elev= 30
  4813.1  452.01  4829.6  451.67  4865.8  449.09  4880.9  448.72  4886.9  448.06
  4894.2  447.82  4902.0  447.08  4908.0  447.02  4917.1  446.14  4923.1  446.01
  4953.3  442.44  4959.2  442.60  4965.9  440.27  4980.3  438.37  4989.4  438.25
  4995.4  435.66  5014.5  434.92  5014.8  434.42  5018.3  434.42  5018.5  434.92
  5025.6  438.90  5031.6  444.02  5037.6  447.09  5046.7  446.51  5082.9  446.69
  5104.0  447.41  5119.1  447.54  5125.1  447.90  5133.2  447.80  5164.0  449.09
#Mann=3,-1,0
  4813.1    0.07       0  5014.5    0.05       0  5018.5    0.07       0
Bank Sta=5014.5,5018.5
Exp/Cntr=0.3,0.1

Type RM Length L Ch R = 1,2340,137,137,137
BEGIN DESCRIPTION:
DARST TRIBUTARY 4 5.0
END DESCRIPTION:
XS GIS Cut Line= 3
      2357704.72     13757152.45      2357525.00     13757375.00
      2357389.81     13757589.62
#Sta/Elev= 30
  4718.8  455.67  4805.8  451.07  4876.3  448.32  4884.1  446.48  4890.5  447.73
  4898.5  446.81  4912.9  439.92  4919.3  439.62  4927.3  436.19  4933.7  435.97
  4940.6  433.81  4946.1  433.31  4946.3  432.81  4950.1  433.31  4962.5  433.43
  4968.9  434.48  4976.8  433.36  4983.3  436.51  4991.2  433.38  4997.7  434.39
  5001.6  433.37  5012.5  433.50  5018.4  434.43  5027.8  441.78  5033.7  440.38
  5040.3  442.13  5049.0  441.71  5063.9  444.66  5143.2  445.80  5258.5  450.74
#Mann=3,-1,0
  4718.8    0.07       0  4946.1    0.05       0  4950.1    0.07       0
Bank Sta=4946.1,4950.1
Exp/Cntr=0.3,0.1

Type RM Length L Ch R = 1,2203,166,166,166
BEGIN DESCRIPTION:
X18755
END DESCRIPTION:
XS GIS Cut Line= 3
      2357569.28     13757123.84      2357400.00     13757321.76
      2357303.93     13757560.63
#Sta/Elev= 30
  4755.5  452.48  4759.6  452.48  4781.0  451.30  4787.5  450.55  4816.1  448.66
  4851.2  447.03  4908.3  444.72  4951.1  444.19  4972.0  442.97  4979.7  435.83
  4991.9  431.98  4992.1  431.48  4995.6  431.48  4995.9  431.98  5007.1  433.18
  5014.8  434.58  5020.4  436.13  5030.2  438.35  5039.2  439.82  5044.6  440.35
  5051.8  439.04  5062.5  439.39  5068.7  441.41  5084.1  442.93  5098.3  444.66
  5200.4  448.52  5213.4  449.41  5245.8  450.65  5267.3  451.79  5273.4  452.36
#Mann=3,-1,0
  4755.5    0.07       0  4991.9    0.05       0  4995.9    0.07       0
Bank Sta=4991.9,4995.9
Exp/Cntr=0.3,0.1

Type RM Length L Ch R = 1,2037,166,166,166
BEGIN DESCRIPTION:
X18754
END DESCRIPTION:
XS GIS Cut Line= 3
      2357478.16     13757058.71      2357220.31     13757269.67
      2357059.40     13757428.00
#Sta/Elev= 30
  4741.5  451.26  4747.8  451.13  4790.9  447.64  4805.2  447.13  4819.6  445.68
  4840.4  445.12  4848.3  444.35  4869.1  443.46  4912.2  442.93  4947.3  438.36
  4968.2  437.71  4982.5  434.49  4988.4  431.90  4988.7  431.40  4992.2  431.40
  4992.4  431.90  4996.9  432.19  5011.2  438.79  5017.7  441.02  5025.6  442.60
  5054.3  443.40  5068.4  444.58  5082.1  445.01  5160.0  449.81  5223.6  452.48
  5251.8  454.70  5259.0  455.93  5280.1  456.25  5294.3  457.45  5300.4  458.53
#Mann=3,-1,0
  4741.5    0.07       0  4988.4    0.05       0  4992.4    0.07       0
Bank Sta=4988.4,4992.4
Exp/Cntr=0.3,0.1

Type RM Length L Ch R = 1,1871,215,215,215
BEGIN DESCRIPTION:
DARST TRIBUTARY 4 4.0
END DESCRIPTION:
XS GIS Cut Line= 3
      2357431.26     13756910.29      2357225.00     13757075.00
      2356973.94     13757250.73
#Sta/Elev= 30
  4736.3  449.17  4808.3  445.17  4836.1  445.46  4844.1  444.40  4879.4  442.28
  4900.2  442.14  4908.2  440.69  4914.6  436.26  4929.0  431.20  4934.3  430.16
  4934.5  429.66  4938.0  429.66  4938.3  430.16  4943.4  430.54  4949.8  432.65
  4957.8  432.51  4978.6  433.74  5007.7  433.57  5013.8  434.87  5022.5  435.42
  5028.6  440.36  5036.9  440.14  5043.4  437.98  5064.3  440.67  5100.1  443.71
  5135.8  446.02  5207.8  449.02  5230.9  450.74  5266.6  451.93  5306.7  455.07
#Mann=3,-1,0
  4736.3    0.07       0  4934.3    0.05       0  4938.3    0.07       0
Bank Sta=4934.3,4938.3
Exp/Cntr=0.3,0.1

Type RM Length L Ch R = 1,1656,246,246,246
BEGIN DESCRIPTION:
X18753
END DESCRIPTION:
XS GIS Cut Line= 3
      2357303.65     13756782.69      2357092.71     13756920.72
      2356912.99     13757168.15
#Sta/Elev= 30
  4744.1  444.47  4831.3  442.16  4846.4  441.42  4882.6  441.37  4918.8  440.57
  4933.7  438.11  4939.9  436.65  4945.9  434.28  4955.0  433.17  4961.0  433.51
  4976.1  430.89  4980.0  429.11  4980.3  428.61  4983.8  428.61  4984.0  429.11
  4991.2  429.40  4995.5  430.21  5018.9  431.95  5033.6  433.59  5039.8  433.67
  5048.3  436.81  5054.5  437.35  5063.0  439.42  5075.6  439.97  5083.9  440.98
  5098.5  441.55  5104.7  442.30  5205.2  446.19  5270.1  449.86  5302.0  451.06
#Mann=3,-1,0
  4744.1    0.07       0  4980.0    0.05       0  4984.0    0.07       0
Bank Sta=4980,4984
Exp/Cntr=0.3,0.1

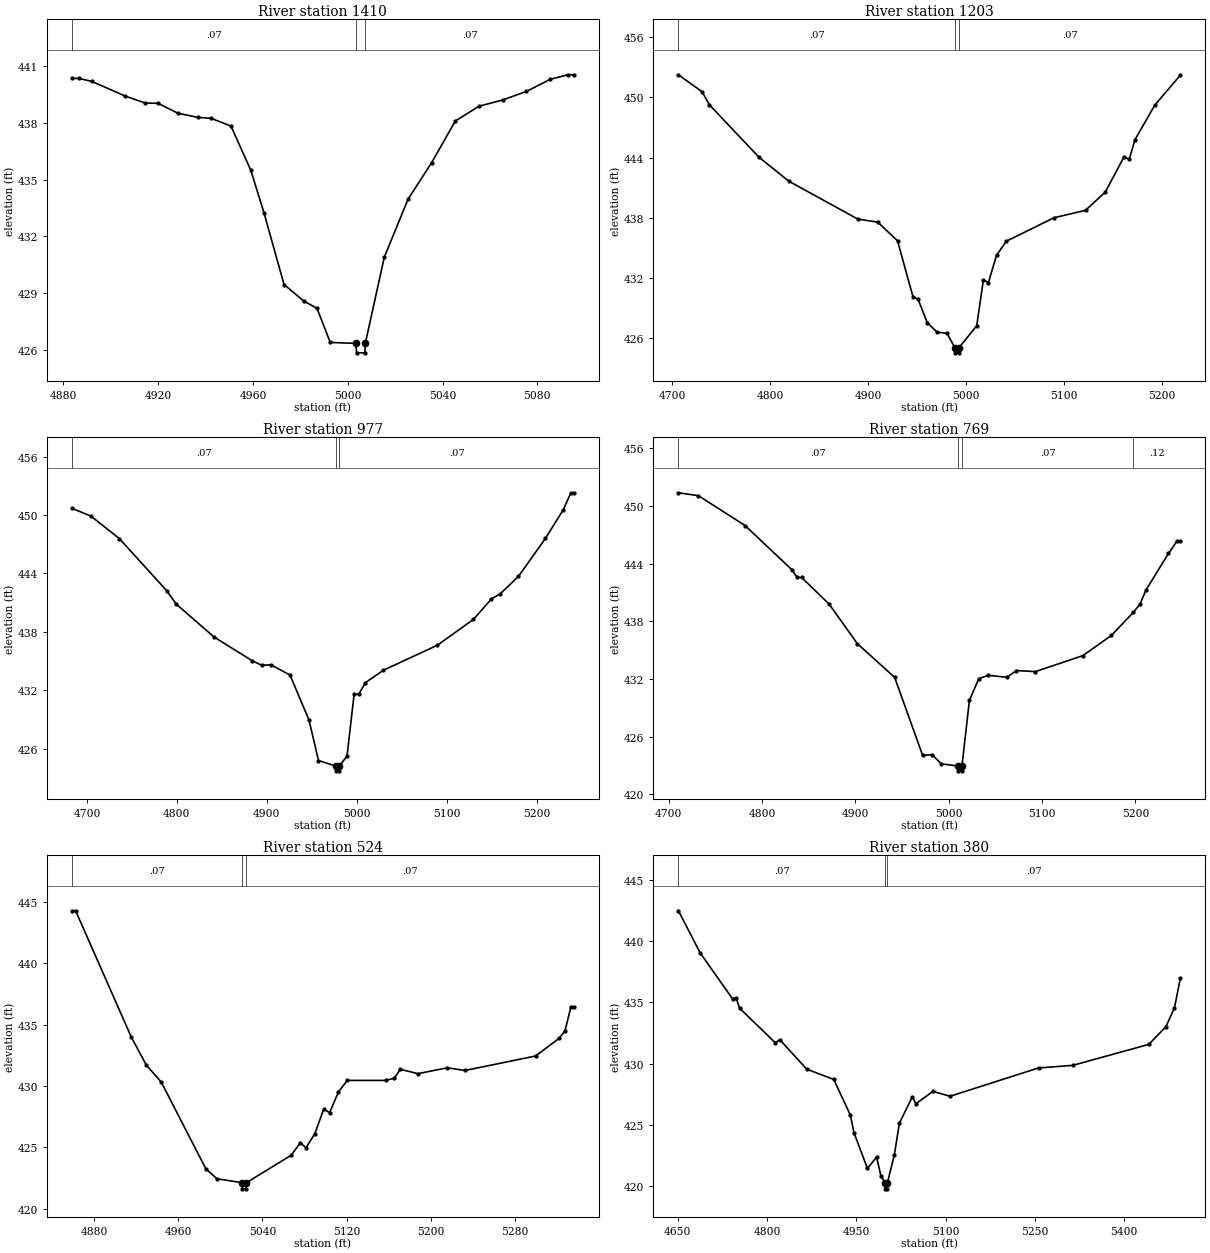
Type RM Length L Ch R = 1,1410,207,207,207
BEGIN DESCRIPTION:
DARST TRIBUTARY 4 3.0
END DESCRIPTION:
XS GIS Cut Line= 3
      2356925.01     13756724.98      2356875.00     13756825.00
      2356875.00     13756924.98
#Sta/Elev= 30
  4883.6  440.35  4886.4  440.35  4892.0  440.19  4906.0  439.42  4914.4  439.05
  4920.0  439.03  4928.3  438.51  4936.7  438.29  4942.3  438.24  4950.7  437.83
  4959.1  435.49  4964.7  433.22  4973.1  429.46  4981.4  428.59  4987.0  428.20
  4992.6  426.40  5003.4  426.35  5003.7  425.85  5007.2  425.85  5007.4  426.35
  5015.4  430.90  5025.4  433.96  5035.4  435.90  5045.4  438.10  5055.4  438.88
  5065.4  439.21  5075.4  439.66  5085.4  440.30  5092.9  440.54  5095.4  440.54
#Mann=3,-1,0
  4883.6    0.07       0  5003.4    0.05       0  5007.4    0.07       0
Bank Sta=5003.4,5007.4
Exp/Cntr=0.3,0.1

Type RM Length L Ch R = 1,1203,226,226,226
BEGIN DESCRIPTION:
X18752
END DESCRIPTION:
XS GIS Cut Line= 2
      2356722.92     13756493.60      2356652.70     13757000.76
#Sta/Elev= 30
  4706.5  452.25  4730.5  450.57  4738.2  449.25  4788.7  444.03  4819.0  441.65
  4889.6  437.86  4909.8  437.56  4930.0  435.70  4945.8  430.12  4950.9  429.89
  4960.3  427.54  4970.4  426.59  4980.5  426.47  4988.6  425.03  4988.8  424.53
  4992.3  424.53  4992.6  425.03  5010.8  427.23  5017.6  431.80  5022.7  431.52
  5031.0  434.26  5041.1  435.66  5089.4  437.99  5121.8  438.74  5142.0  440.56
  5161.2  444.10  5166.3  443.81  5172.3  445.79  5192.5  449.23  5218.5  452.21
#Mann=3,-1,0
  4706.5    0.07       0  4988.6    0.05       0  4992.6    0.07       0
Bank Sta=4988.6,4992.6
Exp/Cntr=0.3,0.1

Type RM Length L Ch R = 1,977,208,208,208
BEGIN DESCRIPTION:
DARST TRIBUTARY 4 2.0
END DESCRIPTION:
XS GIS Cut Line= 3
      2356375.01     13756525.03      2356475.00     13756825.00
      2356478.13     13757066.59
#Sta/Elev= 30
  4683.4  450.68  4704.4  449.89  4736.1  447.57  4788.8  442.21  4799.3  440.84
  4841.5  437.45  4883.6  435.03  4894.2  434.56  4904.7  434.60  4925.8  433.55
  4946.9  428.91  4957.4  424.77  4976.5  424.21  4976.8  423.71  4980.3  423.71
  4980.5  424.21  4989.1  425.22  4997.0  431.58  5002.1  431.58  5009.6  432.77
  5029.6  434.05  5089.6  436.62  5129.6  439.27  5149.6  441.37  5159.6  441.92
  5179.6  443.68  5209.6  447.59  5229.6  450.56  5237.9  452.28  5241.2  452.28
#Mann=3,-1,0
  4683.4    0.07       0  4976.5    0.05       0  4980.5    0.07       0
Bank Sta=4976.5,4980.5
Exp/Cntr=0.3,0.1

Type RM Length L Ch R = 1,769,245,245,245
BEGIN DESCRIPTION:
X18751
END DESCRIPTION:
XS GIS Cut Line= 3
      2356295.83     13756493.64      2356280.21     13756834.78
      2356316.66     13757027.47
#Sta/Elev= 30
  4710.5  451.38  4731.9  451.08  4781.9  447.97  4832.0  443.37  4837.5  442.58
  4842.5  442.56  4872.0  439.78  4902.1  435.68  4942.1  432.16  4972.1  424.04
  4982.1  424.11  4992.2  423.16  5010.2  422.93  5010.4  422.43  5013.9  422.43
  5014.2  422.93  5022.2  429.77  5032.2  432.01  5042.2  432.38  5062.4  432.17
  5072.6  432.87  5092.9  432.76  5143.8  434.43  5174.3  436.53  5197.8  438.93
  5204.9  439.78  5211.1  441.22  5235.4  445.06  5244.3  446.32  5248.1  446.32
#Mann=4,-1,0
  4710.5    0.07       0  5010.2    0.05       0  5014.2    0.07       0
  5197.8    0.12       0
Bank Sta=5010.2,5014.2
Exp/Cntr=0.3,0.1

Type RM Length L Ch R = 1,524,144,144,144
BEGIN DESCRIPTION:
DARST TRIBUTARY 4 1.0
END DESCRIPTION:
XS GIS Cut Line= 3
      2356174.97     13756575.03      2356075.00     13756675.00
      2356225.01     13756975.02
#Sta/Elev= 30
  4859.1  444.28  4862.6  444.28  4915.6  433.96  4929.8  431.69  4943.9  430.32
  4986.3  423.24  4996.9  422.43  5020.8  422.11  5021.1  421.61  5024.6  421.61
  5024.8  422.11  5067.6  424.36  5075.9  425.36  5081.5  424.97  5089.9  426.12
  5098.3  428.11  5103.9  427.82  5112.3  429.52  5120.7  430.45  5157.0  430.45
  5165.4  430.63  5171.0  431.36  5187.7  431.00  5215.7  431.48  5232.5  431.26
  5299.5  432.44  5321.9  433.88  5327.5  434.50  5333.1  436.44  5335.9  436.44
#Mann=3,-1,0
  4859.1    0.07       0  5020.8    0.05       0  5024.8    0.07       0
Bank Sta=5020.8,5024.8
Exp/Cntr=0.3,0.1

Type RM Length L Ch R = 1,380,227,227,227
BEGIN DESCRIPTION:
X18750
END DESCRIPTION:
XS GIS Cut Line= 3
      2356105.72     13756334.79      2355915.63     13756691.55
      2356193.18     13757031.36
#Sta/Elev= 30
  4651.4  442.51  4688.1  439.05  4742.3  435.30  4748.3  435.36  4754.0  434.54
  4814.2  431.70  4821.6  431.96  4866.9  429.54  4912.3  428.70  4940.3  425.77
  4946.2  424.34  4968.9  421.41  4984.2  422.34  4991.6  420.80  4998.5  420.24
  4998.8  419.74  5002.3  419.74  5002.5  420.24  5014.2  422.55  5022.5  425.11
  5044.4  427.29  5050.1  426.70  5078.9  427.72  5107.6  427.32  5256.2  429.64
  5313.7  429.85  5441.5  431.57  5470.2  433.02  5484.6  434.56  5494.4  436.99
#Mann=3,-1,0
  4651.4    0.07       0  4998.5    0.05       0  5002.5    0.07       0
Bank Sta=4998.5,5002.5
Exp/Cntr=0.3,0.1

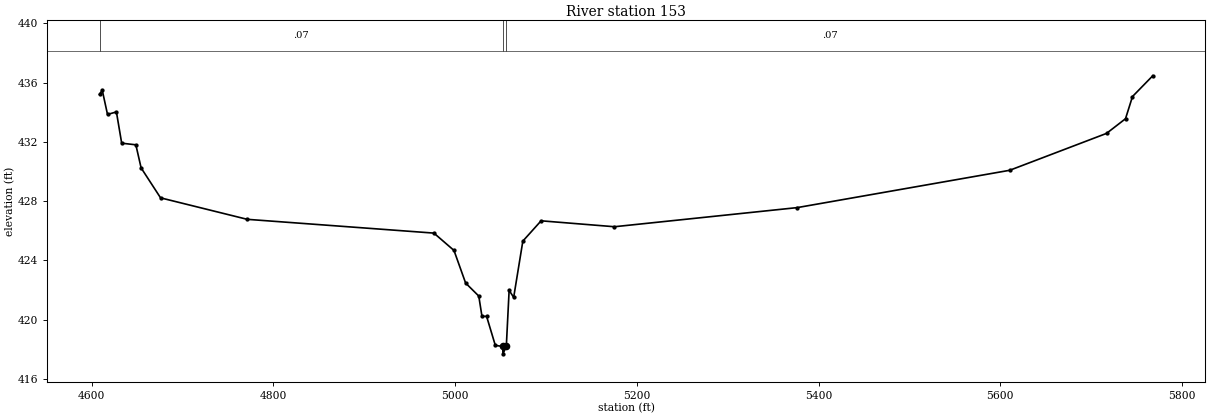
Type RM Length L Ch R = 1,153,0,0,0
BEGIN DESCRIPTION:
X18749
END DESCRIPTION:
XS GIS Cut Line= 4
      2355962.48     13756188.98      2355746.35     13756550.92
      2355769.79     13756738.42      2356189.10     13757092.62
#Sta/Elev= 30
  4608.5  435.20  4611.5  435.49  4617.3  433.85  4627.1  434.02  4632.9  431.91
  4648.5  431.80  4654.3  430.24  4675.7  428.22  4771.1  426.77  4976.6  425.84
  4998.7  424.67  5011.5  422.47  5026.0  421.59  5029.5  420.22  5034.6  420.22
  5044.2  418.26  5052.3  418.19  5052.6  417.69  5056.3  418.19  5059.4  421.98
  5064.4  421.50  5074.5  425.30  5094.6  426.67  5175.3  426.27  5376.4  427.56
  5610.4  430.08  5717.0  432.57  5737.9  433.56  5745.6  435.06  5767.9  436.46
#Mann=3,-1,0
  4608.5    0.07       0  5052.3    0.05       0  5056.3    0.07       0
Bank Sta=5052.3,5056.3
Exp/Cntr=0.3,0.1

Chan Stop Cuts=-1