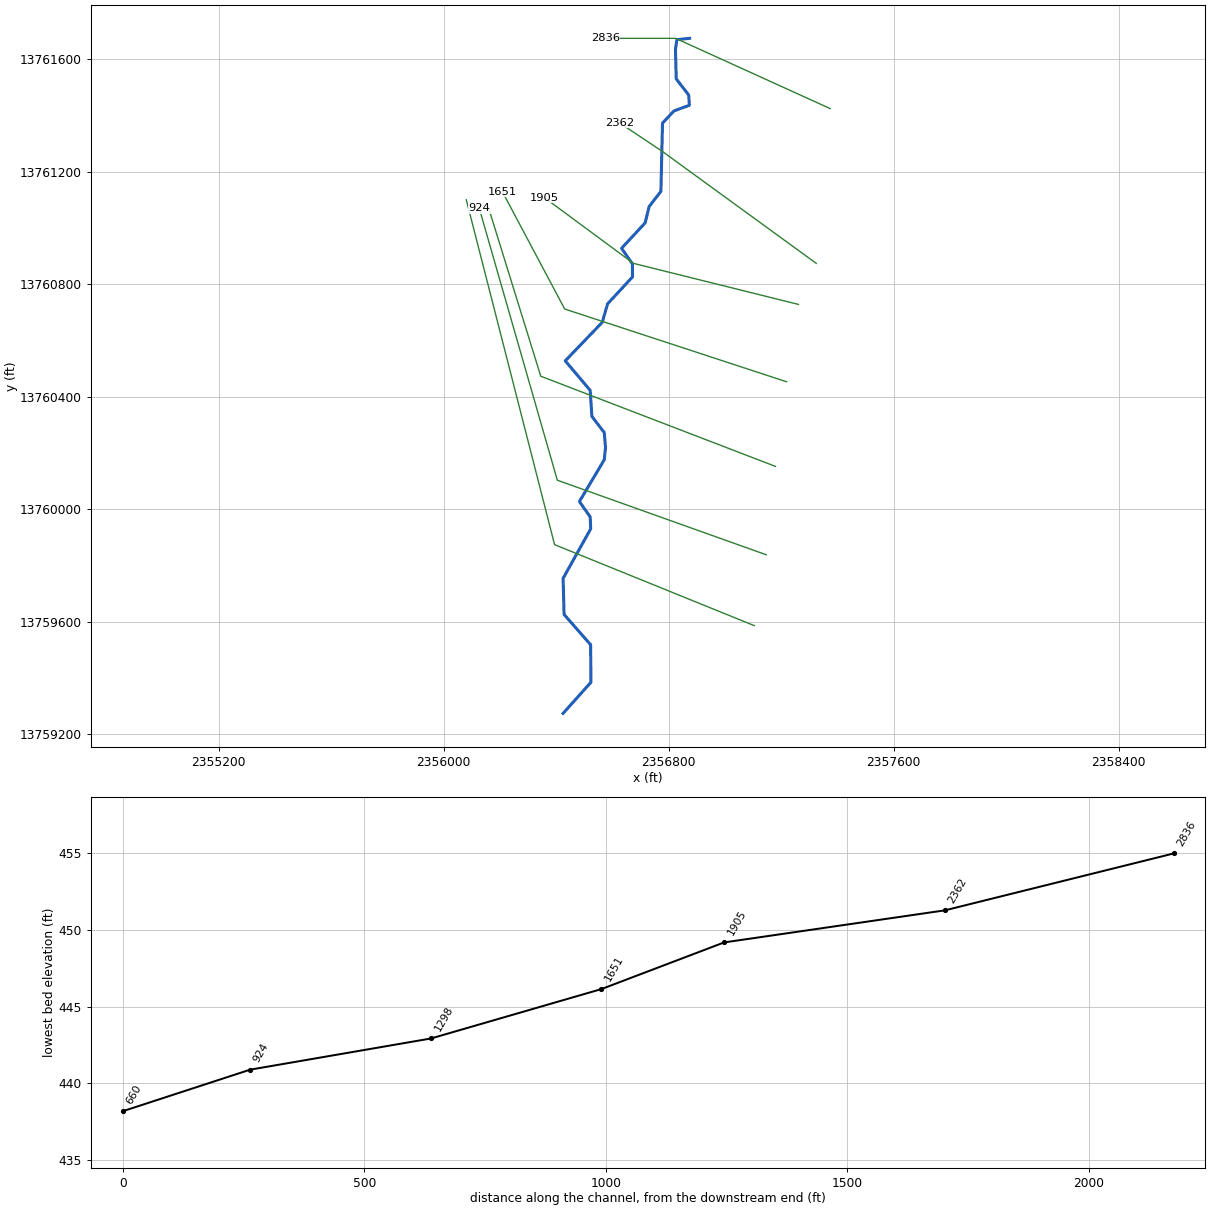
--- DARST TRIBUTARY 5.prj (project) ---

Proj Title=DARST TRIBUTARY 5 Base Level Engineering
Current Plan=p01
Default Exp/Contr=0.3,0.1
English Units
Geom File=g01
Flow File=f01
Plan File=p01
BEGIN DESCRIPTION:
DARST TRIBUTARY 5
END DESCRIPTION:

--- DARST TRIBUTARY 5.p01 (plan) ---

Plan Title=Multiple Run
Short Identifier=Multiple
Geom File=g01
Flow File=f01
Subcritical Flow
K Sum by GR= 0
Std Step Tol= 0.01
Critical Tol= 0.01
Num of Std Step Trials= 20
Max Error Tol= 0.3
Flow Tol Ratio= 0.001
Split Flow NTrial= 30
Split Flow Tol= 0.02
Split Flow Ratio= 0.02
Log Output Level= 0
Friction Slope Method= 1
Unsteady Friction Slope Method= 2
Unsteady Bridges Friction Slope Method= 1
Parabolic Critical Depth
Global Vel Dist=  1 , 1 , 1
Global Log Level= 0
CheckData=True
Encroach Param= -1, 0, 0, 0
BEGIN DESCRIPTION:
Multiple Run
END DESCRIPTION:

--- DARST TRIBUTARY 5.f01 (steady flow) ---

Flow Title=Multiple
Number of Profiles=7
Profile Names=10-year,25-year,50-year,1pct_min,100-year,1pct_plu,500-year
River Rch & RM= DARST TRIBUTARY ,Reach-1,2836
     616    1005    1361     894    1784    3559    3033
Boundary for River Rch & Prof#=DARST TRIBUTARY ,Reach-1,1
Up Type=0
Dn Type=3
Dn Slope=0.005
Boundary for River Rch & Prof#=DARST TRIBUTARY ,Reach-1,2
Up Type=0
Dn Type=3
Dn Slope=0.005
Boundary for River Rch & Prof#=DARST TRIBUTARY ,Reach-1,3
Up Type=0
Dn Type=3
Dn Slope=0.005
Boundary for River Rch & Prof#=DARST TRIBUTARY ,Reach-1,4
Up Type=0
Dn Type=3
Dn Slope=0.005
Boundary for River Rch & Prof#=DARST TRIBUTARY ,Reach-1,5
Up Type=0
Dn Type=3
Dn Slope=0.005
Boundary for River Rch & Prof#=DARST TRIBUTARY ,Reach-1,6
Up Type=0
Dn Type=3
Dn Slope=0.005
Boundary for River Rch & Prof#=DARST TRIBUTARY ,Reach-1,7
Up Type=0
Dn Type=3
Dn Slope=0.005

--- DARST TRIBUTARY 5.g01 (geometry) ---

Geom Title=Existing Conditions

River Reach=DARST TRIBUTARY ,Reach-1
Reach XY= 30
      2356875.00     13761675.00      2356829.62     13761670.37
      2356824.49     13761635.43      2356827.28     13761530.91
      2356871.81     13761472.89      2356873.81     13761437.02
      2356819.02     13761416.85      2356778.48     13761373.74
      2356772.76     13761130.93      2356731.14     13761077.17
      2356716.82     13761018.94      2356632.83     13760928.40
      2356671.41     13760873.35      2356671.83     13760826.65
      2356583.18     13760731.04      2356564.22     13760665.32
      2356432.60     13760528.34      2356521.36     13760423.50
      2356527.36     13760330.98      2356571.30     13760273.40
      2356575.81     13760219.97      2356571.32     13760176.58
      2356483.07     13760028.31      2356521.40     13759973.36
      2356523.16     13759931.12      2356425.04     13759754.97
      2356428.54     13759626.47      2356522.94     13759519.14
      2356523.99     13759385.43      2356425.00     13759275.00

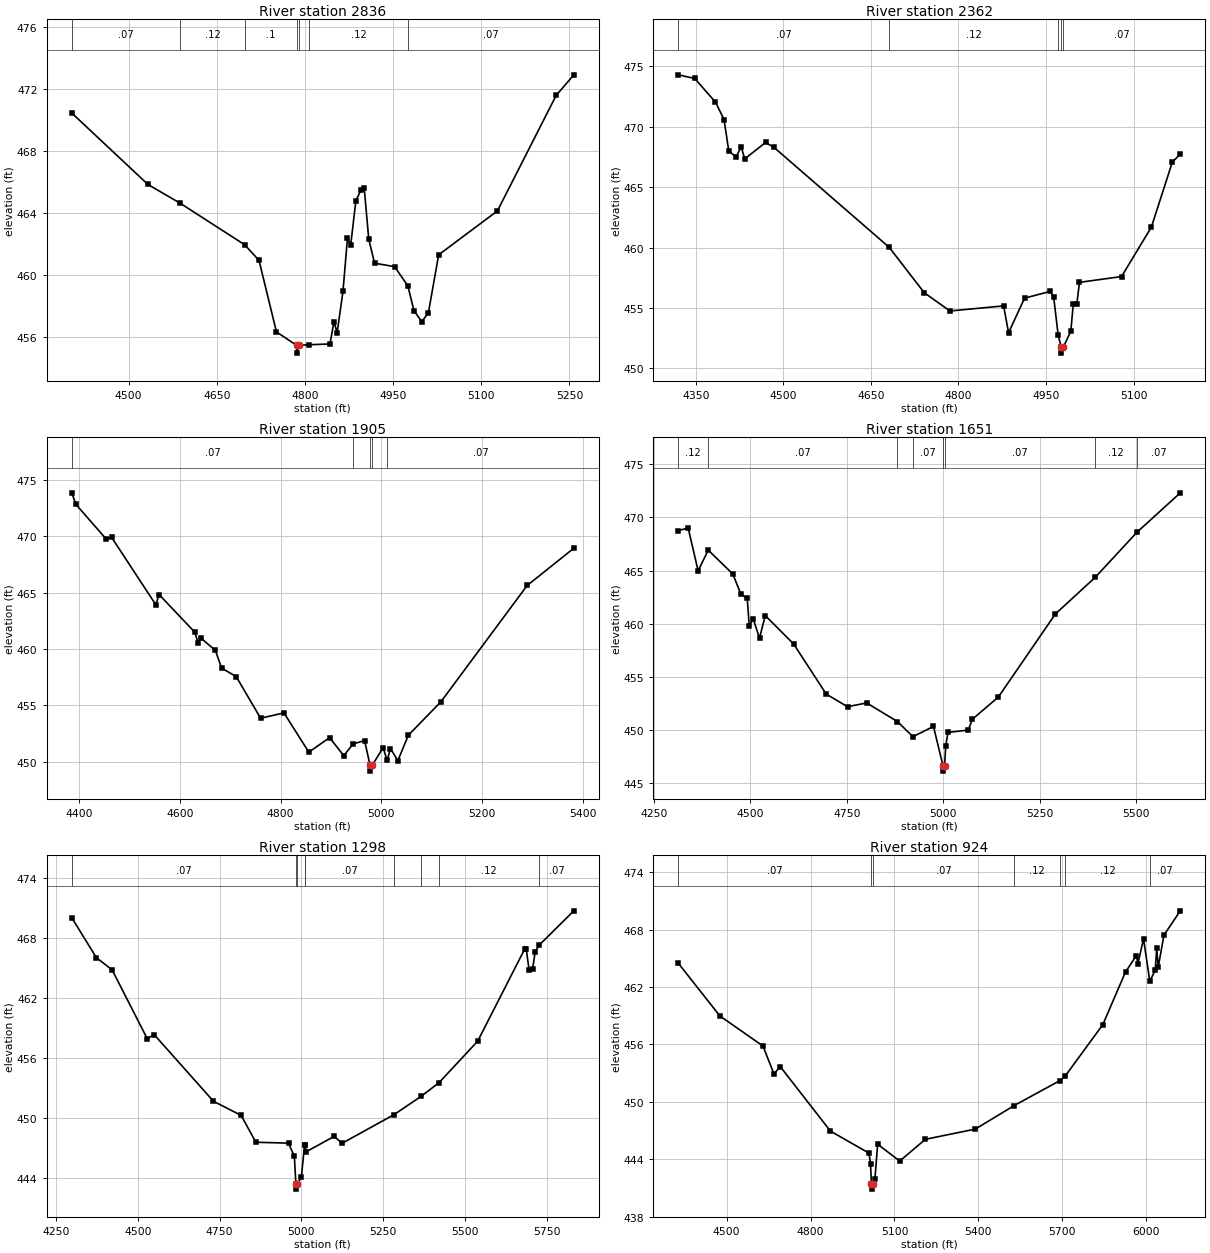
Type RM Length L Ch R = 1,2836,474,474,474
BEGIN DESCRIPTION:
DARST TRIBUTARY 5 3.0
END DESCRIPTION:
XS GIS Cut Line= 3
      2357375.01     13761424.99      2356825.00     13761675.00
      2356574.97     13761675.00
#Sta/Elev= 30
  4403.3  470.44  4532.9  465.84  4587.8  464.63  4697.4  461.96  4721.9  460.95
  4751.5  456.35  4785.8  455.48  4786.0  454.98  4789.8  455.48  4807.1  455.52
  4842.7  455.57  4849.3  457.01  4854.8  456.30  4864.7  458.95  4872.4  462.41
  4877.8  461.92  4886.6  464.78  4895.4  465.50  4900.9  465.59  4908.6  462.31
  4918.5  460.77  4952.5  460.55  4975.1  459.31  4985.5  457.71  4998.7  457.01
  5010.0  457.57  5027.5  461.31  5127.5  464.14  5227.5  471.58  5257.5  472.90
#Mann=7,-1,0
  4403.3    0.07       0  4587.8    0.12       0  4697.4     0.1       0
  4785.8    0.05       0  4789.8     0.1       0  4807.1    0.12       0
  4975.1    0.07       0
Bank Sta=4785.8,4789.8
Exp/Cntr=0.3,0.1

Type RM Length L Ch R = 1,2362,457,457,457
BEGIN DESCRIPTION:
DARST TRIBUTARY 5 2.0
END DESCRIPTION:
XS GIS Cut Line= 3
      2357325.02     13760874.99      2356775.00     13761275.00
      2356624.98     13761375.01
#Sta/Elev= 30
  4319.8  474.31  4348.0  474.01  4383.6  472.05  4398.3  470.61  4406.4  468.00
  4419.1  467.51  4427.6  468.36  4433.8  467.35  4469.4  468.71  4484.0  468.30
  4681.3  460.03  4741.4  456.27  4785.4  454.76  4877.4  455.18  4885.9  452.96
  4913.3  455.82  4957.0  456.38  4963.2  455.90  4970.8  452.80  4975.9  451.77
  4976.1  451.27  4979.9  451.77  4992.6  453.09  4996.8  455.35  5002.9  455.35
  5007.4  457.13  5079.5  457.61  5130.6  461.70  5166.7  467.11  5180.2  467.73
#Mann=5,-1,0
  4319.8    0.07       0  4681.3    0.12       0  4970.8    0.07       0
  4975.9    0.05       0  4979.9    0.07       0
Bank Sta=4975.9,4979.9
Exp/Cntr=0.3,0.1

Type RM Length L Ch R = 1,1905,254,254,254
BEGIN DESCRIPTION:
DARST TRIBUTARY 5 1.0
END DESCRIPTION:
XS GIS Cut Line= 3
      2357261.88     13760728.97      2356675.00     13760875.00
      2356359.41     13761108.06
#Sta/Elev= 30
  4385.2  473.84  4393.5  472.81  4454.1  469.72  4464.4  469.89  4552.0  463.93
  4558.7  464.82  4629.3  461.50  4636.2  460.54  4641.4  460.98  4670.5  459.87
  4682.7  458.31  4711.7  457.56  4760.2  453.87  4806.6  454.34  4856.0  450.86
  4897.2  452.15  4925.4  450.55  4943.9  451.59  4966.7  451.89  4977.7  449.68
  4977.9  449.18  4981.7  449.68  5003.5  451.26  5011.5  450.13  5018.1  451.18
  5032.8  450.11  5053.6  452.36  5118.4  455.33  5289.6  465.63  5382.3  468.93
#Mann=5,-1,0
  4385.2    0.07       0  4943.9    0.12       0  4977.7    0.05       0
  4981.7    0.12       0  5011.5    0.07       0
Bank Sta=4977.7,4981.7
Exp/Cntr=0.3,0.1

Type RM Length L Ch R = 1,1651,353,353,353
BEGIN DESCRIPTION:
X18759
END DESCRIPTION:
XS GIS Cut Line= 3
      2357219.38     13760454.08      2356430.74     13760712.60
      2356209.50     13761129.05
#Sta/Elev= 30
  4312.7  468.75  4338.4  469.01  4364.2  464.98  4390.5  466.92  4454.1  464.68
  4475.2  462.78  4491.6  462.38  4496.8  459.76  4506.7  460.49  4523.4  458.65
  4538.3  460.77  4612.0  458.09  4696.2  453.39  4751.5  452.20  4801.4  452.55
  4880.9  450.80  4921.1  449.38  4974.4  450.34  4999.0  446.64  4999.2  446.14
  5003.0  446.64  5006.2  448.53  5011.9  449.78  5064.5  450.00  5075.2  451.02
  5142.6  453.11  5290.2  460.91  5393.8  464.37  5501.5  468.59  5614.2  472.31
#Mann=8,-1,0
  4312.7    0.12       0  4390.5    0.07       0  4880.9    0.12       0
  4921.1    0.07       0  4999.0    0.05       0  5003.0    0.07       0
  5393.8    0.12       0  5501.5    0.07       0
Bank Sta=4999,5003
Exp/Cntr=0.3,0.1

Type RM Length L Ch R = 1,1298,374,374,374
BEGIN DESCRIPTION:
X18758
END DESCRIPTION:
XS GIS Cut Line= 3
      2357180.14     13760153.01      2356345.66     13760473.72
      2356155.86     13761085.67
#Sta/Elev= 30
  4298.0  470.01  4373.2  466.03  4421.4  464.80  4528.5  457.95  4549.9  458.34
  4731.1  451.69  4815.8  450.28  4860.6  447.60  4960.5  447.51  4978.4  446.18
  4983.1  443.42  4983.4  442.92  4987.1  443.42  4999.9  444.14  5009.5  447.31
  5010.4  447.33  5015.2  446.66  5099.8  448.18  5124.5  447.50  5283.3  450.36
  5366.2  452.19  5420.4  453.54  5538.8  457.69  5681.9  466.85  5687.2  466.90
  5695.9  464.79  5706.4  464.86  5714.5  466.61  5726.8  467.28  5832.7  470.70
#Mann=9,-1,0
  4298.0    0.07       0  4983.1    0.05       0  4987.1    0.07       0
  5009.5    0.12       0  5010.4    0.07       0  5283.3    0.12       0
  5366.2    0.07       0  5420.4    0.12       0  5726.8    0.07       0
Bank Sta=4983.1,4987.1
Exp/Cntr=0.3,0.1

Type RM Length L Ch R = 1,924,264,264,264
BEGIN DESCRIPTION:
X18757
END DESCRIPTION:
XS GIS Cut Line= 3
      2357147.39     13759838.88      2356404.56     13760103.94
      2356126.79     13761071.25
#Sta/Elev= 30
  4326.8  464.49  4475.8  458.97  4629.8  455.83  4669.1  452.91  4691.4  453.69
  4870.9  446.95  5008.9  444.65  5014.3  443.55  5017.6  441.39  5017.9  440.89
  5021.6  441.39  5030.1  441.99  5039.8  445.58  5118.6  443.82  5210.2  446.09
  5389.0  447.16  5528.1  449.62  5691.3  452.22  5710.6  452.71  5844.9  458.07
  5926.0  463.57  5964.9  465.27  5970.1  464.42  5990.5  467.03  6012.8  462.58
  6032.2  463.77  6037.6  466.05  6042.8  464.06  6063.4  467.41  6121.9  469.95
#Mann=7,-1,0
  4326.8    0.07       0  5017.6    0.05       0  5021.6    0.07       0
  5528.1    0.12       0  5691.3    0.07       0  5710.6    0.12       0
  6012.8    0.07       0
Bank Sta=5017.6,5021.6
Exp/Cntr=0.3,0.1

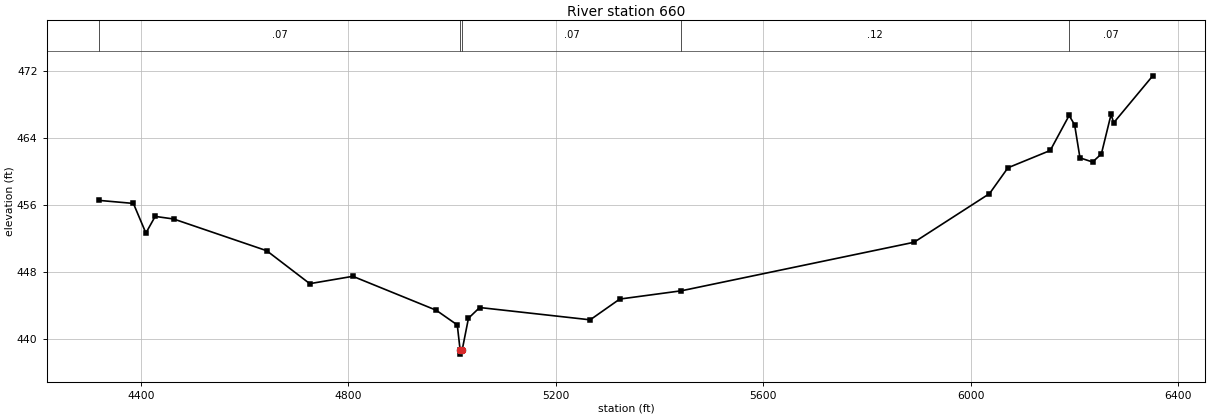
Type RM Length L Ch R = 1,660,0,0,0
BEGIN DESCRIPTION:
X18760
END DESCRIPTION:
XS GIS Cut Line= 3
      2357104.80     13759586.93      2356394.74     13759874.88
      2356080.85     13761101.02
#Sta/Elev= 30
  4319.6  456.55  4385.3  456.19  4409.4  452.65  4427.3  454.64  4462.9  454.33
  4642.4  450.54  4725.5  446.60  4808.6  447.48  4969.3  443.43  5010.0  441.67
  5015.5  438.68  5015.8  438.18  5019.5  438.68  5031.6  442.47  5053.2  443.75
  5266.4  442.28  5323.4  444.76  5442.3  445.75  5891.1  451.55  6036.6  457.36
  6072.2  460.45  6153.8  462.52  6190.2  466.70  6200.8  465.59  6211.1  461.64
  6235.4  461.14  6252.4  462.10  6271.1  466.83  6276.2  465.83  6351.5  471.44
#Mann=5,-1,0
  4319.6    0.07       0  5015.5    0.05       0  5019.5    0.07       0
  5442.3    0.12       0  6190.2    0.07       0
Bank Sta=5015.5,5019.5
Exp/Cntr=0.3,0.1

Chan Stop Cuts=-1