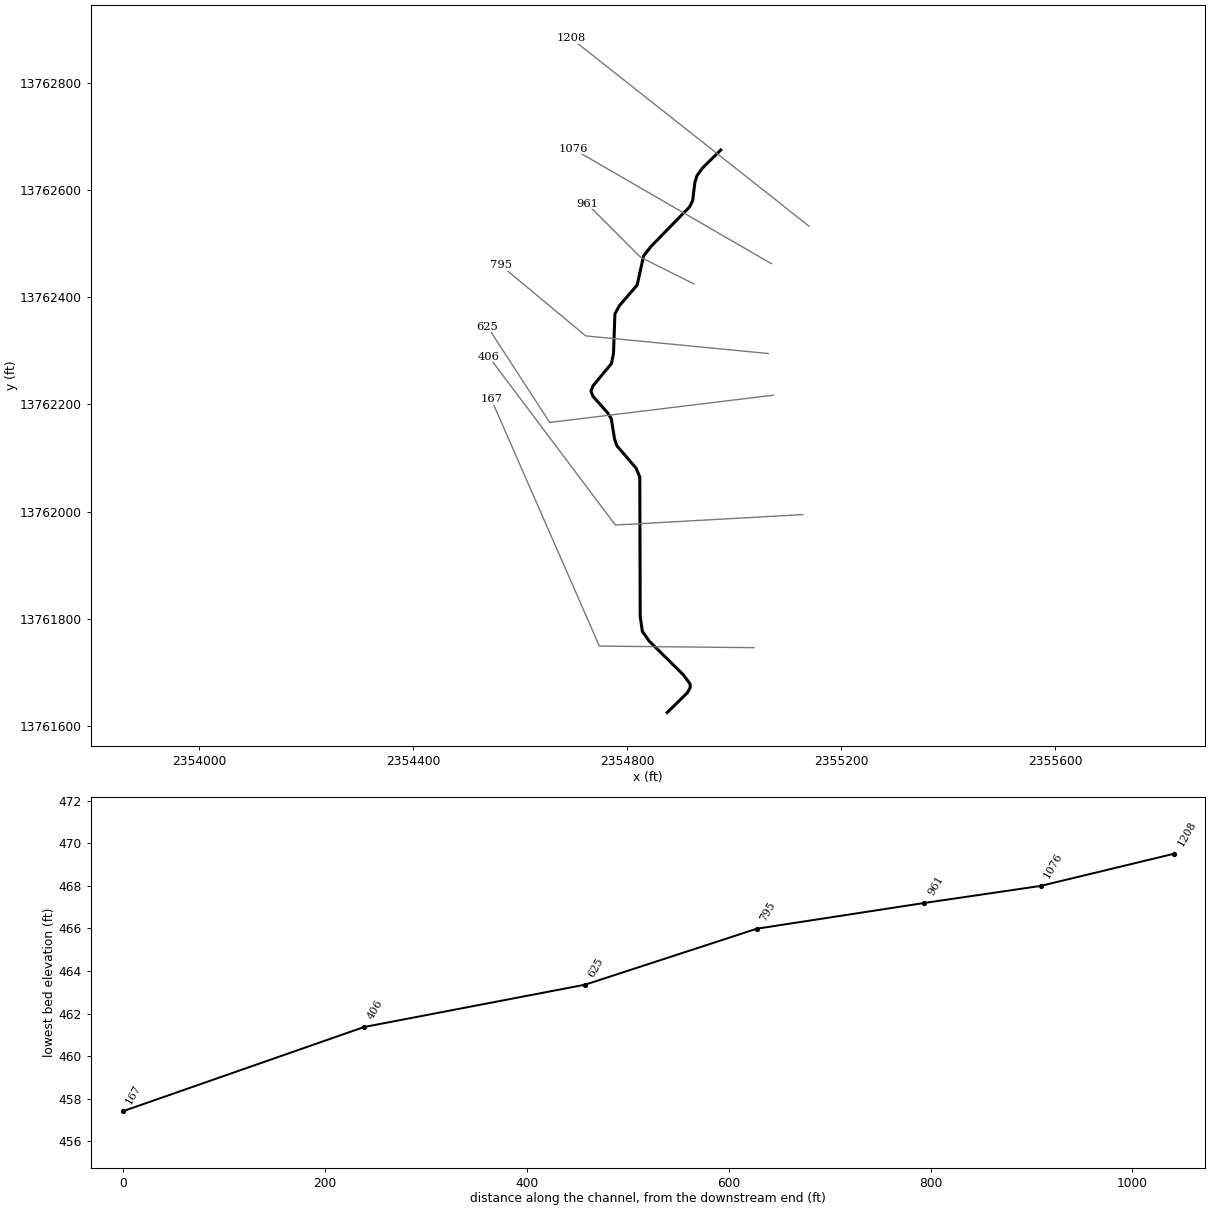
--- DARST TRIBUTARY 5B.prj (project) ---

Proj Title=DARST TRIBUTARY 5B Base Level Engineering
Current Plan=p01
Default Exp/Contr=0.3,0.1
English Units
Geom File=g01
Flow File=f01
Plan File=p01
BEGIN DESCRIPTION:
DARST TRIBUTARY 5B
END DESCRIPTION:

--- DARST TRIBUTARY 5B.p01 (plan) ---

Plan Title=Multiple Run
Short Identifier=Multiple
Geom File=g01
Flow File=f01
Subcritical Flow
K Sum by GR= 0
Std Step Tol= 0.01
Critical Tol= 0.01
Num of Std Step Trials= 20
Max Error Tol= 0.3
Flow Tol Ratio= 0.001
Split Flow NTrial= 30
Split Flow Tol= 0.02
Split Flow Ratio= 0.02
Log Output Level= 0
Friction Slope Method= 1
Unsteady Friction Slope Method= 2
Unsteady Bridges Friction Slope Method= 1
Parabolic Critical Depth
Global Vel Dist=  1 , 1 , 1
Global Log Level= 0
CheckData=True
Encroach Param= -1, 0, 0, 0
BEGIN DESCRIPTION:
Multiple Run
END DESCRIPTION:

--- DARST TRIBUTARY 5B.f01 (steady flow) ---

Flow Title=Multiple
Number of Profiles=7
Profile Names=10-year,25-year,50-year,1pct_min,100-year,1pct_plu,500-year
River Rch & RM= DARST TRIBUTARY ,Reach-1,1208
     188     284     364     228     456     909     703
Boundary for River Rch & Prof#=DARST TRIBUTARY ,Reach-1,1
Up Type=0
Dn Type=3
Dn Slope=0.005
Boundary for River Rch & Prof#=DARST TRIBUTARY ,Reach-1,2
Up Type=0
Dn Type=3
Dn Slope=0.005
Boundary for River Rch & Prof#=DARST TRIBUTARY ,Reach-1,3
Up Type=0
Dn Type=3
Dn Slope=0.005
Boundary for River Rch & Prof#=DARST TRIBUTARY ,Reach-1,4
Up Type=0
Dn Type=3
Dn Slope=0.005
Boundary for River Rch & Prof#=DARST TRIBUTARY ,Reach-1,5
Up Type=0
Dn Type=3
Dn Slope=0.005
Boundary for River Rch & Prof#=DARST TRIBUTARY ,Reach-1,6
Up Type=0
Dn Type=3
Dn Slope=0.005
Boundary for River Rch & Prof#=DARST TRIBUTARY ,Reach-1,7
Up Type=0
Dn Type=3
Dn Slope=0.005

--- DARST TRIBUTARY 5B.g01 (geometry) ---

Geom Title=Existing Conditions

River Reach=DARST TRIBUTARY ,Reach-1
Reach XY= 30
      2354975.00     13762675.00      2354941.42     13762641.92
      2354930.70     13762627.35      2354926.65     13762614.32
      2354922.65     13762580.97      2354916.93     13762568.92
      2354844.82     13762495.07      2354830.84     13762477.29
      2354818.86     13762422.83      2354785.83     13762384.65
      2354777.33     13762369.03      2354774.65     13762295.05
      2354770.91     13762276.50      2354736.45     13762234.90
      2354732.53     13762224.99      2354736.42     13762215.07
      2354763.50     13762184.67      2354770.58     13762173.36
      2354776.62     13762135.71      2354781.09     13762122.83
      2354816.90     13762081.08      2354823.80     13762064.50
      2354824.57     13761804.82      2354828.55     13761776.46
      2354841.48     13761758.23      2354905.60     13761694.98
      2354917.73     13761678.33      2354918.04     13761671.66
      2354912.49     13761661.66      2354875.00     13761625.00

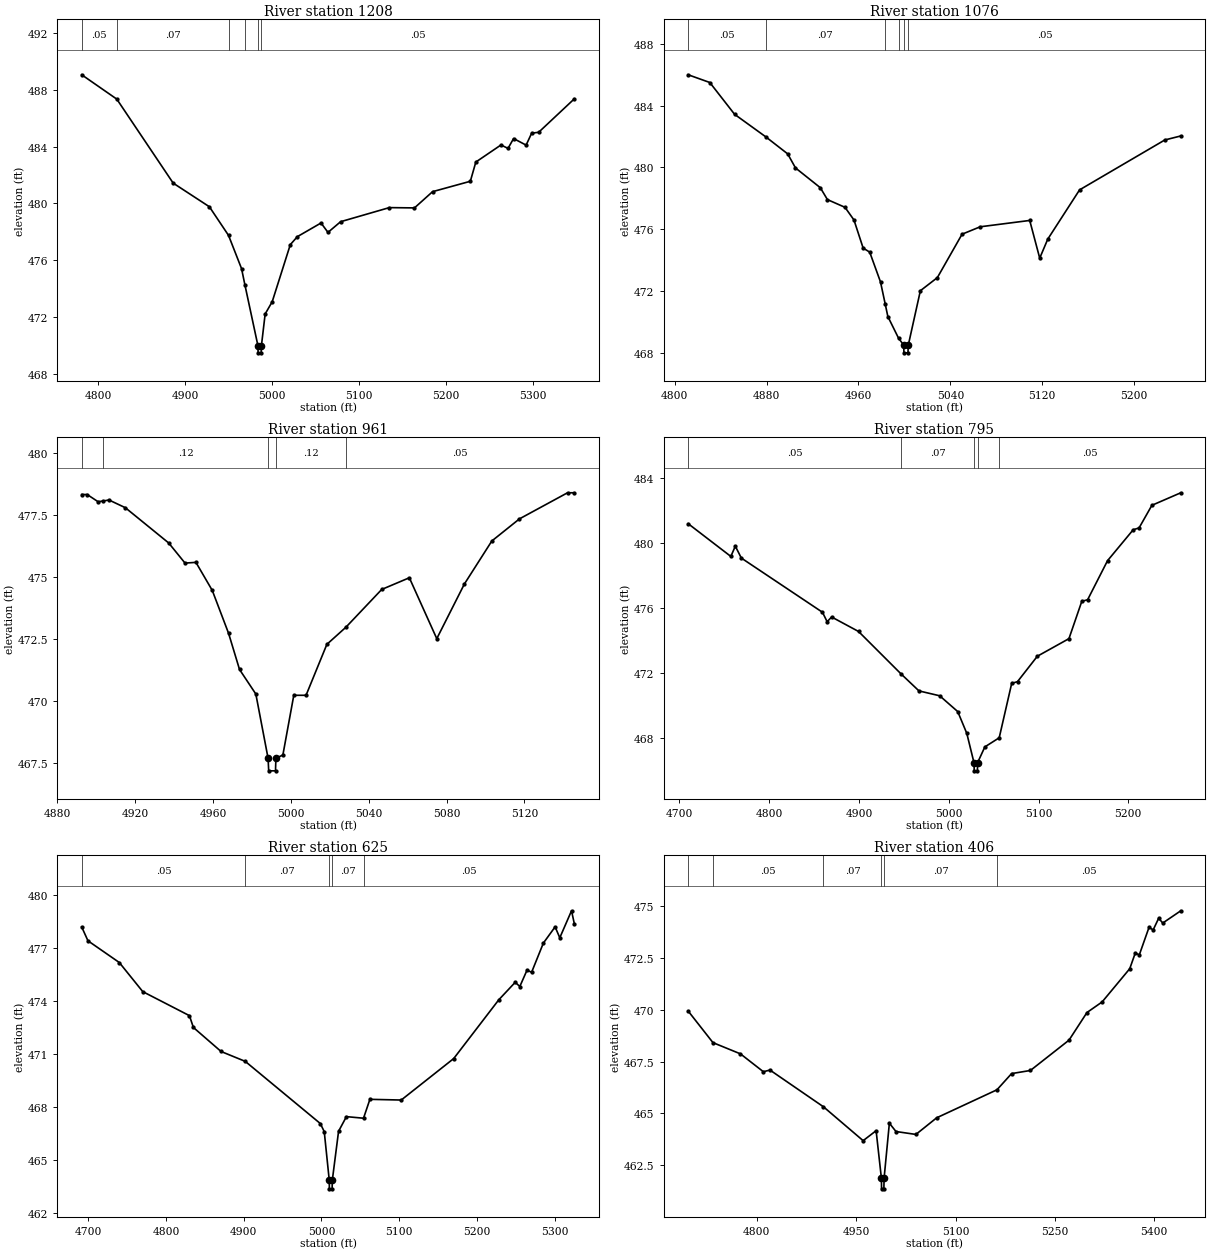
Type RM Length L Ch R = 1,1208,132,132,132
BEGIN DESCRIPTION:
DARST TRIBUTARY 5B10503
END DESCRIPTION:
XS GIS Cut Line= 2
      2355139.92     13762532.87      2354695.51     13762883.54
#Sta/Elev= 30
  4781.2  489.04  4821.5  487.33  4886.3  481.43  4927.9  479.77  4949.9  477.76
  4964.9  475.42  4968.7  474.29  4983.7  470.01  4983.9  469.51  4987.4  469.51
  4987.7  470.01  4992.0  472.24  5000.1  473.10  5020.9  477.11  5029.0  477.67
  5056.2  478.63  5064.2  477.97  5078.7  478.72  5134.7  479.71  5163.6  479.69
  5184.4  480.83  5227.8  481.56  5234.1  482.91  5263.0  484.11  5271.1  483.87
  5277.5  484.56  5291.9  484.10  5298.3  484.94  5306.3  485.00  5347.3  487.35
#Mann=6,-1,0
  4781.2    0.05       0  4821.5    0.07       0  4949.9    0.12       0
  4968.7    0.05       0  4983.7    0.05       0  4987.7    0.05       0
Bank Sta=4983.7,4987.7
Exp/Cntr=0.3,0.1

Type RM Length L Ch R = 1,1076,115,115,115
BEGIN DESCRIPTION:
DARST TRIBUTARY 5B10502
END DESCRIPTION:
XS GIS Cut Line= 2
      2355069.93     13762462.69      2354698.73     13762677.35
#Sta/Elev= 30
  4811.8  486.00  4830.6  485.50  4852.2  483.44  4879.2  481.99  4898.4  480.88
  4905.2  479.97  4926.8  478.69  4933.0  477.92  4948.3  477.42  4956.1  476.60
  4964.1  474.78  4969.8  474.52  4979.2  472.59  4983.3  471.16  4985.6  470.35
  4994.9  468.95  4999.4  468.50  4999.6  468.00  5003.1  468.00  5003.4  468.50
  5013.9  472.02  5028.7  472.87  5050.2  475.68  5066.0  476.16  5109.1  476.57
  5117.8  474.13  5124.8  475.36  5152.5  478.55  5226.7  481.78  5240.6  482.04
#Mann=6,-1,0
  4811.8    0.05       0  4879.2    0.07       0  4983.3    0.12       0
  4994.9    0.05       0  4999.4    0.05       0  5003.4    0.05       0
Bank Sta=4999.4,5003.4
Exp/Cntr=0.3,0.1

Type RM Length L Ch R = 1,961,166,166,166
BEGIN DESCRIPTION:
DARST TRIBUTARY 5B3018
END DESCRIPTION:
XS GIS Cut Line= 3
      2354925.01     13762425.00      2354825.00     13762475.00
      2354725.03     13762574.97
#Sta/Elev= 30
  4892.5  478.32  4895.3  478.32  4900.9  478.03  4903.6  478.06  4906.5  478.10
  4914.9  477.79  4937.2  476.37  4945.6  475.56  4951.2  475.59  4959.6  474.46
  4968.0  472.73  4973.6  471.28  4982.0  470.29  4988.3  467.70  4988.6  467.20
  4992.1  467.20  4992.3  467.70  4995.9  467.84  5001.5  470.24  5007.8  470.24
  5018.5  472.29  5028.3  472.98  5046.7  474.50  5060.9  474.97  5075.0  472.52
  5089.2  474.72  5103.3  476.45  5117.5  477.34  5142.2  478.39  5145.7  478.39
#Mann=5,-1,0
  4892.5    0.05       0  4903.6    0.12       0  4988.3    0.05       0
  4992.3    0.12       0  5028.3    0.05       0
Bank Sta=4988.3,4992.3
Exp/Cntr=0.3,0.1

Type RM Length L Ch R = 1,795,170,170,170
BEGIN DESCRIPTION:
DARST TRIBUTARY 5B10501
END DESCRIPTION:
XS GIS Cut Line= 3
      2355063.93     13762295.12      2354722.83     13762328.04
      2354564.25     13762459.69
#Sta/Elev= 30
  4709.7  481.17  4757.2  479.16  4762.2  479.79  4768.9  479.06  4859.3  475.73
  4864.5  475.15  4869.5  475.44  4899.5  474.55  4946.9  471.94  4966.8  470.90
  4989.9  470.60  5010.0  469.63  5020.1  468.29  5028.1  466.49  5028.4  465.99
  5031.9  465.99  5032.1  466.49  5040.2  467.46  5056.2  468.02  5070.1  471.36
  5076.6  471.47  5098.7  473.03  5133.9  474.11  5148.2  476.40  5154.7  476.50
  5176.9  478.90  5205.5  480.80  5212.0  480.91  5226.3  482.30  5258.5  483.07
#Mann=5,-1,0
  4709.7    0.05       0  4946.9    0.07       0  5028.1    0.05       0
  5032.1    0.07       0  5056.2    0.05       0
Bank Sta=5028.1,5032.1
Exp/Cntr=0.3,0.1

Type RM Length L Ch R = 1,625,219,219,219
BEGIN DESCRIPTION:
DARST TRIBUTARY 5B10500
END DESCRIPTION:
XS GIS Cut Line= 3
      2355072.90     13762217.32      2354655.51     13762166.46
      2354539.42     13762345.06
#Sta/Elev= 30
  4691.7  478.19  4699.7  477.41  4740.0  476.18  4770.2  474.53  4830.2  473.17
  4835.3  472.50  4870.9  471.14  4902.0  470.58  4998.5  467.06  5003.6  466.60
  5010.0  463.86  5010.2  463.36  5013.7  463.36  5014.0  463.86  5022.0  466.62
  5032.1  467.45  5054.1  467.36  5062.3  468.43  5102.6  468.39  5170.1  470.74
  5228.1  474.07  5249.2  475.06  5255.1  474.82  5264.3  475.74  5270.3  475.63
  5285.4  477.28  5300.5  478.20  5306.5  477.58  5321.6  479.11  5325.2  478.38
#Mann=5,-1,0
  4691.7    0.05       0  4902.0    0.07       0  5010.0    0.05       0
  5014.0    0.07       0  5054.1    0.05       0
Bank Sta=5010,5014
Exp/Cntr=0.3,0.1

Type RM Length L Ch R = 1,406,239,239,239
BEGIN DESCRIPTION:
DARST TRIBUTARY 5B10499
END DESCRIPTION:
XS GIS Cut Line= 3
      2355128.32     13761994.41      2354778.19     13761974.95
      2354541.77     13762289.18
#Sta/Elev= 30
  4696.3  469.93  4733.7  468.41  4775.2  467.87  4809.8  467.01  4819.8  467.09
  4900.6  465.32  4960.5  463.69  4980.1  464.17  4988.1  461.87  4988.3  461.37
  4991.8  461.37  4992.1  461.87  5000.1  464.53  5010.1  464.13  5040.2  463.99
  5071.5  464.79  5162.6  466.14  5184.7  466.92  5213.1  467.07  5271.4  468.53
  5298.5  469.86  5321.4  470.37  5363.1  471.97  5371.4  472.72  5377.6  472.64
  5392.2  473.96  5398.5  473.84  5406.8  474.40  5413.0  474.17  5440.2  474.76
#Mann=6,-1,0
  4696.3    0.07       0  4733.7    0.05       0  4900.6    0.07       0
  4988.1    0.05       0  4992.1    0.07       0  5162.6    0.05       0
Bank Sta=4988.1,4992.1
Exp/Cntr=0.3,0.1

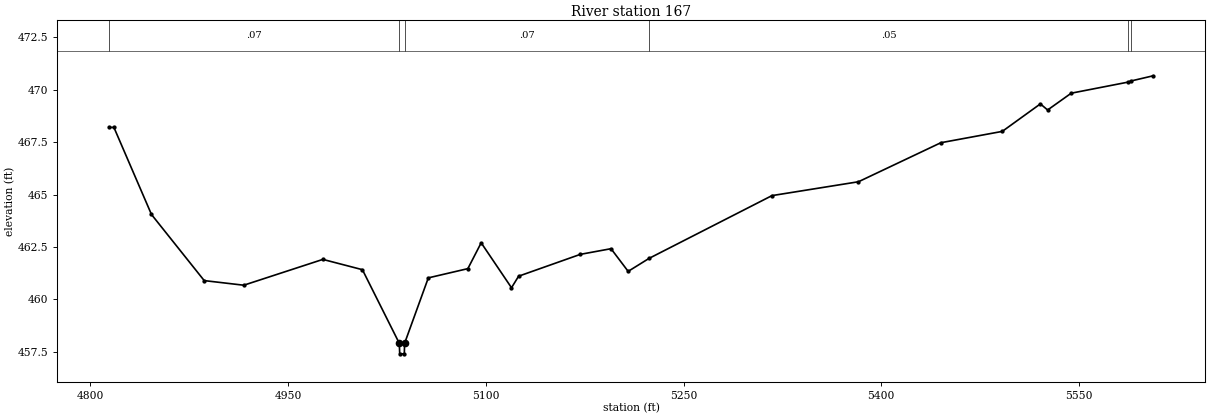
Type RM Length L Ch R = 1,167,0,0,0
BEGIN DESCRIPTION:
DARST TRIBUTARY 5B10498
END DESCRIPTION:
XS GIS Cut Line= 3
      2355037.04     13761746.05      2354748.26     13761749.04
      2354546.29     13762209.83
#Sta/Elev= 30
  4814.4  468.20  4817.9  468.20  4846.4  464.05  4886.4  460.90  4916.4  460.68
  4976.4  461.91  5006.4  461.42  5034.4  457.91  5034.7  457.41  5038.2  457.41
  5038.4  457.91  5056.4  461.03  5086.4  461.47  5096.5  462.70  5119.5  460.56
  5124.9  461.11  5171.7  462.15  5195.0  462.42  5208.0  461.34  5223.9  461.96
  5317.1  464.95  5382.7  465.61  5445.2  467.47  5491.8  468.01  5520.7  469.32
  5526.2  469.03  5544.1  469.83  5587.4  470.36  5589.3  470.41  5606.3  470.66
#Mann=6,-1,0
  4814.4    0.07       0  5034.4    0.05       0  5038.4    0.07       0
  5223.9    0.05       0  5587.4    0.07       0  5589.3    0.05       0
Bank Sta=5034.4,5038.4
Exp/Cntr=0.3,0.1

Chan Stop Cuts=-1