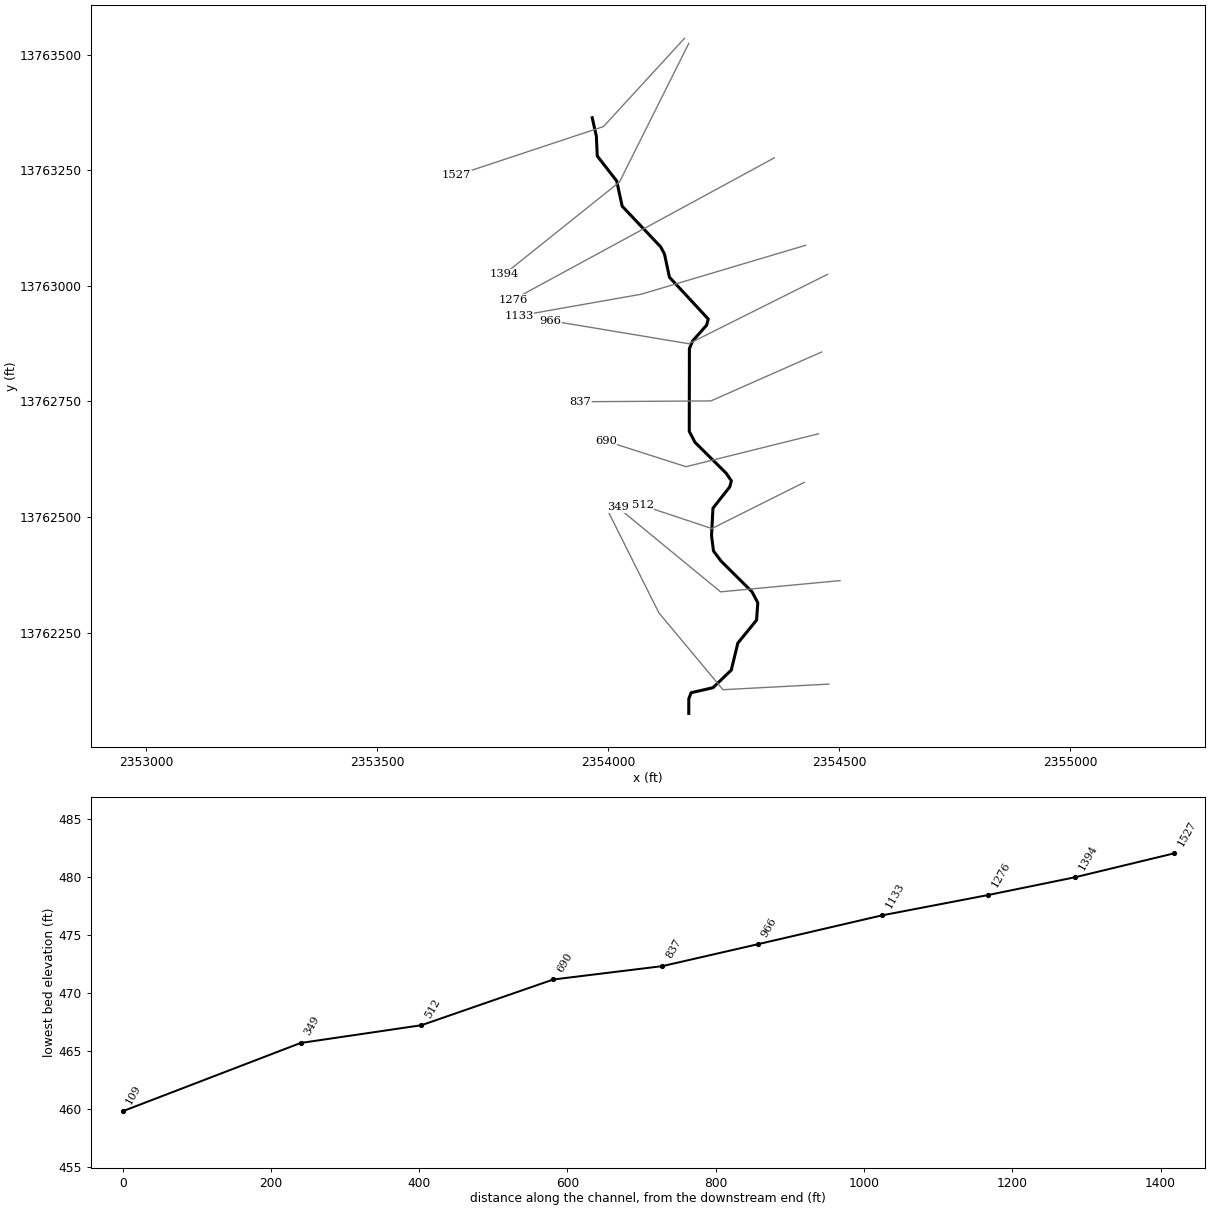
--- DARST TRIBUTARY 5C.prj (project) ---

Proj Title=DARST TRIBUTARY 5C Base Level Engineering
Current Plan=p01
Default Exp/Contr=0.3,0.1
English Units
Geom File=g01
Flow File=f01
Plan File=p01
BEGIN DESCRIPTION:
DARST TRIBUTARY 5C
END DESCRIPTION:

--- DARST TRIBUTARY 5C.p01 (plan) ---

Plan Title=Multiple Run
Short Identifier=Multiple
Geom File=g01
Flow File=f01
Subcritical Flow
K Sum by GR= 0
Std Step Tol= 0.01
Critical Tol= 0.01
Num of Std Step Trials= 20
Max Error Tol= 0.3
Flow Tol Ratio= 0.001
Split Flow NTrial= 30
Split Flow Tol= 0.02
Split Flow Ratio= 0.02
Log Output Level= 0
Friction Slope Method= 1
Unsteady Friction Slope Method= 2
Unsteady Bridges Friction Slope Method= 1
Parabolic Critical Depth
Global Vel Dist=  1 , 1 , 1
Global Log Level= 0
CheckData=True
Encroach Param= -1, 0, 0, 0
BEGIN DESCRIPTION:
Multiple Run
END DESCRIPTION:

--- DARST TRIBUTARY 5C.f01 (steady flow) ---

Flow Title=Multiple
Number of Profiles=7
Profile Names=10-year,25-year,50-year,1pct_min,100-year,1pct_plu,500-year
River Rch & RM= DARST TRIBUTARY ,Reach-1,1527
     262     404     527     335     669    1334    1061
Boundary for River Rch & Prof#=DARST TRIBUTARY ,Reach-1,1
Up Type=0
Dn Type=3
Dn Slope=0.005
Boundary for River Rch & Prof#=DARST TRIBUTARY ,Reach-1,2
Up Type=0
Dn Type=3
Dn Slope=0.005
Boundary for River Rch & Prof#=DARST TRIBUTARY ,Reach-1,3
Up Type=0
Dn Type=3
Dn Slope=0.005
Boundary for River Rch & Prof#=DARST TRIBUTARY ,Reach-1,4
Up Type=0
Dn Type=3
Dn Slope=0.005
Boundary for River Rch & Prof#=DARST TRIBUTARY ,Reach-1,5
Up Type=0
Dn Type=3
Dn Slope=0.005
Boundary for River Rch & Prof#=DARST TRIBUTARY ,Reach-1,6
Up Type=0
Dn Type=3
Dn Slope=0.005
Boundary for River Rch & Prof#=DARST TRIBUTARY ,Reach-1,7
Up Type=0
Dn Type=3
Dn Slope=0.005

--- DARST TRIBUTARY 5C.g01 (geometry) ---

Geom Title=Existing Conditions

River Reach=DARST TRIBUTARY ,Reach-1
Reach XY= 30
      2353966.02     13763364.06      2353975.03     13763324.06
      2353976.95     13763281.26      2354019.03     13763227.24
      2354030.83     13763172.70      2354114.20     13763084.67
      2354122.46     13763068.95      2354133.20     13763018.95
      2354217.19     13762928.41      2354213.67     13762915.15
      2354183.47     13762881.19      2354176.39     13762864.57
      2354176.06     13762685.43      2354188.43     13762661.68
      2354255.66     13762595.02      2354267.19     13762578.41
      2354263.66     13762565.15      2354227.37     13762519.11
      2354224.25     13762459.92      2354228.48     13762426.50
      2354244.63     13762404.86      2354311.85     13762338.20
      2354324.40     13762314.37      2354321.69     13762276.73
      2354281.19     13762227.16      2354266.97     13762168.67
      2354227.42     13762130.60      2354179.96     13762119.66
      2354175.09     13762106.53      2354175.00     13762075.00

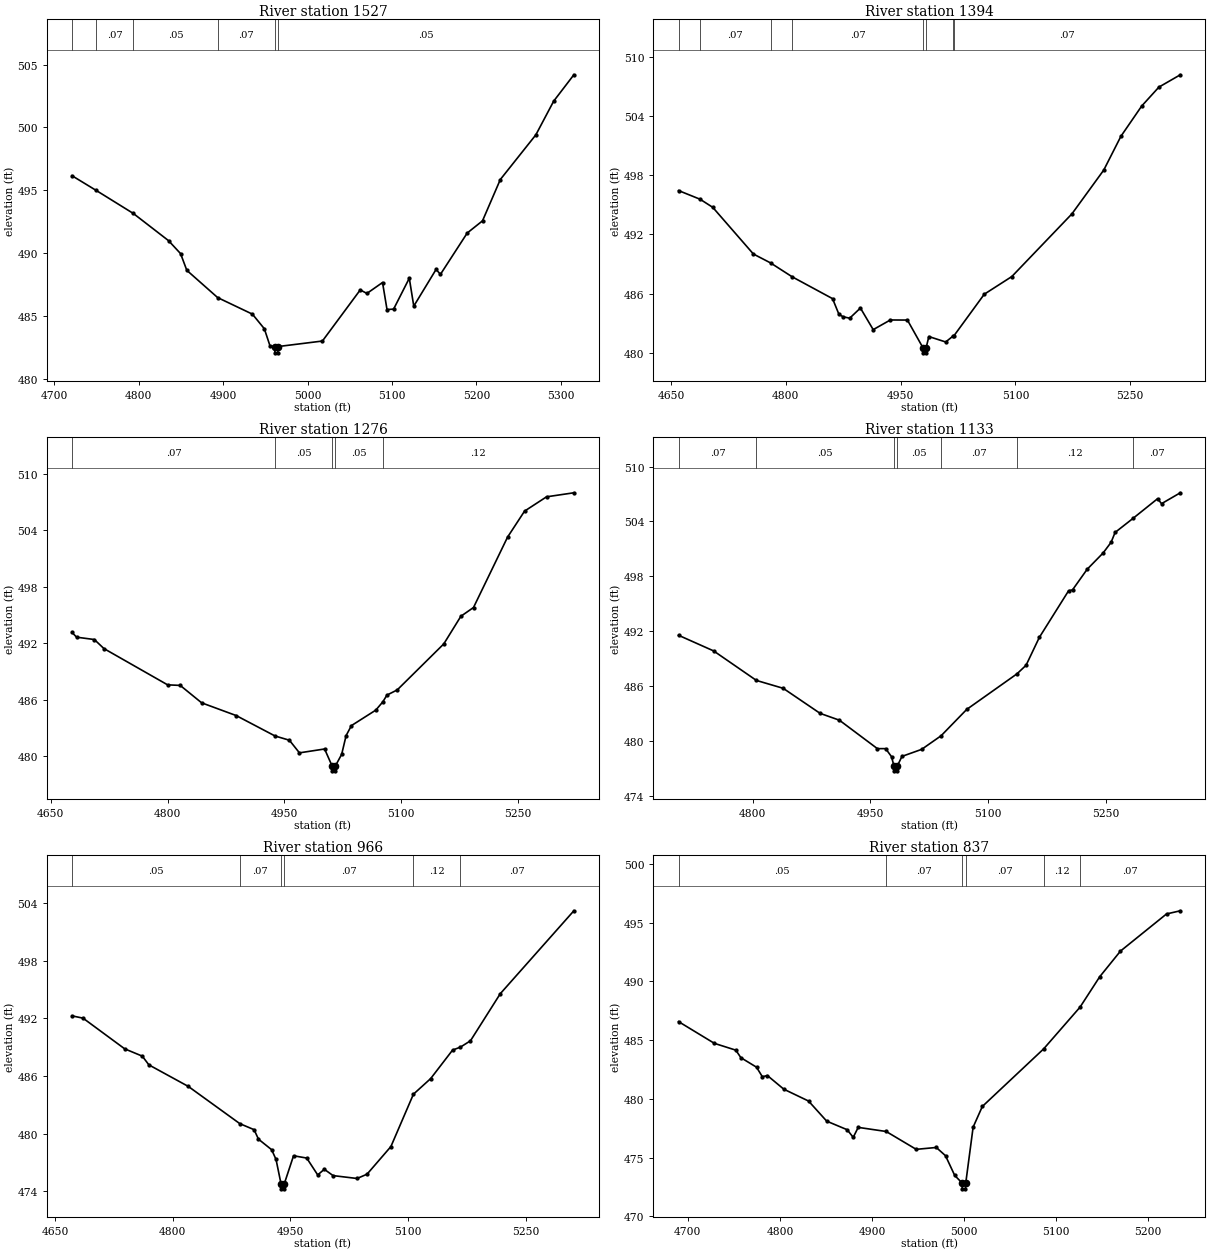
Type RM Length L Ch R = 1,1527,133,133,133
BEGIN DESCRIPTION:
X18767
END DESCRIPTION:
XS GIS Cut Line= 3
      2354165.69     13763535.96      2353990.32     13763344.97
      2353672.33     13763239.54
#Sta/Elev= 30
  4721.1  496.15  4749.7  494.98  4793.6  493.15  4835.4  490.98  4849.6  489.95
  4857.0  488.62  4893.5  486.45  4934.7  485.13  4948.8  483.97  4955.6  482.59
  4961.0  482.55  4961.3  482.05  4964.8  482.05  4965.0  482.55  5017.6  482.99
  5062.4  487.06  5070.3  486.78  5088.8  487.65  5094.1  485.50  5101.9  485.53
  5120.5  487.99  5125.8  485.77  5152.2  488.69  5157.4  488.30  5189.1  491.59
  5207.2  492.56  5228.3  495.85  5270.4  499.41  5291.5  502.09  5315.4  504.19
#Mann=6,-1,0
  4721.1    0.05       0  4749.7    0.07       0  4793.6    0.05       0
  4893.5    0.07       0  4961.0    0.05       0  4965.0    0.05       0
Bank Sta=4961,4965
Exp/Cntr=0.3,0.1

Type RM Length L Ch R = 1,1394,118,118,118
BEGIN DESCRIPTION:
DARST TRIBUTARY 5C 3.0
END DESCRIPTION:
XS GIS Cut Line= 3
      2354174.99     13763524.98      2354025.00     13763225.00
      2353775.03     13763025.03
#Sta/Elev= 30
  4659.9  496.44  4688.1  495.56  4704.6  494.74  4757.7  490.01  4780.1  489.11
  4808.4  487.70  4861.1  485.49  4869.5  483.89  4875.1  483.65  4883.5  483.51
  4897.5  484.54  4914.2  482.35  4936.6  483.33  4958.9  483.32  4979.3  480.50
  4979.6  480.00  4983.1  480.00  4983.3  480.50  4986.9  481.65  5008.9  481.10
  5018.5  481.70  5019.5  481.71  5059.3  485.94  5095.3  487.73  5173.8  494.08
  5215.4  498.52  5237.8  501.94  5265.0  505.01  5287.4  506.92  5315.4  508.17
#Mann=8,-1,0
  4659.9    0.05       0  4688.1    0.07       0  4780.1    0.05       0
  4808.4    0.07       0  4979.3    0.05       0  4983.3    0.07       0
  5018.5    0.05       0  5019.5    0.07       0
Bank Sta=4979.3,4983.3
Exp/Cntr=0.3,0.1

Type RM Length L Ch R = 1,1276,143,143,143
BEGIN DESCRIPTION:
X18766
END DESCRIPTION:
XS GIS Cut Line= 2
      2354360.10     13763277.25      2353794.14     13762969.97
#Sta/Elev= 30
  4677.5  493.15  4683.3  492.65  4706.1  492.40  4718.4  491.44  4800.1  487.59
  4816.3  487.53  4843.8  485.68  4888.1  484.33  4938.0  482.16  4956.4  481.71
  4969.3  480.37  5001.6  480.78  5011.3  478.96  5011.5  478.46  5015.0  478.46
  5015.3  478.96  5023.5  480.21  5029.2  482.20  5036.0  483.26  5067.2  484.90
  5076.3  485.78  5081.6  486.50  5094.8  487.05  5154.6  491.94  5176.5  494.87
  5192.7  495.80  5236.4  503.27  5258.2  506.03  5286.4  507.55  5321.5  507.98
#Mann=5,-1,0
  4677.5    0.07       0  4938.0    0.05       0  5011.3    0.05       0
  5015.3    0.05       0  5076.3    0.12       0
Bank Sta=5011.3,5015.3
Exp/Cntr=0.3,0.1

Type RM Length L Ch R = 1,1133,167,167,167
BEGIN DESCRIPTION:
X18765
END DESCRIPTION:
XS GIS Cut Line= 3
      2354427.80     13763088.02      2354071.92     13762982.12
      2353808.10     13762935.56
#Sta/Elev= 30
  4705.7  491.54  4750.4  489.83  4804.9  486.60  4839.0  485.74  4886.0  483.00
  4910.6  482.25  4959.0  479.14  4969.5  479.14  4977.0  478.26  4980.2  477.21
  4980.4  476.71  4983.9  476.71  4984.2  477.21  4990.3  478.29  5015.4  479.06
  5040.2  480.55  5072.8  483.43  5136.8  487.32  5148.4  488.26  5165.3  491.31
  5202.5  496.40  5207.6  496.51  5226.2  498.76  5246.5  500.54  5256.7  501.71
  5261.8  502.79  5284.8  504.34  5315.9  506.48  5321.0  505.94  5344.9  507.13
#Mann=7,-1,0
  4705.7    0.07       0  4804.9    0.05       0  4980.2    0.05       0
  4984.2    0.05       0  5040.2    0.07       0  5136.8    0.12       0
  5284.8    0.07       0
Bank Sta=4980.2,4984.2
Exp/Cntr=0.3,0.1

Type RM Length L Ch R = 1,966,129,129,129
BEGIN DESCRIPTION:
DARST TRIBUTARY 5C 2.0
END DESCRIPTION:
XS GIS Cut Line= 3
      2354475.04     13763025.02      2354175.00     13762875.00
      2353874.99     13762925.00
#Sta/Elev= 30
  4671.9  492.27  4685.9  492.03  4739.0  488.83  4761.4  488.07  4769.8  487.16
  4820.1  484.91  4885.7  481.03  4903.9  480.40  4909.5  479.41  4926.3  478.31
  4931.9  477.29  4938.3  474.73  4938.5  474.23  4942.0  474.23  4942.3  474.73
  4954.2  477.68  4971.0  477.44  4985.0  475.68  4993.4  476.27  5004.6  475.61
  5035.2  475.31  5047.9  475.76  5078.3  478.64  5107.0  484.10  5129.0  485.73
  5156.9  488.70  5166.9  489.01  5179.7  489.67  5217.7  494.58  5311.5  503.23
#Mann=6,-1,0
  4671.9    0.05       0  4885.7    0.07       0  4938.3    0.05       0
  4942.3    0.07       0  5107.0    0.12       0  5166.9    0.07       0
Bank Sta=4938.3,4942.3
Exp/Cntr=0.3,0.1

Type RM Length L Ch R = 1,837,147,147,147
BEGIN DESCRIPTION:
X18764
END DESCRIPTION:
XS GIS Cut Line= 3
      2354462.50     13762857.10      2354222.96     13762751.22
      2353939.97     13762749.48
#Sta/Elev= 30
  4689.9  486.57  4728.8  484.72  4752.1  484.14  4757.6  483.50  4774.6  482.69
  4780.9  481.88  4786.4  481.98  4804.2  480.82  4831.1  479.81  4850.8  478.10
  4873.0  477.37  4879.6  476.72  4885.0  477.57  4915.4  477.22  4948.0  475.70
  4969.8  475.86  4979.8  475.16  4989.8  473.48  4997.8  472.84  4998.0  472.34
  5001.5  472.34  5001.8  472.84  5009.8  477.59  5019.8  479.35  5086.4  484.25
  5125.9  487.80  5147.3  490.39  5169.8  492.57  5219.8  495.73  5234.8  496.00
#Mann=6,-1,0
  4689.9    0.05       0  4915.4    0.07       0  4997.8    0.05       0
  5001.8    0.07       0  5086.4    0.12       0  5125.9    0.07       0
Bank Sta=4997.8,5001.8
Exp/Cntr=0.3,0.1

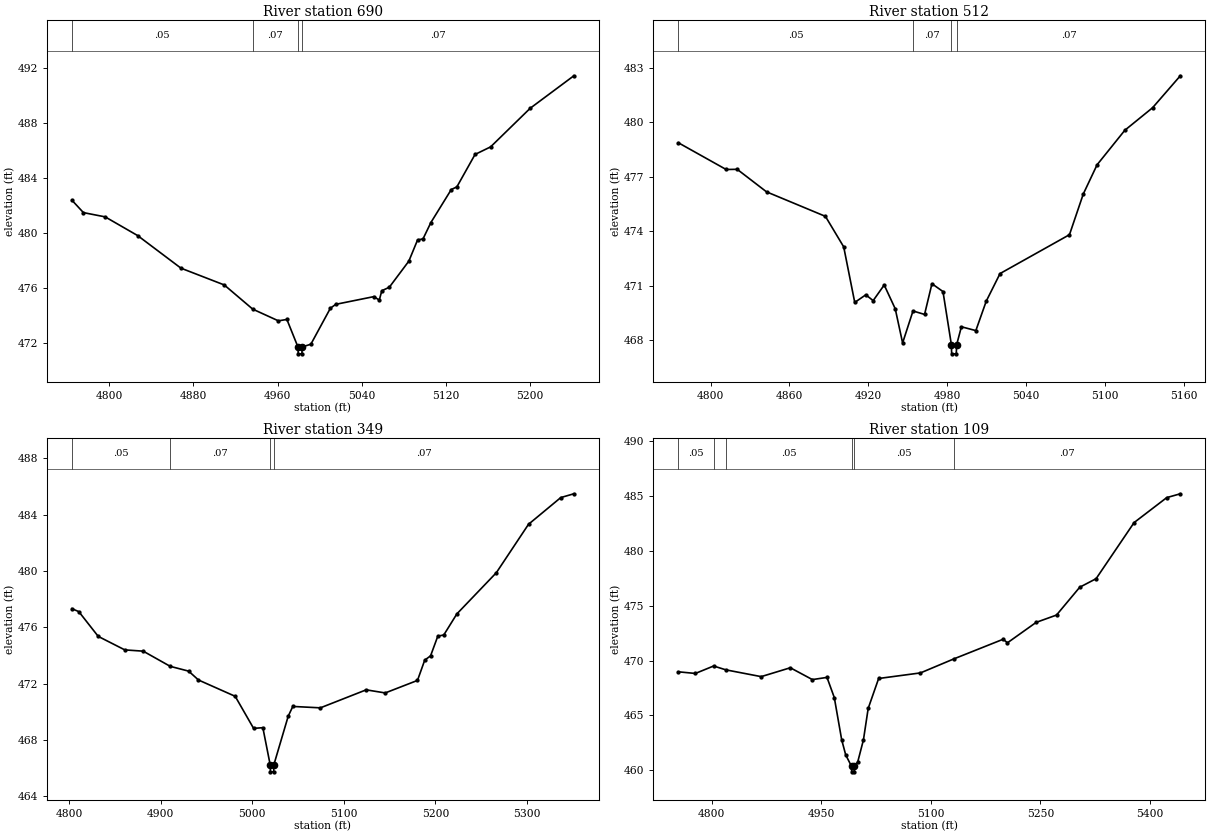
Type RM Length L Ch R = 1,690,178,178,178
BEGIN DESCRIPTION:
X18763
END DESCRIPTION:
XS GIS Cut Line= 3
      2354455.62     13762680.04      2354169.14     13762608.85
      2353995.51     13762664.42
#Sta/Elev= 30
  4764.4  482.36  4775.3  481.46  4796.0  481.15  4826.9  479.79  4868.1  477.42
  4909.3  476.20  4936.4  474.44  4960.8  473.59  4968.9  473.69  4979.4  471.69
  4979.7  471.19  4983.2  471.19  4983.4  471.69  4991.7  471.89  5010.3  474.51
  5015.4  474.79  5051.6  475.35  5056.8  475.10  5059.2  475.78  5066.3  476.03
  5084.9  477.93  5093.2  479.47  5098.4  479.55  5105.9  480.74  5125.3  483.14
  5130.6  483.33  5147.9  485.69  5162.7  486.24  5200.4  489.05  5241.9  491.41
#Mann=4,-1,0
  4764.4    0.05       0  4936.4    0.07       0  4979.4    0.05       0
  4983.4    0.07       0
Bank Sta=4979.4,4983.4
Exp/Cntr=0.3,0.1

Type RM Length L Ch R = 1,512,163,163,163
BEGIN DESCRIPTION:
DARST TRIBUTARY 5C 1.0
END DESCRIPTION:
XS GIS Cut Line= 3
      2354424.96     13762574.98      2354225.00     13762475.00
      2354074.98     13762525.01
#Sta/Elev= 30
  4775.6  478.87  4811.9  477.40  4820.3  477.41  4842.6  476.17  4887.4  474.82
  4901.3  473.14  4909.7  470.08  4918.1  470.50  4923.7  470.18  4932.1  471.04
  4940.5  469.73  4946.1  467.85  4954.0  469.61  4962.8  469.42  4968.4  471.11
  4976.8  470.68  4983.2  467.75  4983.4  467.25  4986.9  467.25  4987.2  467.75
  4990.8  468.74  5001.8  468.53  5009.7  470.15  5020.2  471.67  5073.0  473.81
  5083.5  476.05  5094.0  477.66  5115.1  479.56  5136.2  480.80  5157.3  482.56
#Mann=4,-1,0
  4775.6    0.05       0  4954.0    0.07       0  4983.2    0.05       0
  4987.2    0.07       0
Bank Sta=4983.2,4987.2
Exp/Cntr=0.3,0.1

Type RM Length L Ch R = 1,349,240,240,240
BEGIN DESCRIPTION:
X18762
END DESCRIPTION:
XS GIS Cut Line= 3
      2354502.45     13762362.32      2354243.79     13762338.02
      2354021.20     13762520.93
#Sta/Elev= 30
  4803.3  477.32  4810.8  477.11  4832.0  475.35  4861.0  474.39  4881.1  474.30
  4910.6  473.22  4930.7  472.88  4941.4  472.25  4981.5  471.09  5001.6  468.81
  5011.7  468.86  5019.7  466.22  5020.0  465.72  5023.5  465.72  5023.7  466.22
  5039.4  469.68  5044.4  470.37  5074.5  470.27  5124.5  471.55  5145.3  471.33
  5180.5  472.22  5188.4  473.66  5194.8  473.97  5202.7  475.37  5209.2  475.45
  5223.5  476.95  5266.6  479.88  5301.7  483.32  5336.9  485.22  5351.2  485.49
#Mann=4,-1,0
  4803.3    0.05       0  4910.6    0.07       0  5019.7    0.05       0
  5023.7    0.07       0
Bank Sta=5019.7,5023.7
Exp/Cntr=0.3,0.1

Type RM Length L Ch R = 1,109,0,0,0
BEGIN DESCRIPTION:
X18761
END DESCRIPTION:
XS GIS Cut Line= 4
      2354478.15     13762138.37      2354249.00     13762126.22
      2354110.11     13762292.88      2354002.48     13762508.15
#Sta/Elev= 30
  4754.4  468.97  4777.6  468.82  4802.6  469.50  4819.3  469.15  4867.7  468.53
  4907.6  469.34  4937.8  468.26  4957.8  468.46  4967.8  466.62  4977.9  462.77
  4983.4  461.39  4991.4  460.34  4991.6  459.84  4995.1  459.84  4995.4  460.34
  4999.9  460.75  5007.7  462.76  5014.2  465.63  5028.5  468.36  5085.8  468.87
  5131.5  470.15  5198.9  471.94  5204.9  471.62  5244.1  473.48  5272.0  474.15
  5303.8  476.69  5326.2  477.47  5378.2  482.59  5422.9  484.87  5441.5  485.22
#Mann=6,-1,0
  4754.4    0.05       0  4802.6    0.07       0  4819.3    0.05       0
  4991.4    0.05       0  4995.4    0.05       0  5131.5    0.07       0
Bank Sta=4991.4,4995.4
Exp/Cntr=0.3,0.1

Chan Stop Cuts=-1