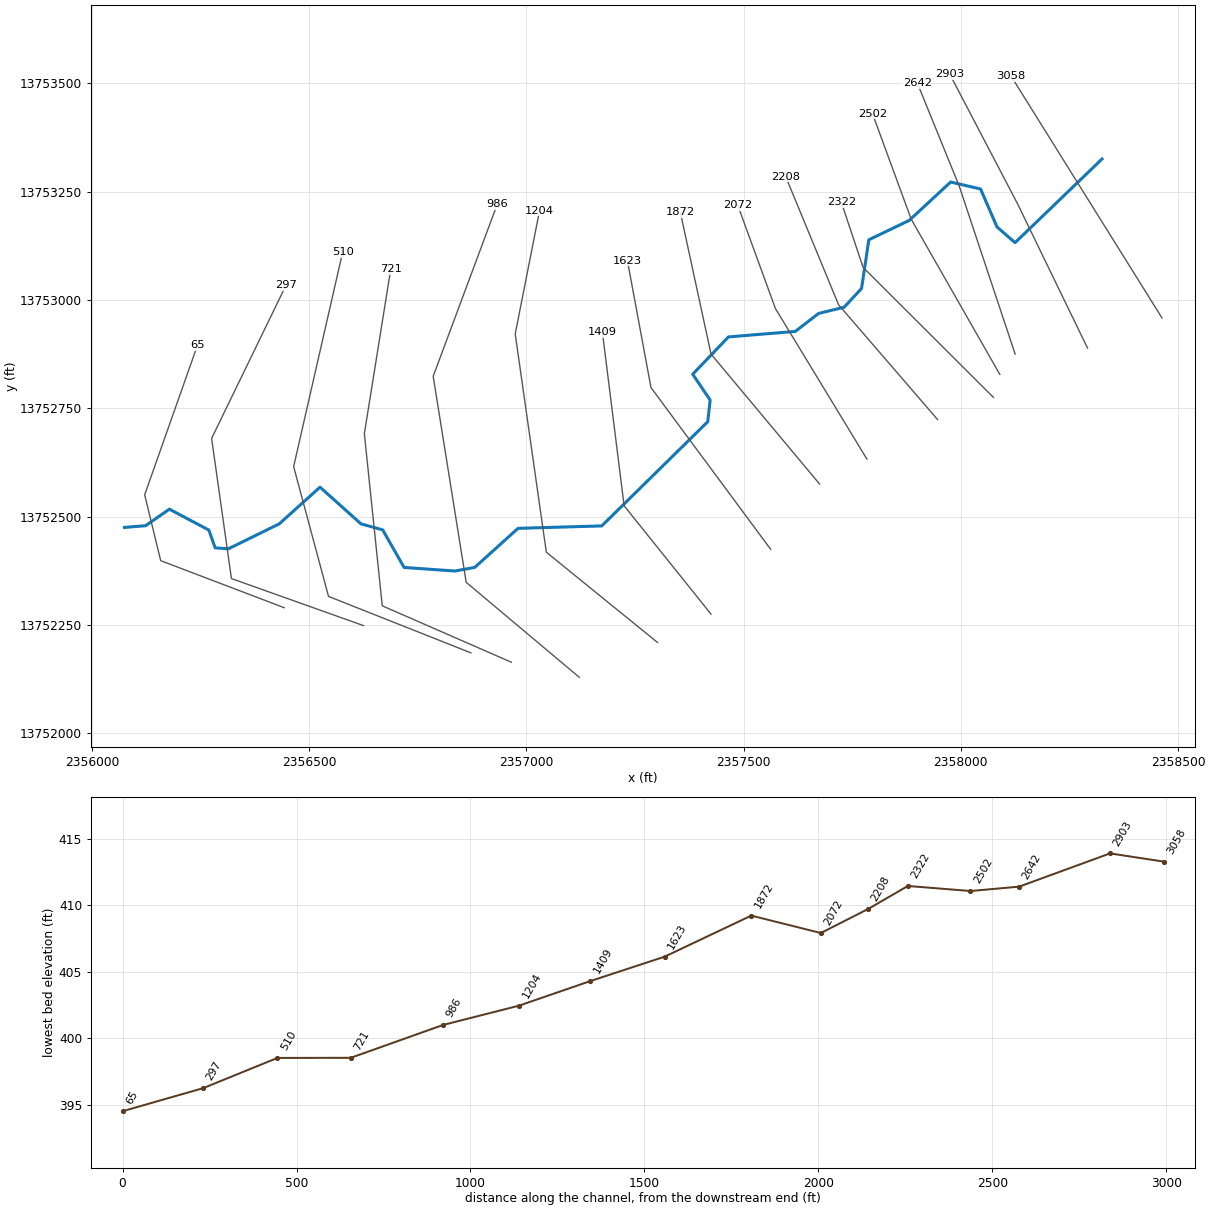
--- DEER CREEK 2.prj (project) ---

Proj Title=DEER CREEK 2 Base Level Engineering
Current Plan=p01
Default Exp/Contr=0.3,0.1
English Units
Geom File=g01
Flow File=f01
Plan File=p01
Y Axis Title=Elevation
X Axis Title(PF)=Main Channel Distance
X Axis Title(XS)=Station
BEGIN DESCRIPTION:
DEER CREEK 2
END DESCRIPTION:
DSS Export Rating Curves= 0
DSS Export Rating Curve Sorted= 0
DSS Export Volume Flow Curves= 0
DXF OffsetX= 0
DXF OffsetY= 0
DXF ScaleX= 1
DXF ScaleY= 10

--- DEER CREEK 2.p01 (plan) ---

Plan Title=Multiple Run
Program Version=4.10
Short Identifier=Multiple
Geom File=g01
Flow File=f01
Subcritical Flow
K Sum by GR= 0
Std Step Tol= 0.01
Critical Tol= 0.01
Num of Std Step Trials= 20
Max Error Tol= 0.3
Flow Tol Ratio= 0.001
Split Flow NTrial= 30
Split Flow Tol= 0.02
Split Flow Ratio= 0.02
Log Output Level= 0
Friction Slope Method= 1
Unsteady Friction Slope Method= 2
Unsteady Bridges Friction Slope Method= 1
Parabolic Critical Depth
Global Vel Dist= 1 , 1 , 1
Global Log Level= 0
CheckData=True
Encroach Param=-1 ,0,0, 0
BEGIN DESCRIPTION:
Multiple Run
END DESCRIPTION:
Computation Interval=1HOUR
Output Interval=1HOUR
Run HTab= 0
Run UNet= 0
Run PostProcess= 0
Run WQNet= 0
UNET Theta= 1
UNET Theta Warmup= 1
UNET ZTol= 0.02
UNET ZSATol= 0.05
UNET MxIter= 20
UNET MaxInSteps= 0
UNET DtIC= 0
UNET DtMin= 0
UNET MaxCRTS= 20
UNET WFStab= 2
UNET SFStab= 1
UNET WFX= 1
UNET SFX= 1
UNET DSS MLevel= 4
UNET DZMax Abort= 100
UNET Convert EG Bridges= 0
UNET Use Existing IB Tables=-1
UNET Froude Reduction=False
UNET Froude Limit= 1
UNET Froude Power= 10
UNET Time Slicing=0,0, 5
UNET Junction Losses=0
Instantaneous Interval=1HOUR
Write IC File= 0
Write IC File at Sim End=0
Echo Input=False
Echo Parameters=False
Echo Output=False
Write Detailed= 0
WQ AD Non Conservative
WQ ULTIMATE=-1
WQ Max Comp Step=1HOUR
WQ Output Interval=15MIN
WQ Output Selected Increments= 0
WQ Output face flow=0
WQ Output face velocity=0
WQ Output face area=0
WQ Output face dispersion=0
WQ Output cell volume=0
WQ Output cell surface area=0
WQ Output cell continuity=0
WQ Output cumulative cell continuity=0
WQ Output face conc=0
WQ Output face dconc_dx=0
WQ Output face courant=0
WQ Output face peclet=0
WQ Output face adv mass=0
WQ Output face disp mass=0
WQ Output cell mass=0
WQ Output cell source sink temp=0
WQ Output cell source sink nsm=0
WQ Output MaxMinRange=-1
WQ Daily Max Min Mean=-1
WQ Daily Range=0
WQ Daily Time=0
WQ Create Restart=0
WQ Fixed Restart=0
WQ System Summary=0
WQ Use Fixed Temperature=0
Sorting and Armoring Iterations= 10
XS Update Threshold= 0.02
Hydraulics Update Threshold= 0.02
Energy Slope Method= 1
Volume Change Method= 0
XS Weighting Method= 0
Number of US Weighted Cross Sections= 1
Number of DS Weighted Cross Sections= 1
Upstream XS Weight=0.25
Main XS Weight=0.5
Downstream XS Weight=0.25
Number of DS XS's Weighted with US Boundary= 1
Upstream Boundary Weight= 1
Weight of XSs Associated with US Boundary= 0
Number of US XS's Weighted with DS Boundary= 1
Downstream Boundary Weight= 0.5
Weight of XSs Associated with DS Boundary= 0.5
Sediment Output Level= 4
Mass or Volume Output= 0
Output Increment Type= 1
Profile and TS Output Increment= 10
XS Output Flag= 0
XS Output Increment= 10
Disregard all LS=0
Disregard all Conn=0
Disregard all Breaches=0
Disregard all Pumps=0

--- DEER CREEK 2.f01 (steady flow) ---

Flow Title=Multiple
Number of Profiles=7
Profile Names=10-year,25-year,50-year,1pct_min,100-year,1pct_plu,500-year
River Rch & RM= DEER CREEK 2,Reach-1,3058
     591     951    1274     828    1651    3295    2745
Boundary for River Rch & Prof#=DEER CREEK 2,Reach-1,1
Up Type=0
Dn Type=3
Dn Slope=0.005
Boundary for River Rch & Prof#=DEER CREEK 2,Reach-1,2
Up Type=0
Dn Type=3
Dn Slope=0.005
Boundary for River Rch & Prof#=DEER CREEK 2,Reach-1,3
Up Type=0
Dn Type=3
Dn Slope=0.005
Boundary for River Rch & Prof#=DEER CREEK 2,Reach-1,4
Up Type=0
Dn Type=3
Dn Slope=0.005
Boundary for River Rch & Prof#=DEER CREEK 2,Reach-1,5
Up Type=0
Dn Type=3
Dn Slope=0.005
Boundary for River Rch & Prof#=DEER CREEK 2,Reach-1,6
Up Type=0
Dn Type=3
Dn Slope=0.005
Boundary for River Rch & Prof#=DEER CREEK 2,Reach-1,7
Up Type=0
Dn Type=3
Dn Slope=0.005

--- DEER CREEK 2.g01 (geometry) ---

Geom Title=Existing Conditions

River Reach=DEER CREEK 2,Reach-1
Reach XY= 30
      2358325.00     13753325.00      2358124.79     13753131.98
      2358083.17     13753168.31      2358045.47     13753255.73
      2357976.68     13753271.91      2357881.02     13753183.19
      2357788.26     13753138.65      2357771.47     13753026.29
      2357731.38     13752983.00      2357672.86     13752968.85
      2357619.07     13752927.25      2357465.15     13752914.52
      2357382.81     13752828.42      2357423.01     13752768.95
      2357417.50     13752718.95      2357173.54     13752478.54
      2356980.86     13752472.93      2356881.18     13752382.82
      2356835.18     13752374.45      2356718.54     13752382.73
      2356669.36     13752469.35      2356619.25     13752483.32
      2356525.00     13752567.91      2356431.05     13752483.17
      2356313.96     13752425.65      2356283.62     13752427.96
      2356269.23     13752468.92      2356178.32     13752517.16
      2356123.64     13752479.00      2356075.00     13752475.00

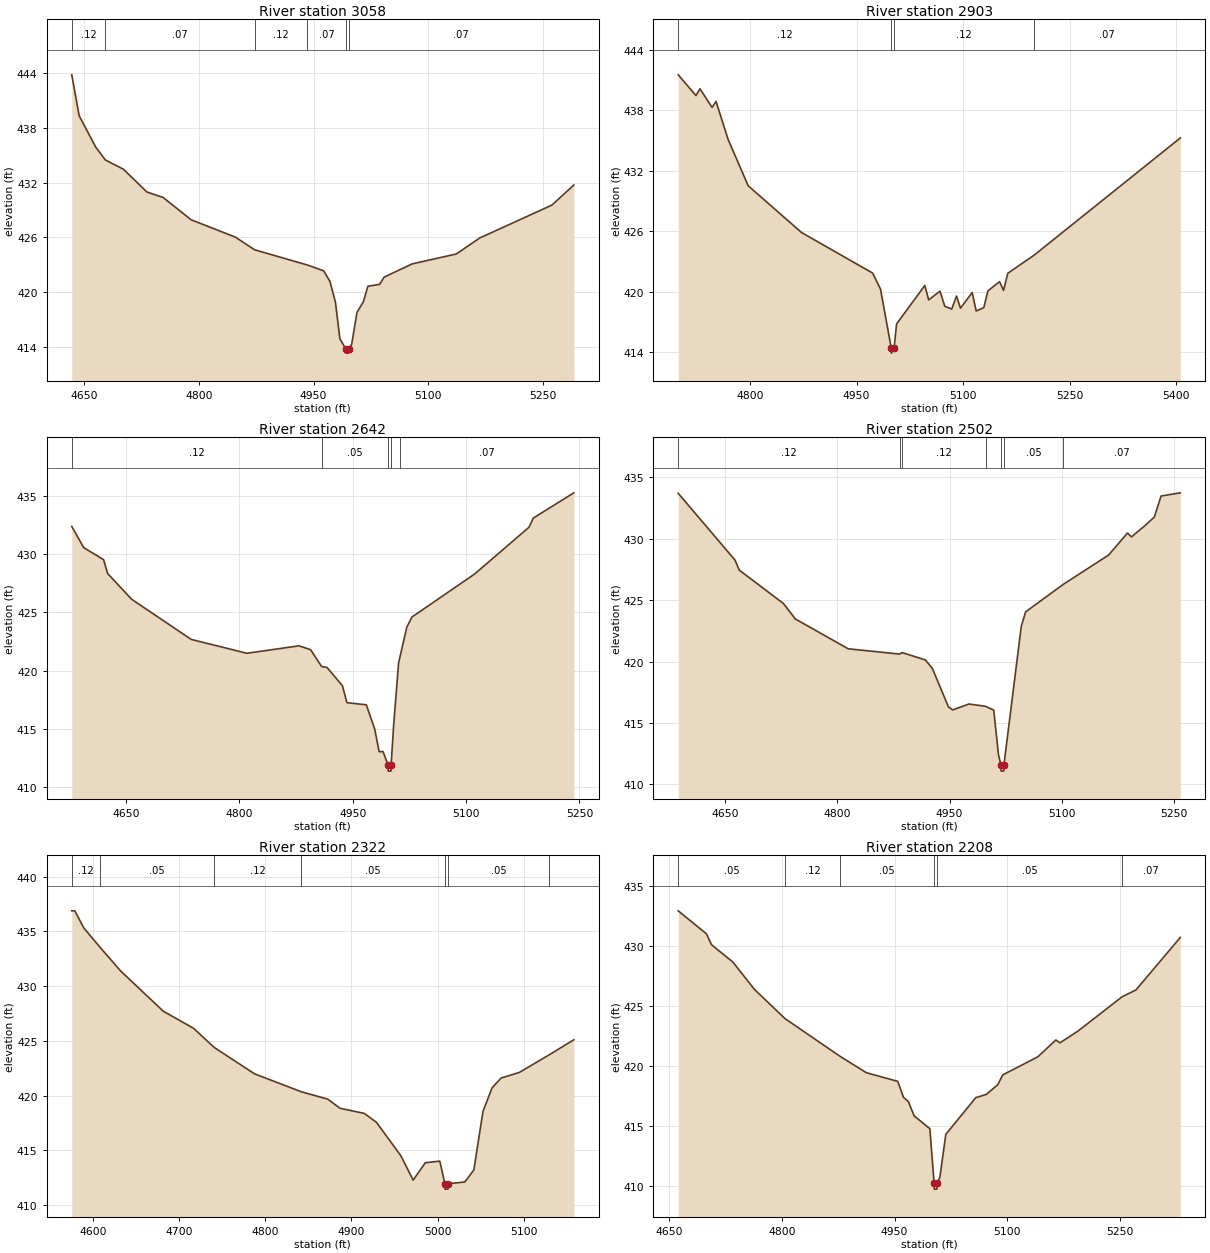
Type RM Length L Ch R = 1,3058,155,155,155
BEGIN DESCRIPTION:
X18844
END DESCRIPTION:
XS GIS Cut Line= 2
      2358463.00     13752958.27      2358115.82     13753515.92
#Sta/Elev= 30
  4633.6  443.85  4643.3  439.35  4665.1  435.89  4677.5  434.50  4701.2  433.48
  4731.9  430.98  4753.1  430.38  4789.7  427.93  4847.5  426.03  4872.9  424.63
  4941.8  422.96  4963.2  422.32  4971.4  421.15  4978.6  418.87  4984.4  414.85
  4991.9  413.78  4992.2  413.28  4995.7  413.28  4995.9  413.78  4999.8  414.24
  5006.7  417.74  5015.1  418.92  5021.0  420.62  5036.4  420.84  5042.3  421.63
  5078.9  423.08  5136.7  424.17  5167.4  425.93  5261.8  429.54  5290.5  431.75
#Mann=6,-1,0
  4633.6    0.12       0  4677.5    0.07       0  4872.9    0.12       0
  4941.8    0.07       0  4991.9    0.05       0  4995.9    0.07       0
Bank Sta=4991.9,4995.9
Exp/Cntr=0.3,0.1

Type RM Length L Ch R = 1,2903,261,261,261
BEGIN DESCRIPTION:
X18845
END DESCRIPTION:
XS GIS Cut Line= 3
      2358291.56     13752888.83      2358130.99     13753220.82
      2357974.82     13753520.15
#Sta/Elev= 30
  4699.1  441.50  4724.1  439.44  4729.7  440.12  4746.7  438.27  4752.3  438.86
  4769.3  435.09  4797.5  430.50  4872.6  425.86  4972.6  421.84  4983.7  420.25
  4998.8  414.40  4999.0  413.90  5002.8  414.40  5006.3  416.79  5046.0  420.61
  5051.5  419.18  5067.4  420.05  5074.1  418.55  5083.9  418.27  5090.6  419.56
  5096.2  418.36  5112.7  419.91  5118.3  418.08  5129.0  418.41  5134.8  420.07
  5151.2  420.99  5156.8  420.12  5162.8  421.82  5199.9  423.62  5405.5  435.24
#Mann=4,-1,0
  4699.1    0.12       0  4998.8    0.05       0  5002.8    0.12       0
  5199.9    0.07       0
Bank Sta=4998.8,5002.8
Exp/Cntr=0.3,0.1

Type RM Length L Ch R = 1,2642,140,140,140
BEGIN DESCRIPTION:
DEER CREEK 2 6.0
END DESCRIPTION:
XS GIS Cut Line= 3
      2358125.00     13752875.01      2357996.44     13753262.05
      2357899.97     13753500.01
#Sta/Elev= 30
  4578.0  432.35  4593.8  430.54  4620.1  429.51  4625.5  428.32  4657.2  426.12
  4736.0  422.68  4809.8  421.49  4878.8  422.13  4894.1  421.80  4908.7  420.36
  4915.8  420.28  4936.3  418.71  4942.2  417.26  4967.9  417.08  4979.1  414.98
  4984.8  413.07  4990.1  413.07  4996.7  411.90  4996.9  411.40  5000.4  411.40
  5000.7  411.90  5004.1  415.36  5010.6  420.65  5012.0  421.05  5021.4  423.71
  5028.2  424.59  5111.3  428.28  5183.2  432.28  5189.0  433.07  5242.6  435.23
#Mann=5,-1,0
  4578.0    0.12       0  4908.7    0.05       0  4996.7    0.05       0
  5000.7    0.05       0  5012.0    0.07       0
Bank Sta=4996.7,5000.7
Exp/Cntr=0.3,0.1

Type RM Length L Ch R = 1,2502,180,180,180
BEGIN DESCRIPTION:
X18843
END DESCRIPTION:
XS GIS Cut Line= 3
      2358089.75     13752828.03      2357885.76     13753186.10
      2357796.80     13753429.13
#Sta/Elev= 30
  4587.4  433.71  4663.2  428.27  4669.0  427.45  4728.0  424.73  4743.9  423.47
  4814.5  421.04  4883.2  420.61  4886.7  420.73  4917.7  420.13  4926.9  419.45
  4948.5  416.30  4954.2  416.06  4975.9  416.54  4998.1  416.35  5009.0  416.04
  5015.3  412.42  5018.6  411.57  5018.9  411.07  5022.4  411.07  5022.6  411.57
  5045.8  422.87  5051.6  424.05  5101.9  426.29  5162.5  428.68  5187.7  430.47
  5193.1  430.16  5211.3  431.09  5223.6  431.78  5232.6  433.49  5258.3  433.75
#Mann=7,-1,0
  4587.4    0.12       0  4883.2    0.05       0  4886.7    0.12       0
  4998.1    0.05       0  5018.6    0.05       0  5022.6    0.05       0
  5101.9    0.07       0
Bank Sta=5018.6,5022.6
Exp/Cntr=0.3,0.1

Type RM Length L Ch R = 1,2322,114,114,114
BEGIN DESCRIPTION:
DEER CREEK 2 5.0
END DESCRIPTION:
XS GIS Cut Line= 3
      2358074.99     13752775.01      2357775.00     13753075.00
      2357724.99     13753225.04
#Sta/Elev= 30
  4575.7  436.88  4579.2  436.88  4589.8  435.30  4608.6  433.54  4632.3  431.39
  4681.8  427.71  4717.1  426.14  4740.7  424.41  4787.8  421.98  4841.9  420.35
  4872.7  419.67  4886.8  418.84  4915.1  418.37  4929.2  417.55  4957.5  414.49
  4971.7  412.27  4985.8  413.86  5002.6  414.01  5008.5  411.95  5008.7  411.45
  5012.2  411.45  5012.5  411.95  5031.6  412.10  5042.1  413.20  5052.7  418.55
  5063.2  420.70  5073.7  421.60  5094.8  422.11  5129.7  423.73  5158.1  425.10
#Mann=7,-1,0
  4575.7    0.12       0  4608.6    0.05       0  4740.7    0.12       0
  4841.9    0.05       0  5008.5    0.05       0  5012.5    0.05       0
  5129.7    0.07       0
Bank Sta=5008.5,5012.5
Exp/Cntr=0.3,0.1

Type RM Length L Ch R = 1,2208,136,136,136
BEGIN DESCRIPTION:
X18842
END DESCRIPTION:
XS GIS Cut Line= 3
      2357946.56     13752723.82      2357718.66     13752988.61
      2357597.15     13753283.72
#Sta/Elev= 30
  4662.0  432.93  4699.6  431.01  4706.2  430.11  4734.7  428.66  4763.3  426.39
  4804.2  423.94  4877.6  420.79  4912.5  419.43  4954.2  418.71  4961.9  417.38
  4968.5  417.01  4976.1  415.83  4997.0  414.76  5002.7  410.22  5002.9  409.72
  5006.4  409.72  5006.7  410.22  5010.3  410.70  5018.3  414.29  5058.2  417.35
  5072.3  417.62  5087.6  418.44  5094.0  419.24  5140.9  420.76  5164.8  422.16
  5170.3  421.92  5194.2  422.90  5253.2  425.77  5271.4  426.33  5330.5  430.71
#Mann=6,-1,0
  4662.0    0.05       0  4804.2    0.12       0  4877.6    0.05       0
  5002.7    0.05       0  5006.7    0.05       0  5253.2    0.07       0
Bank Sta=5002.7,5006.7
Exp/Cntr=0.3,0.1

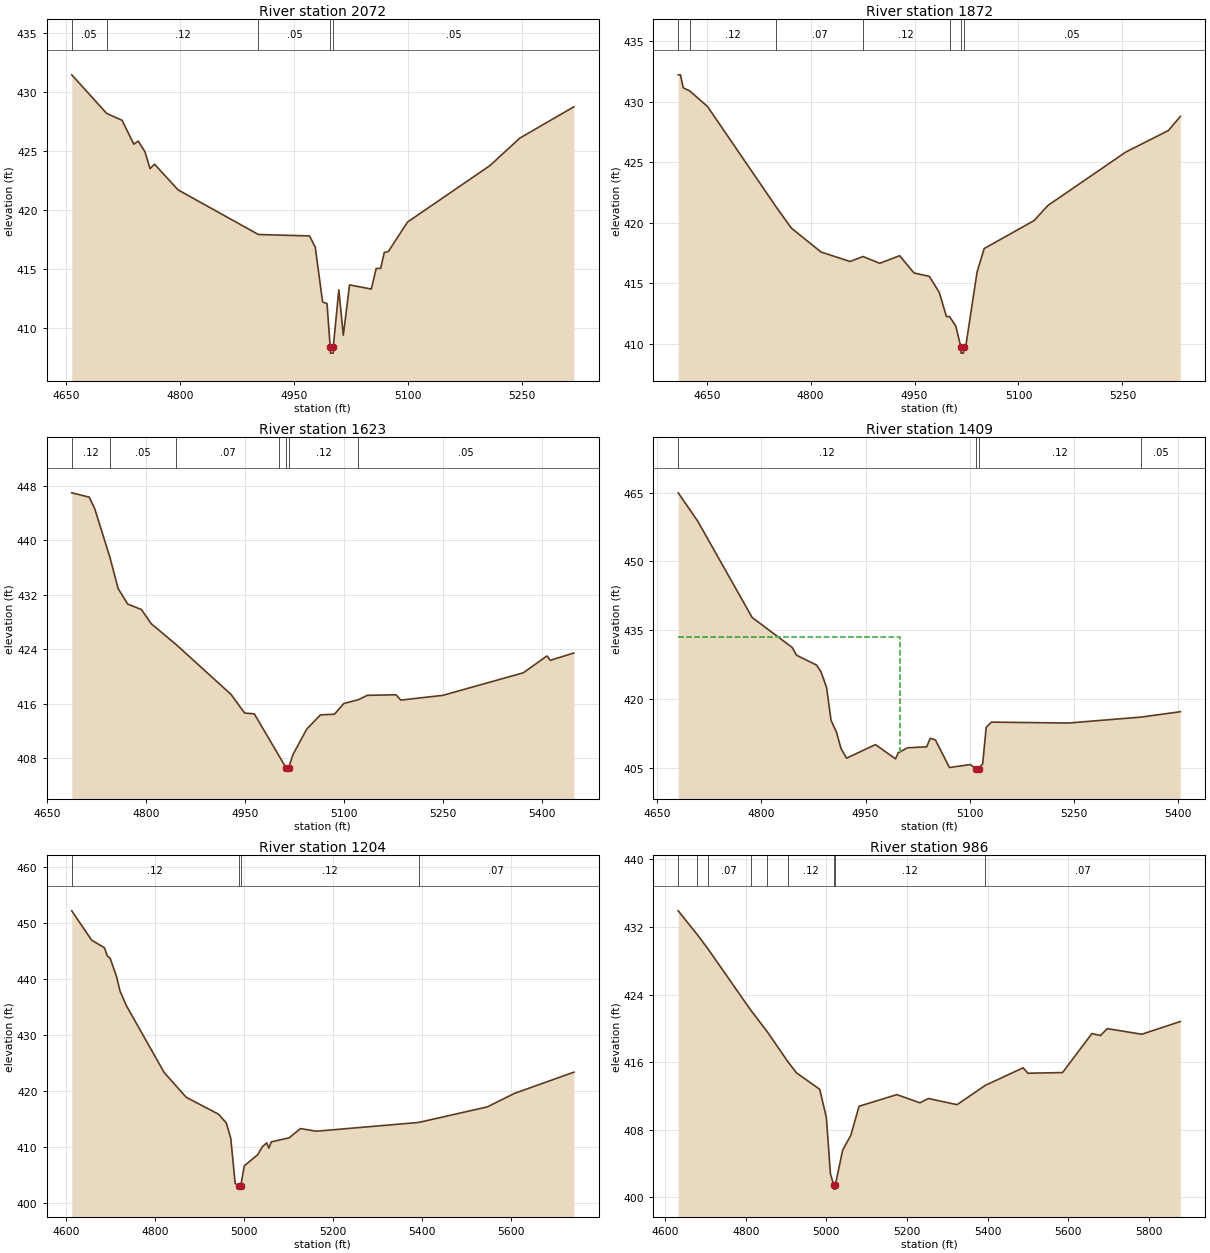
Type RM Length L Ch R = 1,2072,200,200,200
BEGIN DESCRIPTION:
X18841
END DESCRIPTION:
XS GIS Cut Line= 3
      2357783.79     13752632.68      2357573.26     13752979.93
      2357486.46     13753218.65
#Sta/Elev= 30
  4657.9  431.49  4703.8  428.22  4724.0  427.64  4739.5  425.61  4745.3  425.88
  4754.2  424.96  4760.8  423.54  4766.7  423.92  4797.7  421.74  4903.3  417.96
  4970.5  417.84  4978.0  416.89  4987.7  412.24  4993.5  412.11  4997.7  408.41
  4998.0  407.91  5001.5  407.91  5001.7  408.41  5009.0  413.27  5014.9  409.43
  5023.1  413.69  5051.7  413.34  5058.2  415.09  5064.0  415.09  5068.8  416.44
  5074.1  416.52  5099.4  419.02  5207.7  423.80  5247.0  426.13  5318.0  428.78
#Mann=5,-1,0
  4657.9    0.05       0  4703.8    0.12       0  4903.3    0.05       0
  4997.7    0.05       0  5001.7    0.05       0
Bank Sta=4997.7,5001.7
Exp/Cntr=0.3,0.1

Type RM Length L Ch R = 1,1872,249,249,249
BEGIN DESCRIPTION:
DEER CREEK 2 4.0
END DESCRIPTION:
XS GIS Cut Line= 3
      2357674.99     13752575.01      2357425.00     13752875.00
      2357354.45     13753201.77
#Sta/Elev= 30
  4608.8  432.21  4612.0  432.21  4616.0  431.14  4625.4  430.88  4651.1  429.59
  4750.5  421.27  4772.2  419.54  4815.1  417.57  4856.8  416.79  4875.6  417.20
  4899.7  416.64  4928.4  417.27  4949.2  415.84  4971.3  415.56  4985.6  414.24
  4996.0  412.24  5000.5  412.24  5009.5  411.45  5016.8  409.72  5017.1  409.22
  5020.6  409.22  5020.8  409.72  5023.9  409.79  5040.2  415.92  5050.5  417.86
  5122.5  420.17  5142.5  421.42  5254.9  425.83  5316.4  427.61  5333.6  428.77
#Mann=7,-1,0
  4608.8    0.05       0  4625.4    0.12       0  4750.5    0.07       0
  4875.6    0.12       0  5000.5    0.05       0  5016.8    0.05       0
  5020.8    0.05       0
Bank Sta=5016.8,5020.8
Exp/Cntr=0.3,0.1

Type RM Length L Ch R = 1,1623,214,214,214
BEGIN DESCRIPTION:
X18840
END DESCRIPTION:
XS GIS Cut Line= 3
      2357562.41     13752424.39      2357286.81     13752797.64
      2357232.61     13753090.29
#Sta/Elev= 30
  4687.1  446.96  4713.5  446.33  4721.9  444.64  4745.0  437.49  4757.4  432.92
  4772.0  430.63  4792.8  429.84  4807.5  427.77  4845.9  424.66  4928.6  417.39
  4949.4  414.65  4964.0  414.53  5002.1  408.27  5012.1  406.63  5012.4  406.13
  5016.1  406.63  5022.6  408.55  5043.4  412.28  5064.3  414.38  5085.6  414.48
  5099.7  416.05  5121.9  416.61  5135.4  417.25  5178.9  417.33  5186.2  416.55
  5250.1  417.25  5372.1  420.56  5407.9  423.03  5413.0  422.39  5448.7  423.46
#Mann=7,-1,0
  4687.1    0.12       0  4745.0    0.05       0  4845.9    0.07       0
  5002.1    0.12       0  5012.1    0.05       0  5016.1    0.12       0
  5121.9    0.05       0
Bank Sta=5012.1,5016.1
Exp/Cntr=0.3,0.1

Type RM Length L Ch R = 1,1409,205,205,205
BEGIN DESCRIPTION:
DEER CREEK 2 3.0
END DESCRIPTION:
XS GIS Cut Line= 3
      2357425.00     13752275.00      2357225.00     13752525.00
      2357175.00     13752925.03
#Sta/Elev= 30
  4680.1  464.94  4708.1  458.79  4786.6  437.77  4844.2  431.25  4850.6  429.54
  4879.4  427.40  4885.8  425.91  4893.8  422.55  4900.2  415.39  4908.2  412.71
  4914.6  409.21  4922.6  407.11  4964.2  410.07  4993.1  406.97  4997.1  408.30
  5010.3  409.37  5038.0  409.59  5043.1  411.45  5050.6  411.09  5070.8  405.08
  5101.0  405.72  5109.1  404.79  5109.4  404.29  5113.1  404.79  5118.7  405.88
  5123.7  413.82  5131.3  414.97  5242.1  414.77  5347.0  416.07  5403.4  417.24
#Mann=4,-1,0
  4680.1    0.12       0  5109.1    0.05       0  5113.1    0.12       0
  5347.0    0.05       0
#XS Ineff=2,0
    0.00 4999.90  433.48               0
Permanent Ineff=
       F       F
Bank Sta=5109.1,5113.1
Exp/Cntr=0.3,0.1

Type RM Length L Ch R = 1,1204,218,218,218
BEGIN DESCRIPTION:
X18839
END DESCRIPTION:
XS GIS Cut Line= 4
      2357301.96     13752209.56      2357045.92     13752417.87
      2356974.31     13752921.34      2357030.37     13753205.96
#Sta/Elev= 30
  4611.9  452.23  4656.6  446.98  4685.3  445.63  4691.8  444.16  4698.2  443.74
  4712.6  440.46  4720.5  437.85  4734.9  435.23  4819.6  423.31  4869.2  418.87
  4942.0  415.84  4959.3  414.28  4969.4  411.50  4979.2  403.48  4987.6  402.94
  4987.8  402.44  4991.6  402.94  4999.7  406.60  5030.0  408.61  5040.1  410.00
  5050.1  410.71  5055.1  409.76  5060.3  410.89  5100.7  411.62  5126.0  413.27
  5161.3  412.80  5391.8  414.37  5546.0  417.15  5607.1  419.57  5740.6  423.36
#Mann=4,-1,0
  4611.9    0.12       0  4987.6    0.05       0  4991.6    0.12       0
  5391.8    0.07       0
Bank Sta=4987.6,4991.6
Exp/Cntr=0.3,0.1

Type RM Length L Ch R = 1,986,265,265,265
BEGIN DESCRIPTION:
X18838
END DESCRIPTION:
XS GIS Cut Line= 4
      2357121.85     13752129.26      2356861.46     13752348.42
      2356785.50     13752823.68      2356932.93     13753220.44
#Sta/Elev= 30
  4632.6  433.91  4679.9  431.09  4706.1  429.43  4811.8  422.20  4853.8  419.58
  4904.7  416.05  4925.7  414.75  4983.4  412.80  4999.9  409.46  5010.0  402.78
  5018.1  401.49  5018.4  400.99  5021.9  400.99  5022.1  401.49  5040.4  405.62
  5060.6  407.36  5080.9  410.79  5174.7  412.17  5231.7  411.20  5253.0  411.71
  5323.9  410.98  5393.8  413.26  5487.6  415.34  5499.8  414.70  5585.5  414.78
  5658.3  419.39  5679.7  419.16  5696.3  419.98  5782.0  419.31  5877.5  420.82
#Mann=9,-1,0
  4632.6    0.07       0  4679.9    0.12       0  4706.1    0.07       0
  4811.8    0.12       0  4853.8    0.07       0  4904.7    0.12       0
  5018.1    0.05       0  5022.1    0.12       0  5393.8    0.07       0
Bank Sta=5018.1,5022.1
Exp/Cntr=0.3,0.1

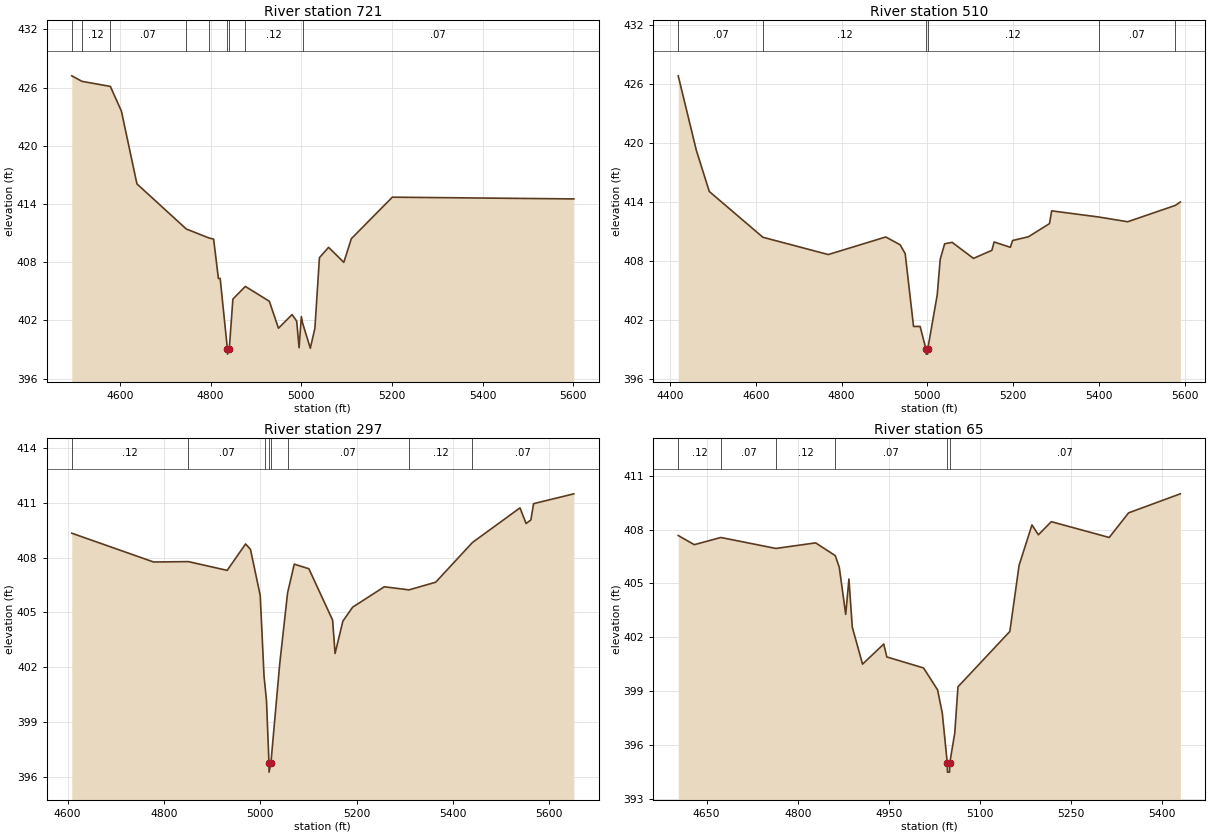
Type RM Length L Ch R = 1,721,211,211,211
BEGIN DESCRIPTION:
X18837
END DESCRIPTION:
XS GIS Cut Line= 4
      2356965.59     13752163.98      2356668.32     13752294.17
      2356627.08     13752691.30      2356687.77     13753070.58
#Sta/Elev= 30
  4493.6  427.21  4516.2  426.64  4578.7  426.12  4603.1  423.58  4637.4  416.07
  4746.3  411.42  4796.5  410.49  4806.6  410.38  4817.2  406.32  4821.1  406.32
  4837.1  399.02  4837.3  398.52  4841.1  399.02  4849.1  404.19  4876.6  405.50
  4929.6  403.97  4949.7  401.19  4979.8  402.60  4989.9  401.92  4995.2  399.18
  5000.2  402.39  5002.9  401.73  5020.0  399.13  5030.1  401.19  5040.1  408.46
  5060.3  409.53  5093.9  407.98  5110.5  410.42  5201.0  414.70  5601.5  414.52
#Mann=9,-1,0
  4493.6    0.07       0  4516.2    0.12       0  4578.7    0.07       0
  4746.3    0.12       0  4796.5    0.07       0  4837.1    0.05       0
  4841.1    0.07       0  4876.6    0.12       0  5002.9    0.07       0
Bank Sta=4837.1,4841.1
Exp/Cntr=0.3,0.1

Type RM Length L Ch R = 1,510,213,213,213
BEGIN DESCRIPTION:
X18836
END DESCRIPTION:
XS GIS Cut Line= 4
      2356872.27     13752185.68      2356544.62     13752315.87
      2356464.32     13752615.35      2356577.16     13753110.12
#Sta/Elev= 30
  4419.4  426.85  4461.5  419.28  4491.8  415.07  4616.7  410.41  4769.1  408.65
  4903.1  410.44  4936.7  409.64  4948.3  408.74  4967.8  401.33  4983.1  401.33
  4996.8  399.01  4997.1  398.51  5000.6  398.51  5000.8  399.01  5023.1  404.57
  5029.9  408.16  5040.3  409.75  5057.9  409.89  5107.4  408.26  5150.4  409.08
  5155.6  409.93  5193.4  409.39  5198.6  410.08  5235.5  410.46  5284.6  411.80
  5289.7  413.10  5399.8  412.47  5466.8  411.99  5577.6  413.65  5589.5  414.00
#Mann=6,-1,0
  4419.4    0.07       0  4616.7    0.12       0  4996.8    0.05       0
  5000.8    0.12       0  5399.8    0.07       0  5577.6   0.035       0
Bank Sta=4996.8,5000.8
Exp/Cntr=0.3,0.1

Type RM Length L Ch R = 1,297,232,232,232
BEGIN DESCRIPTION:
X18835
END DESCRIPTION:
XS GIS Cut Line= 4
      2356624.92     13752248.59      2356321.09     13752357.10
      2356275.52     13752680.45      2356446.98     13753034.22
#Sta/Elev= 30
  4608.5  409.35  4778.3  407.77  4850.6  407.79  4931.1  407.31  4969.4  408.76
  4979.5  408.46  4999.7  405.94  5007.7  401.49  5010.2  400.84  5012.7  400.18
  5017.9  396.74  5018.1  396.24  5021.9  396.74  5040.1  402.15  5056.5  406.07
  5070.4  407.65  5100.7  407.40  5150.0  404.58  5155.1  402.75  5171.4  404.53
  5191.6  405.29  5257.4  406.41  5308.5  406.24  5364.0  406.66  5440.3  408.84
  5539.0  410.74  5551.7  409.88  5561.6  410.08  5567.2  410.97  5650.8  411.51
#Mann=8,-1,0
  4608.5    0.12       0  4850.6    0.07       0  5010.2    0.12       0
  5017.9    0.05       0  5021.9    0.12       0  5056.5    0.07       0
  5308.5    0.12       0  5440.3    0.07       0
Bank Sta=5017.9,5021.9
Exp/Cntr=0.3,0.1

Type RM Length L Ch R = 1,65,0,0,0
BEGIN DESCRIPTION:
X18834
END DESCRIPTION:
XS GIS Cut Line= 4
      2356442.64     13752289.82      2356158.33     13752398.34
      2356121.44     13752550.25      2356242.98     13752895.33
#Sta/Elev= 30
  4603.3  407.67  4629.7  407.16  4673.5  407.56  4764.0  406.95  4829.5  407.26
  4861.8  406.55  4868.4  405.90  4879.0  403.28  4884.3  405.25  4889.8  402.57
  4906.7  400.51  4941.6  401.63  4946.7  400.91  5007.1  400.30  5030.2  399.08
  5038.0  397.78  5046.2  395.00  5046.5  394.50  5050.0  394.50  5050.2  395.00
  5058.5  396.67  5063.8  399.25  5149.2  402.33  5164.4  406.01  5185.6  408.26
  5196.2  407.71  5217.4  408.44  5312.8  407.56  5344.6  408.93  5429.8  409.99
#Mann=6,-1,0
  4603.3    0.12       0  4673.5    0.07       0  4764.0    0.12       0
  4861.8    0.07       0  5046.2    0.05       0  5050.2    0.07       0
Bank Sta=5046.2,5050.2
Exp/Cntr=0.3,0.1

Chan Stop Cuts=-1