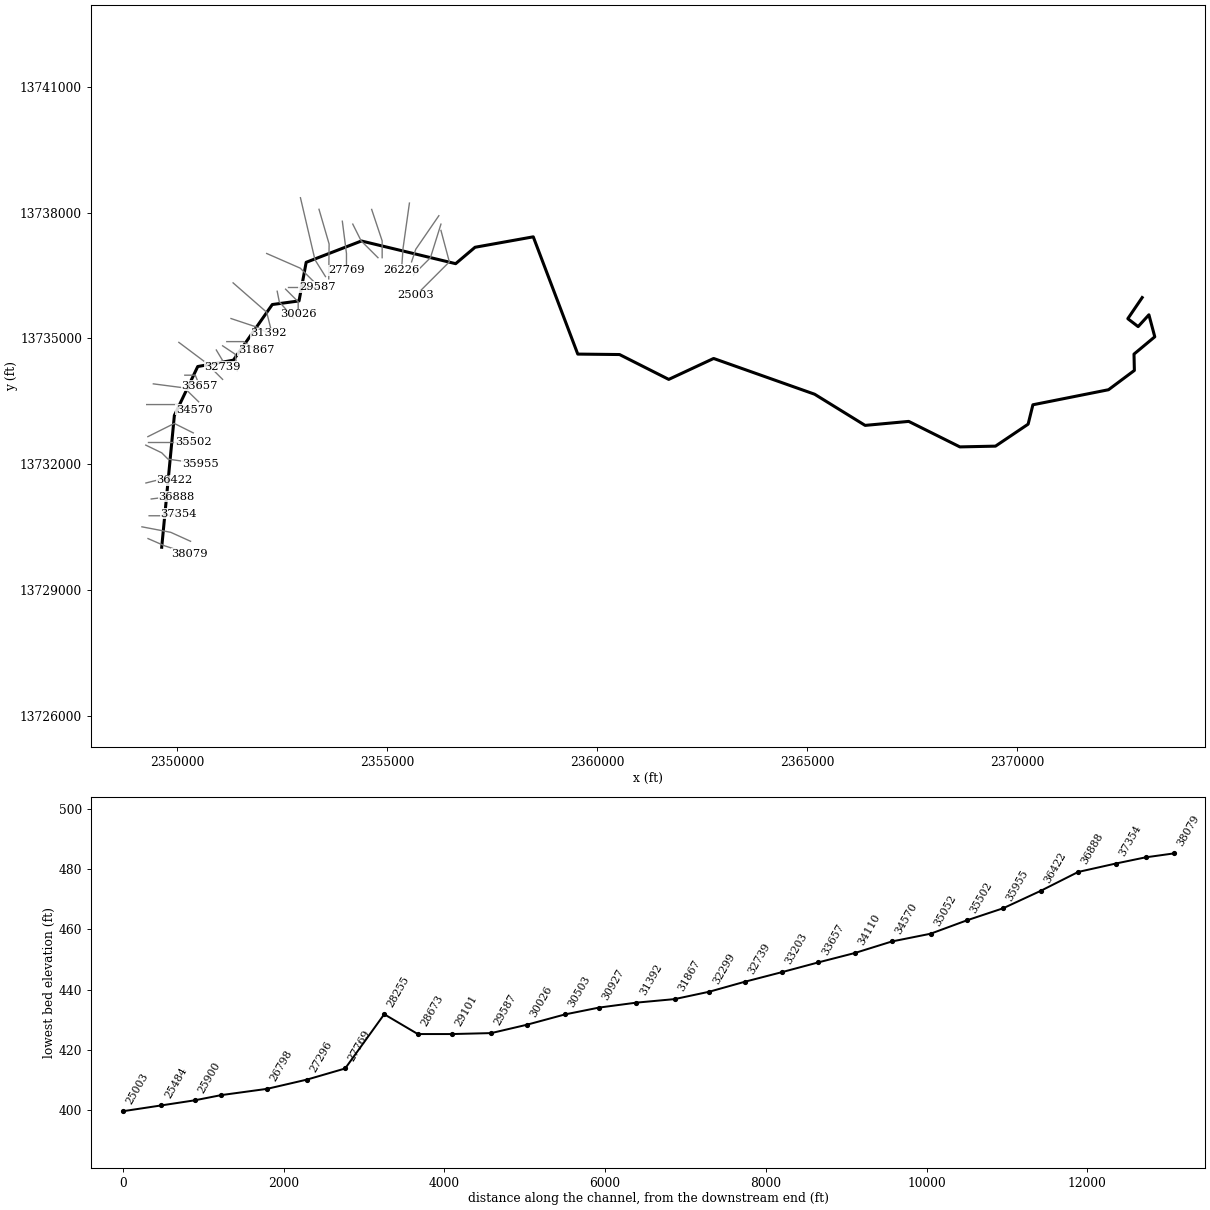
--- GUADALUPE TRIBUTARY 1.prj (project) ---

Proj Title=GUADALUPE TRIBUTARY 1 Base Level Engineering
Current Plan=p01
Default Exp/Contr=0.3,0.1
English Units
Geom File=g01
Flow File=f01
Plan File=p01
Y Axis Title=Elevation
X Axis Title(PF)=Main Channel Distance
X Axis Title(XS)=Station
BEGIN DESCRIPTION:
GUADALUPE TRIBUTARY 1
END DESCRIPTION:
DSS Export Rating Curves= 0
DSS Export Rating Curve Sorted= 0
DSS Export Volume Flow Curves= 0
DXF OffsetX= 0
DXF OffsetY= 0
DXF ScaleX= 1
DXF ScaleY= 10

--- GUADALUPE TRIBUTARY 1.p01 (plan) ---

Plan Title=Multiple Run
Short Identifier=Multiple
Geom File=g01
Flow File=f01
Subcritical Flow
K Sum by GR= 0
Std Step Tol= 0.01
Critical Tol= 0.01
Num of Std Step Trials= 20
Max Error Tol= 0.3
Flow Tol Ratio= 0.001
Split Flow NTrial= 30
Split Flow Tol= 0.02
Split Flow Ratio= 0.02
Log Output Level= 0
Friction Slope Method= 1
Unsteady Friction Slope Method= 2
Unsteady Bridges Friction Slope Method= 1
Parabolic Critical Depth
Global Vel Dist=  1 , 1 , 1
Global Log Level= 0
CheckData=True
Encroach Param= -1, 0, 0, 0
BEGIN DESCRIPTION:
Multiple Run
END DESCRIPTION:

--- GUADALUPE TRIBUTARY 1.f01 (steady flow) ---

Flow Title=Multiple
Number of Profiles=7
Profile Names=10-year,25-year,50-year,1pct_min,100-year,1pct_plu,500-year
River Rch & RM= GUADALUPE TRIBUT,Reach-1,38079
     973    1641    2274    1527    3046    6078    5419
River Rch & RM= GUADALUPE TRIBUT,Reach-1,36422
    1194    2033    2833    1911    3814    7610    6853
River Rch & RM= GUADALUPE TRIBUT,Reach-1,33203
    1490    2556    3579    2423    4834    9646    8749
River Rch & RM= GUADALUPE TRIBUT,Reach-1,28673
    1667    2866    4019    2724    5435   10844    9855
River Rch & RM= GUADALUPE TRIBUT,Reach-1,26226
    1899    3286    4627    3148    6281   12532   11477
River Rch & RM= GUADALUPE TRIBUT,Reach-1,24058
    2018    3491    4915    3341    6665   13299   12162
River Rch & RM= GUADALUPE TRIBUT,Reach-1,21378
    1988    3430    4818    3268    6520   13008   11842
River Rch & RM= GUADALUPE TRIBUT,Reach-1,18407
    2951    5171    7343    5027   10031   20014   18571
River Rch & RM= GUADALUPE TRIBUT,Reach-1,16270
    3154    5533    7862    5384   10743   21436   19906
River Rch & RM= GUADALUPE TRIBUT,Reach-1,15101
    3124    5475    7774    5320   10615   21179   19635
River Rch & RM= GUADALUPE TRIBUT,Reach-1,14064
    3199    5562    7852    5339   10654   21257   19458
Boundary for River Rch & Prof#=GUADALUPE TRIBUT,Reach-1,1
Up Type=0
Dn Type=3
Dn Slope=0.005
Boundary for River Rch & Prof#=GUADALUPE TRIBUT,Reach-1,2
Up Type=0
Dn Type=3
Dn Slope=0.005
Boundary for River Rch & Prof#=GUADALUPE TRIBUT,Reach-1,3
Up Type=0
Dn Type=3
Dn Slope=0.005
Boundary for River Rch & Prof#=GUADALUPE TRIBUT,Reach-1,4
Up Type=0
Dn Type=3
Dn Slope=0.005
Boundary for River Rch & Prof#=GUADALUPE TRIBUT,Reach-1,5
Up Type=0
Dn Type=3
Dn Slope=0.005
Boundary for River Rch & Prof#=GUADALUPE TRIBUT,Reach-1,6
Up Type=0
Dn Type=3
Dn Slope=0.005
Boundary for River Rch & Prof#=GUADALUPE TRIBUT,Reach-1,7
Up Type=0
Dn Type=3
Dn Slope=0.005

--- GUADALUPE TRIBUTARY 1.g01 (geometry) ---

Geom Title=Existing Conditions
Program Version=4.10

River Reach=GUADALUPE TRIBUT,Reach-1
Reach XY= 30
        2349625.       13730025.      2349926.22      13733164.5
      2350482.85     13734331.19      2351331.38     13734482.35
      2352258.21     13735808.56      2352895.21     13735894.59
       2353065.2     13736814.52      2354380.85     13737322.94
      2356625.11     13736782.31      2357086.83     13737173.36
      2358473.58     13737421.96       2359533.4     13734627.61
      2360528.33     13734616.99      2361699.89     13734024.69
      2362768.96     13734523.37      2365173.54     13733671.46
      2366376.47     13732928.55       2367414.5     13733023.78
       2368633.4      13732416.1      2369481.74     13732434.13
       2370258.7     13732957.87      2370372.29     13733419.72
       2372173.5     13733778.61      2372788.67     13734238.23
      2372780.09      13734627.3      2373274.68     13735040.02
        2373135.     13735564.05      2372878.33     13735282.59
      2372632.49     13735471.42        2372975.       13735975.

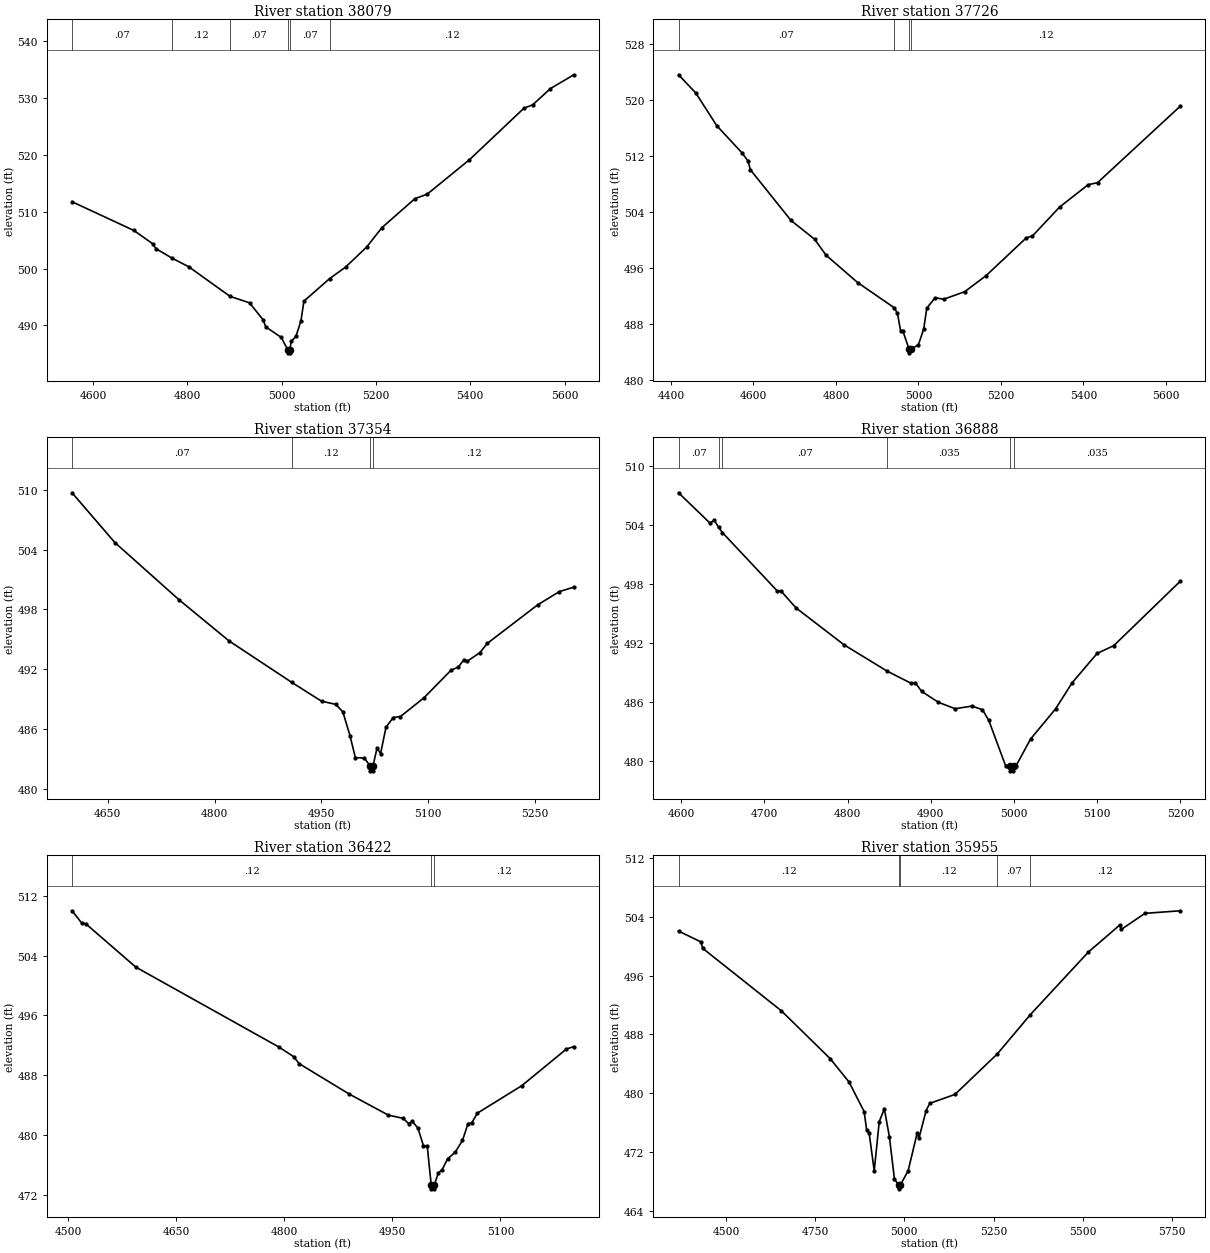
Type RM Length L Ch R = 1 ,38079   ,353,353,353
BEGIN DESCRIPTION:
A19102
END DESCRIPTION:
XS GIS Cut Line= 3
      2349298.32     13730231.56      2349700.74      13730056.6
      2350295.67     13729864.12
#Sta/Elev= 30
  4555.6  511.76  4686.6  506.71  4726.4  504.38  4733.5   503.5  4768.4   501.8
  4802.8  500.33  4890.6  495.11  4931.9  493.97  4960.8  490.98  4966.3  489.74
  4999.3  487.88  5013.2  485.67  5013.5  485.17    5017  485.17  5017.2  485.67
  5020.5  487.19  5030.4  488.07  5040.9  490.79  5047.3  494.27  5101.8  498.24
  5135.5  500.25  5180.5  503.81  5212.6   507.2  5282.7  512.31  5308.6  513.09
  5398.3  519.16  5513.9  528.23  5532.6  528.83  5569.9  531.68  5619.7  534.11
#Mann= 6 ,-1 , 0
  4555.6     .07       0  4768.4     .12       0  4890.6     .07       0
  5013.2     .05       0  5017.2     .07       0  5101.8     .12       0
Bank Sta=5013.2,5017.2
XS Rating Curve= 0 ,0
Exp/Cntr=0.3,0.1

Type RM Length L Ch R = 1 ,37726   ,372,372,372
BEGIN DESCRIPTION:
GUADALUPE TRIBUTARY 2 33.0
END DESCRIPTION:
XS GIS Cut Line= 3
      2349153.94     13730511.53      2349840.72      13730380.3
      2350311.61     13730166.65
#Sta/Elev= 30
  4418.6  523.61  4460.4  521.01  4511.3  516.33  4572.4  512.45  4587.1  511.28
  4592.8  510.03  4691.3  502.78  4748.5   500.1    4776  497.83  4852.7  493.91
  4940.5  490.34  4949.1  489.56  4956.9     487    4962  487.04  4977.6  484.36
  4977.9  483.86  4981.7  484.36    5000  485.01  5012.8  487.26  5020.4  490.26
  5040.7  491.74  5061.1  491.52    5112  492.59  5163.9  494.89  5261.8  500.31
  5276.2  500.55  5342.1  504.69  5411.2  507.89  5434.3  508.19  5634.9  519.13
#Mann= 4 ,-1 , 0
  4418.6     .07       0  4940.5     .12       0  4977.6     .05       0
  4981.7     .12       0
Bank Sta=4977.6,4981.7
XS Rating Curve= 0 ,0
Exp/Cntr=0.3,0.1

Type RM Length L Ch R = 1 ,37354   ,466,466,466
BEGIN DESCRIPTION:
GUADALUPE TRIBUTARY 2 32.0
END DESCRIPTION:
XS GIS Cut Line= 3
      2349325.01       13730775.        2349725.       13730775.
      2350024.97     13730824.99
#Sta/Elev= 30
  4600.1   509.7  4660.1  504.71  4750.1  498.97  4820.1  494.85  4908.5  490.67
  4950.1  488.79  4970.1  488.47  4980.1  487.71  4990.1  485.32  4997.6  483.13
  5010.2  483.08  5018.3   482.3  5018.6   481.8  5022.2   481.8  5022.4   482.3
    5028  484.08    5033  483.53  5040.6  486.17  5050.8  487.15  5060.9  487.25
  5093.9  489.13  5131.9   491.9    5142  492.21  5149.6  492.92  5154.7   492.8
  5172.4  493.66  5182.6  494.58  5253.5  498.46    5284  499.79  5304.2  500.23
#Mann= 4 ,-1 , 0
  4600.1     .07       0  4908.5     .12       0  5018.3     .05       0
  5022.4     .12       0
Bank Sta=5018.3,5022.4
XS Rating Curve= 0 ,0
Exp/Cntr=0.3,0.1

Type RM Length L Ch R = 1 ,36888   ,466,466,466
BEGIN DESCRIPTION:
GUADALUPE TRIBUTARY 2 31.0
END DESCRIPTION:
XS GIS Cut Line= 3
      2349375.02       13731175.        2349775.       13731225.
      2349975.01       13731225.
#Sta/Elev= 30
  4596.9  507.27  4634.7  504.19  4639.7  504.48  4645.2  503.75  4649.7  503.22
  4715.3  497.32  4720.3  497.27    4738  495.58  4795.9  491.82  4847.4  489.16
  4876.5  487.91  4881.6  487.95  4889.1  487.09  4909.3  485.98  4929.4  485.33
  4949.6   485.6  4962.2  485.23  4969.8  484.14  4989.9  479.56  4995.4  479.52
  4995.7  479.02  4999.3  479.02  4999.6  479.52  5002.5  479.52    5020  482.25
    5050  485.31    5070  487.97    5100  490.95    5120  491.74    5200  498.29
#Mann= 6 ,-1 , 0
  4596.9     .07       0  4645.2    .035       0  4649.7     .07       0
  4847.4    .035       0  4995.4    .035       0  4999.6    .035       0
Bank Sta=4995.4,4999.6
XS Rating Curve= 0 ,0
Exp/Cntr=0.3,0.1

Type RM Length L Ch R = 1 ,36422   ,467,467,467
BEGIN DESCRIPTION:
GUADALUPE TRIBUTARY 2 30.0
END DESCRIPTION:
XS GIS Cut Line= 4
      2349249.22     13731556.06        2349525.       13731625.
        2349725.       13731675.      2349925.02     13731624.99
#Sta/Elev= 30
  4505.4     510  4519.1  508.32  4524.2  508.28  4593.8  502.46  4792.2  491.77
  4812.9  490.47  4820.6  489.53  4890.2  485.45  4944.3  482.64  4964.9   482.2
  4972.6  481.51  4977.8  481.79  4985.5   480.9  4993.2  478.53  4998.4  478.53
    5004  473.26  5004.3  472.76    5008  472.76  5008.2  473.26  5013.9  474.91
    5019   475.3  5026.7  476.78  5037.1  477.64  5047.4  479.24  5055.1  481.51
  5060.2  481.58    5068  482.89  5129.8  486.58  5191.7  491.49    5202  491.81
#Mann= 3 ,-1 , 0
  4505.4     .12       0    5004     .05       0  5008.2     .12       0
Bank Sta=5004,5008.2
XS Rating Curve= 0 ,0
Exp/Cntr=0.3,0.1

Type RM Length L Ch R = 1 ,35955   ,453,453,453
BEGIN DESCRIPTION:
GUADALUPE TRIBUTARY 2 29.0
END DESCRIPTION:
XS GIS Cut Line= 4
      2349245.78     13732458.13        2349625.       13732275.
        2349775.       13732125.      2350540.27     13732016.35
#Sta/Elev= 30
  4367.3  502.07  4429.7   500.6  4435.3  499.71  4655.2  491.23    4792  484.72
    4845  481.54  4887.4  477.51  4894.5  474.98  4901.6  474.53  4915.7  469.44
  4929.8  476.15    4944  477.87  4958.1  474.11  4972.3  468.34  4984.1  467.49
  4984.4  466.99  4988.8  467.49  5010.7  469.45    5036  474.56  5041.1   473.9
  5061.2  477.65  5071.3  478.62    5142  479.84  5260.8  485.36  5353.3   490.7
  5515.7  499.21  5603.4  502.87  5608.4   502.3  5674.3  504.48  5773.5  504.83
#Mann= 5 ,-1 , 0
  4367.3     .12       0  4984.1     .05       0  4988.8     .12       0
  5260.8     .07       0  5353.3     .12       0
Bank Sta=4984.1,4988.8
XS Rating Curve= 0 ,0
Exp/Cntr=0.3,0.1

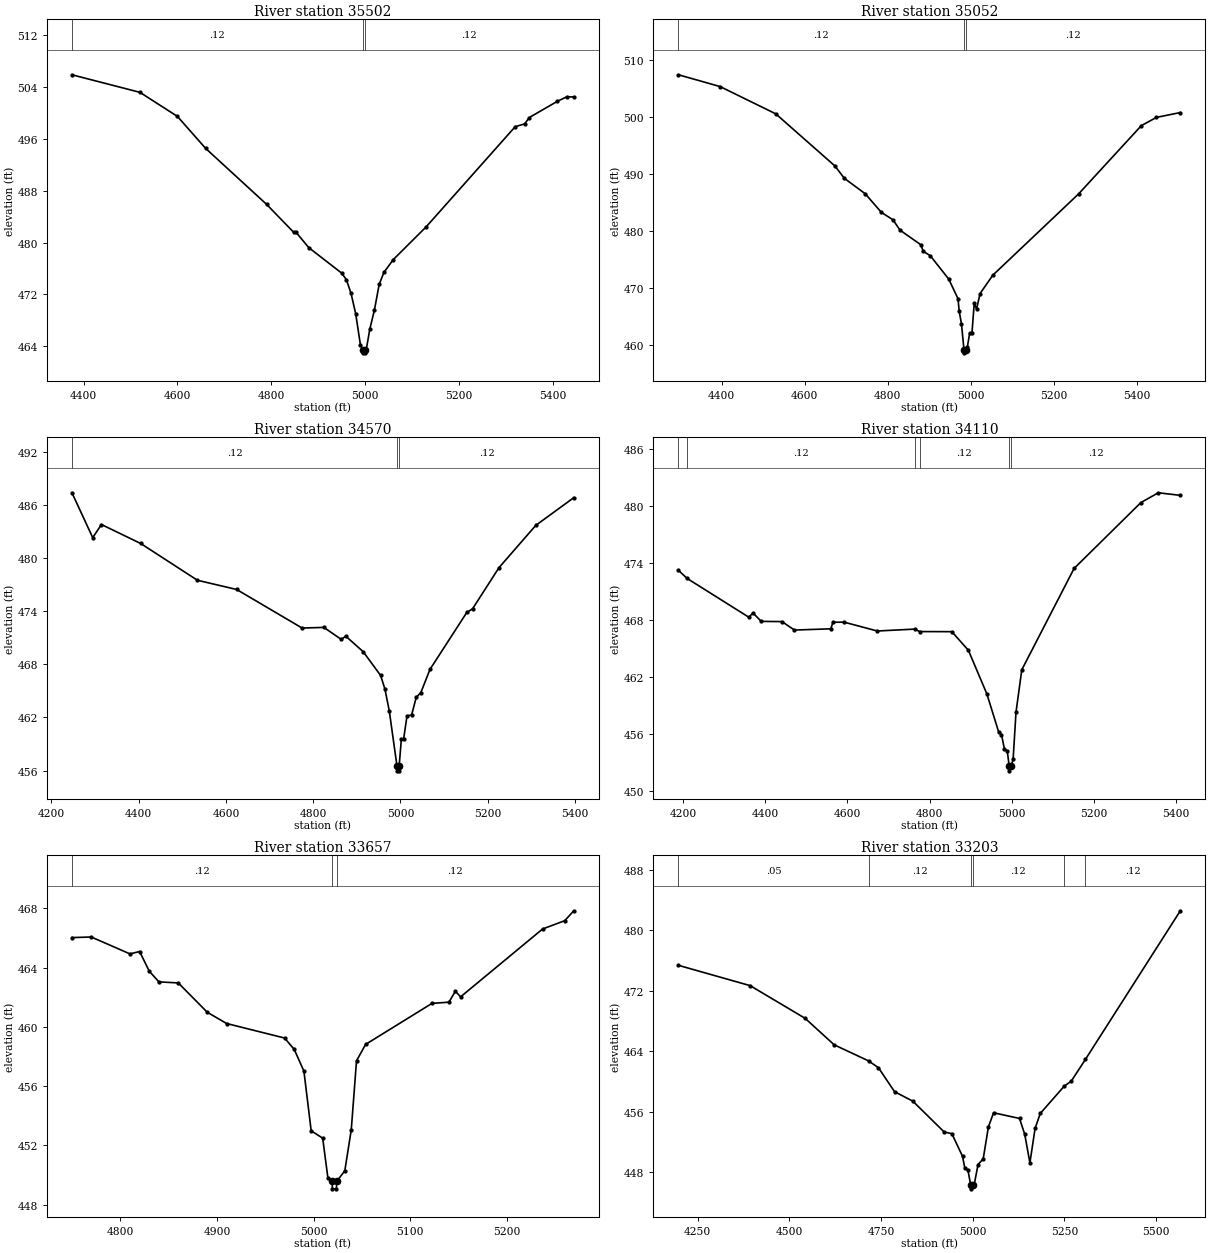
Type RM Length L Ch R = 1 ,35502   ,450,450,450
BEGIN DESCRIPTION:
GUADALUPE TRIBUTARY 2 28.0
END DESCRIPTION:
XS GIS Cut Line= 5
       2349300.2       13732525.        2349775.       13732525.
        2349925.       13732525.        2350025.       13732525.
       2350369.8       13732525.
#Sta/Elev= 30
  4375.1  505.92  4519.9  503.21  4599.9  499.49  4659.9  494.56  4789.9  485.91
  4847.4  481.61  4852.4  481.61  4879.9  479.22  4949.9  475.29  4959.9  474.29
  4969.9  472.16  4979.9     469  4989.9  464.22  4995.1  463.47  4995.4  462.97
  4999.4  462.97  4999.8  463.47  5002.4  463.47  5009.9  466.62  5019.9  469.63
  5029.9  473.53  5039.9  475.38  5059.9  477.37  5129.9  482.42  5319.9  497.91
  5339.9  498.33  5349.9  499.32  5409.9  501.83  5429.9  502.52  5444.7   502.5
#Mann= 3 ,-1 , 0
  4375.1     .12       0  4995.1     .05       0  4999.8     .12       0
Bank Sta=4995.1,4999.8
XS Rating Curve= 0 ,0
Exp/Cntr=0.3,0.1

Type RM Length L Ch R = 1 ,35052   ,482,482,482
BEGIN DESCRIPTION:
GUADALUPE TRIBUTARY 2 27.0
END DESCRIPTION:
XS GIS Cut Line= 5
      2349295.31     13732660.16        2349825.       13732925.
        2349925.       13732975.        2350025.       13732925.
      2350376.41      13732749.3
#Sta/Elev= 30
    4296  507.36  4396.3  505.29  4530.4   500.5    4673  491.34  4695.3   489.2
  4745.7  486.48  4784.8   483.2  4812.7   481.9  4829.5  480.09  4879.8  477.52
  4885.4  476.37  4902.2  475.62  4946.9   471.5  4969.3  468.04  4972.1  465.84
  4977.6  463.63  4983.7  459.05    4984  458.55  4988.4  459.05  4991.6  459.49
  4997.2  461.97  5002.8  461.97  5008.4  467.28    5014  466.23  5022.4  468.96
  5053.1  472.18    5260  486.47  5410.9  498.44  5447.2  499.88  5504.7  500.73
#Mann= 3 ,-1 , 0
    4296     .12       0  4983.7     .05       0  4988.4     .12       0
Bank Sta=4983.7,4988.4
XS Rating Curve= 0 ,0
Exp/Cntr=0.3,0.1

Type RM Length L Ch R = 1 ,34570   ,460,460,460
BEGIN DESCRIPTION:
GUADALUPE TRIBUTARY 2 26.0
END DESCRIPTION:
XS GIS Cut Line= 5
      2349267.45       13733425.        2349825.       13733425.
        2350025.       13733425.        2350175.       13733375.
      2350397.69     13733300.77
#Sta/Elev= 30
  4247.1  487.35  4294.7  482.29  4314.7  483.77  4404.7  481.63  4534.7  477.48
  4624.7  476.44  4774.7  472.09  4824.7  472.16  4864.7   470.8  4874.7  471.18
  4914.7  469.42  4954.7  466.74  4964.7  465.18  4974.7  462.69  4992.3  456.48
  4992.6  455.98  4996.7  455.98  4997.1  456.48  5002.2  459.53  5007.3  459.53
  5015.2  462.19  5025.7  462.28  5036.3  464.27  5046.8   464.8  5067.9  467.43
  5152.2  473.85  5165.4  474.26    5226   478.9  5310.3  483.67  5397.5   486.8
#Mann= 3 ,-1 , 0
  4247.1     .12       0  4992.3     .05       0  4997.1     .12       0
Bank Sta=4992.3,4997.1
XS Rating Curve= 0 ,0
Exp/Cntr=0.3,0.1

Type RM Length L Ch R = 1 ,34110   ,453,453,453
BEGIN DESCRIPTION:
GUADALUPE TRIBUTARY 2 25.0
END DESCRIPTION:
XS GIS Cut Line= 3
      2349425.17     13733918.26      2350164.42     13733822.03
      2350505.42     13733489.77
#Sta/Elev= 30
  4188.9  473.25  4209.9   472.4  4360.2  468.32  4370.3  468.77  4390.4  467.88
  4440.8  467.86  4471.1  466.97  4559.8   467.1  4564.8  467.79  4592.1   467.8
  4672.8  466.87    4764  467.07    4776  466.81  4854.3   466.8  4894.6  464.84
  4939.7  460.24    4968  456.29  4975.2  455.98  4982.2  454.47  4989.3  454.24
  4993.9  452.66  4994.3  452.16  4998.7  452.66  5003.5  453.39  5010.5  458.32
  5024.6  462.79  5151.9  473.45  5314.5  480.38  5356.9  481.41  5410.5  481.14
#Mann= 6 ,-1 , 0
  4188.9     .07       0  4209.9     .12       0    4764     .07       0
    4776     .12       0  4993.9     .05       0  4998.7     .12       0
Bank Sta=4993.9,4998.7
XS Rating Curve= 0 ,0
Exp/Cntr=0.3,0.1

Type RM Length L Ch R = 1 ,33657   ,454,454,454
BEGIN DESCRIPTION:
GUADALUPE TRIBUTARY 2 24.0
END DESCRIPTION:
XS GIS Cut Line= 3
      2350175.01       13734125.        2350425.       13734125.
      2350524.98     13733875.05
#Sta/Elev= 30
    4750  466.02    4770  466.06    4810  464.92    4820  465.08    4830  463.75
    4840  463.03    4860  462.96    4890  460.98    4910  460.22    4970  459.24
    4980  458.47    4990     457  4997.5  452.98  5009.4  452.48  5014.8   449.8
  5019.1  449.56  5019.5  449.06  5023.6  449.06  5023.9  449.56  5032.3  450.28
    5039  453.06  5044.4   457.7  5053.8  458.81  5122.5  461.58    5140  461.66
  5146.7   462.4  5152.1  462.02  5236.9   466.6  5259.8  467.16  5269.2  467.83
#Mann= 3 ,-1 , 0
    4750     .12       0  5019.1     .05       0  5023.9     .12       0
Bank Sta=5019.1,5023.9
XS Rating Curve= 0 ,0
Exp/Cntr=0.3,0.1

Type RM Length L Ch R = 1 ,33203   ,464,464,464
BEGIN DESCRIPTION:
GUADALUPE TRIBUTARY 2 23.0
END DESCRIPTION:
XS GIS Cut Line= 3
      2350033.21     13734906.85        2350675.       13734425.
      2351074.98     13734025.02
#Sta/Elev= 30
  4197.6  475.35  4392.9  472.67  4542.9  468.35  4622.1  464.85  4715.7  462.73
  4742.9  461.82  4786.6  458.66  4836.6   457.4    4922  453.33  4942.9  453.11
    4972  450.12  4978.3  448.54  4986.6  448.31  4994.4  446.32  4994.8  445.82
  4999.6  446.32  5003.7  446.32  5014.3  449.03  5028.4  449.78  5042.6  454.01
  5056.7  455.87  5127.4  455.12  5141.6  453.03  5155.7  449.26  5169.9  453.82
    5184  455.78  5248.8  459.36  5268.8  460.07  5306.9  462.91  5565.8  482.56
#Mann= 6 ,-1 , 0
  4197.6     .05       0  4715.7     .12       0  4994.4     .05       0
  4999.6     .12       0  5248.8     .07       0  5306.9     .12       0
Bank Sta=4994.4,4999.6
XS Rating Curve= 0 ,0
Exp/Cntr=0.3,0.1

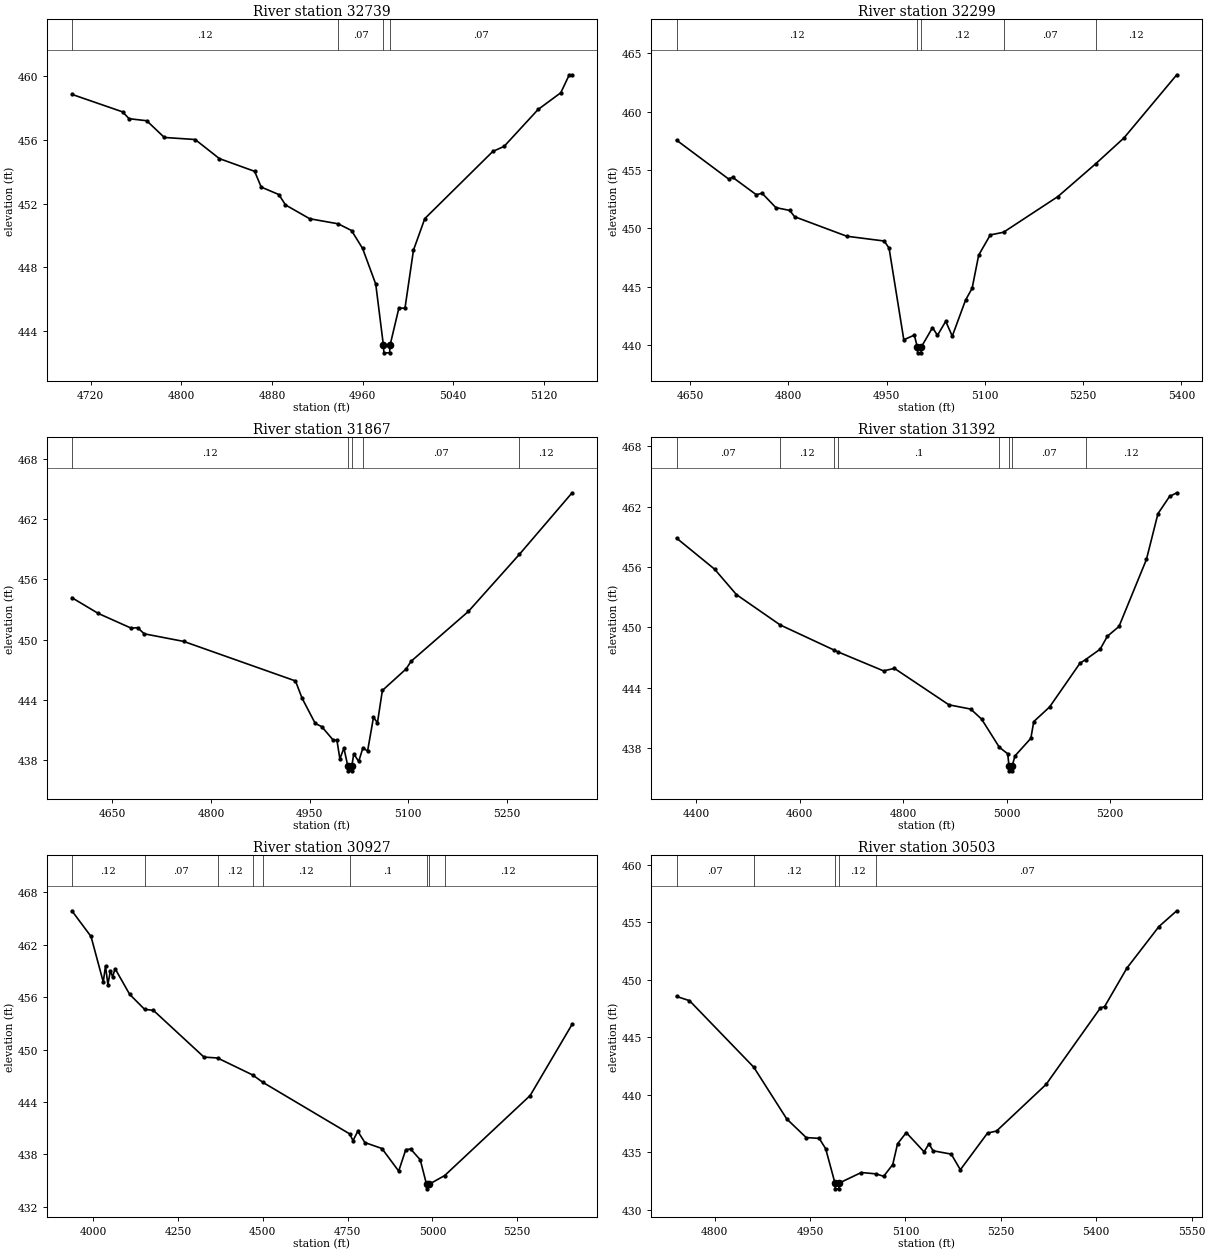
Type RM Length L Ch R = 1 ,32739   ,440,440,440
BEGIN DESCRIPTION:
GUADALUPE TRIBUTARY 2 22.0
END DESCRIPTION:
XS GIS Cut Line= 3
      2350925.01     13734724.99        2351075.       13734475.
        2351075.     13734325.04
#Sta/Elev= 30
  4703.4  458.87  4748.1  457.77  4753.9  457.34  4769.5  457.21    4785  456.16
  4812.2  456.03  4833.6  454.83  4864.7  454.03  4870.5  453.04  4886.1  452.57
  4891.9  451.92  4913.3  451.05  4938.5  450.73  4950.2  450.31    4960  449.18
  4971.6  446.94  4978.3  443.12  4978.8  442.62  4983.8  442.62  4984.3  443.12
    4992  445.43  4997.4  445.43  5004.9  449.08  5014.9  451.06  5074.9  455.28
  5084.9   455.6  5114.9  457.92  5134.9  458.97  5142.4   460.1  5144.9   460.1
#Mann= 4 ,-1 , 0
  4703.4     .12       0  4938.5     .07       0  4978.3     .05       0
  4984.3     .07       0
Bank Sta=4978.3,4984.3
XS Rating Curve= 0 ,0
Exp/Cntr=0.3,0.1

Type RM Length L Ch R = 1 ,32299   ,432,432,432
BEGIN DESCRIPTION:
GUADALUPE TRIBUTARY 2 21.0
END DESCRIPTION:
XS GIS Cut Line= 3
      2351074.99     13734825.01        2351375.       13734625.
        2351425.     13734224.98
#Sta/Elev= 30
  4629.3  457.55  4708.9  454.22  4714.9  454.37    4751  452.88    4760     453
    4781  451.77  4802.1  451.53  4809.6  450.99  4889.2  449.32  4946.3  448.91
  4953.8   448.3  4976.3  440.45  4992.4  440.85  4996.9  439.83  4997.4  439.33
  5002.5  439.33    5003  439.83  5020.1  441.49  5027.7  440.83  5040.3  442.03
  5050.3  440.76  5070.5  443.84  5080.6  444.86  5090.6   447.7  5108.3  449.43
  5128.5  449.66  5211.6  452.72  5269.3  455.53  5312.4  457.74    5393  463.15
#Mann= 5 ,-1 , 0
  4629.3     .12       0  4996.9     .05       0    5003     .12       0
  5128.5     .07       0  5269.3     .12       0
Bank Sta=4996.9,5003
XS Rating Curve= 0 ,0
Exp/Cntr=0.3,0.1

Type RM Length L Ch R = 1 ,31867   ,475,475,475
BEGIN DESCRIPTION:
GUADALUPE TRIBUTARY 2 20.0
END DESCRIPTION:
XS GIS Cut Line= 3
      2351174.96       13734925.        2351575.       13734925.
      2351875.01       13734725.
#Sta/Elev= 30
  4588.4  454.18  4628.4  452.61  4678.4  451.14  4688.4  451.18  4698.4  450.57
  4758.4  449.81  4928.4  445.86  4938.4  444.14  4958.4  441.62  4968.4  441.29
  4985.9  439.94  4991.4  439.94  4995.9  438.07    5002  439.15  5007.9  437.38
  5008.4  436.88  5013.6  436.88  5014.1  437.38    5017  438.58  5024.5  437.82
    5031  439.19    5038  438.85    5047  442.23    5053  441.68  5060.5  444.91
  5096.6  447.06  5104.1  447.82  5191.2   452.8    5269  458.52    5349  464.66
#Mann= 5 ,-1 , 0
  4588.4     .12       0  5007.9     .05       0  5014.1     .12       0
    5031     .07       0    5269     .12       0
Bank Sta=5007.9,5014.1
XS Rating Curve= 0 ,0
Exp/Cntr=0.3,0.1

Type RM Length L Ch R = 1 ,31392   ,465,465,465
BEGIN DESCRIPTION:
GUADALUPE TRIBUTARY 2 19.0
END DESCRIPTION:
XS GIS Cut Line= 3
      2351274.99       13735475.        2351875.       13735275.
      2352175.02     13735124.99
#Sta/Elev= 30
  4361.4  458.88  4435.2  455.78  4477.4  453.25  4562.1  450.23  4666.4  447.73
  4672.9  447.57    4762  445.66    4783  445.91  4888.5  442.28  4930.6  441.86
  4951.7  440.86  4986.1  438.05  5002.2  437.41  5004.7  436.21  5005.2  435.71
  5010.5  435.71    5011  436.21  5016.2  437.19    5047  438.95  5052.6  440.61
  5083.3  442.07    5142  446.42  5152.8  446.78  5181.1  447.82  5195.1  449.11
  5217.5  450.08  5270.6  456.75  5292.9  461.31  5315.3  463.02  5329.3  463.39
#Mann= 8 ,-1 , 0
  4361.4     .07       0  4562.1     .12       0  4666.4     .07       0
  4672.9      .1       0  4986.1     .07       0  5004.7     .05       0
    5011     .07       0  5152.8     .12       0
Bank Sta=5004.7,5011
XS Rating Curve= 0 ,0
Exp/Cntr=0.3,0.1

Type RM Length L Ch R = 1 ,30927   ,424,424,424
BEGIN DESCRIPTION:
GUADALUPE TRIBUTARY 2 18.0
END DESCRIPTION:
XS GIS Cut Line= 3
      2351324.97     13736325.03        2352125.       13735625.
      2352225.01     13735224.96
#Sta/Elev= 30
  3936.7  465.86  3993.2  462.92  4029.3  457.72  4035.9  459.55    4043  457.42
  4050.2  458.98  4056.8  458.34  4064.4  459.23  4107.1  456.31    4151   454.6
  4177.3  454.47  4326.4  449.13  4366.4  449.03  4469.8  447.09  4500.7  446.23
  4756.1  440.35  4765.8  439.58    4780  440.65  4800.9  439.36  4851.2  438.68
  4900.6   436.1  4921.5  438.55  4935.7  438.63  4964.2  437.39  4982.8  434.57
  4983.3  434.07  4989.2  434.57  5036.3  435.59  5288.4  444.74  5412.1  452.88
#Mann= 9 ,-1 , 0
  3936.7     .12       0    4151     .07       0  4366.4     .12       0
  4469.8     .07       0  4500.7     .12       0  4756.1      .1       0
  4982.8     .05       0  4989.2      .1       0  5036.3     .12       0
Bank Sta=4982.8,4989.2
XS Rating Curve= 0 ,0
Exp/Cntr=0.3,0.1

Type RM Length L Ch R = 1 ,30503   ,477,477,477
BEGIN DESCRIPTION:
GUADALUPE TRIBUTARY 2 17.0
END DESCRIPTION:
XS GIS Cut Line= 3
      2352375.01     13736124.96        2352425.       13735875.
      2352774.99     13735475.01
#Sta/Elev= 30
  4740.2  448.54  4760.6  448.17  4861.7  442.38  4913.5  437.88  4944.1  436.26
  4964.5  436.19  4974.7  435.29  4989.3   432.3  4989.8   431.8  4995.3   431.8
  4995.8   432.3  5030.7  433.22  5054.1   433.1  5065.8  432.89  5080.1  433.91
  5087.7  435.72  5101.4  436.69  5129.4  435.02    5137  435.71  5143.6  435.11
  5172.1  434.82  5186.4  433.46  5229.1  436.65  5243.3  436.83  5321.1  440.88
  5406.6  447.54  5413.2  447.66  5448.3  451.01  5498.6  454.62  5526.6  455.99
#Mann= 5 ,-1 , 0
  4740.2     .07       0  4861.7     .12       0  4989.3     .05       0
  4995.8     .12       0  5054.1     .07       0
Bank Sta=4989.3,4995.8
XS Rating Curve= 0 ,0
Exp/Cntr=0.3,0.1

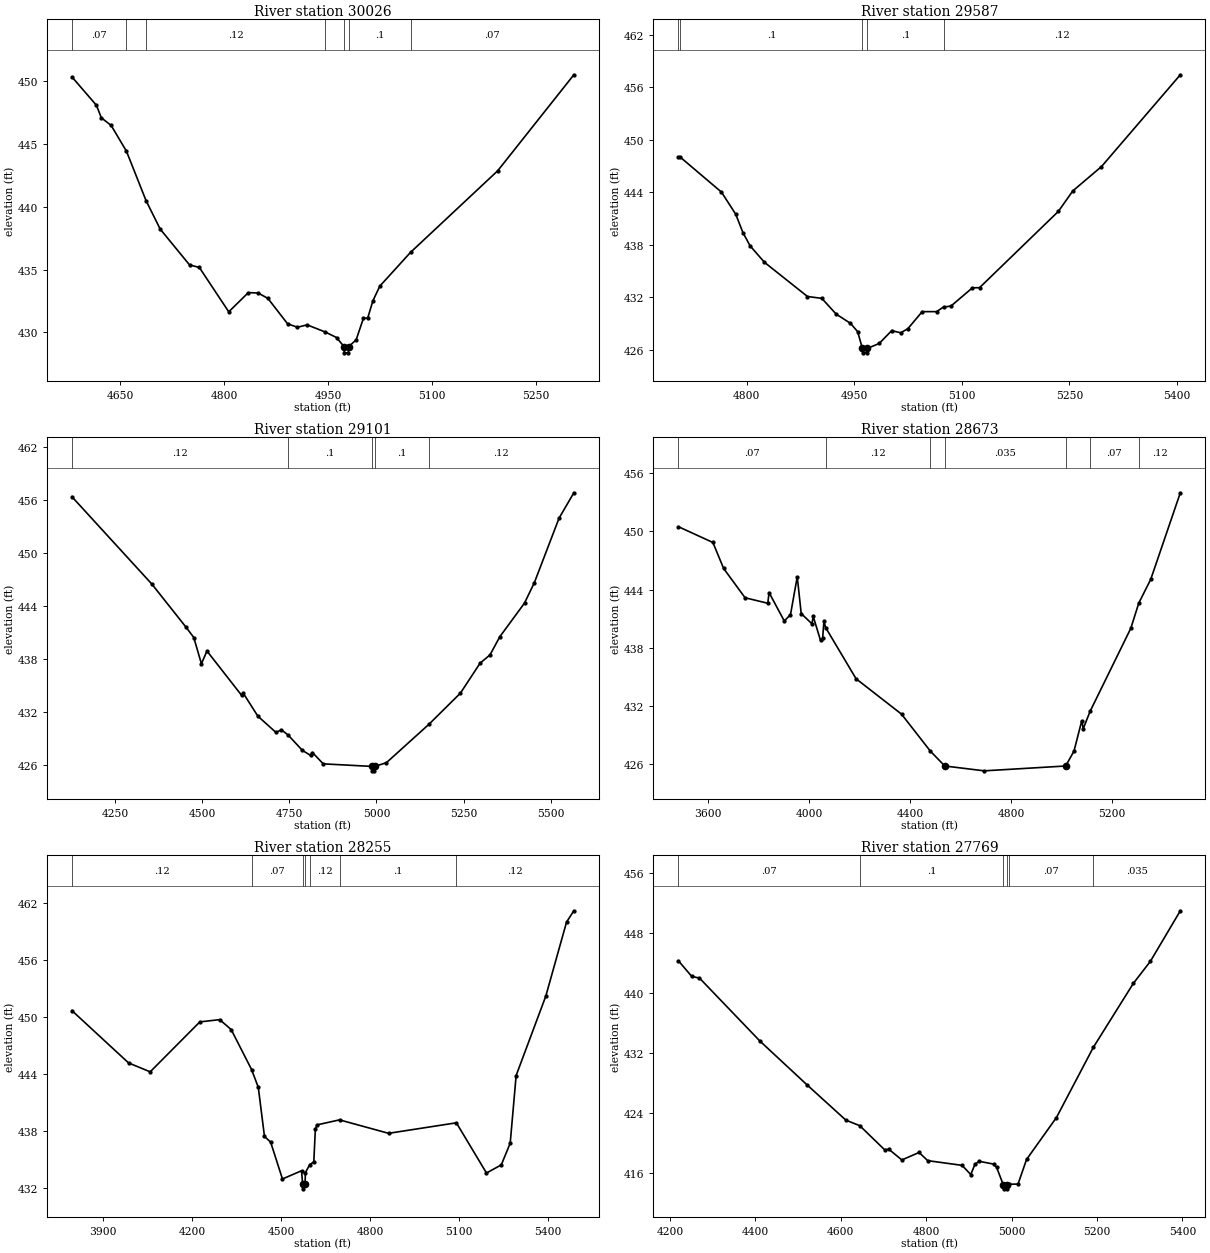
Type RM Length L Ch R = 1 ,30026   ,439,439,439
BEGIN DESCRIPTION:
GUADALUPE TRIBUTARY 2 16.0
END DESCRIPTION:
XS GIS Cut Line= 3
      2352575.01     13736174.99        2352875.       13735875.
        2352875.     13735574.95
#Sta/Elev= 30
    4580  450.36  4615.3   448.1  4622.4   447.1  4636.6  446.49  4658.7  444.43
  4686.9   440.5  4707.3  438.23  4749.7  435.37  4763.8  435.17  4806.3  431.63
  4834.5  433.16  4848.7  433.13  4862.8   432.7  4891.1  430.68  4905.3   430.4
  4919.4  430.59  4945.6  430.02  4961.8  429.58  4972.6  428.86  4973.1  428.36
  4978.8  428.36  4979.3  428.86  4990.1  429.39  5000.7  431.13  5006.8  431.13
  5014.3  432.51  5024.3  433.68  5068.6  436.37  5194.3  442.87  5304.3  450.53
#Mann= 7 ,-1 , 0
    4580     .07       0  4658.7      .1       0  4686.9     .12       0
  4945.6      .1       0  4972.6     .05       0  4979.3      .1       0
  5068.6     .07       0
Bank Sta=4972.6,4979.3
XS Rating Curve= 0 ,0
Exp/Cntr=0.3,0.1

Type RM Length L Ch R = 1 ,29587   ,486,486,486
BEGIN DESCRIPTION:
GUADALUPE TRIBUTARY 2 15.0
END DESCRIPTION:
XS GIS Cut Line= 3
      2352624.98       13736225.        2352925.       13736225.
      2353324.98       13736225.
#Sta/Elev= 30
  4704.7     448  4707.3  447.99  4764.7     444  4784.7  441.46  4794.7  439.36
  4804.7  437.85  4824.7  435.97  4884.7  432.06  4904.7  431.85  4924.7  430.05
  4944.7  428.99  4954.7  428.04  4961.3  426.12  4961.8  425.62  4967.6  425.62
  4968.1  426.12  4984.7  426.69  5002.2  428.16  5014.7  427.91  5024.7  428.38
  5044.7  430.33  5064.7  430.33  5074.5  430.86  5084.7  430.96  5114.7  433.05
  5124.7  433.07  5234.7   441.8  5254.7  444.13  5294.7  446.91  5404.7  457.41
#Mann= 5 ,-1 , 0
  4704.7     .07       0  4707.3      .1       0  4961.3     .05       0
  4968.1      .1       0  5074.5     .12       0
Bank Sta=4961.3,4968.1
XS Rating Curve= 0 ,0
Exp/Cntr=0.3,0.1

Type RM Length L Ch R = 1 ,29101   ,428,428,428
BEGIN DESCRIPTION:
GUADALUPE TRIBUTARY 2 14.0
END DESCRIPTION:
XS GIS Cut Line= 3
      2352125.02     13737024.99        2352925.       13736675.
      2353325.02     13736274.98
#Sta/Elev= 30
  4127.1  456.32  4356.3  446.43  4454.5  441.54  4476.4  440.39  4498.2  437.42
  4514.2  438.86  4613.2  433.86  4618.7  434.06    4660  431.49  4712.2  429.64
  4727.4  429.95  4746.9  429.35  4787.8  427.61  4811.2  427.05  4816.7  427.37
  4847.5  426.09  4987.9   425.8  4988.4   425.3  4994.3   425.3  4994.8   425.8
  5028.6  426.22  5150.3  430.56  5240.7  434.09  5297.3  437.49  5325.6  438.42
  5353.8  440.48  5424.6  444.29  5452.8   446.6  5523.5  453.89    5566  456.77
#Mann= 5 ,-1 , 0
  4127.1     .12       0  4746.9      .1       0  4987.9     .05       0
  4994.8      .1       0  5150.3     .12       0
Bank Sta=4987.9,4994.8
XS Rating Curve= 0 ,0
Exp/Cntr=0.3,0.1

Type RM Length L Ch R = 1 ,28673   ,418,418,418
BEGIN DESCRIPTION:
GUADALUPE TRIBUTARY 2 13.0
END DESCRIPTION:
XS GIS Cut Line= 3
      2352928.99     13738353.88        2353275.       13736875.
      2353524.99     13736475.01
#Sta/Elev= 30
  3481.3  450.49  3618.1  448.86  3660.6  446.18  3745.6  443.16  3835.7  442.59
  3840.8  443.69  3901.2  440.76  3925.8  441.42  3952.6  445.32  3968.3  441.53
  4010.8  440.47  4015.9  441.23    4045  438.75  4053.3     439  4058.4  440.73
  4065.4  440.07  4185.9   434.8  4366.1  431.15  4480.6  427.33  4537.7   425.8
  4694.1   425.3  5017.1   425.8  5050.2  427.34  5080.9  430.47  5086.8  429.65
  5113.8  431.43  5275.5  440.01  5307.1  442.61  5354.5  445.06  5471.8  453.99
#Mann= 7 ,-1 , 0
  3481.3     .07       0  4065.4     .12       0  4480.6     .12       0
  4537.7    .035       0  5017.1      .1       0  5113.8     .07       0
  5307.1     .12       0
Bank Sta=4537.7,5017.1
XS Rating Curve= 0 ,0
Exp/Cntr=0.3,0.1

Type RM Length L Ch R = 1 ,28255   ,486,486,486
BEGIN DESCRIPTION:
GUADALUPE TRIBUTARY 2 12.0
END DESCRIPTION:
XS GIS Cut Line= 3
      2353370.81     13738078.27       2353611.4     13737251.51
      2353602.65     13736420.41
#Sta/Elev= 30
  3795.3  450.68  3986.2  445.16  4059.1  444.22  4226.4  449.49  4293.4  449.73
  4332.2  448.68  4401.1  444.45  4423.6  442.58  4444.4   437.4  4465.2   436.8
    4505  432.91  4569.4  433.78  4573.1  432.37  4573.6  431.87  4581.2  432.37
  4582.4  433.58  4597.1  434.43  4610.7  434.71  4615.9  438.14  4621.5  438.62
  4697.4  439.15  4862.9  437.73  5091.4  438.84  5192.9  433.54  5242.9   434.4
  5272.9  436.69  5292.9  443.83  5392.9  452.21  5462.9  460.03  5487.5  461.22
#Mann= 7 ,-1 , 0
  3795.3     .12       0  4401.1     .07       0  4573.1     .05       0
  4581.2     .07       0  4597.1     .12       0  4697.4      .1       0
  5091.4     .12       0
Bank Sta=4573.1,4581.2
XS Rating Curve= 0 ,0
Exp/Cntr=0.3,0.1

Type RM Length L Ch R = 1 ,27769   ,473,473,473
BEGIN DESCRIPTION:
GUADALUPE TRIBUTARY 2 11.0
END DESCRIPTION:
XS GIS Cut Line= 3
      2353926.35     13737793.92        2354025.       13737025.
        2354025.     13736625.02
#Sta/Elev= 30
  4219.7  444.29  4251.1   442.2    4269  441.99  4410.4   433.6  4521.1  427.74
  4611.8  423.05  4644.3  422.31  4702.5   419.1  4712.6  419.16  4742.9  417.74
  4783.2  418.74  4803.4  417.65    4884  417.02  4904.2  415.79  4914.3   417.2
  4924.3  417.56  4957.6  417.19  4964.7  416.76  4980.7  414.39  4981.2  413.89
  4988.4  413.89  4988.9  414.39  4994.3   414.5  5014.9  414.53  5034.9  417.81
  5104.9   423.4  5191.2  432.75  5284.9  441.28  5324.9  444.23  5394.9  450.96
#Mann= 6 ,-1 , 0
  4219.7     .07       0  4644.3      .1       0  4980.7     .05       0
  4988.9      .1       0  4994.3     .07       0  5191.2    .035       0
Bank Sta=4980.7,4988.9
XS Rating Curve= 0 ,0
Exp/Cntr=0.3,0.1

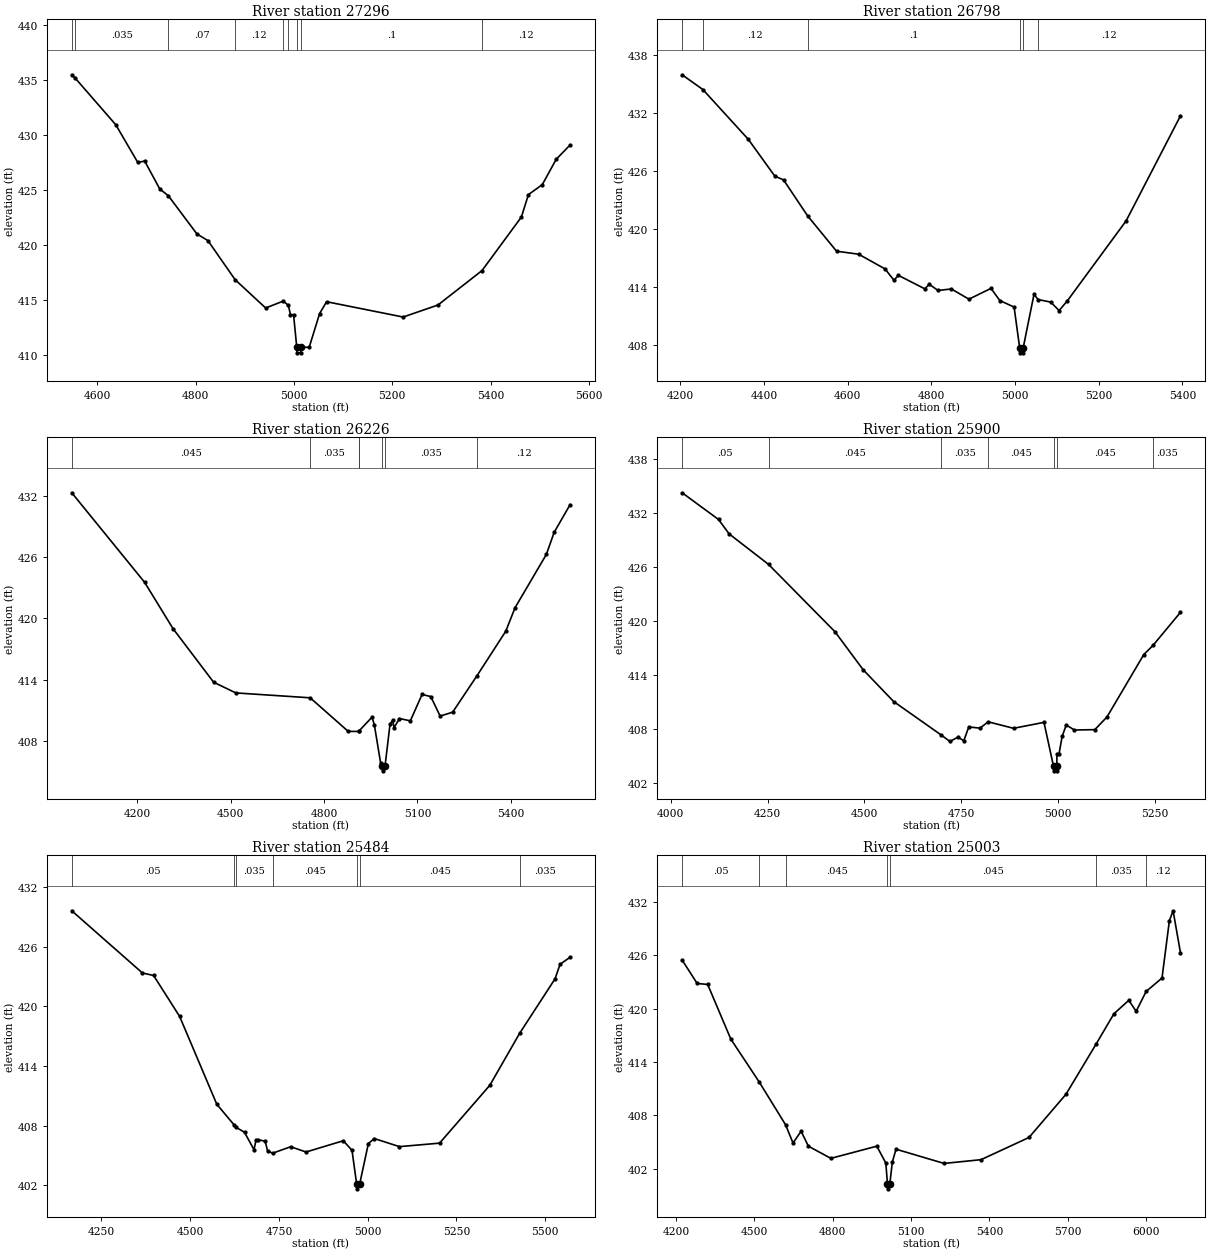
Type RM Length L Ch R = 1 ,27296   ,498,498,498
BEGIN DESCRIPTION:
GUADALUPE TRIBUTARY 2 10.0
END DESCRIPTION:
XS GIS Cut Line= 3
      2354174.99     13737725.02        2354375.       13737325.
      2354774.98     13736925.02
#Sta/Elev= 30
  4548.5  435.46    4555  435.18    4638  430.92  4682.7   427.5  4696.7  427.63
  4727.4  425.09  4744.6  424.49  4802.9  421.01  4825.2  420.41  4880.5  416.86
  4942.6  414.29  4978.5  414.92  4988.9  414.52  4992.9  413.68  4999.3  413.68
  5005.8  410.72  5006.3  410.22  5013.5  410.22    5014  410.72  5031.1  410.73
  5052.3  413.79  5066.4  414.86    5222  413.47  5292.7  414.56  5382.4  417.69
  5462.4  422.55  5476.6  424.58  5504.9  425.49  5533.1  427.79  5561.4  429.09
#Mann= 9 ,-1 , 0
  4548.5     .12       0    4555    .035       0  4744.6     .07       0
  4880.5     .12       0  4978.5     .07       0  4988.9      .1       0
  5005.8     .05       0    5014      .1       0  5382.4     .12       0
Bank Sta=5005.8,5014
XS Rating Curve= 0 ,0
Exp/Cntr=0.3,0.1

Type RM Length L Ch R = 1 ,26798   ,572,572,572
BEGIN DESCRIPTION:
GUADALUPE TRIBUTARY 2 9.0
END DESCRIPTION:
XS GIS Cut Line= 3
        2354625.       13738075.        2354875.       13737325.
        2354875.     13736924.97
#Sta/Elev= 30
  4204.9  435.95  4254.4  434.42    4363  429.26  4426.3  425.45  4447.3  425.05
  4504.5  421.34  4573.8  417.67  4626.5  417.36  4689.8  415.83  4710.9  414.66
  4721.4  415.17  4784.7  413.77  4795.2  414.24  4816.3   413.6  4847.9  413.76
  4890.1   412.7  4942.8  413.82  4963.8  412.56    4998  411.88  5011.3  407.64
  5011.8  407.14  5019.1  407.14  5019.6  407.64  5045.5   413.2  5055.4  412.66
  5085.5   412.4  5105.5  411.52  5125.5  412.55  5265.5  420.81  5395.5   431.7
#Mann= 6 ,-1 , 0
  4204.9     .07       0  4254.4     .12       0  4504.5      .1       0
  5011.3     .05       0  5019.6      .1       0  5055.4     .12       0
Bank Sta=5011.3,5019.6
XS Rating Curve= 0 ,0
Exp/Cntr=0.3,0.1

Type RM Length L Ch R = 1 ,26226   ,326,326,326
BEGIN DESCRIPTION:
GUADALUPE TRIBUTARY 2 8.0
END DESCRIPTION:
XS GIS Cut Line= 3
      2355524.13     13738226.59      2355372.46     13737150.44
      2355336.43      13736638.8
#Sta/Elev= 30
  3990.3  432.32  4224.2  423.54  4315.1  419.01  4445.6  413.75  4516.7   412.7
  4755.6  412.22  4877.6  408.93    4911  408.92  4911.9  408.95  4953.9  410.32
  4961.4  409.59  4981.6  405.86  4987.4  405.56  4987.9  405.06    4996  405.56
  5011.9  409.63    5020  410.01    5025   409.3  5042.2  410.19  5077.1  409.96
  5114.8  412.55  5142.7  412.34  5172.8  410.43  5212.9  410.81  5291.2  414.39
  5383.3  418.74  5413.4  421.06  5513.6  426.27  5538.9  428.45    5590  431.16
#Mann= 7 ,-1 , 0
  3990.3    .045       0  4755.6    .035       0    4911    .045       0
  4911.9    .035       0  4987.4    .035       0    4996    .035       0
  5291.2     .12       0
Bank Sta=4987.4,4996
XS Rating Curve= 0 ,0
Exp/Cntr=0.3,0.1

Type RM Length L Ch R = 1 ,25900   ,416,416,416
BEGIN DESCRIPTION:
GUADALUPE TRIBUTARY 2 7.0
END DESCRIPTION:
XS GIS Cut Line= 3
      2356224.99     13737924.98        2355675.       13737125.
      2355575.01     13736825.03
#Sta/Elev= 30
  4029.2  434.27  4123.2   431.3  4150.5   429.7  4252.2  426.31  4423.6  418.83
  4496.7  414.59  4575.3  411.06  4697.7  407.35  4720.6  406.62  4741.6   407.1
  4756.5  406.69  4769.4  408.23  4798.4   408.1  4819.6   408.8    4885  408.08
  4963.6  408.74  4988.3  403.85  4988.8  403.35  4996.4  403.35  4996.9  403.85
    4997  405.25  5002.6  405.25  5010.5  407.17  5021.1  408.45  5042.2  407.89
  5094.9  407.93  5126.5  409.35  5221.4  416.28    5245  417.29  5316.2  420.98
#Mann= 7 ,-1 , 0
  4029.2     .05       0  4252.2    .045       0  4697.7    .035       0
  4819.6    .045       0  4988.3    .045       0  4996.9    .045       0
    5245    .035       0
Bank Sta=4988.3,4996.9
XS Rating Curve= 0 ,0
Exp/Cntr=0.3,0.1

Type RM Length L Ch R = 1 ,25484   ,481,481,481
BEGIN DESCRIPTION:
GUADALUPE TRIBUTARY 2 6.0
END DESCRIPTION:
XS GIS Cut Line= 3
        2356275.     13737724.99        2356025.       13736925.
      2355625.02     13736525.02
#Sta/Elev= 30
  4166.4  429.59  4365.5  423.34  4396.9  423.09  4470.2  418.98    4575  410.15
  4623.1  408.11  4628.3  407.86    4653  407.34  4679.8  405.59  4685.5  406.58
  4690.8  406.59  4711.2  406.45    4718  405.46  4732.4  405.24    4783  405.89
  4826.4  405.36  4931.2  406.49  4955.8  405.53  4968.8  402.16  4969.3  401.66
  4977.5  402.16  5001.9  406.21  5018.7  406.71  5089.4   405.9  5202.5  406.25
    5344  412.06    5428  417.28  5527.8  422.76  5541.9  424.22  5570.2  424.92
#Mann= 7 ,-1 , 0
  4166.4     .05       0  4623.1    .045       0  4628.3    .035       0
  4732.4    .045       0  4968.8    .045       0  4977.5    .045       0
    5428    .035       0
Bank Sta=4968.8,4977.5
XS Rating Curve= 0 ,0
Exp/Cntr=0.3,0.1

Type RM Length L Ch R = 1 ,25003   ,945,945,945
BEGIN DESCRIPTION:
GUADALUPE TRIBUTARY 2 5.0
END DESCRIPTION:
XS GIS Cut Line= 3
        2356275.     13737574.98        2356475.       13736825.
      2355674.97     13736024.97
#Sta/Elev= 30
  4223.9  425.46  4281.4  422.83  4321.6  422.72  4410.2  416.57  4518.5  411.76
  4619.6  406.94  4648.2  404.88  4679.3   406.2  4707.1  404.52  4793.1  403.15
    4969  404.52  5003.6  402.62  5009.9  400.22  5010.4  399.72  5018.6  400.22
  5028.4  402.73  5042.5  404.18  5226.4  402.58  5367.8     403  5551.6   405.5
  5693.1  410.36    5808  415.99  5876.9  419.43  5933.5  420.93  5961.8   419.7
  5999.9  421.93  6060.7  423.44    6089   429.9  6103.2  431.01  6131.5  426.27
#Mann= 7 ,-1 , 0
  4223.9     .05       0  4518.5    .035       0  4619.6    .045       0
  5009.9    .045       0  5018.6    .045       0    5808    .035       0
  5999.9     .12       0
Bank Sta=5009.9,5018.6
XS Rating Curve= 0 ,0
Exp/Cntr=0.3,0.1