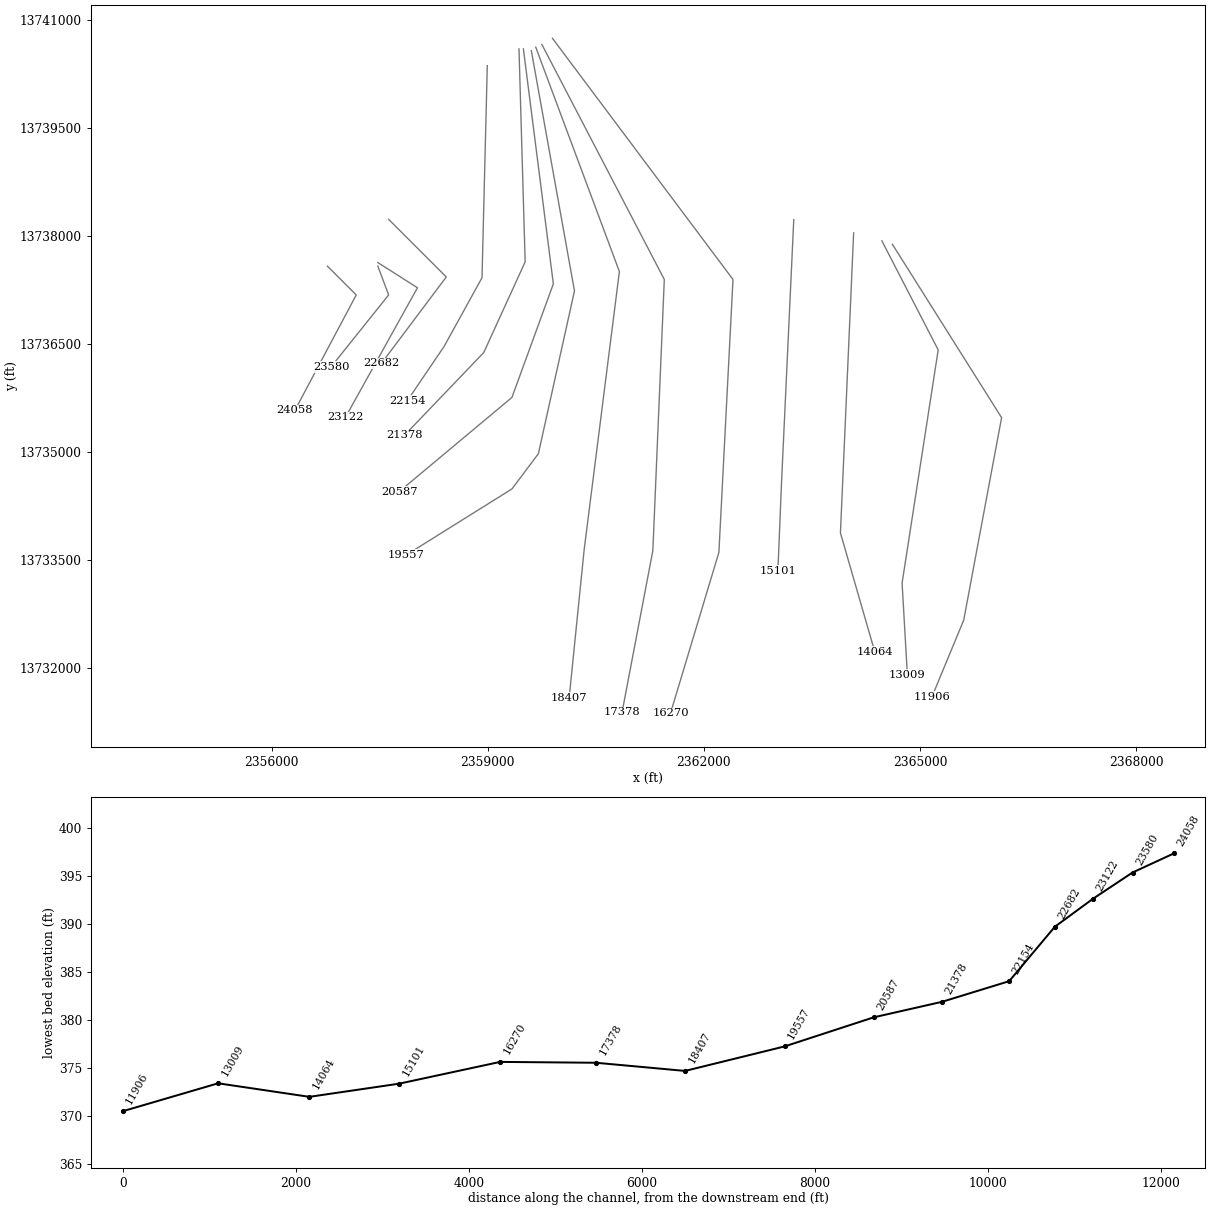
HEC-RAS study GUADALUPE TRIBUTARY 1.prj: GUADALUPE TRIBUTARY 1 Base Level Engineering

--- GUADALUPE TRIBUTARY 1.g01 (geometry) --- (continued)

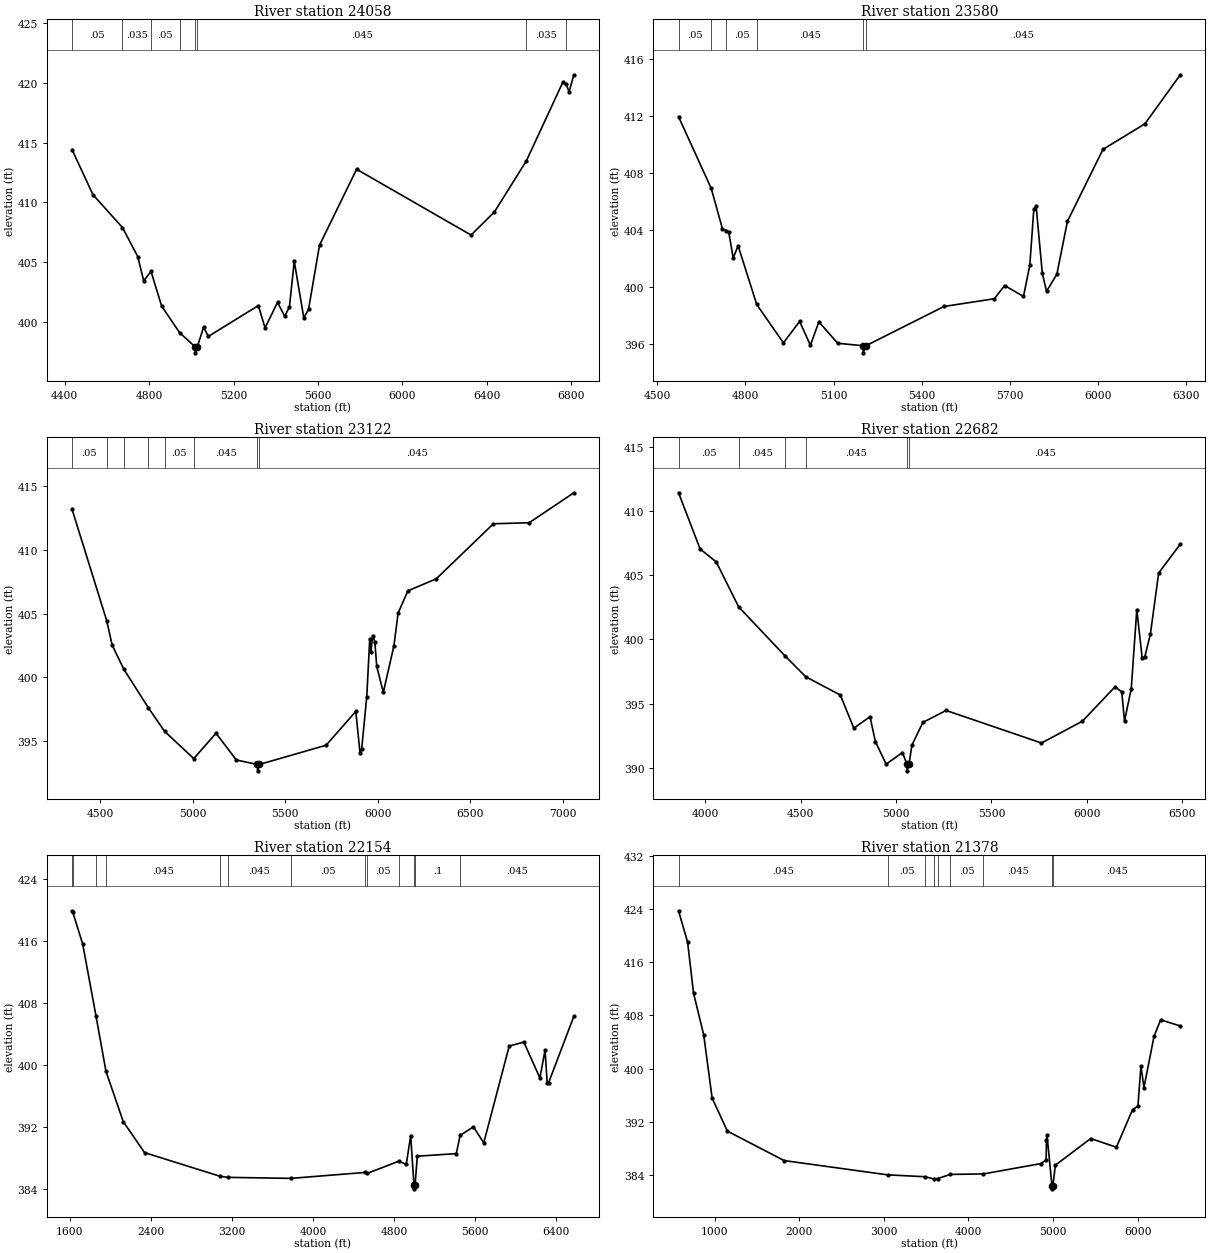
Type RM Length L Ch R = 1 ,24058   ,478,478,478
BEGIN DESCRIPTION:
GUADALUPE TRIBUTARY 2 4.0
END DESCRIPTION:
XS GIS Cut Line= 3
      2356775.02     13737574.98        2357175.       13737175.
      2356325.01     13735575.02
#Sta/Elev= 30
  4434.5   414.4  4533.5  410.63  4673.3  407.88  4745.6  405.45  4773.9  403.42
  4808.6  404.21  4858.7  401.31  4943.9  399.08  5017.9  397.89  5018.4  397.39
  5027.7  397.89  5057.9  399.55  5079.9  398.76  5317.2  401.35  5348.7  399.48
  5407.8  401.61  5442.3  400.45  5464.4  401.25  5487.1  405.06  5532.4  400.32
    5555  401.04  5606.8   406.4  5782.6  412.76    6325  407.25  6435.7  409.19
  6586.5  413.45  6759.8  420.05  6775.7  419.87  6789.3  419.25  6811.9  420.67
#Mann= 8 ,-1 , 0
  4434.5     .05       0  4673.3    .035       0  4808.6     .05       0
  4943.9    .045       0  5017.9    .045       0  5027.7    .045       0
  6586.5    .035       0  6775.7     .07       0
Bank Sta=5017.9,5027.7
XS Rating Curve= 0 ,0
Exp/Cntr=0.3,0.1

Type RM Length L Ch R = 1 ,23580   ,458,458,458
BEGIN DESCRIPTION:
GUADALUPE TRIBUTARY 2 3.0
END DESCRIPTION:
XS GIS Cut Line= 3
        2357475.       13737575.        2357625.       13737175.
      2356825.02     13736175.02
#Sta/Elev= 30
  4572.1  411.95  4683.5  406.92  4721.6  404.09  4734.2  403.96    4743  403.86
  4758.1  402.05    4775   402.9  4838.2  398.79    4929   396.1  4984.2   397.6
  5020.9  395.93  5049.7  397.57  5113.8  396.07  5200.1   395.9  5200.6   395.4
    5210   395.9  5475.5  398.65  5646.8  399.19    5682  400.12  5746.1  399.35
  5767.7  401.55  5781.3  405.49  5789.3  405.66  5810.1  400.99  5824.5  399.71
  5859.7  400.91  5895.7  404.62  6016.6  409.66  6159.1  411.45  6279.9  414.89
#Mann= 6 ,-1 , 0
  4572.1     .05       0  4683.5    .035       0  4734.2     .05       0
  4838.2    .045       0  5200.1    .045       0    5210    .045       0
Bank Sta=5200.1,5210
XS Rating Curve= 0 ,0
Exp/Cntr=0.3,0.1

Type RM Length L Ch R = 1 ,23122   ,440,440,440
BEGIN DESCRIPTION:
GUADALUPE TRIBUTARY 2 2.0
END DESCRIPTION:
XS GIS Cut Line= 3
      2357475.02     13737624.99        2358025.       13737275.
      2357025.01     13735475.02
#Sta/Elev= 30
    4348  413.17  4534.9  404.45  4564.7  402.52  4627.6  400.63  4760.6   397.6
  4847.7  395.76  5005.6  393.62  5125.7  395.61  5235.6  393.51  5349.6  393.16
  5350.1  392.66  5359.5  393.16  5720.6  394.67  5880.8  397.32  5903.6  394.09
  5912.8   394.4  5940.2  398.49  5956.3  403.03    5962  401.97  5972.3  403.27
  5983.7  402.77    5994  400.85  6029.5  398.81  6086.7  402.46  6109.5  405.03
  6162.2  406.78  6315.5  407.72  6624.3  412.04  6817.7  412.12    7059  414.47
#Mann= 8 ,-1 , 0
    4348     .05       0  4534.9    .035       0  4627.6     .05       0
  4760.6    .045       0  4847.7     .05       0  5005.6    .045       0
  5349.6     .05       0  5359.5    .045       0
Bank Sta=5349.6,5359.5
XS Rating Curve= 0 ,0
Exp/Cntr=0.3,0.1

Type RM Length L Ch R = 1 ,22682   ,528,528,528
BEGIN DESCRIPTION:
GUADALUPE TRIBUTARY 2 1.0
END DESCRIPTION:
XS GIS Cut Line= 3
        2357625.       13738225.        2358425.       13737425.
      2357524.98     13736224.98
#Sta/Elev= 30
    3859  411.44  3972.1  407.06    4057  406.04  4174.3  402.54  4415.8  398.74
    4526  397.09  4707.5  395.66  4778.2  393.08  4863.1  393.97  4891.4  392.03
  4947.9  390.27  5033.1  391.18  5057.3  390.25  5057.8  389.75  5067.2  390.25
  5083.1  391.76  5140.4  393.53  5262.2  394.46  5762.2  391.92  5976.8  393.62
  6147.7   396.3  6183.1  395.91  6197.7  393.63  6233.1  396.17  6262.2  402.33
  6290.4  398.54  6303.9  398.63  6333.1  400.39  6376.8  405.18  6490.4  407.44
#Mann= 6 ,-1 , 0
    3859     .05       0  4174.3    .045       0  4415.8    .035       0
    4526    .045       0  5057.3    .045       0  5067.2    .045       0
Bank Sta=5057.3,5067.2
XS Rating Curve= 0 ,0
Exp/Cntr=0.3,0.1

Type RM Length L Ch R = 1 ,22154   ,776,776,776
BEGIN DESCRIPTION:
A19101
END DESCRIPTION:
XS GIS Cut Line= 4
        2358994.     13740360.04      2358920.67     13737414.34
      2358395.09     13736460.97      2357881.72     13735703.14
#Sta/Elev= 30
  1622.5  419.93  1628.5  419.79  1727.6  415.63  1858.8  406.35  1957.3  399.21
  2127.7  392.74  2337.8  388.75  3079.9  385.71  3157.7  385.56  3781.7  385.43
  4508.8  386.19  4533.8  386.07  4845.4  387.64  4919.6  387.24  4963.2  390.94
  4995.5  384.58    4996  384.08  5006.6  384.58  5028.5  388.29  5413.4  388.62
  5450.5  390.96  5582.2  392.08  5683.9     390  5935.5  402.49  6079.3     403
    6238  398.38  6288.9  401.96  6309.9  397.76  6324.9  397.79  6573.1  406.33
#Mann= 13 ,-1 , 0
  1622.5    .035       0  1628.5     .05       0  1858.8    .035       0
  1957.3    .045       0  3079.9     .07       0  3157.7    .045       0
  3781.7     .05       0  4508.8    .045       0  4533.8     .05       0
  4845.4      .1       0  4995.5     .05       0  5006.6      .1       0
  5450.5    .045       0
Bank Sta=4995.5,5006.6
XS Rating Curve= 0 ,0
Exp/Cntr=0.3,0.1

Type RM Length L Ch R = 1 ,21378   ,791,791,791
BEGIN DESCRIPTION:
A19100
END DESCRIPTION:
XS GIS Cut Line= 4
      2359434.02     13740592.29      2359519.58     13737634.35
      2358945.11     13736375.41      2357845.03     13735226.43
#Sta/Elev= 30
   572.5  423.74   679.8  419.02   749.9  411.35   869.9  405.09     970  395.57
    1150  390.61  1821.1  386.18  3045.9  384.03  3490.3  383.75  3589.6  383.42
  3637.5  383.48  3787.7   384.1  4177.2  384.17  4855.5  385.72  4919.2  386.25
  4922.9  389.22  4929.9  389.97  4988.1  382.43  4988.6  381.93  4999.3  382.43
  5028.9  385.49  5446.3  389.49  5750.4  388.19  5941.3  393.84  6005.1  394.37
  6040.3  400.43  6075.9  397.15    6196   404.9  6273.7  407.34  6506.2  406.42
#Mann= 9 ,-1 , 0
   572.5    .045       0  3045.9     .05       0  3490.3     .07       0
  3589.6     .05       0  3637.5     .07       0  3787.7     .05       0
  4177.2    .045       0  4988.1    .045       0  4999.3    .045       0
Bank Sta=4988.1,4999.3
XS Rating Curve= 0 ,0
Exp/Cntr=0.3,0.1

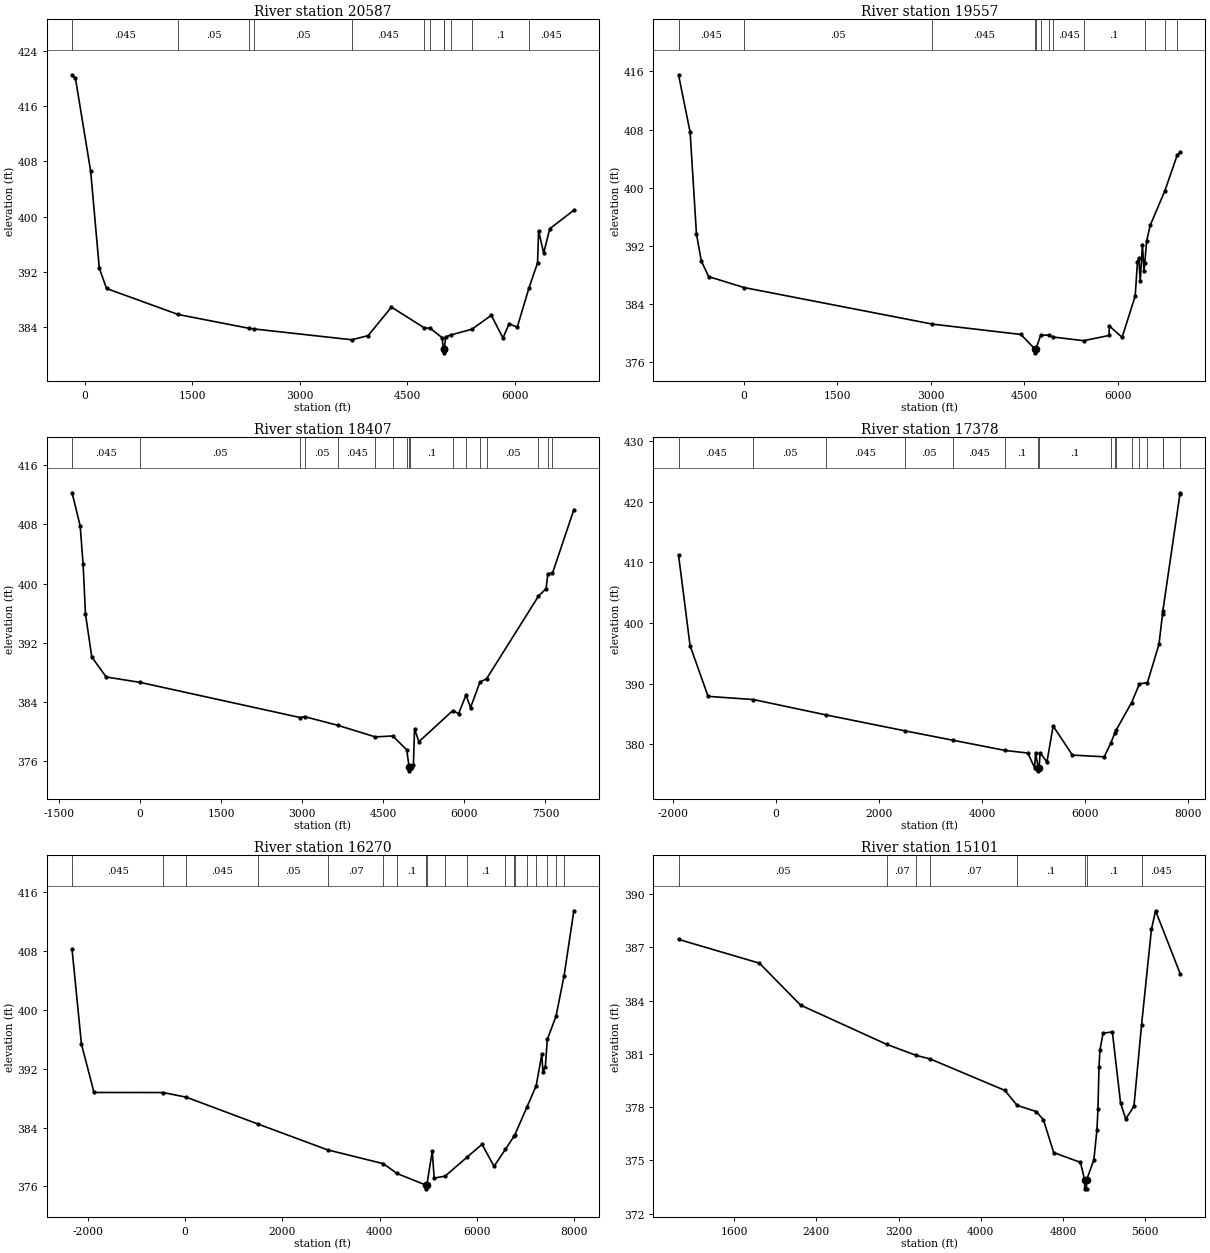
Type RM Length L Ch R = 1 ,20587   ,1030,1030,1030
BEGIN DESCRIPTION:
A19099
END DESCRIPTION:
XS GIS Cut Line= 4
      2359495.14     13740592.23      2359910.71     13737328.78
      2359336.24     13735752.05      2357771.71      13734444.2
#Sta/Elev= 30
  -180.1  420.54  -132.5  420.01    79.2  406.61   200.2  392.56     301  389.62
  1300.1  385.86  2290.6  383.86  2357.3  383.77  3726.5   382.2  3954.1   382.8
  4279.7  386.93  4733.9  383.95  4823.8  383.85    4985  382.52  5007.8  380.81
  5008.3  380.31  5019.1  380.81  5035.5  382.62  5113.7  382.91  5404.3  383.73
  5674.5  385.74  5837.2  382.45    5923  384.52  6036.3  384.02  6200.2  389.69
    6320  393.32  6334.3  397.95  6405.6  394.75  6490.4  398.27    6827  400.94
#Mann= 12 ,-1 , 0
  -180.1    .045       0  1300.1     .05       0  2290.6    .045       0
  2357.3     .05       0  3726.5    .045       0  4733.9    .035       0
  4823.8      .1       0  5007.8     .05       0  5019.1      .1       0
  5113.7    .045       0  5404.3      .1       0  6200.2    .045       0
Bank Sta=5007.8,5019.1
XS Rating Curve= 0 ,0
Exp/Cntr=0.3,0.1

Type RM Length L Ch R = 1 ,19557   ,1150,1150,1150
BEGIN DESCRIPTION:
A19098
END DESCRIPTION:
XS GIS Cut Line= 5
      2359605.14     13740567.82      2360204.06       13737231.
      2359702.92     13734969.79      2359336.24     13734480.88
      2357869.76     13733564.33
#Sta/Elev= 30
   -1044  415.54  -858.3  407.64  -756.7  393.65  -678.7  389.93  -561.1  387.77
     3.9  386.27  3027.9  381.23  4445.8  379.81  4673.4  377.78  4673.9  377.28
  4684.8  377.78  4763.4   379.7  4897.7  379.73  4968.8  379.45  5452.2  378.95
  5859.2  379.67  5865.1  380.98  6069.1  379.41  6279.1  385.11  6315.6  389.83
  6336.8  390.27  6359.7  387.14  6395.1  392.17  6418.7  388.59  6432.7  389.58
  6461.8  392.64  6519.6  394.82  6754.2  399.56  6955.2  404.54  7002.7  404.86
#Mann= 12 ,-1 , 0
   -1044    .045       0     3.9     .05       0  3027.9    .045       0
  4673.4    .045       0  4684.8    .045       0  4763.4      .1       0
  4897.7    .035       0  4968.8    .045       0  5452.2      .1       0
  6432.7    .045       0  6754.2    .035       0  6955.2     .12       0
Bank Sta=4673.4,4684.8
XS Rating Curve= 0 ,0
Exp/Cntr=0.3,0.1

Type RM Length L Ch R = 1 ,18407   ,1029,1029,1029
BEGIN DESCRIPTION:
A19097
END DESCRIPTION:
XS GIS Cut Line= 4
      2359666.25     13740616.73      2360827.42      13737499.9
      2360338.51     13733637.51      2360130.72     13731584.11
#Sta/Elev= 30
 -1257.9  412.27   -1108   407.8 -1053.3   402.6 -1010.6  395.94  -893.2   390.1
  -626.4   387.4     2.1  386.67  2964.6  381.92  3042.9  382.05  3665.9  380.86
  4352.5  379.31  4675.5  379.44  4932.8  377.57  4977.9  375.23  4978.4  374.73
  4994.6  375.23  5056.8  375.51  5077.8  380.39  5157.9  378.66  5786.3  382.87
  5893.4  382.45  6029.1  384.95  6114.7  383.28    6288  386.71  6411.6  387.17
  7368.5  398.29  7511.8  399.34    7544  401.36  7629.1   401.4  8025.3  409.99
#Mann= 17 ,-1 , 0
 -1257.9    .045       0     2.1     .05       0  2964.6    .045       0
  3042.9     .05       0  3665.9    .045       0  4352.5      .1       0
  4675.5    .045       0  4932.8      .1       0  4977.9     .05       0
  4994.6      .1       0  5786.3     .12       0  6029.1     .05       0
    6288     .07       0  6411.6     .05       0  7368.5    .035       0
    7544     .07       0  7629.1     .12       0
Bank Sta=4977.9,4994.6
XS Rating Curve= 0 ,0
Exp/Cntr=0.3,0.1

Type RM Length L Ch R = 1 ,17378   ,1108,1108,1108
BEGIN DESCRIPTION:
A19096
END DESCRIPTION:
XS GIS Cut Line= 4
      2359751.81     13740653.39      2361450.78      13737389.9
      2361291.88     13733625.29      2360864.45     13731378.19
#Sta/Elev= 30
 -1886.3  411.22 -1662.6  396.26 -1313.1  387.88  -432.5  387.35     966  384.83
  2502.6  382.19  3438.4  380.63  4455.3  378.94  4889.9  378.52  5020.7  376.09
  5040.7  378.52  5092.3  376.08  5092.8  375.58  5109.2  376.08  5128.5  378.57
  5260.9  377.04    5381  382.98  5754.6  378.18  6372.1   377.9  6499.1  380.14
  6580.4   381.9  6599.9  382.25  6902.2  386.84    7055  389.94  7210.1  390.15
  7434.2  396.48    7503  401.47  7508.5  401.95  7840.1  421.26  7848.3   421.5
#Mann= 17 ,-1 , 0
 -1886.3    .045       0  -432.5     .05       0     966    .045       0
  2502.6     .05       0  3438.4    .045       0  4455.3      .1       0
  5092.3     .05       0  5109.2      .1       0  6499.1     .12       0
  6580.4      .1       0  6599.9     .12       0  6902.2     .07       0
    7055    .035       0  7210.1     .07       0    7503     .12       0
  7508.5     .07       0  7840.1     .12       0
Bank Sta=5092.3,5109.2
XS Rating Curve= 0 ,0
Exp/Cntr=0.3,0.1

Type RM Length L Ch R = 1 ,16270   ,1169,1169,1169
BEGIN DESCRIPTION:
A19095
END DESCRIPTION:
XS GIS Cut Line= 4
       2359898.5     13740738.91      2362404.15      13737389.9
      2362208.59     13733600.84      2361536.34     13731364.08
#Sta/Elev= 30
 -2318.7  408.21 -2126.4  395.36   -1868  388.77  -446.7  388.76    28.5  388.13
  1497.9  384.49  2931.3  380.97  4078.6  379.09    4356  377.77    4954  376.17
  4954.5  375.67  4971.9  376.17  5083.1   380.8  5123.1  377.13  5348.1   377.4
  5801.1  379.99  6106.3  381.72  6353.3  378.73    6586  381.03  6760.4  382.79
    6777  382.95  7028.3  386.77  7219.1  389.68  7334.8  393.94  7358.2  391.49
  7407.9   392.3  7448.4     396  7627.1  399.13  7792.1  404.62  7993.6  413.47
#Mann= 19 ,-1 , 0
 -2318.7    .045       0  -446.7     .05       0    28.5    .045       0
  1497.9     .05       0  2931.3     .07       0  4078.6     .05       0
    4356      .1       0    4954     .05       0  4971.9      .1       0
  5348.1    .045       0  5801.1      .1       0    6586    .045       0
  6760.4     .12       0    6777      .1       0  7028.3     .05       0
  7219.1    .035       0  7448.4     .05       0  7627.1    .035       0
  7792.1     .07       0
Bank Sta=4954,4971.9
XS Rating Curve= 0 ,0
Exp/Cntr=0.3,0.1

Type RM Length L Ch R = 1 ,15101   ,1037,1037,1037
BEGIN DESCRIPTION:
A19094
END DESCRIPTION:
XS GIS Cut Line= 3
      2363247.52     13738221.03      2363076.41     13734541.99
      2363027.52      13733344.2
#Sta/Elev= 30
  1058.7  387.44  1845.6   386.1    2246  383.74  3084.6  381.53  3371.6  380.91
  3507.1  380.71  4233.5  378.94  4352.1   378.1  4538.5  377.75  4608.6  377.29
  4708.7  375.44  4968.9  374.89  5009.7   373.9  5010.2   373.4  5027.7   373.4
  5028.2   373.9    5099  375.02    5129   376.7    5139  377.87    5149  380.23
  5159.1  381.24  5189.1  382.16  5279.2  382.23  5359.2  378.23  5409.3  377.33
  5489.3  378.05  5563.3  382.63  5659.5     388  5699.5  389.05  5940.5  385.49
#Mann= 8 ,-1 , 0
  1058.7     .05       0  3084.6     .07       0  3371.6     .05       0
  3507.1     .07       0  4352.1      .1       0  5009.7     .05       0
  5028.2      .1       0  5563.3    .045       0
Bank Sta=5009.7,5028.2
XS Rating Curve= 0 ,0
Exp/Cntr=0.3,0.1

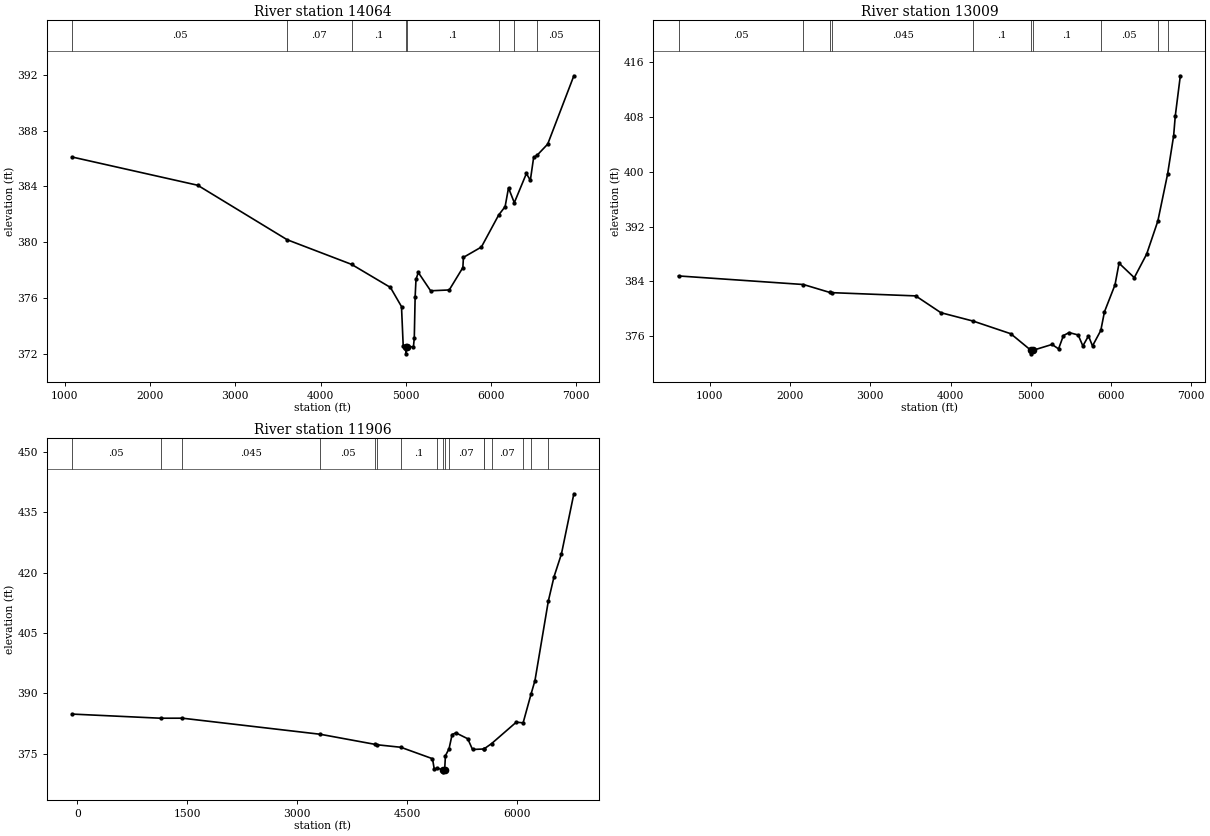
Type RM Length L Ch R = 1 ,14064   ,1055,1055,1055
BEGIN DESCRIPTION:
A19093
END DESCRIPTION:
XS GIS Cut Line= 3
      2364078.67     13738037.65      2363895.33     13733869.74
      2364371.97     13732219.85
#Sta/Elev= 30
  1083.9  386.11    2558  384.09    3609  380.19  4364.2  378.43  4820.2  376.78
  4950.3  375.41  4970.3  372.59  5000.5  372.53    5001  372.03  5020.2  372.53
  5090.4  372.54  5100.4  373.16  5110.4  376.12  5120.5  377.36  5147.5  377.85
    5292  376.54  5510.6   376.6  5670.5   378.2  5677.1  378.93  5887.9  379.67
  6090.7  381.96  6166.4  382.56  6206.1   383.9  6274.3  382.84  6416.2  384.93
  6462.3  384.44  6501.2  386.08  6539.3  386.22    6666  387.03  6973.2  391.92
#Mann= 8 ,-1 , 0
  1083.9     .05       0    3609     .07       0  4364.2      .1       0
  5000.5     .05       0  5020.2      .1       0  6090.7     .05       0
  6274.3    .035       0  6539.3     .05       0
Bank Sta=5000.5,5020.2
XS Rating Curve= 0 ,0
Exp/Cntr=0.3,0.1

Type RM Length L Ch R = 1 ,13009   ,1103,1103,1103
BEGIN DESCRIPTION:
A19092
END DESCRIPTION:
XS GIS Cut Line= 4
      2364469.79     13737927.71      2365252.06     13736412.08
      2364750.92     13733173.04      2364824.26     13731901.83
#Sta/Elev= 30
   608.8   384.8  2165.4  383.55  2495.8  382.39  2524.2  382.36  3565.8  381.89
  3879.9  379.44  4283.6  378.21  4751.5  376.37    5004  373.94  5004.5  373.44
  5023.7  373.94  5266.1  374.81  5347.1  374.16  5407.9  376.11  5478.7  376.54
    5592  376.19  5650.1  374.59  5720.2  376.05  5770.3  374.59  5873.7  376.85
  5919.4  379.57  6050.8   383.5  6101.3  386.66  6291.2  384.55  6445.2  387.98
  6584.8   392.8  6706.6  399.66    6782  405.25    6802   408.1  6865.3  413.99
#Mann= 10 ,-1 , 0
   608.8     .05       0  2165.4    .045       0  2495.8    .035       0
  2524.2    .045       0  4283.6      .1       0    5004     .05       0
  5023.7      .1       0  5873.7     .05       0  6584.8     .07       0
  6706.6     .05       0
Bank Sta=5004,5023.7
XS Rating Curve= 0 ,0
Exp/Cntr=0.3,0.1

Type RM Length L Ch R = 1 ,11906   ,1370,1370,1370
BEGIN DESCRIPTION:
A19091
END DESCRIPTION:
XS GIS Cut Line= 4
      2364616.49     13737878.79      2366132.09     13735470.92
      2365606.52     13732659.69      2365167.27     13731598.17
#Sta/Elev= 30
   -73.1  384.87  1136.6  383.84  1432.9  383.85  3316.1  379.86  4059.8  377.37
  4092.9  377.25    4417  376.63  4849.8  373.79  4873.8  371.23    4916  371.42
  4995.9  371.03  4996.4  370.53  5016.2  371.03  5026.4  374.52  5076.2  376.28
  5117.9  379.78  5168.8  380.21  5331.6  378.74  5396.5  376.08  5546.9   376.2
  5553.2  376.22  5656.3  377.53  5994.3  382.86  6087.7  382.69  6195.5   389.8
  6249.5  393.19  6432.1  412.93  6510.2  418.99  6611.1  424.62  6780.8  439.56
#Mann= 17 ,-1 , 0
   -73.1     .05       0  1136.6    .035       0  1432.9    .045       0
  3316.1     .05       0  4059.8     .07       0  4092.9     .05       0
    4417      .1       0    4916     .12       0  4995.9     .05       0
  5016.2     .12       0  5076.2     .07       0  5546.9      .1       0
  5553.2     .12       0  5656.3     .07       0  6087.7     .05       0
  6195.5     .07       0  6432.1     .05       0
Bank Sta=4995.9,5016.2
XS Rating Curve= 0 ,0
Exp/Cntr=0.3,0.1