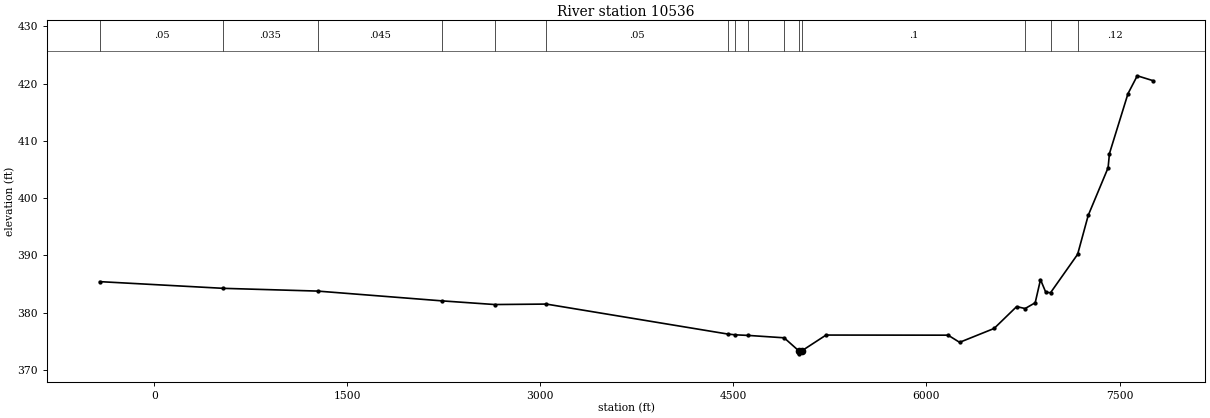
HEC-RAS study GUADALUPE TRIBUTARY 1.prj: GUADALUPE TRIBUTARY 1 Base Level Engineering

--- GUADALUPE TRIBUTARY 1.g01 (geometry) --- (continued)

Type RM Length L Ch R = 1 ,10536   ,0,0,0
BEGIN DESCRIPTION:
A19090
END DESCRIPTION:
XS GIS Cut Line= 4
      2364763.15      13737829.9      2366682.12     13734859.79
      2366828.79     13732305.23      2366328.12     13730278.11
#Sta/Elev= 30
  -424.5  385.43   536.1  384.26  1268.6  383.78  2235.9  382.07  2645.1  381.43
  3046.1  381.51  4455.2  376.28  4514.9  376.14  4613.4  376.04  4894.1  375.62
  5009.3  373.32  5009.8  372.82  5029.8  373.32  5219.9   376.1    6168  376.08
  6257.7  374.83  6525.5  377.25  6700.7  381.07  6766.6  380.73  6844.9  381.74
  6886.1  385.78  6927.3  383.56  6964.4   383.5  7174.6   390.2  7256.9     397
  7411.4  405.32  7421.9   407.8  7565.9  418.26    7638  421.38  7758.4  420.54
#Mann= 15 ,-1 , 0
  -424.5     .05       0   536.1    .035       0  1268.6    .045       0
  2235.9     .05       0  2645.1    .035       0  3046.1     .05       0
  4455.2     .07       0  4514.9     .05       0  4613.4     .12       0
  4894.1      .1       0  5009.3     .05       0  5029.8      .1       0
  6766.6    .035       0  6964.4     .07       0  7174.6     .12       0
Bank Sta=5009.3,5029.8
XS Rating Curve= 0 ,0
Exp/Cntr=0.3,0.1

Chan Stop Cuts=-1
Use User Specified Reach Order=0
Composite Channel Slope=5