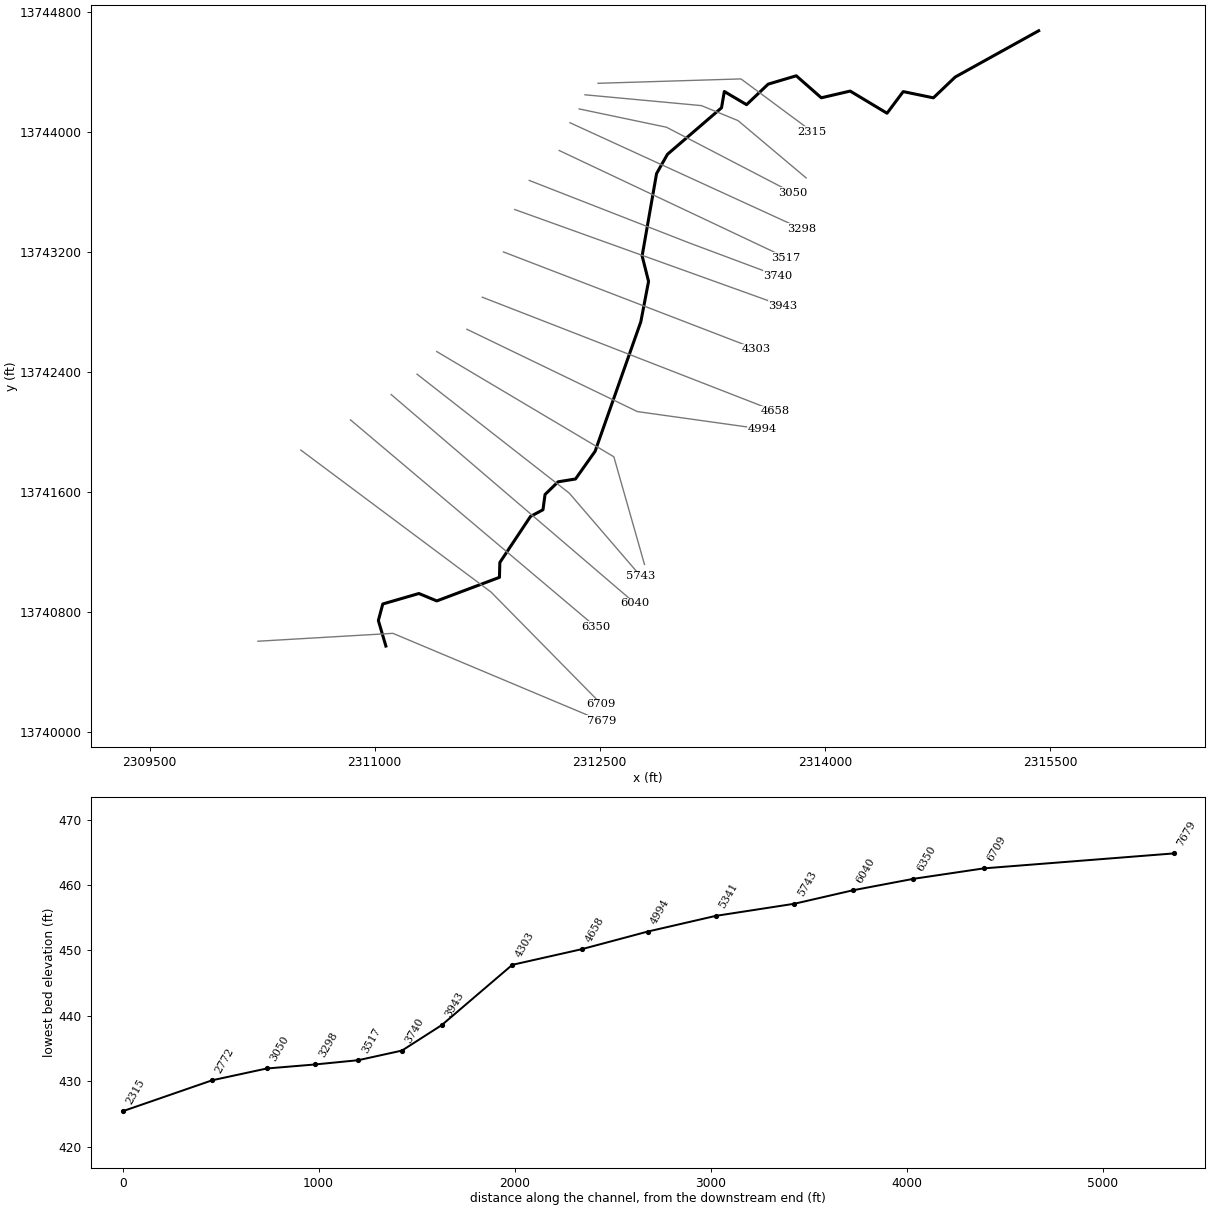
--- GUADALUPE TRIBUTARY 11 2.prj (project) ---

Proj Title=GUADALUPE TRIBUTARY 11 2 Base Level Engineering
Current Plan=p01
Default Exp/Contr=0.3,0.1
English Units
Geom File=g01
Flow File=f01
Plan File=p01
BEGIN DESCRIPTION:
GUADALUPE TRIBUTARY 11 2
END DESCRIPTION:

--- GUADALUPE TRIBUTARY 11 2.p01 (plan) ---

Plan Title=Multiple Run
Short Identifier=Multiple
Geom File=g01
Flow File=f01
Subcritical Flow
K Sum by GR= 0
Std Step Tol= 0.01
Critical Tol= 0.01
Num of Std Step Trials= 20
Max Error Tol= 0.3
Flow Tol Ratio= 0.001
Split Flow NTrial= 30
Split Flow Tol= 0.02
Split Flow Ratio= 0.02
Log Output Level= 0
Friction Slope Method= 1
Unsteady Friction Slope Method= 2
Unsteady Bridges Friction Slope Method= 1
Parabolic Critical Depth
Global Vel Dist=  1 , 1 , 1
Global Log Level= 0
CheckData=True
Encroach Param= -1, 0, 0, 0
BEGIN DESCRIPTION:
Multiple Run
END DESCRIPTION:

--- GUADALUPE TRIBUTARY 11 2.f01 (steady flow) ---

Flow Title=Multiple
Number of Profiles=7
Profile Names=10-year,25-year,50-year,1pct_min,100-year,1pct_plu,500-year
River Rch & RM= GUADALUPE TRIBUT,Reach-1,7679
     573     914    1218     786    1568    3129    2576
River Rch & RM= GUADALUPE TRIBUT,Reach-1,4658
     708    1144    1538    1000    1995    3981    3330
River Rch & RM= GUADALUPE TRIBUT,Reach-1,2315
     881    1444    1960    1287    2567    5122    4365
Boundary for River Rch & Prof#=GUADALUPE TRIBUT,Reach-1,1
Up Type=0
Dn Type=3
Dn Slope=0.005
Boundary for River Rch & Prof#=GUADALUPE TRIBUT,Reach-1,2
Up Type=0
Dn Type=3
Dn Slope=0.005
Boundary for River Rch & Prof#=GUADALUPE TRIBUT,Reach-1,3
Up Type=0
Dn Type=3
Dn Slope=0.005
Boundary for River Rch & Prof#=GUADALUPE TRIBUT,Reach-1,4
Up Type=0
Dn Type=3
Dn Slope=0.005
Boundary for River Rch & Prof#=GUADALUPE TRIBUT,Reach-1,5
Up Type=0
Dn Type=3
Dn Slope=0.005
Boundary for River Rch & Prof#=GUADALUPE TRIBUT,Reach-1,6
Up Type=0
Dn Type=3
Dn Slope=0.005
Boundary for River Rch & Prof#=GUADALUPE TRIBUT,Reach-1,7
Up Type=0
Dn Type=3
Dn Slope=0.005

--- GUADALUPE TRIBUTARY 11 2.g01 (geometry) ---

Geom Title=Existing Conditions

River Reach=GUADALUPE TRIBUT,Reach-1
Reach XY= 30
      2311075.00     13740575.00      2311024.88     13740745.11
      2311054.41     13740855.42      2311295.13     13740925.17
      2311414.31     13740875.77      2311831.80     13741032.86
      2311834.32     13741131.65      2312038.56     13741438.53
      2312121.81     13741483.35      2312135.52     13741584.77
      2312222.56     13741669.48      2312338.65     13741688.26
      2312469.16     13741872.71      2312773.78     13742735.50
      2312825.39     13743004.87      2312782.56     13743175.00
      2312878.76     13743723.44      2312951.29     13743851.82
      2313311.59     13744161.71      2313330.26     13744270.41
      2313478.34     13744182.60      2313622.57     13744319.48
      2313809.66     13744375.05      2313976.50     13744228.46
      2314168.88     13744273.18      2314414.47     13744125.47
      2314522.33     13744269.70      2314723.37     13744228.13
      2314868.94     13744366.86      2315425.00     13744675.00

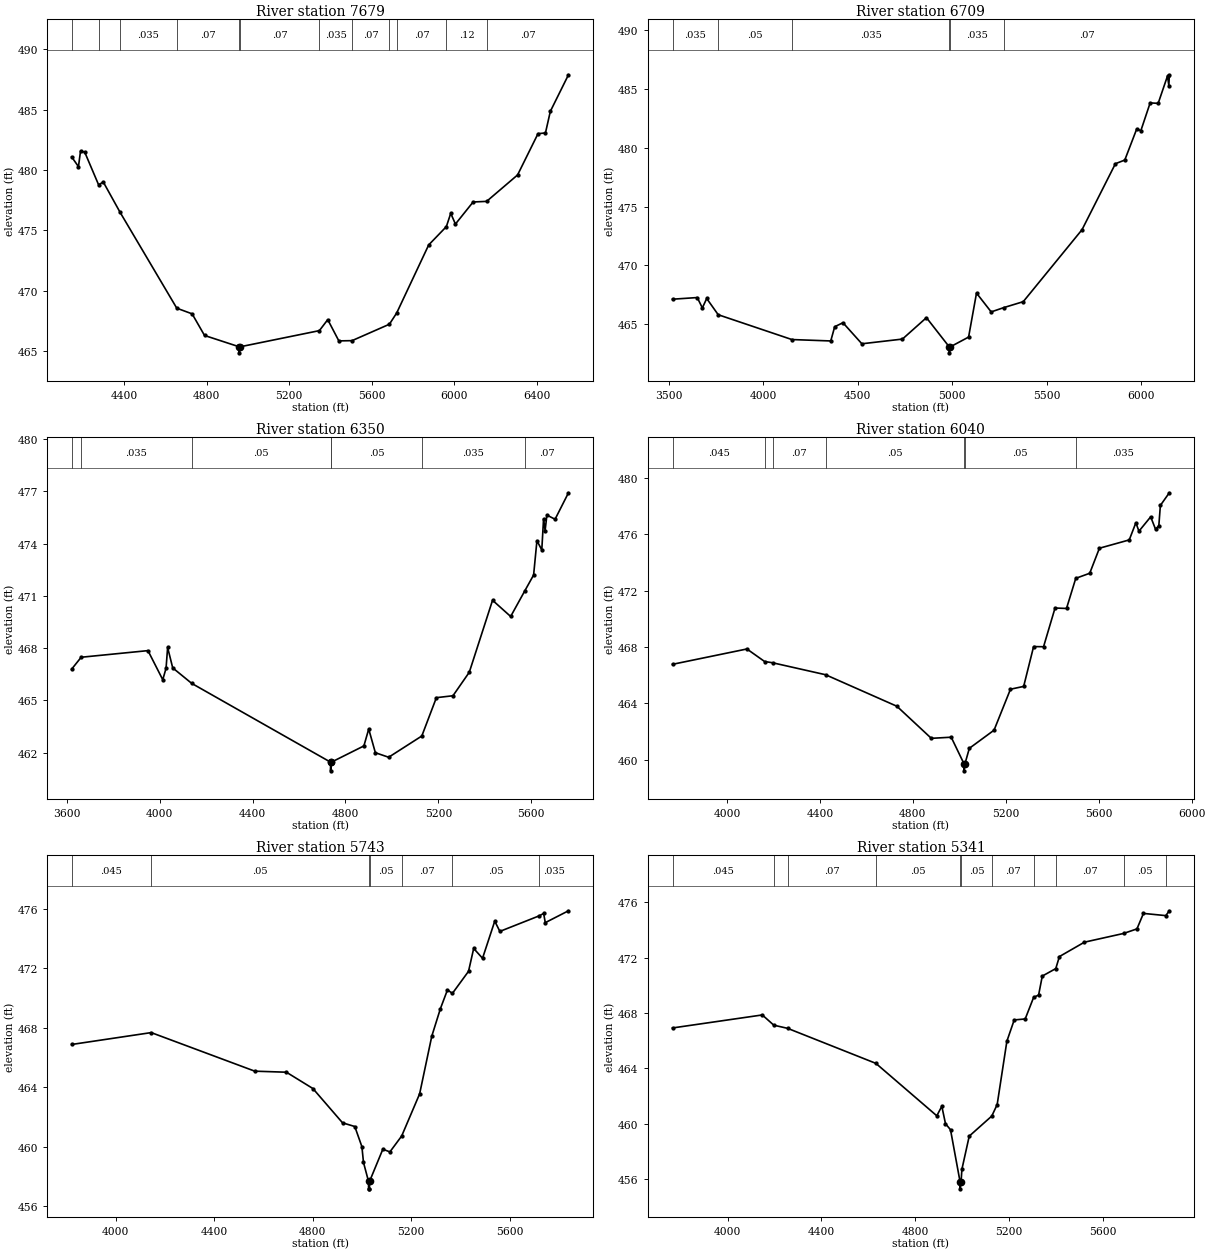
Type RM Length L Ch R = 1,7679,970,970,970
BEGIN DESCRIPTION:
GUADALUPE TRIBUTARY 11 210444
END DESCRIPTION:
XS GIS Cut Line= 3
      2310222.24     13740607.18      2311121.89     13740659.76
      2312511.16     13740076.04
#Sta/Elev= 30
  4145.8  481.08  4178.6  480.28  4188.6  481.56  4208.7  481.49  4276.3  478.77
  4298.8  479.01  4380.8  476.48  4655.2  468.55  4729.6  468.08  4789.7  466.29
  4957.9  465.35  4958.2  464.85  4961.9  465.35  5346.4  466.69  5387.0  467.60
  5440.8  465.84  5504.8  465.86  5685.8  467.22  5721.1  468.15  5876.3  473.79
  5962.0  475.31  5983.2  476.41  6005.9  475.52  6091.7  477.35  6157.1  477.40
  6307.2  479.59  6406.2  483.01  6442.3  483.07  6466.0  484.86  6553.9  487.89
#Mann=12,-1,0
  4145.8   0.035       0  4276.3    0.05       0  4380.8   0.035       0
  4655.2    0.07       0  4957.9    0.05       0  4961.9    0.07       0
  5346.4   0.035       0  5504.8    0.07       0  5685.8    0.12       0
  5721.1    0.07       0  5962.0    0.12       0  6157.1    0.07       0
Bank Sta=4957.9,4961.9
Exp/Cntr=0.3,0.1

Type RM Length L Ch R = 1,6709,359,359,359
BEGIN DESCRIPTION:
GUADALUPE TRIBUTARY 11 210443
END DESCRIPTION:
XS GIS Cut Line= 3
      2310508.45     13741880.76      2311776.19     13740934.33
      2312511.13     13740187.73
#Sta/Elev= 30
  3519.7  467.12  3650.6  467.26  3677.6  466.38  3700.6  467.18  3761.5  465.80
  4151.5  463.69  4357.3  463.57  4378.1  464.78  4421.9  465.12  4522.0  463.33
  4736.7  463.73  4863.8  465.55  4984.9  463.06  4985.1  462.56  4988.9  463.06
  5086.9  463.90  5128.8  467.64  5206.5  466.04  5274.0  466.41  5376.2  466.91
  5687.4  473.03  5864.1  478.64  5913.7  478.95  5977.3  481.61  5998.6  481.44
  6048.0  483.81  6090.4  483.77  6139.9  486.10  6147.0  485.27  6149.4  486.20
#Mann=6,-1,0
  3519.7   0.035       0  3761.5    0.05       0  4151.5   0.035       0
  4984.9   0.035       0  4988.9   0.035       0  5274.0    0.07       0
Bank Sta=4984.9,4988.9
Exp/Cntr=0.3,0.1

Type RM Length L Ch R = 1,6350,310,310,310
BEGIN DESCRIPTION:
A19121
END DESCRIPTION:
XS GIS Cut Line= 2
      2310839.38     13742082.02      2312473.79     13740702.46
#Sta/Elev= 30
  3621.2  466.80  3662.0  467.48  3949.5  467.86  4013.3  466.19  4027.5  466.85
  4034.2  468.04  4056.1  466.87  4137.9  465.98  4735.5  461.46  4735.7  460.96
  4739.5  461.46  4879.2  462.39  4900.0  463.36  4928.6  462.00  4985.8  461.74
  5128.6  462.96  5191.3  465.16  5262.7  465.27  5333.0  466.62  5433.1  470.75
  5511.1  469.82  5571.1  471.27  5609.9  472.20  5624.2  474.17  5645.1  473.64
  5652.8  475.43  5659.4  474.75  5667.1  475.64  5702.3  475.40  5760.0  476.92
#Mann=7,-1,0
  3621.2    0.05       0  3662.0   0.035       0  4137.9    0.05       0
  4735.5    0.05       0  4739.5    0.05       0  5128.6   0.035       0
  5571.1    0.07       0
Bank Sta=4735.5,4739.5
Exp/Cntr=0.3,0.1

Type RM Length L Ch R = 1,6040,297,297,297
BEGIN DESCRIPTION:
GUADALUPE TRIBUTARY 11 210442
END DESCRIPTION:
XS GIS Cut Line= 2
      2311110.24     13742251.08      2312734.28     13740860.72
#Sta/Elev= 30
  3765.9  466.77  4086.0  467.86  4162.1  466.97  4196.6  466.88  4424.5  466.03
  4731.4  463.79  4879.6  461.51  4965.2  461.59  5020.3  459.70  5020.6  459.20
  5024.4  459.70  5043.2  460.80  5149.6  462.09  5220.2  465.00  5277.0  465.20
  5319.8  468.03  5362.6  468.02  5412.0  470.77  5461.4  470.74  5501.2  472.88
  5561.3  473.24  5603.0  475.02  5731.4  475.61  5759.9  476.83  5773.1  476.23
  5823.6  477.25  5844.5  476.37  5858.7  476.62  5865.3  478.06  5903.8  478.96
#Mann=7,-1,0
  3765.9   0.045       0  4162.1    0.05       0  4196.6    0.07       0
  4424.5    0.05       0  5020.3    0.05       0  5024.4    0.05       0
  5501.2   0.035       0
Bank Sta=5020.3,5024.4
Exp/Cntr=0.3,0.1

Type RM Length L Ch R = 1,5743,402,402,402
BEGIN DESCRIPTION:
A19120
END DESCRIPTION:
XS GIS Cut Line= 3
      2311282.63     13742386.74      2312296.53     13741594.46
      2312773.02     13741040.40
#Sta/Elev= 30
  3821.6  466.88  4144.6  467.68  4565.2  465.08  4693.6  465.01  4801.2  463.91
  4921.5  461.60  4971.3  461.35  5000.2  459.99  5006.6  458.93  5027.1  457.65
  5027.3  457.15  5030.9  457.15  5031.2  457.65  5085.2  459.82  5113.9  459.64
  5161.7  460.71  5234.6  463.55  5284.0  467.44  5319.1  469.30  5347.7  470.56
  5367.6  470.32  5433.2  471.81  5454.1  473.35  5490.1  472.69  5539.7  475.19
  5560.5  474.50  5720.4  475.55  5738.3  475.71  5744.9  475.09  5839.1  475.89
#Mann=7,-1,0
  3821.6   0.045       0  4144.6    0.05       0  5027.1    0.05       0
  5031.2    0.05       0  5161.7    0.07       0  5367.6    0.05       0
  5720.4   0.035       0
Bank Sta=5027.1,5031.2
Exp/Cntr=0.3,0.1

Type RM Length L Ch R = 1,5341,347,347,347
BEGIN DESCRIPTION:
GUADALUPE TRIBUTARY 11 210441
END DESCRIPTION:
XS GIS Cut Line= 3
      2311414.01     13742537.36      2312594.07     13741836.33
      2312798.22     13741118.89
#Sta/Elev= 30
  3765.1  466.92  4147.9  467.86  4197.0  467.12  4256.2  466.89  4632.3  464.36
  4892.1  460.57  4913.5  461.26  4929.1  460.00  4950.6  459.56  4991.4  455.79
  4991.6  455.29  4995.5  455.79  4999.2  456.71  5030.4  459.10  5126.5  460.55
  5149.5  461.38  5190.9  465.96  5222.2  467.50  5269.0  467.57  5305.0  469.13
  5326.2  469.30  5341.9  470.67  5399.4  471.21  5414.9  472.08  5521.6  473.12
  5688.3  473.75  5745.6  474.08  5773.3  475.20  5868.6  475.04  5883.6  475.39
#Mann=11,-1,0
  3765.1   0.045       0  4197.0    0.05       0  4256.2    0.07       0
  4632.3    0.05       0  4991.4    0.05       0  4995.5    0.05       0
  5126.5    0.07       0  5305.0    0.12       0  5399.4    0.07       0
  5688.3    0.05       0  5868.6   0.035       0
Bank Sta=4991.4,4995.5
Exp/Cntr=0.3,0.1

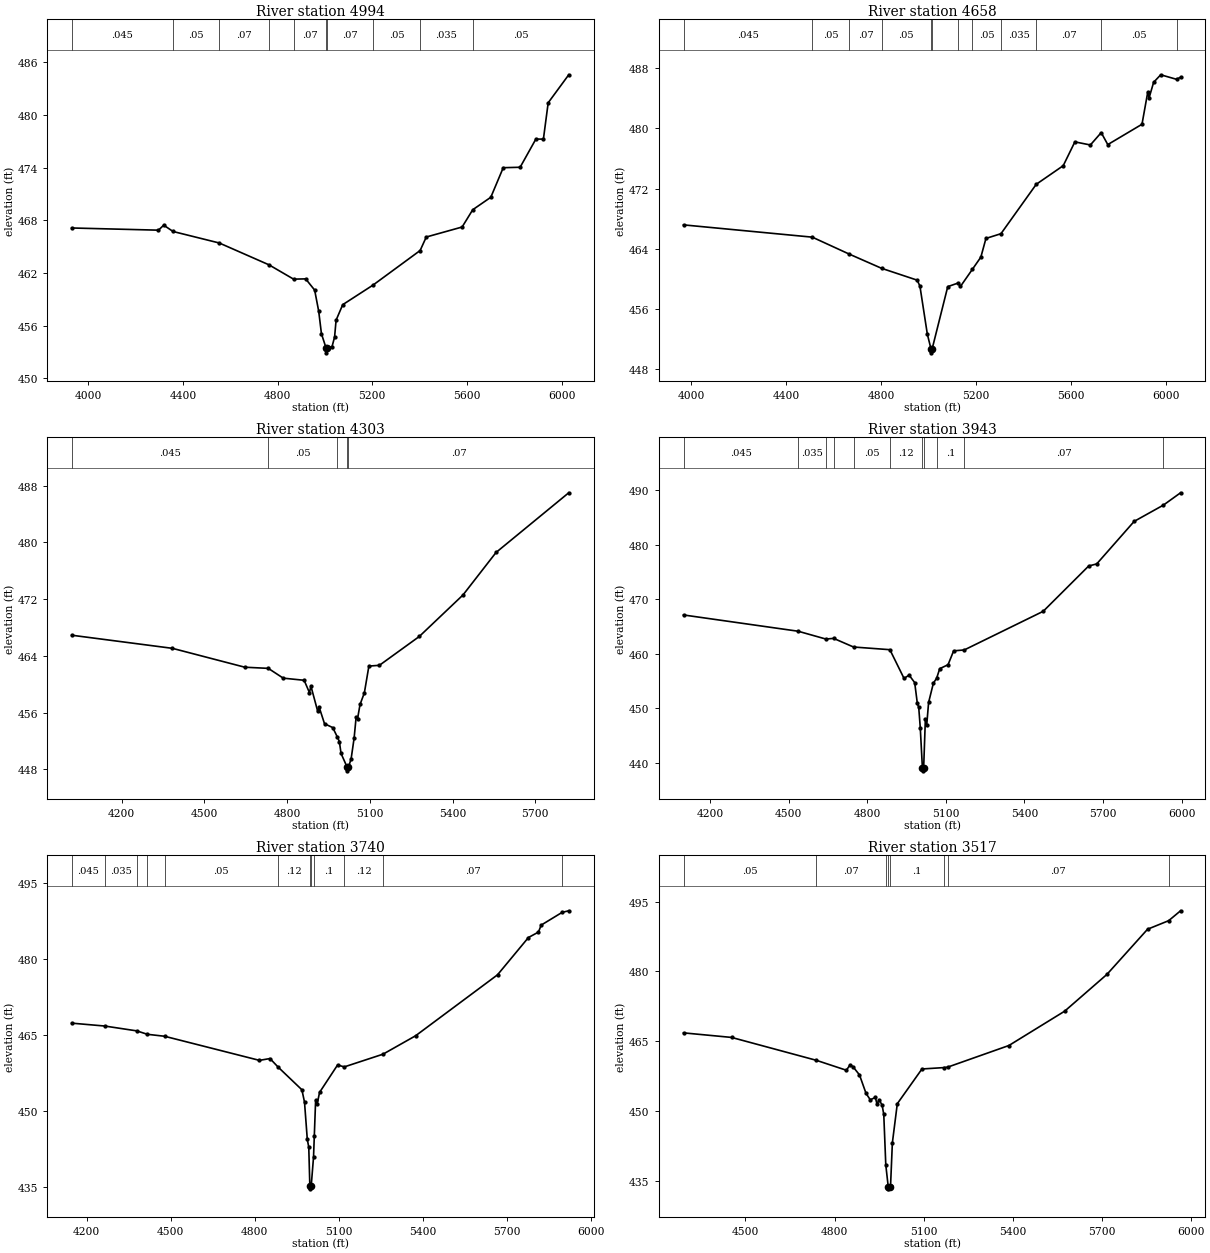
Type RM Length L Ch R = 1,4994,336,336,336
BEGIN DESCRIPTION:
A19119
END DESCRIPTION:
XS GIS Cut Line= 3
      2311615.01     13742685.96      2312750.85     13742137.43
      2313581.00     13742021.21
#Sta/Elev= 30
  3930.6  467.12  4297.1  466.87  4319.3  467.44  4358.7  466.72  4553.9  465.41
  4764.0  462.92  4867.8  461.29  4918.9  461.32  4956.9  460.04  4974.0  457.63
  4985.6  455.06  5005.7  453.39  5006.0  452.89  5009.8  453.39  5030.3  453.60
  5041.1  454.69  5047.4  456.61  5075.5  458.38  5203.9  460.62  5402.4  464.55
  5428.4  466.09  5579.8  467.23  5624.7  469.20  5701.0  470.62  5753.5  473.99
  5824.9  474.04  5891.3  477.25  5923.2  477.25  5943.4  481.39  6030.2  484.58
#Mann=10,-1,0
  3930.6   0.045       0  4358.7    0.05       0  4553.9    0.07       0
  4764.0    0.05       0  4867.8    0.07       0  5005.7    0.05       0
  5009.8    0.07       0  5203.9    0.05       0  5402.4   0.035       0
  5624.7    0.05       0
Bank Sta=5005.7,5009.8
Exp/Cntr=0.3,0.1

Type RM Length L Ch R = 1,4658,355,355,355
BEGIN DESCRIPTION:
GUADALUPE TRIBUTARY 11 210440
END DESCRIPTION:
XS GIS Cut Line= 2
      2311717.73     13742899.59      2313669.04     13742140.10
#Sta/Elev= 30
  3967.7  467.19  4510.1  465.56  4665.8  463.31  4802.3  461.42  4952.0  459.85
  4963.6  459.06  4994.9  452.66  5010.4  450.70  5010.7  450.20  5014.9  450.70
  5080.8  458.99  5124.5  459.47  5134.4  459.02  5184.6  461.29  5220.3  462.91
  5241.7  465.39  5305.0  466.02  5453.7  472.58  5567.3  475.05  5616.3  478.21
  5681.7  477.80  5727.3  479.44  5755.0  477.85  5899.1  480.55  5923.6  484.86
  5928.9  484.04  5948.1  486.12  5978.0  487.12  6044.5  486.52  6061.6  486.79
#Mann=12,-1,0
  3967.7   0.045       0  4510.1    0.05       0  4665.8    0.07       0
  4802.3    0.05       0  5010.4    0.05       0  5014.9    0.05       0
  5124.5    0.07       0  5184.6    0.05       0  5305.0   0.035       0
  5453.7    0.07       0  5727.3    0.05       0  6044.5   0.035       0
Bank Sta=5010.4,5014.9
Exp/Cntr=0.3,0.1

Type RM Length L Ch R = 1,4303,360,360,360
BEGIN DESCRIPTION:
A19118
END DESCRIPTION:
XS GIS Cut Line= 2
      2311858.81     13743201.22      2313541.58     13742553.58
#Sta/Elev= 30
  4018.5  466.91  4384.0  465.06  4646.6  462.40  4731.6  462.24  4785.9  460.86
  4861.7  460.56  4881.0  458.82  4886.3  459.74  4911.0  456.18  4916.3  456.76
  4935.6  454.44  4965.6  453.89  4981.6  452.61  4989.5  451.93  4995.6  450.25
  5017.9  448.30  5018.3  447.80  5022.5  448.30  5032.3  449.52  5043.1  452.44
  5050.2  455.33  5055.6  455.17  5064.5  457.15  5080.2  458.79  5096.6  462.56
  5134.8  462.67  5279.4  466.73  5438.0  472.58  5557.9  478.57  5821.6  486.98
#Mann=5,-1,0
  4018.5   0.045       0  4731.6    0.05       0  4981.6    0.07       0
  5017.9    0.05       0  5022.5    0.07       0
Bank Sta=5017.9,5022.5
Exp/Cntr=0.3,0.1

Type RM Length L Ch R = 1,3943,203,203,203
BEGIN DESCRIPTION:
GUADALUPE TRIBUTARY 11 210439
END DESCRIPTION:
XS GIS Cut Line= 2
      2311933.96     13743483.76      2313720.82     13742841.42
#Sta/Elev= 30
  4097.6  467.13  4535.5  464.15  4641.3  462.72  4671.1  462.84  4747.0  461.26
  4885.9  460.77  4940.0  455.51  4959.4  456.11  4980.7  454.74  4990.8  450.93
  4996.1  450.21  5002.0  446.48  5010.2  439.08  5010.6  438.58  5014.9  439.08
  5021.5  448.10  5026.8  447.04  5033.8  451.10  5052.2  454.66  5064.3  455.51
  5076.3  457.29  5108.2  458.02  5129.5  460.56  5170.0  460.72  5471.7  467.80
  5645.4  476.10  5676.1  476.48  5819.1  484.27  5931.1  487.26  5996.4  489.51
#Mann=11,-1,0
  4097.6   0.045       0  4535.5   0.035       0  4641.3    0.05       0
  4671.1   0.035       0  4747.0    0.05       0  4885.9    0.12       0
  5010.2    0.05       0  5014.9    0.12       0  5064.3     0.1       0
  5170.0    0.07       0  5931.1   0.035       0
Bank Sta=5010.2,5014.9
Exp/Cntr=0.3,0.1

Type RM Length L Ch R = 1,3740,223,223,223
BEGIN DESCRIPTION:
A19117
END DESCRIPTION:
XS GIS Cut Line= 3
      2312030.56     13743677.71      2313094.37     13743262.16
      2313687.21     13743040.54
#Sta/Elev= 30
  4147.1  467.40  4265.0  466.83  4379.8  465.87  4417.1  465.20  4478.8  464.81
  4817.5  460.05  4855.2  460.41  4884.1  458.73  4969.2  454.24  4978.5  451.80
  4988.4  444.47  4993.7  442.89  4997.6  435.18  4998.0  434.68  5002.3  435.18
  5010.7  440.94  5013.5  445.14  5018.2  452.20  5023.6  451.39  5032.2  453.72
  5096.6  459.14  5120.5  458.76  5258.8  461.27  5375.3  464.91  5667.7  476.94
  5778.2  484.31  5813.9  485.38  5823.7  486.76  5898.3  489.27  5922.1  489.59
#Mann=12,-1,0
  4147.1   0.045       0  4265.0   0.035       0  4379.8    0.05       0
  4417.1   0.035       0  4478.8    0.05       0  4884.1    0.12       0
  4997.6    0.05       0  5002.3    0.12       0  5013.5     0.1       0
  5120.5    0.12       0  5258.8    0.07       0  5898.3   0.035       0
Bank Sta=4997.6,5002.3
Exp/Cntr=0.3,0.1

Type RM Length L Ch R = 1,3517,219,219,219
BEGIN DESCRIPTION:
A19116
END DESCRIPTION:
XS GIS Cut Line= 2
      2312230.02     13743877.17      2313741.29     13743163.05
#Sta/Elev= 30
  4291.9  466.77  4453.5  465.79  4738.8  460.86  4839.4  458.73  4851.5  459.83
  4861.5  459.51  4883.6  457.73  4905.7  453.74  4919.8  452.38  4937.0  452.87
  4942.5  451.45  4950.0  452.35  4959.8  451.20  4965.3  449.21  4972.1  438.34
  4980.2  433.71  4980.5  433.21  4984.9  433.71  4988.1  433.85  4994.2  443.10
  5010.8  451.53  5093.7  459.00  5168.2  459.30  5180.3  459.40  5386.1  464.05
  5573.7  471.44  5715.9  479.36  5852.4  489.07  5923.4  490.91  5963.4  493.04
#Mann=8,-1,0
  4291.9    0.05       0  4738.8    0.07       0  4972.1     0.1       0
  4980.2    0.05       0  4984.9     0.1       0  5168.2    0.12       0
  5180.3    0.07       0  5923.4   0.035       0
Bank Sta=4980.2,4984.9
Exp/Cntr=0.3,0.1

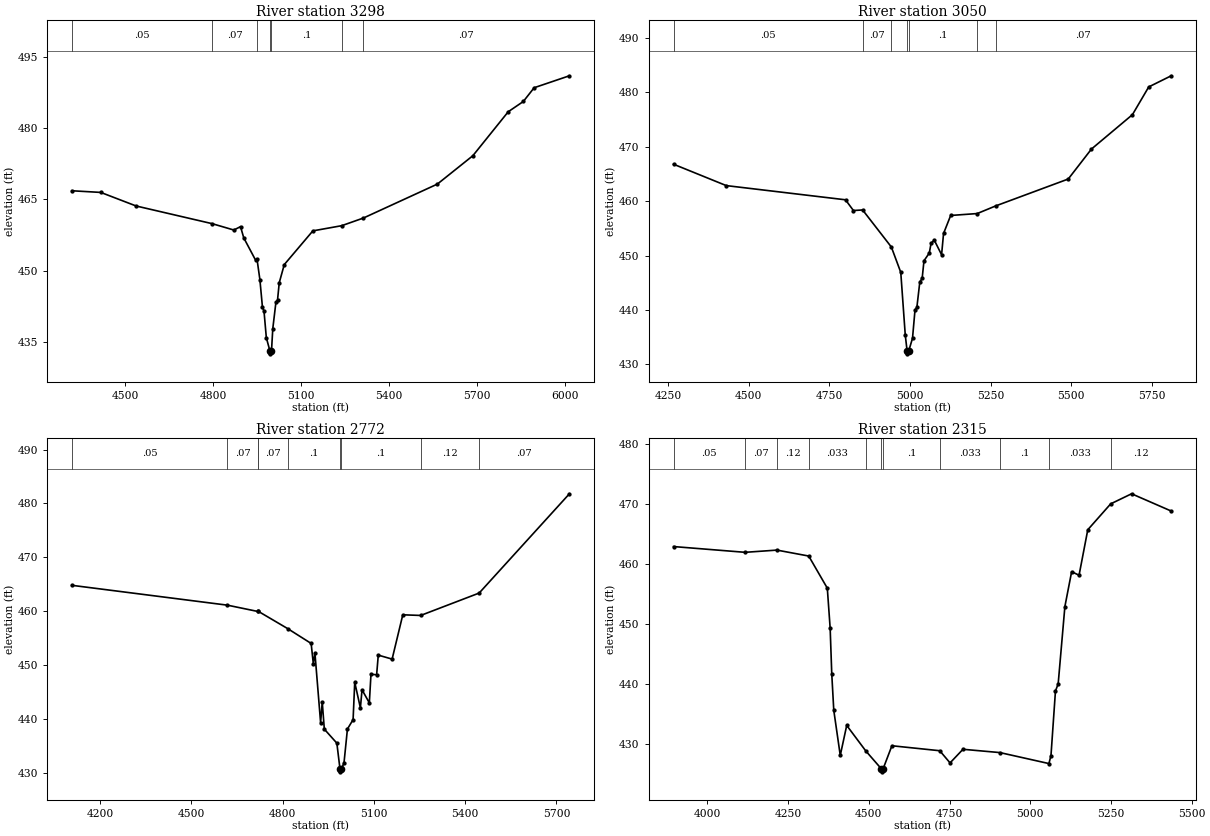
Type RM Length L Ch R = 1,3298,248,248,248
BEGIN DESCRIPTION:
GUADALUPE TRIBUTARY 11 210438
END DESCRIPTION:
XS GIS Cut Line= 2
      2312301.95     13744062.13      2313844.27     13743355.24
#Sta/Elev= 30
  4318.7  466.83  4417.7  466.48  4538.2  463.63  4797.0  459.92  4871.2  458.58
  4894.1  459.29  4905.2  456.92  4945.7  452.22  4950.3  452.47  4960.1  448.17
  4968.7  442.47  4974.2  441.49  4982.1  435.94  4994.8  433.06  4995.2  432.56
  4999.6  433.06  5004.1  437.86  5014.7  443.37  5020.2  443.83  5026.1  447.50
  5043.2  451.31  5140.7  458.40  5239.1  459.49  5313.1  461.10  5565.1  468.23
  5686.1  474.19  5806.7  483.43  5858.2  485.59  5895.1  488.48  6015.3  490.99
#Mann=7,-1,0
  4318.7    0.05       0  4797.0    0.07       0  4950.3     0.1       0
  4994.8    0.05       0  4999.6     0.1       0  5239.1    0.12       0
  5313.1    0.07       0
Bank Sta=4994.8,4999.6
Exp/Cntr=0.3,0.1

Type RM Length L Ch R = 1,3050,278,278,278
BEGIN DESCRIPTION:
A19115
END DESCRIPTION:
XS GIS Cut Line= 3
      2312363.04     13744154.18      2312944.77     13744032.30
      2313786.95     13743594.58
#Sta/Elev= 30
  4266.6  466.80  4430.1  462.87  4799.9  460.26  4824.4  458.29  4853.0  458.39
  4942.1  451.58  4971.3  446.92  4985.2  435.42  4991.0  432.44  4991.4  431.94
  4995.8  432.44  5007.7  434.80  5015.5  440.03  5021.2  440.46  5030.3  445.13
  5037.7  445.84  5043.3  449.05  5059.8  450.48  5065.4  452.30  5075.3  452.83
  5097.9  450.16  5104.0  454.07  5126.1  457.38  5208.4  457.73  5265.5  459.13
  5490.7  464.08  5562.7  469.59  5689.8  475.91  5740.3  481.01  5810.1  483.06
#Mann=7,-1,0
  4266.6    0.05       0  4853.0    0.07       0  4942.1     0.1       0
  4991.0    0.05       0  4995.8     0.1       0  5208.4    0.12       0
  5265.5    0.07       0
Bank Sta=4991,4995.8
Exp/Cntr=0.3,0.1

Type RM Length L Ch R = 1,2772,457,457,457
BEGIN DESCRIPTION:
A19114
END DESCRIPTION:
XS GIS Cut Line= 4
      2312401.81     13744248.38      2313177.47     13744176.35
      2313421.26     13744076.62      2313875.61     13743694.30
#Sta/Elev= 30
  4106.3  464.79  4618.1  461.10  4717.2  459.94  4719.8  459.95  4816.4  456.74
  4893.4  453.99  4900.5  450.25  4905.9  452.16  4924.5  439.29  4929.9  443.12
  4936.7  438.07  4977.9  435.47  4988.3  430.64  4988.6  430.14  4993.1  430.64
  5001.5  431.85  5012.7  438.10  5031.3  439.83  5036.7  446.78  5055.3  442.01
  5060.7  445.38  5084.7  442.95  5090.1  448.25  5108.7  448.18  5114.1  451.82
  5159.6  451.08  5194.7  459.31  5253.5  459.19  5445.8  463.35  5742.5  481.79
#Mann=9,-1,0
  4106.3    0.05       0  4618.1    0.07       0  4717.2     0.1       0
  4719.8    0.07       0  4816.4     0.1       0  4988.3    0.05       0
  4993.1     0.1       0  5253.5    0.12       0  5445.8    0.07       0
Bank Sta=4988.3,4993.1
Exp/Cntr=0.3,0.1

Type RM Length L Ch R = 1,2315,0,0,0
BEGIN DESCRIPTION:
GUADALUPE TRIBUTARY 11 210437
END DESCRIPTION:
XS GIS Cut Line= 3
      2312488.89     13744325.01      2313441.15     13744354.22
      2313914.36     13744003.70
#Sta/Elev= 30
  3895.1  462.96  4116.9  462.00  4215.3  462.37  4313.8  461.38  4371.4  456.02
  4380.2  449.35  4385.2  441.70  4391.4  435.66  4411.5  428.14  4431.5  433.14
  4490.5  428.89  4538.8  425.90  4539.3  425.40  4544.2  425.90  4571.5  429.75
  4719.6  428.92  4751.6  426.89  4791.6  429.16  4906.1  428.61  5057.8  426.78
  5064.2  428.10  5078.1  438.88  5086.5  440.06  5107.3  452.96  5128.2  458.77
  5151.2  458.18  5178.2  465.76  5249.2  470.08  5313.9  471.76  5436.7  468.88
#Mann=11,-1,0
  3895.1    0.05       0  4116.9    0.07       0  4215.3    0.12       0
  4313.8   0.033       0  4490.5     0.1       0  4538.8    0.05       0
  4544.2     0.1       0  4719.6   0.033       0  4906.1     0.1       0
  5057.8   0.033       0  5249.2    0.12       0
Bank Sta=4538.8,4544.2
Exp/Cntr=0.3,0.1

Chan Stop Cuts=-1