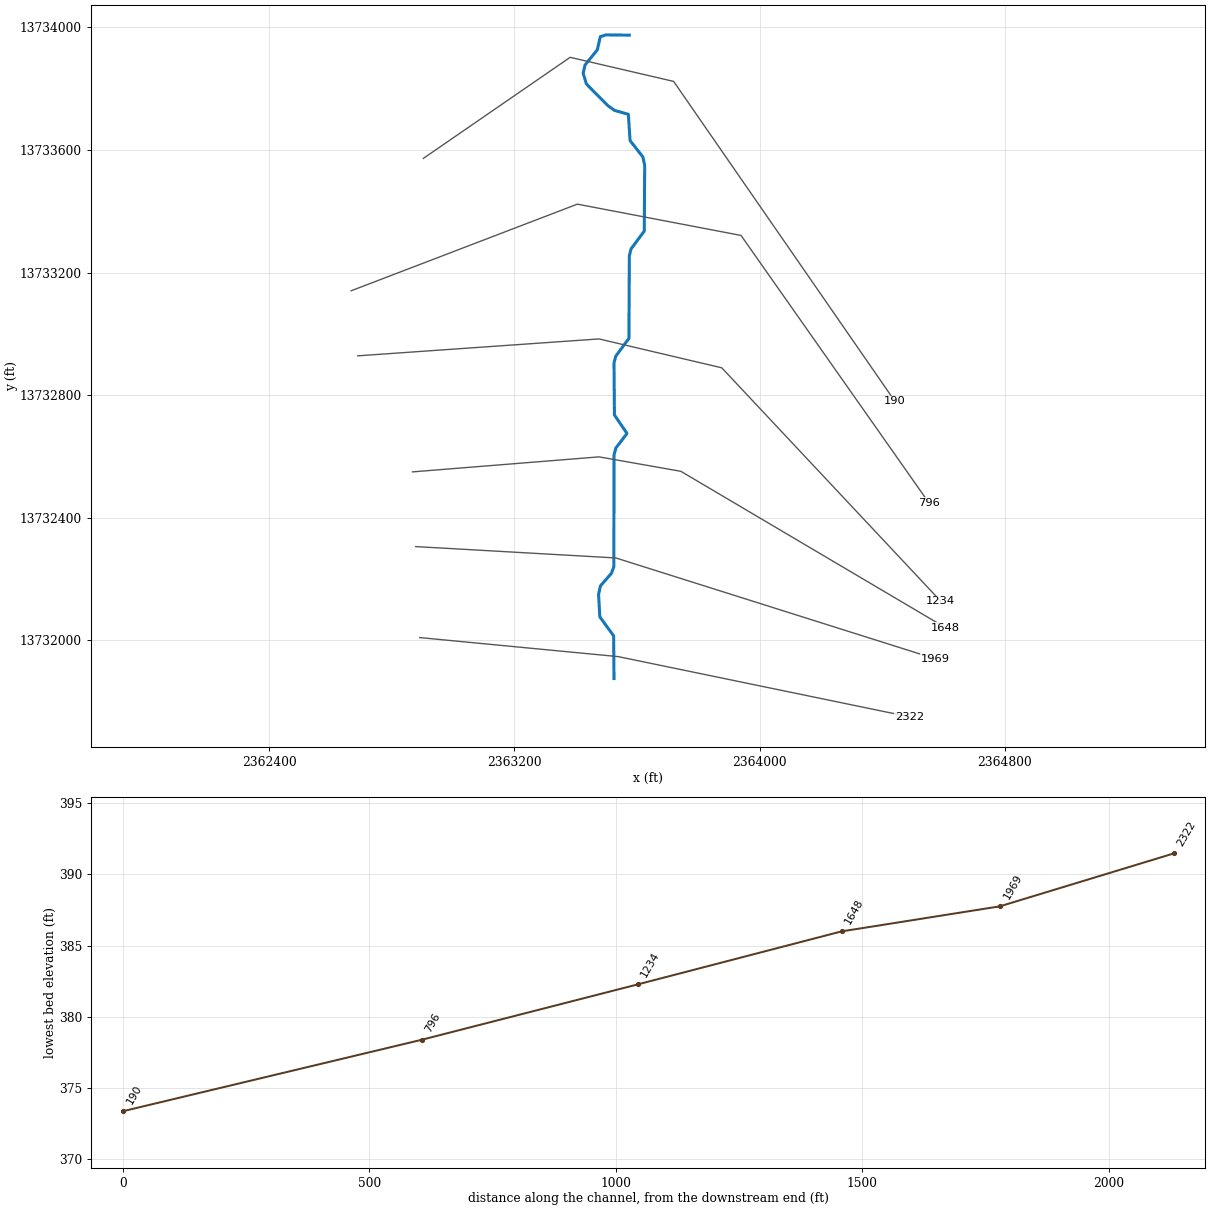
--- GUADALUPE TRIBUTARY 4 2.prj (project) ---

Proj Title=GUADALUPE TRIBUTARY 4 2 Base Level Engineering
Current Plan=p01
Default Exp/Contr=0.3,0.1
English Units
Geom File=g01
Flow File=f01
Plan File=p01
BEGIN DESCRIPTION:
GUADALUPE TRIBUTARY 4 2
END DESCRIPTION:

--- GUADALUPE TRIBUTARY 4 2.p01 (plan) ---

Plan Title=Multiple Run
Short Identifier=Multiple
Geom File=g01
Flow File=f01
Subcritical Flow
K Sum by GR= 0
Std Step Tol= 0.01
Critical Tol= 0.01
Num of Std Step Trials= 20
Max Error Tol= 0.3
Flow Tol Ratio= 0.001
Split Flow NTrial= 30
Split Flow Tol= 0.02
Split Flow Ratio= 0.02
Log Output Level= 0
Friction Slope Method= 1
Unsteady Friction Slope Method= 2
Unsteady Bridges Friction Slope Method= 1
Parabolic Critical Depth
Global Vel Dist=  1 , 1 , 1
Global Log Level= 0
CheckData=True
Encroach Param= -1, 0, 0, 0
BEGIN DESCRIPTION:
Multiple Run
END DESCRIPTION:

--- GUADALUPE TRIBUTARY 4 2.f01 (steady flow) ---

Flow Title=Multiple
Number of Profiles=7
Profile Names=10-year,25-year,50-year,1pct_min,100-year,1pct_plu,500-year
River Rch & RM= GUADALUPE TRIBUT,Reach-1,2322
     744    1220    1658    1091    2177    4344    3720
Boundary for River Rch & Prof#=GUADALUPE TRIBUT,Reach-1,1
Up Type=0
Dn Type=3
Dn Slope=0.005
Boundary for River Rch & Prof#=GUADALUPE TRIBUT,Reach-1,2
Up Type=0
Dn Type=3
Dn Slope=0.005
Boundary for River Rch & Prof#=GUADALUPE TRIBUT,Reach-1,3
Up Type=0
Dn Type=3
Dn Slope=0.005
Boundary for River Rch & Prof#=GUADALUPE TRIBUT,Reach-1,4
Up Type=0
Dn Type=3
Dn Slope=0.005
Boundary for River Rch & Prof#=GUADALUPE TRIBUT,Reach-1,5
Up Type=0
Dn Type=3
Dn Slope=0.005
Boundary for River Rch & Prof#=GUADALUPE TRIBUT,Reach-1,6
Up Type=0
Dn Type=3
Dn Slope=0.005
Boundary for River Rch & Prof#=GUADALUPE TRIBUT,Reach-1,7
Up Type=0
Dn Type=3
Dn Slope=0.005

--- GUADALUPE TRIBUTARY 4 2.g01 (geometry) ---

Geom Title=Existing Conditions

River Reach=GUADALUPE TRIBUT,Reach-1
Reach XY= 30
      2363525.00     13731875.00      2363523.83     13732014.52
      2363478.70     13732076.60      2363474.60     13732150.00
      2363480.68     13732177.31      2363516.85     13732218.94
      2363524.48     13732240.22      2363525.18     13732605.02
      2363531.02     13732627.45      2363567.44     13732675.00
      2363526.38     13732735.44      2363525.07     13732904.97
      2363530.75     13732927.33      2363573.78     13732985.50
      2363575.07     13733254.97      2363580.75     13733277.33
      2363623.78     13733335.50      2363625.20     13733550.08
      2363619.26     13733577.34      2363577.40     13733631.06
      2363571.84     13733716.66      2363527.07     13733729.15
      2363505.05     13733744.85      2363435.18     13733815.30
      2363424.49     13733849.97      2363430.29     13733877.22
      2363470.63     13733927.13      2363480.27     13733970.01
      2363499.42     13733975.73      2363575.00     13733975.00

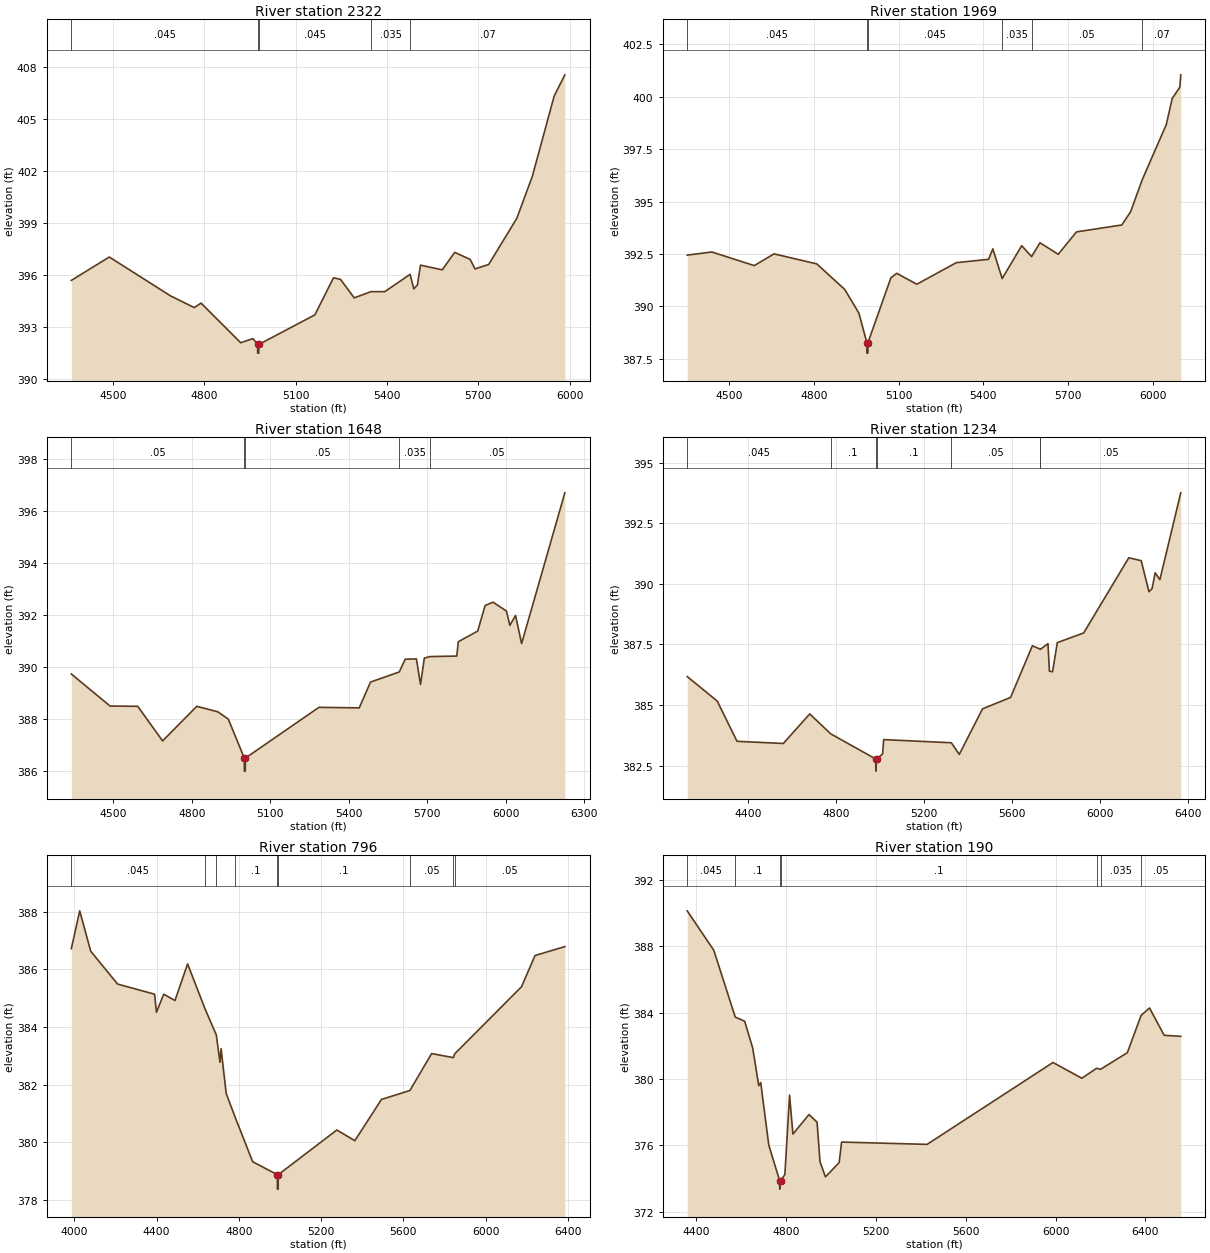
Type RM Length L Ch R = 1,2322,353,353,353
BEGIN DESCRIPTION:
GUADALUPE TRIBUTARY 4 210497
END DESCRIPTION:
XS GIS Cut Line= 3
      2362890.90     13732008.85      2363538.96     13731946.67
      2364489.45     13731750.29
#Sta/Elev= 30
  4362.7  395.68  4487.4  397.03  4688.3  394.79  4766.6  394.11  4788.8  394.37
  4919.3  392.08  4959.5  392.32  4974.7  391.98  4975.0  391.48  4978.5  391.48
  4978.7  391.98  5162.9  393.69  5224.1  395.83  5247.0  395.74  5292.2  394.67
  5347.2  395.03  5392.6  395.03  5475.7  396.03  5488.0  395.19  5499.8  395.42
  5510.0  396.56  5581.5  396.29  5622.4  397.30  5673.4  396.89  5689.0  396.34
  5734.1  396.60  5826.6  399.27  5877.6  401.70  5949.1  406.32  5984.3  407.55
#Mann=5,-1,0
  4362.7   0.045       0  4974.7   0.045       0  4978.7   0.045       0
  5347.2   0.035       0  5475.7    0.07       0
Bank Sta=4974.7,4978.7
Exp/Cntr=0.3,0.1

Type RM Length L Ch R = 1,1969,321,321,321
BEGIN DESCRIPTION:
GUADALUPE TRIBUTARY 4 210496
END DESCRIPTION:
XS GIS Cut Line= 3
      2362877.97     13732305.83      2363531.10     13732268.72
      2364573.95     13731939.40
#Sta/Elev= 30
  4351.5  392.44  4438.7  392.59  4588.9  391.94  4659.0  392.50  4810.6  392.02
  4909.4  390.80  4959.5  389.67  4987.6  388.26  4987.8  387.76  4991.3  387.76
  4991.6  388.26  5072.9  391.36  5093.7  391.57  5164.7  391.05  5304.5  392.08
  5418.8  392.24  5433.8  392.74  5466.9  391.32  5536.1  392.89  5571.1  392.37
  5600.7  393.03  5665.4  392.48  5730.1  393.55  5890.7  393.88  5922.1  394.52
  5962.9  396.04  6048.0  398.67  6069.1  399.92  6096.2  400.46  6099.3  401.05
#Mann=6,-1,0
  4351.5   0.045       0  4987.6   0.045       0  4991.6   0.045       0
  5466.9   0.035       0  5571.1    0.05       0  5962.9    0.07       0
Bank Sta=4987.6,4991.6
Exp/Cntr=0.3,0.1

Type RM Length L Ch R = 1,1648,414,414,414
BEGIN DESCRIPTION:
GUADALUPE TRIBUTARY 4 210495
END DESCRIPTION:
XS GIS Cut Line= 4
      2362867.38     13732549.60      2363476.12     13732598.63
      2363743.19     13732551.50      2364607.21     13732040.94
#Sta/Elev= 30
  4340.0  389.73  4488.1  388.50  4593.8  388.49  4688.7  387.16  4819.2  388.49
  4899.4  388.28  4939.6  388.00  5000.9  386.50  5001.1  386.00  5004.6  386.00
  5004.9  386.50  5285.9  388.45  5440.0  388.43  5482.9  389.42  5592.9  389.81
  5615.6  390.30  5658.4  390.31  5674.1  389.33  5688.6  390.34  5709.3  390.40
  5812.6  390.42  5818.4  390.97  5892.5  391.38  5920.9  392.36  5951.1  392.49
  6002.2  392.15  6015.4  391.60  6037.1  391.98  6060.3  390.90  6225.5  396.69
#Mann=5,-1,0
  4340.0    0.05       0  5000.9    0.05       0  5004.9    0.05       0
  5592.9   0.035       0  5709.3    0.05       0
Bank Sta=5000.9,5004.9
Exp/Cntr=0.3,0.1

Type RM Length L Ch R = 1,1234,438,438,438
BEGIN DESCRIPTION:
GUADALUPE TRIBUTARY 4 210494
END DESCRIPTION:
XS GIS Cut Line= 4
      2362688.85     13732928.36      2363476.12     13732983.52
      2363876.72     13732889.26      2364591.53     13732127.32
#Sta/Elev= 30
  4122.2  386.17  4258.7  385.16  4348.9  383.50  4559.4  383.41  4679.7  384.63
  4774.8  383.81  4980.1  382.77  4980.4  382.27  4984.2  382.77  5011.0  382.98
  5016.1  383.57  5324.0  383.44  5360.0  382.96  5466.0  384.84  5593.5  385.31
  5692.6  387.44  5726.2  387.31  5728.7  387.29  5763.5  387.53  5770.3  386.39
  5784.5  386.37  5806.0  387.57  5926.1  387.97  6131.3  391.07  6187.9  390.95
  6223.1  389.67  6237.3  389.80  6251.4  390.45  6272.9  390.17  6367.7  393.75
#Mann=7,-1,0
  4122.2   0.045       0  4774.8     0.1       0  4980.1    0.05       0
  4984.2     0.1       0  5324.0    0.05       0  5726.2   0.035       0
  5728.7    0.05       0
Bank Sta=4980.1,4984.2
Exp/Cntr=0.3,0.1

Type RM Length L Ch R = 1,796,606,606,606
BEGIN DESCRIPTION:
GUADALUPE TRIBUTARY 4 210493
END DESCRIPTION:
XS GIS Cut Line= 4
      2362667.04     13733140.61      2363405.42     13733423.40
      2363939.56     13733321.29      2364552.23     13732449.42
#Sta/Elev= 30
  3985.4  386.72  4026.1  388.03  4079.6  386.63  4210.4  385.49  4390.1  385.14
  4399.3  384.51  4434.7  385.14  4489.4  384.92  4550.8  386.19  4634.5  384.65
  4690.3  383.73  4708.3  382.78  4713.7  383.25  4738.4  381.70  4781.1  380.89
  4867.3  379.33  4987.4  378.88  4987.7  378.38  4991.3  378.38  4991.5  378.88
  5276.6  380.43  5364.2  380.06  5493.6  381.49  5631.9  381.80  5737.6  383.08
  5843.2  382.94  5849.8  383.07  6175.0  385.40  6240.3  386.48  6385.5  386.79
#Mann=9,-1,0
  3985.4   0.045       0  4634.5     0.1       0  4690.3   0.045       0
  4781.1     0.1       0  4987.4    0.05       0  4991.5     0.1       0
  5631.9    0.05       0  5843.2   0.035       0  5849.8    0.05       0
Bank Sta=4987.4,4991.5
Exp/Cntr=0.3,0.1

Type RM Length L Ch R = 1,190,0,0,0
BEGIN DESCRIPTION:
GUADALUPE TRIBUTARY 4 210492
END DESCRIPTION:
XS GIS Cut Line= 4
      2362902.71     13733572.65      2363381.86     13733902.55
      2363719.62     13733824.00      2364442.04     13732779.64
#Sta/Elev= 30
  4359.2  390.15  4477.6  387.77  4573.1  383.74  4615.0  383.49  4650.8  381.88
  4677.8  379.60  4686.6  379.79  4722.5  376.02  4771.1  373.86  4771.4  373.36
  4775.3  373.86  4794.2  374.24  4815.1  379.03  4830.0  376.68  4901.7  377.86
  4937.6  377.40  4950.8  375.01  4975.0  374.10  5036.0  374.96  5046.8  376.20
  5427.7  376.06  5988.6  381.00  6117.0  380.05  6182.6  380.65  6200.4  380.59
  6319.7  381.59  6381.0  383.84  6418.4  384.29  6483.9  382.64  6557.6  382.58
#Mann=7,-1,0
  4359.2   0.045       0  4573.1     0.1       0  4771.1    0.05       0
  4775.3     0.1       0  6182.6    0.05       0  6200.4   0.035       0
  6381.0    0.05       0
Bank Sta=4771.1,4775.3
Exp/Cntr=0.3,0.1

Chan Stop Cuts=-1