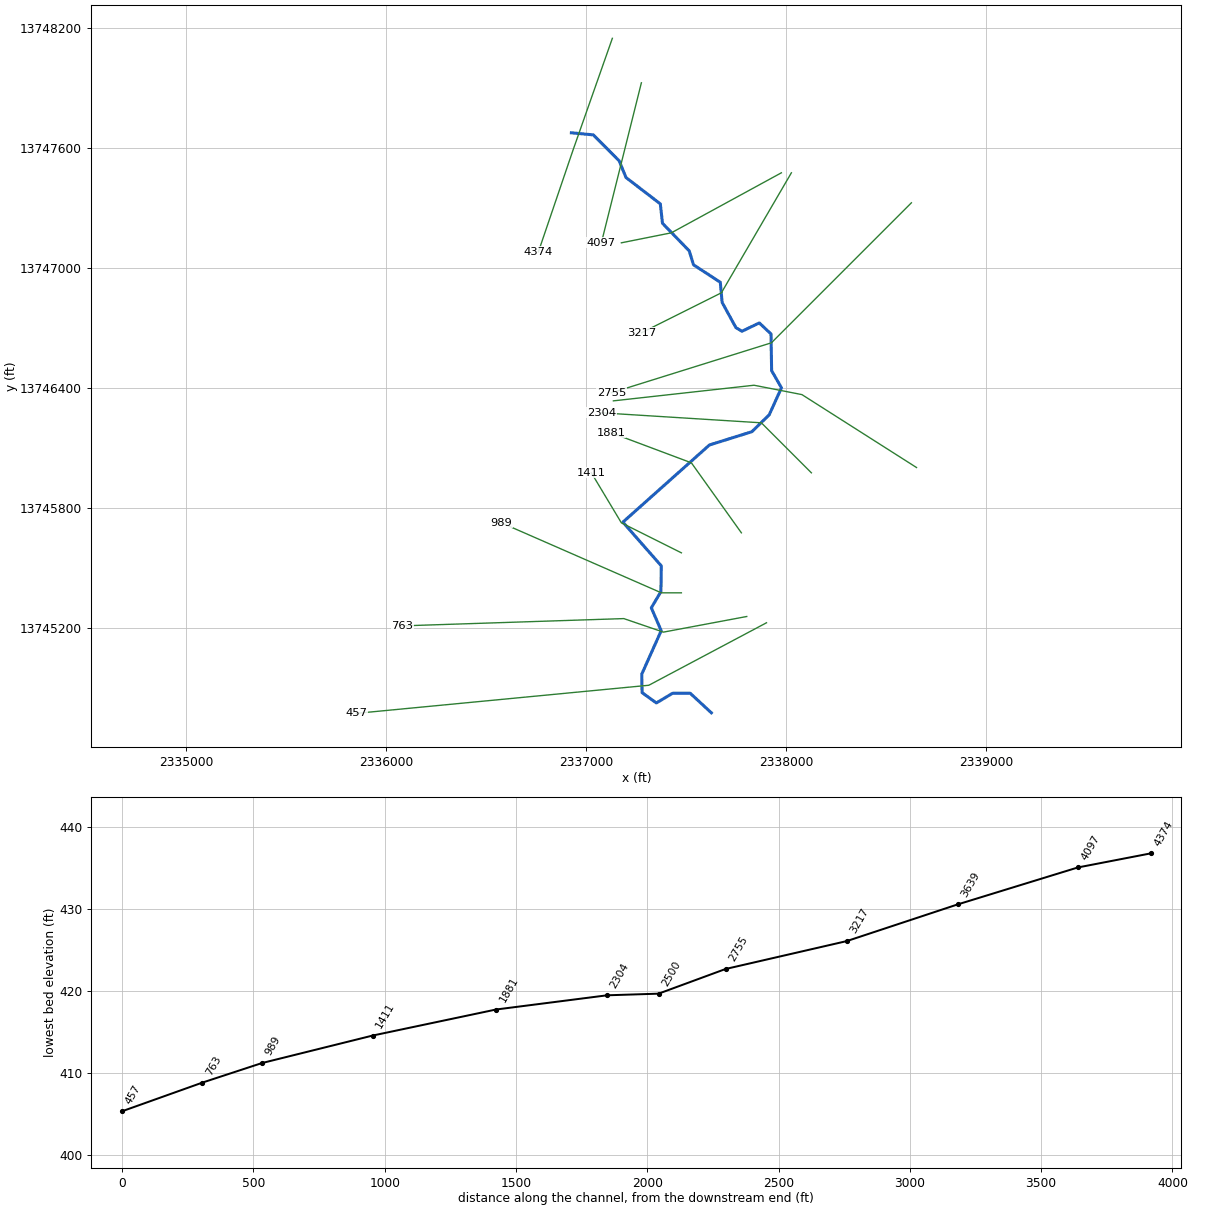
--- GUADALUPE TRIBUTARY 9.prj (project) ---

Proj Title=GUADALUPE TRIBUTARY 9 Base Level Engineering
Current Plan=p01
Default Exp/Contr=0.3,0.1
English Units
Geom File=g01
Flow File=f01
Plan File=p01
BEGIN DESCRIPTION:
GUADALUPE TRIBUTARY 9
END DESCRIPTION:

--- GUADALUPE TRIBUTARY 9.p01 (plan) ---

Plan Title=Multiple Run
Short Identifier=Multiple
Geom File=g01
Flow File=f01
Subcritical Flow
K Sum by GR= 0
Std Step Tol= 0.01
Critical Tol= 0.01
Num of Std Step Trials= 20
Max Error Tol= 0.3
Flow Tol Ratio= 0.001
Split Flow NTrial= 30
Split Flow Tol= 0.02
Split Flow Ratio= 0.02
Log Output Level= 0
Friction Slope Method= 1
Unsteady Friction Slope Method= 2
Unsteady Bridges Friction Slope Method= 1
Parabolic Critical Depth
Global Vel Dist=  1 , 1 , 1
Global Log Level= 0
CheckData=True
Encroach Param= -1, 0, 0, 0
BEGIN DESCRIPTION:
Multiple Run
END DESCRIPTION:

--- GUADALUPE TRIBUTARY 9.f01 (steady flow) ---

Flow Title=Multiple
Number of Profiles=7
Profile Names=10-year,25-year,50-year,1pct_min,100-year,1pct_plu,500-year
River Rch & RM= GUADALUPE TRIBUT,Reach-1,4374
     672    1091    1472     961    1918    3827    3228
River Rch & RM= GUADALUPE TRIBUT,Reach-1,2755
     970    1610    2204    1459    2912    5810    5038
Boundary for River Rch & Prof#=GUADALUPE TRIBUT,Reach-1,1
Up Type=0
Dn Type=3
Dn Slope=0.005
Boundary for River Rch & Prof#=GUADALUPE TRIBUT,Reach-1,2
Up Type=0
Dn Type=3
Dn Slope=0.005
Boundary for River Rch & Prof#=GUADALUPE TRIBUT,Reach-1,3
Up Type=0
Dn Type=3
Dn Slope=0.005
Boundary for River Rch & Prof#=GUADALUPE TRIBUT,Reach-1,4
Up Type=0
Dn Type=3
Dn Slope=0.005
Boundary for River Rch & Prof#=GUADALUPE TRIBUT,Reach-1,5
Up Type=0
Dn Type=3
Dn Slope=0.005
Boundary for River Rch & Prof#=GUADALUPE TRIBUT,Reach-1,6
Up Type=0
Dn Type=3
Dn Slope=0.005
Boundary for River Rch & Prof#=GUADALUPE TRIBUT,Reach-1,7
Up Type=0
Dn Type=3
Dn Slope=0.005

--- GUADALUPE TRIBUTARY 9.g01 (geometry) ---

Geom Title=Existing Conditions

River Reach=GUADALUPE TRIBUT,Reach-1
Reach XY= 30
      2336925.00     13747675.00      2337034.82     13747664.57
      2337164.22     13747534.68      2337198.01     13747451.53
      2337369.74     13747319.53      2337380.55     13747222.63
      2337514.21     13747084.66      2337535.65     13747015.01
      2337669.58     13746927.67      2337678.83     13746826.59
      2337747.99     13746700.59      2337778.05     13746682.84
      2337864.53     13746724.42      2337923.02     13746669.38
      2337926.24     13746485.50      2337975.41     13746400.00
      2337914.25     13746265.29      2337827.44     13746180.52
      2337615.32     13746114.24      2337182.59     13745728.33
      2337374.63     13745509.84      2337372.72     13745380.93
      2337324.61     13745300.00      2337374.23     13745185.69
      2337277.16     13744969.02      2337278.37     13744876.22
      2337349.87     13744824.46      2337430.96     13744872.81
      2337519.12     13744873.08      2337625.00     13744775.00

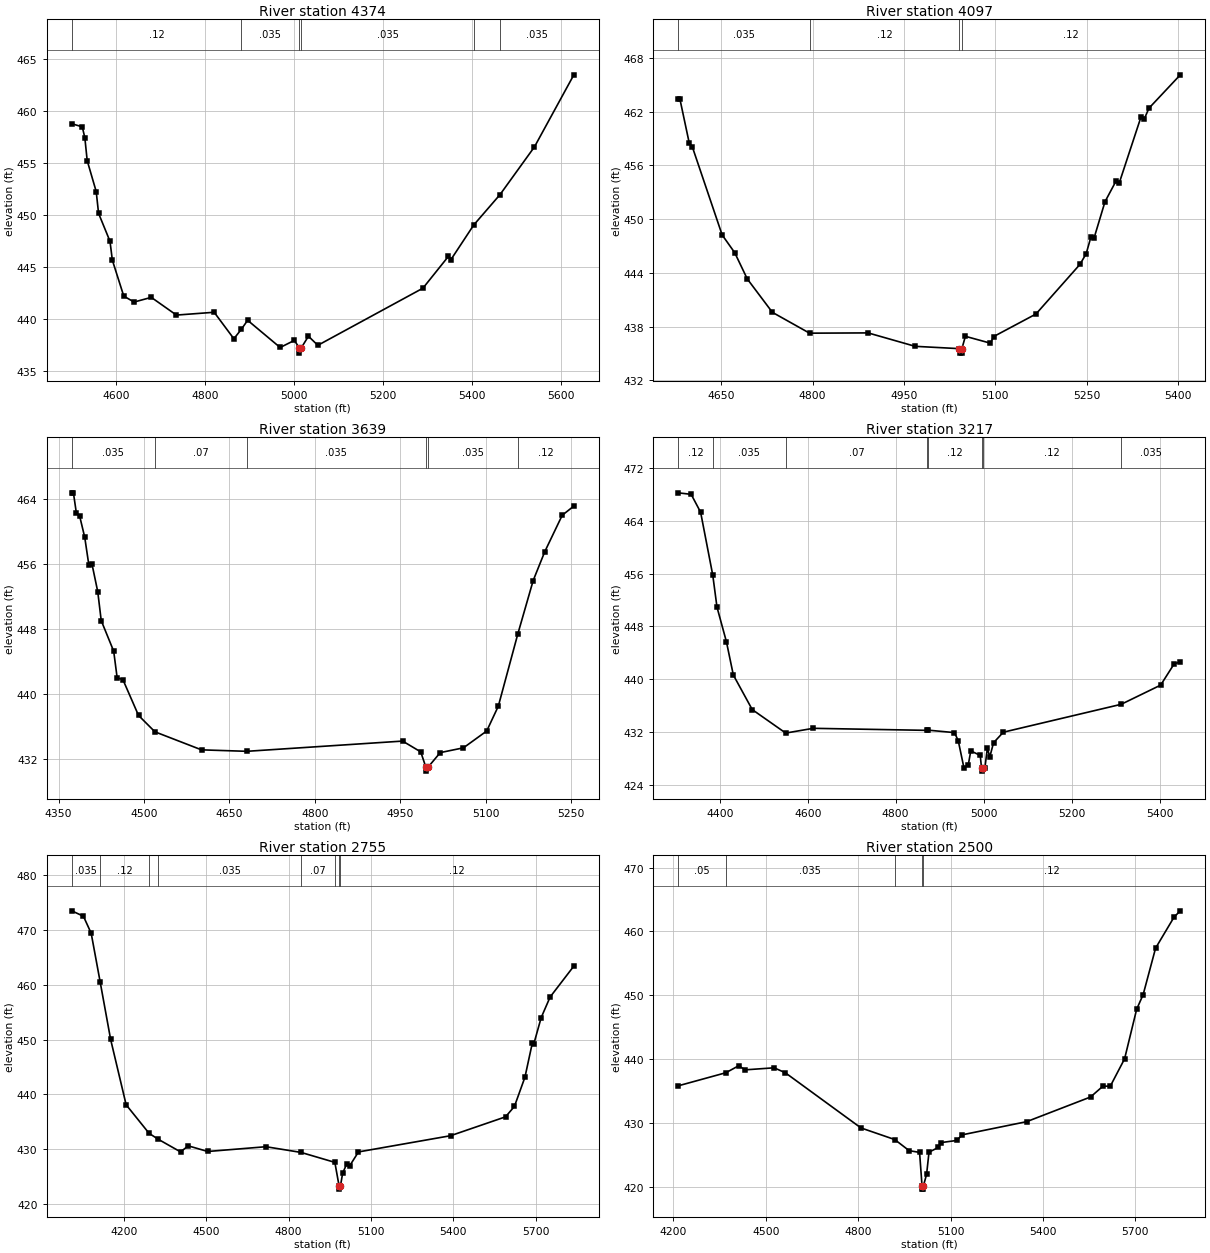
Type RM Length L Ch R = 1,4374,277,277,277
BEGIN DESCRIPTION:
A19403
END DESCRIPTION:
XS GIS Cut Line= 3
      2337129.89     13748147.27      2336931.98     13747584.77
      2336760.18     13747079.80
#Sta/Elev= 30
  4499.9  458.75  4523.5  458.45  4529.3  457.41  4534.6  455.21  4554.9  452.24
  4560.2  450.15  4585.9  447.47  4591.2  445.66  4616.9  442.21  4640.1  441.64
  4678.8  442.09  4735.4  440.39  4820.3  440.66  4864.6  438.12  4881.2  439.01
  4895.6  439.89  4968.8  437.28  5000.6  437.96  5012.1  437.24  5012.3  436.74
  5016.2  437.24  5032.4  438.36  5053.6  437.49  5290.0  442.97  5347.5  446.03
  5352.7  445.69  5404.3  449.03  5463.5  451.95  5541.0  456.53  5629.6  463.44
#Mann=6,-1,0
  4499.9    0.12       0  4881.2   0.035       0  5012.1   0.035       0
  5016.2   0.035       0  5404.3    0.12       0  5463.5   0.035       0
Bank Sta=5012.1,5016.2
Exp/Cntr=0.3,0.1

Type RM Length L Ch R = 1,4097,458,458,458
BEGIN DESCRIPTION:
GUADALUPE TRIBUTARY 9 9.0
END DESCRIPTION:
XS GIS Cut Line= 3
      2337275.00     13747924.99      2337175.00     13747525.00
      2337075.00     13747125.01
#Sta/Elev= 30
  4579.2  463.47  4581.8  463.47  4597.2  458.53  4602.4  458.07  4651.3  448.24
  4672.0  446.25  4692.6  443.32  4733.8  439.59  4794.9  437.26  4891.0  437.29
  4968.3  435.79  5041.0  435.53  5041.2  435.03  5044.8  435.03  5045.1  435.53
  5050.8  436.91  5092.0  436.14  5097.2  436.88  5166.7  439.40  5238.9  444.94
  5249.2  446.14  5256.9  447.99  5262.1  447.88  5280.1  451.95  5298.2  454.26
  5303.3  454.00  5339.4  461.46  5344.5  461.18  5352.3  462.40  5403.8  466.13
#Mann=4,-1,0
  4579.2   0.035       0  4794.9    0.12       0  5041.0    0.05       0
  5045.1    0.12       0
Bank Sta=5041,5045.1
Exp/Cntr=0.3,0.1

Type RM Length L Ch R = 1,3639,422,422,422
BEGIN DESCRIPTION:
GUADALUPE TRIBUTARY 9 8.0
END DESCRIPTION:
XS GIS Cut Line= 3
      2337975.01     13747475.00      2337425.00     13747175.00
      2337174.96     13747124.99
#Sta/Elev= 30
  4373.2  464.80  4376.1  464.80  4381.3  462.29  4387.0  461.95  4396.0  459.31
  4403.1  455.95  4408.8  455.99  4418.8  452.63  4424.9  449.07  4446.8  445.30
  4452.9  442.01  4462.9  441.81  4490.4  437.39  4519.2  435.37  4601.0  433.15
  4680.5  432.97  4954.1  434.23  4985.9  432.90  4994.8  431.03  4995.1  430.53
  4998.9  431.03  5020.1  432.81  5060.9  433.40  5101.7  435.47  5122.1  438.53
  5156.2  447.39  5183.3  454.00  5203.7  457.56  5234.3  462.04  5254.7  463.17
#Mann=6,-1,0
  4373.2   0.035       0  4519.2    0.07       0  4680.5   0.035       0
  4994.8   0.035       0  4998.9   0.035       0  5156.2    0.12       0
Bank Sta=4994.8,4998.9
Exp/Cntr=0.3,0.1

Type RM Length L Ch R = 1,3217,462,462,462
BEGIN DESCRIPTION:
GUADALUPE TRIBUTARY 9 7.0
END DESCRIPTION:
XS GIS Cut Line= 3
      2338025.00     13747475.00      2337675.00     13746875.00
      2337275.03     13746675.02
#Sta/Elev= 30
  4305.5  468.26  4334.9  468.03  4356.4  465.32  4384.1  455.75  4393.6  450.94
  4415.1  445.68  4430.8  440.64  4473.8  435.40  4549.9  431.84  4612.7  432.56
  4871.1  432.25  4872.4  432.29  4933.6  431.91  4942.2  430.71  4955.1  426.61
  4965.0  426.98  4970.8  429.14  4992.3  428.45  4995.2  426.57  4995.4  426.07
  4999.3  426.57  5002.9  426.57  5008.5  429.54  5014.1  428.23  5022.5  430.37
  5044.8  431.97  5312.8  436.20  5402.6  439.11  5433.4  442.34  5447.3  442.63
#Mann=8,-1,0
  4305.5    0.12       0  4384.1   0.035       0  4549.9    0.07       0
  4871.1   0.035       0  4872.4    0.12       0  4995.2    0.05       0
  4999.3    0.12       0  5312.8   0.035       0
Bank Sta=4995.2,4999.3
Exp/Cntr=0.3,0.1

Type RM Length L Ch R = 1,2755,255,255,255
BEGIN DESCRIPTION:
GUADALUPE TRIBUTARY 9 6.0
END DESCRIPTION:
XS GIS Cut Line= 3
      2338624.99     13747324.99      2337925.00     13746625.00
      2337124.99     13746375.00
#Sta/Elev= 30
  4010.7  473.53  4053.1  472.54  4081.4  469.43  4114.2  460.50  4152.1  450.05
  4208.7  438.08  4292.2  432.87  4324.9  431.80  4406.7  429.48  4434.9  430.58
  4505.7  429.55  4717.8  430.42  4845.4  429.38  4968.6  427.56  4984.3  423.17
  4984.6  422.67  4988.7  423.17  4997.1  425.61  5011.1  427.18  5022.1  426.89
  5054.6  429.47  5389.8  432.43  5590.0  435.88  5622.4  437.78  5660.7  443.12
  5687.4  449.33  5692.6  449.13  5719.9  454.02  5752.4  457.78  5838.8  463.43
#Mann=8,-1,0
  4010.7   0.035       0  4114.2    0.12       0  4292.2    0.05       0
  4324.9   0.035       0  4845.4    0.07       0  4968.6    0.12       0
  4984.3    0.05       0  4988.7    0.12       0
Bank Sta=4984.3,4988.7
Exp/Cntr=0.3,0.1

Type RM Length L Ch R = 1,2500,196,196,196
BEGIN DESCRIPTION:
A19402
END DESCRIPTION:
XS GIS Cut Line= 4
      2338650.71     13746001.45      2338077.81     13746366.02
      2337838.23     13746412.90      2337135.14     13746334.78
#Sta/Elev= 30
  4215.5  435.84  4370.3  437.89  4411.8  438.98  4433.0  438.34  4527.0  438.66
  4563.4  437.88  4808.9  429.25  4918.6  427.43  4965.5  425.69  4999.3  425.42
  5007.3  420.17  5007.6  419.67  5011.4  419.67  5011.7  420.17  5022.1  421.99
  5029.9  425.45  5060.5  426.21  5068.5  426.95  5120.1  427.29  5137.8  428.17
  5347.1  430.23  5554.5  434.09  5594.7  435.78  5618.8  435.79  5665.1  440.06
  5704.3  447.82  5725.5  450.13  5765.8  457.39  5826.1  462.27  5846.1  463.23
#Mann=5,-1,0
  4215.5    0.05       0  4370.3   0.035       0  4918.6    0.12       0
  5007.3    0.05       0  5011.7    0.12       0
Bank Sta=5007.3,5011.7
Exp/Cntr=0.3,0.1

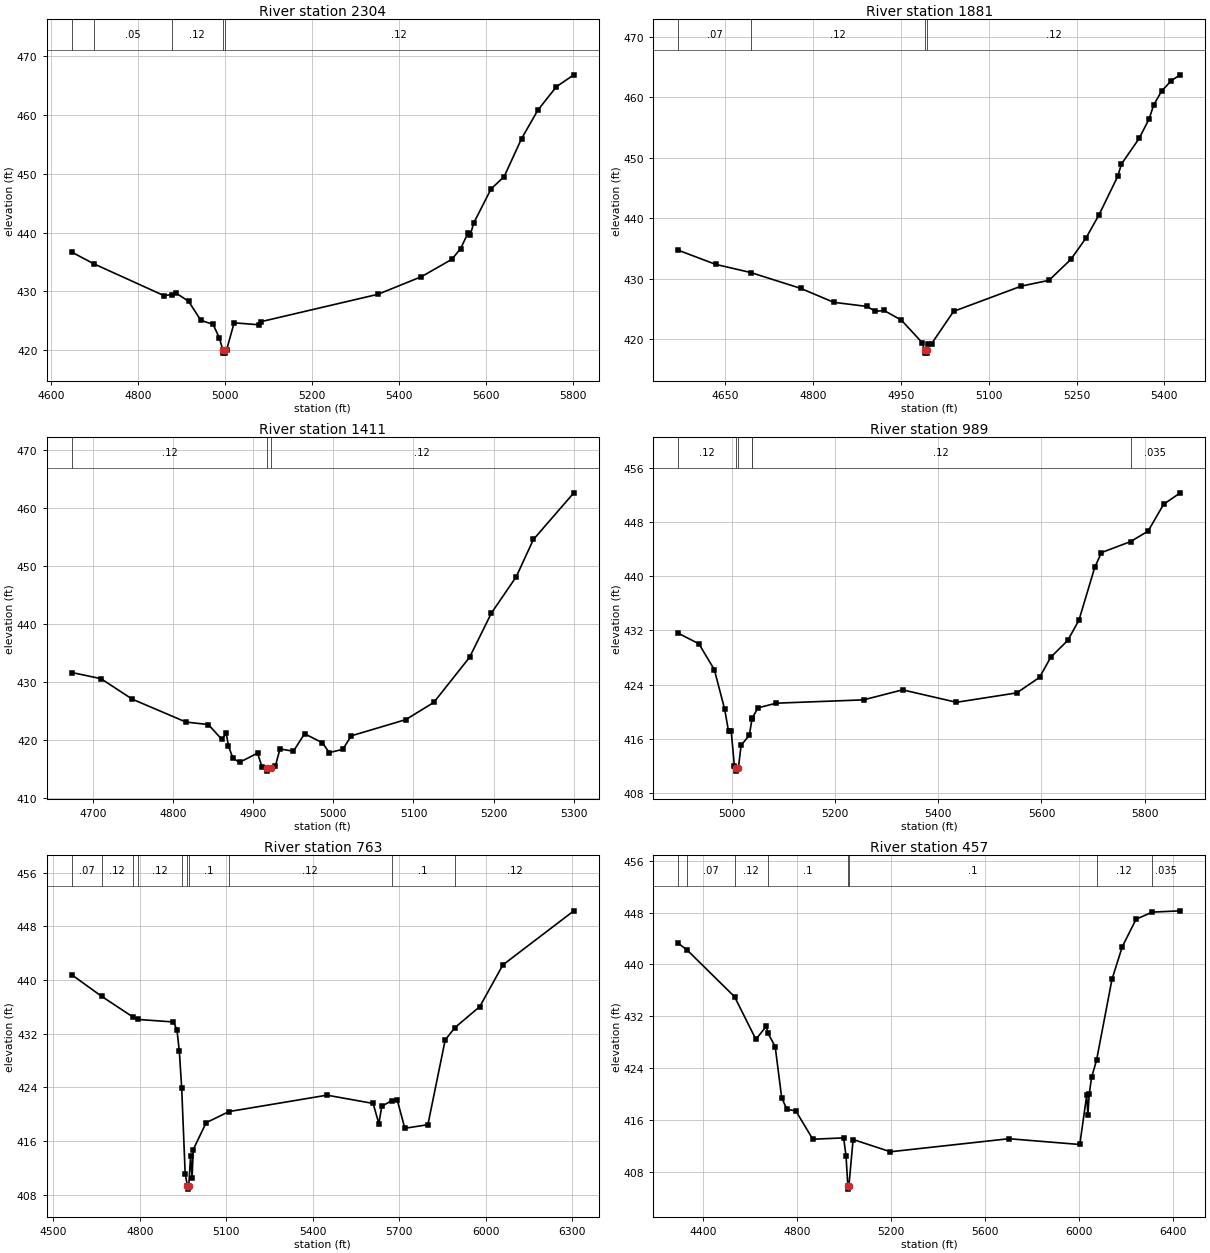
Type RM Length L Ch R = 1,2304,423,423,423
BEGIN DESCRIPTION:
GUADALUPE TRIBUTARY 9 5.0
END DESCRIPTION:
XS GIS Cut Line= 3
      2338124.96     13745975.04      2337875.00     13746225.00
      2337074.96     13746275.00
#Sta/Elev= 30
  4647.0  436.66  4697.5  434.68  4859.1  429.26  4876.7  429.44  4887.4  429.66
  4915.7  428.30  4943.9  425.06  4972.2  424.36  4986.4  422.07  4994.8  419.97
  4995.1  419.47  4998.9  419.47  4999.2  419.97  5003.0  419.97  5020.5  424.63
  5078.2  424.29  5083.2  424.84  5351.2  429.48  5451.4  432.48  5521.5  435.44
  5541.6  437.27  5559.1  439.98  5564.1  439.64  5571.6  441.60  5611.7  447.42
  5641.8  449.52  5681.8  455.98  5719.4  460.84  5762.0  464.82  5802.1  466.84
#Mann=5,-1,0
  4647.0    0.07       0  4697.5    0.05       0  4876.7    0.12       0
  4994.8    0.05       0  4999.2    0.12       0
Bank Sta=4994.8,4999.2
Exp/Cntr=0.3,0.1

Type RM Length L Ch R = 1,1881,470,470,470
BEGIN DESCRIPTION:
GUADALUPE TRIBUTARY 9 4.0
END DESCRIPTION:
XS GIS Cut Line= 3
      2337775.02     13745674.97      2337525.00     13746025.00
      2337124.96     13746175.01
#Sta/Elev= 30
  4569.8  434.75  4633.7  432.41  4693.7  431.06  4778.8  428.45  4835.3  426.14
  4891.8  425.46  4906.6  424.65  4921.3  424.79  4950.8  423.20  4986.4  419.47
  4990.4  418.24  4990.7  417.74  4994.5  417.74  4994.8  418.24  4996.9  419.32
  5002.6  419.32  5040.0  424.64  5155.7  428.82  5202.9  429.77  5240.3  433.24
  5266.1  436.76  5288.3  440.58  5320.4  446.98  5326.6  448.98  5356.8  453.22
  5373.8  456.42  5381.8  458.76  5395.1  461.03  5412.0  462.80  5427.2  463.74
#Mann=4,-1,0
  4569.8    0.07       0  4693.7    0.12       0  4990.4    0.05       0
  4994.8    0.12       0
Bank Sta=4990.4,4994.8
Exp/Cntr=0.3,0.1

Type RM Length L Ch R = 1,1411,422,422,422
BEGIN DESCRIPTION:
GUADALUPE TRIBUTARY 9 3.0
END DESCRIPTION:
XS GIS Cut Line= 3
      2337475.03     13745574.98      2337175.00     13745725.00
      2337025.00     13745975.00
#Sta/Elev= 30
  4673.3  431.61  4709.7  430.55  4748.8  427.01  4815.9  423.05  4843.8  422.62
  4860.6  420.07  4866.2  421.08  4869.0  418.92  4874.6  416.77  4883.0  416.10
  4905.3  417.68  4910.9  415.29  4917.1  415.07  4917.4  414.57  4921.6  415.07
  4927.7  415.52  4933.3  418.40  4950.1  418.01  4964.0  421.03  4986.4  419.46
  4994.8  417.77  5011.7  418.33  5022.4  420.67  5090.4  423.47  5125.4  426.44
  5170.1  434.24  5197.3  441.87  5228.4  448.17  5249.8  454.60  5300.3  462.66
#Mann=3,-1,0
  4673.3    0.12       0  4917.1    0.05       0  4921.6    0.12       0
Bank Sta=4917.1,4921.6
Exp/Cntr=0.3,0.1

Type RM Length L Ch R = 1,989,226,226,226
BEGIN DESCRIPTION:
GUADALUPE TRIBUTARY 9 2.0
END DESCRIPTION:
XS GIS Cut Line= 3
      2337474.98     13745375.00      2337375.00     13745375.00
      2336575.00     13745725.00
#Sta/Elev= 30
  4895.9  431.57  4935.9  430.02  4965.9  426.19  4985.9  420.36  4993.4  417.09
  4998.6  417.09  5004.8  411.94  5008.1  411.72  5008.4  411.22  5012.6  411.72
  5017.7  415.02  5033.7  416.52  5039.0  418.97  5039.1  419.02  5050.5  420.56
  5085.9  421.25  5255.1  421.74  5330.7  423.22  5435.2  421.38  5552.2  422.77
  5596.2  425.06  5618.0  428.03  5650.8  430.51  5672.6  433.50  5703.4  441.33
  5716.3  443.48  5772.6  445.10  5806.7  446.65  5836.7  450.61  5869.1  452.30
#Mann=6,-1,0
  4895.9    0.12       0  5008.1    0.05       0  5012.6    0.12       0
  5039.0     0.1       0  5039.1    0.12       0  5772.6   0.035       0
Bank Sta=5008.1,5012.6
Exp/Cntr=0.3,0.1

Type RM Length L Ch R = 1,763,306,306,306
BEGIN DESCRIPTION:
A19401
END DESCRIPTION:
XS GIS Cut Line= 4
      2337801.77     13745256.65      2337385.10     13745178.52
      2337187.19     13745246.23      2336078.89     13745209.81
#Sta/Elev= 30
  4563.8  440.79  4667.4  437.58  4776.0  434.50  4794.9  434.13  4916.6  433.76
  4928.7  432.58  4937.0  429.40  4945.2  423.90  4957.3  411.08  4965.2  409.35
  4965.5  408.85  4969.7  409.35  4976.1  413.80  4981.2  410.50  4985.2  414.74
  5030.1  418.75  5109.5  420.41  5449.2  422.85  5609.3  421.62  5629.3  418.61
  5639.3  421.17  5673.2  422.04  5692.7  422.18  5719.4  417.92  5799.4  418.45
  5859.5  431.09  5893.2  432.92  5979.5  436.05  6059.6  442.26  6305.8  450.32
#Mann=10,-1,0
  4563.8    0.07       0  4667.4    0.12       0  4776.0    0.07       0
  4794.9    0.12       0  4945.2     0.1       0  4965.2    0.05       0
  4969.7     0.1       0  5109.5    0.12       0  5673.2     0.1       0
  5893.2    0.12       0
Bank Sta=4965.2,4969.7
Exp/Cntr=0.3,0.1

Type RM Length L Ch R = 1,457,0,0,0
BEGIN DESCRIPTION:
GUADALUPE TRIBUTARY 9 1.0
END DESCRIPTION:
XS GIS Cut Line= 3
      2337900.73     13745225.40      2337312.19     13744912.90
      2335849.28     13744772.33
#Sta/Elev= 30
  4295.5  443.25  4332.3  442.25  4535.1  435.02  4625.8  428.45  4669.7  430.44
  4677.4  429.39  4708.0  427.32  4735.7  419.42  4757.7  417.68  4796.0  417.40
  4868.1  413.05  4999.2  413.26  5009.3  410.49  5017.1  405.86  5017.4  405.36
  5021.6  405.86  5039.4  413.01  5198.2  411.12  5702.4  413.13  6003.8  412.24
  6033.3  419.81  6038.3  416.74  6044.0  420.05  6054.1  422.59  6075.2  425.24
  6140.8  437.70  6184.7  442.74  6243.3  446.96  6311.6  448.06  6431.5  448.26
#Mann=8,-1,0
  4295.5    0.12       0  4332.3    0.07       0  4535.1    0.12       0
  4677.4     0.1       0  5017.1    0.05       0  5021.6     0.1       0
  6075.2    0.12       0  6311.6   0.035       0
Bank Sta=5017.1,5021.6
Exp/Cntr=0.3,0.1

Chan Stop Cuts=-1