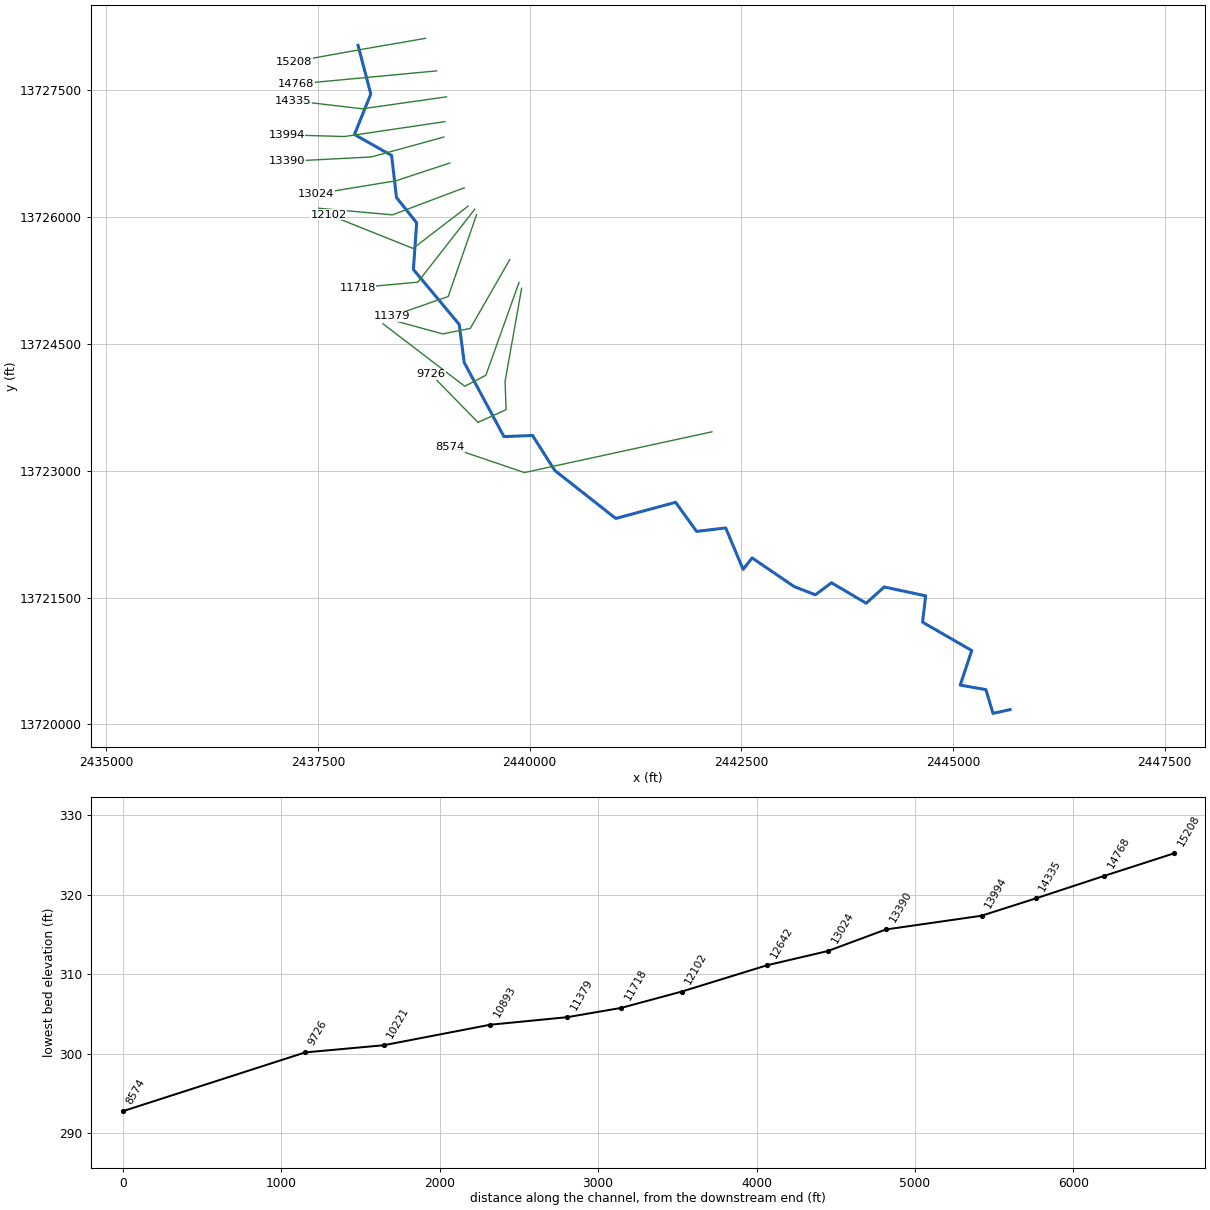
--- KEIFER SLOUGH.prj (project) ---

Proj Title=KEIFER SLOUGH Base Level Engineering
Current Plan=p01
Default Exp/Contr=0.3,0.1
English Units
Geom File=g01
Flow File=f01
Plan File=p01
BEGIN DESCRIPTION:
KEIFER SLOUGH
END DESCRIPTION:

--- KEIFER SLOUGH.p01 (plan) ---

Plan Title=Multiple Run
Short Identifier=Multiple
Geom File=g01
Flow File=f01
Subcritical Flow
K Sum by GR= 0
Std Step Tol= 0.01
Critical Tol= 0.01
Num of Std Step Trials= 20
Max Error Tol= 0.3
Flow Tol Ratio= 0.001
Split Flow NTrial= 30
Split Flow Tol= 0.02
Split Flow Ratio= 0.02
Log Output Level= 0
Friction Slope Method= 1
Unsteady Friction Slope Method= 2
Unsteady Bridges Friction Slope Method= 1
Parabolic Critical Depth
Global Vel Dist=  1 , 1 , 1
Global Log Level= 0
CheckData=True
Encroach Param= -1, 0, 0, 0
BEGIN DESCRIPTION:
Multiple Run
END DESCRIPTION:

--- KEIFER SLOUGH.f01 (steady flow) ---

Flow Title=Multiple
Number of Profiles=7
Profile Names=10-year,25-year,50-year,1pct_min,100-year,1pct_plu,500-year
River Rch & RM= KEIFER SLOUGH,Reach-1,15208
     827    1346    1818    1189    2372    4733    3997
Boundary for River Rch & Prof#=KEIFER SLOUGH,Reach-1,1
Up Type=0
Dn Type=3
Dn Slope=0.005
Boundary for River Rch & Prof#=KEIFER SLOUGH,Reach-1,2
Up Type=0
Dn Type=3
Dn Slope=0.005
Boundary for River Rch & Prof#=KEIFER SLOUGH,Reach-1,3
Up Type=0
Dn Type=3
Dn Slope=0.005
Boundary for River Rch & Prof#=KEIFER SLOUGH,Reach-1,4
Up Type=0
Dn Type=3
Dn Slope=0.005
Boundary for River Rch & Prof#=KEIFER SLOUGH,Reach-1,5
Up Type=0
Dn Type=3
Dn Slope=0.005
Boundary for River Rch & Prof#=KEIFER SLOUGH,Reach-1,6
Up Type=0
Dn Type=3
Dn Slope=0.005
Boundary for River Rch & Prof#=KEIFER SLOUGH,Reach-1,7
Up Type=0
Dn Type=3
Dn Slope=0.005

--- KEIFER SLOUGH.g01 (geometry) ---

Geom Title=Existing Conditions

River Reach=KEIFER SLOUGH,Reach-1
Reach XY= 30
      2437975.00     13728025.00      2438125.42     13727450.00
      2437932.69     13726971.33      2438371.24     13726723.44
      2438428.75     13726226.55      2438667.21     13725928.43
      2438628.54     13725376.46      2439169.48     13724727.43
      2439228.74     13724276.52      2439697.86     13723401.36
      2440035.17     13723414.68      2440298.13     13723001.18
      2441018.26     13722434.13      2441725.00     13722625.00
      2441972.67     13722280.83      2442316.49     13722322.43
      2442521.60     13721832.41      2442628.15     13721967.49
      2443126.47     13721628.56      2443375.00     13721532.08
      2443565.36     13721674.36      2443975.10     13721432.32
      2444188.86     13721624.48      2444677.74     13721519.66
      2444641.28     13721208.30      2445221.91     13720873.36
      2445085.76     13720464.61      2445389.16     13720411.63
      2445472.71     13720130.80      2445675.00     13720175.00

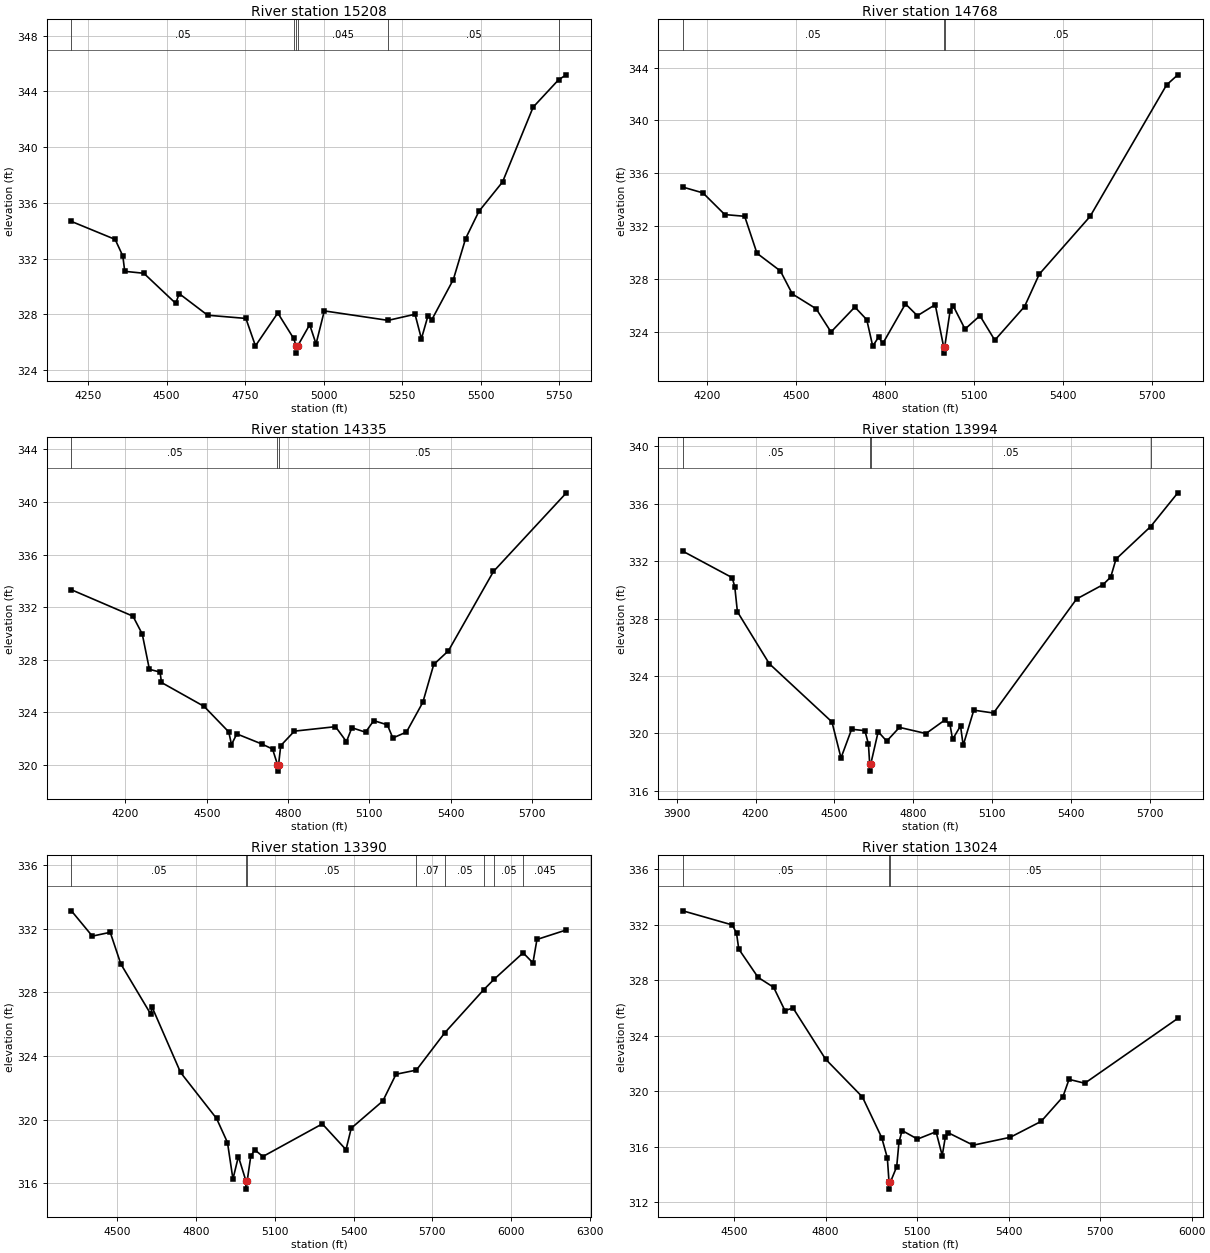
Type RM Length L Ch R = 1,15208,440,440,440
BEGIN DESCRIPTION:
KEIFER SLOUGH 16.0
END DESCRIPTION:
XS GIS Cut Line= 3
      2438772.18     13728107.67      2438055.19     13727983.83
      2437220.86     13727833.91
#Sta/Elev= 30
  4197.2  334.66  4336.4  333.37  4360.8  332.18  4366.9  331.08  4427.7  330.94
  4529.2  328.78  4540.2  329.48  4630.7  327.93  4752.5  327.70  4782.9  325.73
  4854.0  328.09  4904.3  326.27  4912.9  325.71  4913.1  325.21  4916.9  325.71
  4955.5  327.25  4975.8  325.87  5002.1  328.24  5205.1  327.56  5290.8  328.00
  5311.1  326.24  5331.4  327.84  5344.5  327.62  5412.7  330.49  5451.8  333.43
  5494.0  335.38  5569.3  337.49  5666.7  342.86  5748.3  344.84  5772.5  345.18
#Mann=6,-1,0
  4197.2    0.05       0  4904.3   0.045       0  4912.9   0.045       0
  4916.9   0.045       0  5205.1    0.05       0  5748.3   0.045       0
Bank Sta=4912.9,4916.9
Exp/Cntr=0.3,0.1

Type RM Length L Ch R = 1,14768,433,433,433
BEGIN DESCRIPTION:
A19518
END DESCRIPTION:
XS GIS Cut Line= 2
      2438902.54     13727723.09      2437240.39     13727566.65
#Sta/Elev= 30
  4118.8  334.95  4186.6  334.51  4260.2  332.87  4327.3  332.74  4368.8  329.94
  4447.8  328.60  4488.0  326.86  4568.3  325.74  4618.5  323.98  4698.9  325.87
  4739.1  324.91  4759.2  322.91  4779.2  323.60  4793.2  323.11  4869.6  326.11
  4909.8  325.21  4970.1  326.05  4998.2  322.88  4998.5  322.38  5002.2  322.88
  5020.3  325.59  5030.4  325.97  5070.5  324.20  5120.8  325.21  5171.0  323.36
  5271.4  325.91  5321.1  328.36  5492.4  332.73  5750.5  342.69  5788.3  343.45
#Mann=3,-1,0
  4118.8    0.05       0  4998.2    0.05       0  5002.2    0.05       0
Bank Sta=4998.2,5002.2
Exp/Cntr=0.3,0.1

Type RM Length L Ch R = 1,14335,341,341,341
BEGIN DESCRIPTION:
KEIFER SLOUGH 15.0
END DESCRIPTION:
XS GIS Cut Line= 3
      2439019.89     13727416.72      2438025.00     13727275.00
      2437208.86     13727370.97
#Sta/Elev= 30
  4000.5  333.33  4227.7  331.32  4262.0  329.96  4288.3  327.28  4327.7  327.07
  4332.8  326.28  4490.3  324.46  4581.2  322.52  4591.3  321.56  4610.9  322.37
  4702.4  321.61  4742.8  321.22  4761.0  320.04  4761.3  319.54  4765.0  320.04
  4773.1  321.48  4823.4  322.58  4975.1  322.92  5015.5  321.78  5035.6  322.84
  5086.0  322.50  5116.2  323.38  5166.5  323.06  5186.7  322.06  5237.0  322.51
  5297.4  324.77  5337.7  327.65  5391.9  328.69  5558.1  334.72  5827.2  340.70
#Mann=3,-1,0
  4000.5    0.05       0  4761.0    0.05       0  4765.0    0.05       0
Bank Sta=4761,4765
Exp/Cntr=0.3,0.1

Type RM Length L Ch R = 1,13994,604,604,604
BEGIN DESCRIPTION:
A19517
END DESCRIPTION:
XS GIS Cut Line= 3
      2439000.35     13727123.40      2437814.01     13726947.40
      2437129.81     13726966.95
#Sta/Elev= 30
  3923.5  332.70  4110.9  330.86  4121.0  330.24  4131.1  328.48  4252.4  324.86
  4490.9  320.80  4525.4  318.29  4565.8  320.29  4616.3  320.19  4629.8  319.26
  4634.5  317.87  4634.8  317.37  4638.7  317.87  4666.9  320.12  4699.3  319.46
  4747.8  320.42  4848.9  319.99  4919.6  320.92  4939.8  320.66  4950.0  319.59
  4980.3  320.52  4990.4  319.17  5030.8  321.62  5105.9  321.42  5422.0  329.37
  5522.0  330.36  5552.0  330.90  5572.0  332.15  5703.9  334.42  5807.3  336.77
#Mann=4,-1,0
  3923.5    0.05       0  4634.5    0.05       0  4638.7    0.05       0
  5703.9   0.045       0
Bank Sta=4634.5,4638.7
Exp/Cntr=0.3,0.1

Type RM Length L Ch R = 1,13390,366,366,366
BEGIN DESCRIPTION:
A19516
END DESCRIPTION:
XS GIS Cut Line= 3
      2438987.30     13726940.88      2438133.41     13726706.22
      2437138.02     13726654.17
#Sta/Elev= 30
  4327.2  333.13  4406.7  331.54  4474.8  331.78  4515.1  329.79  4628.8  326.64
  4634.0  327.08  4742.4  322.97  4879.2  320.08  4920.7  318.57  4941.5  316.27
  4962.2  317.69  4991.2  316.14  4991.5  315.64  4995.5  316.14  5009.3  317.71
  5024.4  318.11  5055.5  317.69  5281.3  319.74  5371.4  318.12  5391.4  319.47
  5511.6  321.18  5561.6  322.86  5639.0  323.12  5747.3  325.47  5895.6  328.18
  5934.8  328.83  6045.0  330.49  6082.3  329.86  6097.6  331.33  6209.5  331.93
#Mann=8,-1,0
  4327.2    0.05       0  4991.2    0.05       0  4995.5    0.05       0
  5639.0    0.07       0  5747.3    0.05       0  5895.6    0.07       0
  5934.8    0.05       0  6045.0   0.045       0
Bank Sta=4991.2,4995.5
Exp/Cntr=0.3,0.1

Type RM Length L Ch R = 1,13024,382,382,382
BEGIN DESCRIPTION:
KEIFER SLOUGH 14.0
END DESCRIPTION:
XS GIS Cut Line= 3
      2439059.07     13726634.53      2438425.00     13726425.00
      2437483.10     13726269.74
#Sta/Elev= 30
  4332.3  333.01  4494.6  331.99  4508.2  331.39  4515.6  330.25  4578.8  328.21
  4629.9  327.49  4666.9  325.81  4693.4  326.00  4800.0  322.31  4920.8  319.58
  4984.2  316.64  5002.6  315.18  5008.1  313.43  5008.4  312.93  5012.4  313.43
  5033.2  314.54  5040.6  316.30  5050.8  317.16  5101.4  316.54  5162.2  317.07
  5182.5  315.35  5192.7  316.70  5202.8  316.99  5283.9  316.10  5405.5  316.67
  5506.8  317.82  5577.8  319.58  5598.1  320.85  5649.7  320.57  5954.7  325.25
#Mann=3,-1,0
  4332.3    0.05       0  5008.1    0.05       0  5012.4    0.05       0
Bank Sta=5008.1,5012.4
Exp/Cntr=0.3,0.1

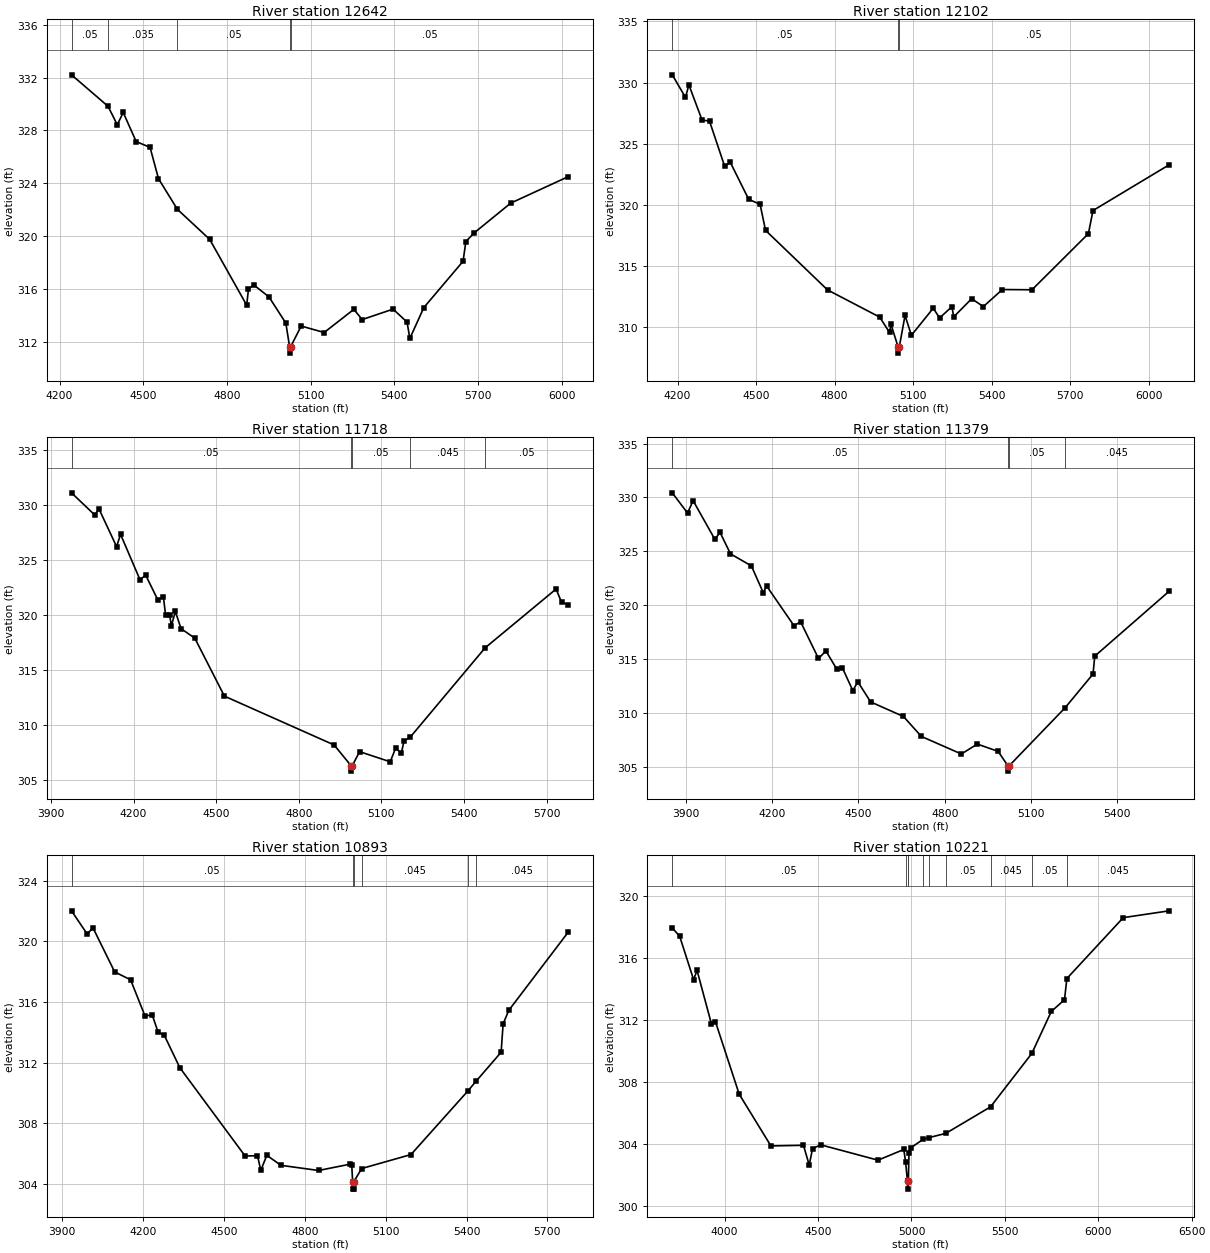
Type RM Length L Ch R = 1,12642,540,540,540
BEGIN DESCRIPTION:
A19515
END DESCRIPTION:
XS GIS Cut Line= 3
      2439228.50     13726341.19      2438381.11     13726021.79
      2437508.89     13726099.89
#Sta/Elev= 30
  4242.9  332.21  4373.8  329.83  4406.9  328.43  4428.3  329.36  4474.7  327.16
  4524.5  326.72  4554.7  324.35  4622.6  322.03  4738.2  319.76  4870.9  314.78
  4877.2  315.98  4895.8  316.32  4950.9  315.40  5011.3  313.42  5024.6  311.65
  5024.9  311.15  5028.9  311.65  5066.3  313.20  5148.5  312.71  5255.0  314.46
  5285.1  313.69  5395.6  314.48  5445.8  313.50  5455.8  312.26  5506.0  314.60
  5646.6  318.10  5656.6  319.59  5685.4  320.23  5817.3  322.50  6024.2  324.51
#Mann=5,-1,0
  4242.9    0.05       0  4373.8   0.035       0  4622.6    0.05       0
  5024.6    0.05       0  5028.9    0.05       0
Bank Sta=5024.6,5028.9
Exp/Cntr=0.3,0.1

Type RM Length L Ch R = 1,12102,384,384,384
BEGIN DESCRIPTION:
KEIFER SLOUGH 13.0
END DESCRIPTION:
XS GIS Cut Line= 3
      2439275.02     13726125.01      2438625.00     13725625.00
      2437625.02     13726024.99
#Sta/Elev= 30
  4179.9  330.63  4230.4  328.78  4243.3  329.81  4293.5  326.93  4322.2  326.83
  4380.2  323.12  4401.0  323.48  4471.7  320.43  4515.2  320.02  4536.0  317.89
  4772.6  313.01  4971.9  310.78  5009.4  309.52  5014.8  310.20  5042.2  308.33
  5042.5  307.83  5046.6  308.33  5068.6  310.92  5092.9  309.29  5176.3  311.51
  5200.6  310.71  5247.7  311.64  5254.4  310.80  5323.1  312.29  5367.5  311.64
  5440.2  313.04  5553.3  313.02  5768.7  317.62  5786.2  319.51  6077.0  323.26
#Mann=3,-1,0
  4179.9    0.05       0  5042.2    0.05       0  5046.6    0.05       0
Bank Sta=5042.2,5046.6
Exp/Cntr=0.3,0.1

Type RM Length L Ch R = 1,11718,339,339,339
BEGIN DESCRIPTION:
A19514
END DESCRIPTION:
XS GIS Cut Line= 3
      2439352.34     13726086.96      2438680.96     13725226.54
      2437970.41     13725161.35
#Sta/Elev= 30
  3974.5  331.08  4059.5  329.05  4074.0  329.63  4138.2  326.19  4152.7  327.30
  4223.2  323.18  4244.0  323.59  4287.5  321.37  4308.3  321.61  4316.4  319.94
  4330.9  319.99  4337.2  318.98  4351.7  320.29  4372.5  318.72  4422.2  317.87
  4529.9  312.59  4928.3  308.15  4989.8  306.27  4990.1  305.77  4994.4  306.27
  5021.0  307.54  5132.1  306.62  5152.2  307.88  5172.3  307.38  5182.3  308.51
  5204.9  308.86  5476.8  316.98  5734.6  322.33  5754.7  321.12  5779.4  320.92
#Mann=5,-1,0
  3974.5    0.05       0  4989.8    0.05       0  4994.4    0.05       0
  5204.9   0.045       0  5476.8    0.05       0
Bank Sta=4989.8,4994.4
Exp/Cntr=0.3,0.1

Type RM Length L Ch R = 1,11379,486,486,486
BEGIN DESCRIPTION:
KEIFER SLOUGH 12.0
END DESCRIPTION:
XS GIS Cut Line= 3
      2439375.01     13726025.03      2439039.47     13725057.06
      2438375.01     13724825.00
#Sta/Elev= 30
  3852.4  330.43  3905.4  328.56  3925.0  329.70  4000.6  326.11  4018.4  326.77
  4054.9  324.77  4127.6  323.65  4168.8  321.17  4180.5  321.79  4275.8  318.10
  4298.7  318.47  4361.0  315.06  4386.8  315.76  4424.0  314.10  4443.8  314.21
  4480.3  312.09  4498.0  312.89  4542.5  311.03  4656.5  309.68  4718.8  307.83
  4857.9  306.20  4913.4  307.12  4985.8  306.44  5019.8  305.11  5020.2  304.61
  5024.4  305.11  5218.8  310.49  5315.9  313.62  5322.0  315.28  5580.7  321.30
#Mann=4,-1,0
  3852.4    0.05       0  5019.8    0.05       0  5024.4    0.05       0
  5218.8   0.045       0
Bank Sta=5019.8,5024.4
Exp/Cntr=0.3,0.1

Type RM Length L Ch R = 1,10893,672,672,672
BEGIN DESCRIPTION:
A19513
END DESCRIPTION:
XS GIS Cut Line= 4
      2439766.95     13725493.73      2439300.36     13724679.90
      2438974.84     13724614.79      2438421.47     13724766.70
#Sta/Elev= 30
  3934.0  322.02  3992.1  320.49  4013.6  320.90  4094.2  317.99  4153.2  317.47
  4206.4  315.10  4233.7  315.14  4255.3  314.02  4278.3  313.81  4336.0  311.67
  4578.0  305.85  4624.1  305.86  4636.5  304.90  4658.7  305.89  4711.3  305.23
  4850.8  304.89  4968.9  305.31  4974.0  305.22  4977.2  304.16  4977.6  303.66
  4981.5  303.66  4981.8  304.16  5011.0  305.02  5193.7  305.94  5403.6  310.11
  5434.9  310.77  5528.2  312.69  5535.7  314.56  5556.5  315.45  5777.9  320.63
#Mann=6,-1,0
  3934.0    0.05       0  4977.2    0.05       0  4981.8    0.05       0
  5011.0   0.045       0  5403.6    0.05       0  5434.9   0.045       0
Bank Sta=4977.2,4981.8
Exp/Cntr=0.3,0.1

Type RM Length L Ch R = 1,10221,495,495,495
BEGIN DESCRIPTION:
A19512
END DESCRIPTION:
XS GIS Cut Line= 4
      2439875.46     13725222.46      2439484.82     13724126.51
      2439235.25     13723996.30      2438269.78     13724733.97
#Sta/Elev= 30
  3719.5  317.95  3759.3  317.40  3833.6  314.61  3852.2  315.20  3929.1  311.75
  3950.4  311.90  4077.8  307.21  4247.6  303.87  4421.8  303.91  4452.6  302.64
  4470.6  303.70  4514.2  303.94  4820.9  302.95  4959.0  303.64  4968.4  302.85
  4978.8  301.58  4979.1  301.08  4983.4  301.58  4986.7  303.43  4995.6  303.74
  5064.3  304.31  5095.1  304.41  5183.7  304.68  5423.1  306.39  5644.2  309.84
  5748.5  312.55  5819.2  313.31  5832.0  314.68  6133.8  318.61  6379.5  319.05
#Mann=10,-1,0
  3719.5    0.05       0  4968.4    0.07       0  4978.8    0.05       0
  4983.4    0.07       0  5064.3    0.05       0  5095.1    0.07       0
  5183.7    0.05       0  5423.1   0.045       0  5644.2    0.05       0
  5832.0   0.045       0
Bank Sta=4978.8,4983.4
Exp/Cntr=0.3,0.1

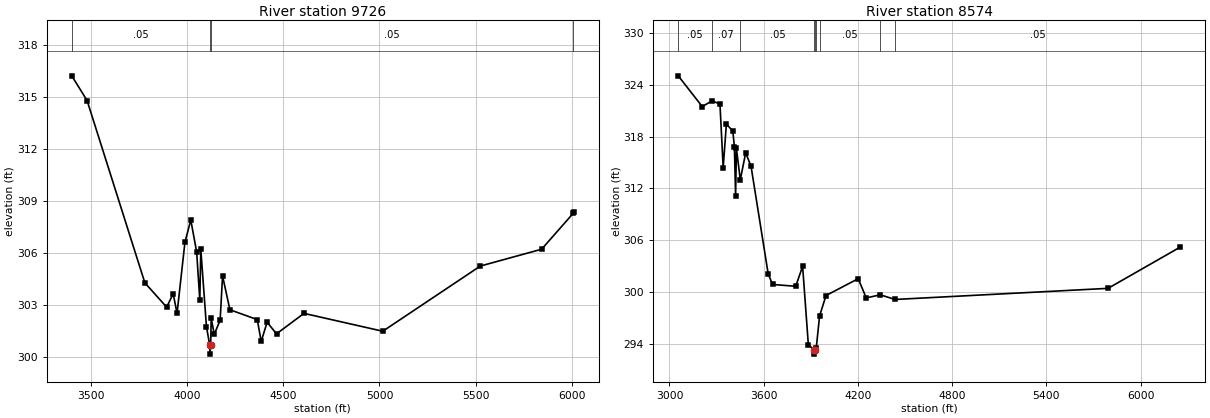
Type RM Length L Ch R = 1,9726,1152,1152,1152
BEGIN DESCRIPTION:
A19519
END DESCRIPTION:
XS GIS Cut Line= 5
      2439906.41     13725153.49      2439710.87     13724051.92
      2439723.90     13723719.48      2439391.46     13723569.56
      2438838.73     13724135.29
#Sta/Elev= 30
  3402.2  316.23  3481.9  314.80  3781.8  304.29  3894.9  302.89  3928.8  303.66
  3948.9  302.53  3989.7  306.62  4020.2  307.92  4050.7  306.07  4067.1  303.29
  4072.2  306.22  4101.5  301.77  4118.8  300.68  4119.1  300.18  4123.4  300.68
  4126.1  302.25  4142.1  301.32  4172.6  302.14  4185.2  304.69  4223.3  302.74
  4365.5  302.17  4385.8  300.91  4416.5  302.02  4465.4  301.35  4608.0  302.53
  5017.0  301.50  5523.8  305.26  5841.9  306.23  6006.7  308.31  6009.3  308.38
#Mann=4,-1,0
  3402.2    0.05       0  4118.8    0.05       0  4123.4    0.05       0
  6006.7   0.045       0
Bank Sta=4118.8,4123.4
Exp/Cntr=0.3,0.1

Type RM Length L Ch R = 1,8574,0,0,0
BEGIN DESCRIPTION:
KEIFER SLOUGH 11.0
END DESCRIPTION:
XS GIS Cut Line= 3
      2442154.52     13723458.11      2439939.01     13722976.38
      2439059.54     13723276.05
#Sta/Elev= 30
  3055.9  325.06  3208.9  321.49  3271.0  322.16  3321.5  321.79  3342.0  314.41
  3362.4  319.46  3403.4  318.66  3413.6  316.78  3421.1  311.12  3426.2  316.64
  3451.0  313.00  3485.2  316.13  3519.4  314.57  3628.5  302.09  3656.5  300.86
  3803.8  300.65  3847.8  302.96  3884.3  293.85  3922.9  293.28  3923.3  292.78
  3927.6  293.28  3934.3  293.44  3955.8  297.22  3996.9  299.58  4201.6  301.53
  4252.8  299.30  4342.3  299.66  4436.1  299.12  5792.3  300.41  6252.3  305.20
#Mann=9,-1,0
  3055.9    0.05       0  3271.0    0.07       0  3451.0    0.05       0
  3922.9    0.05       0  3927.6    0.05       0  3934.3    0.07       0
  3955.8    0.05       0  4342.3   0.035       0  4436.1    0.05       0
Bank Sta=3922.9,3927.6
Exp/Cntr=0.3,0.1

Chan Stop Cuts=-1