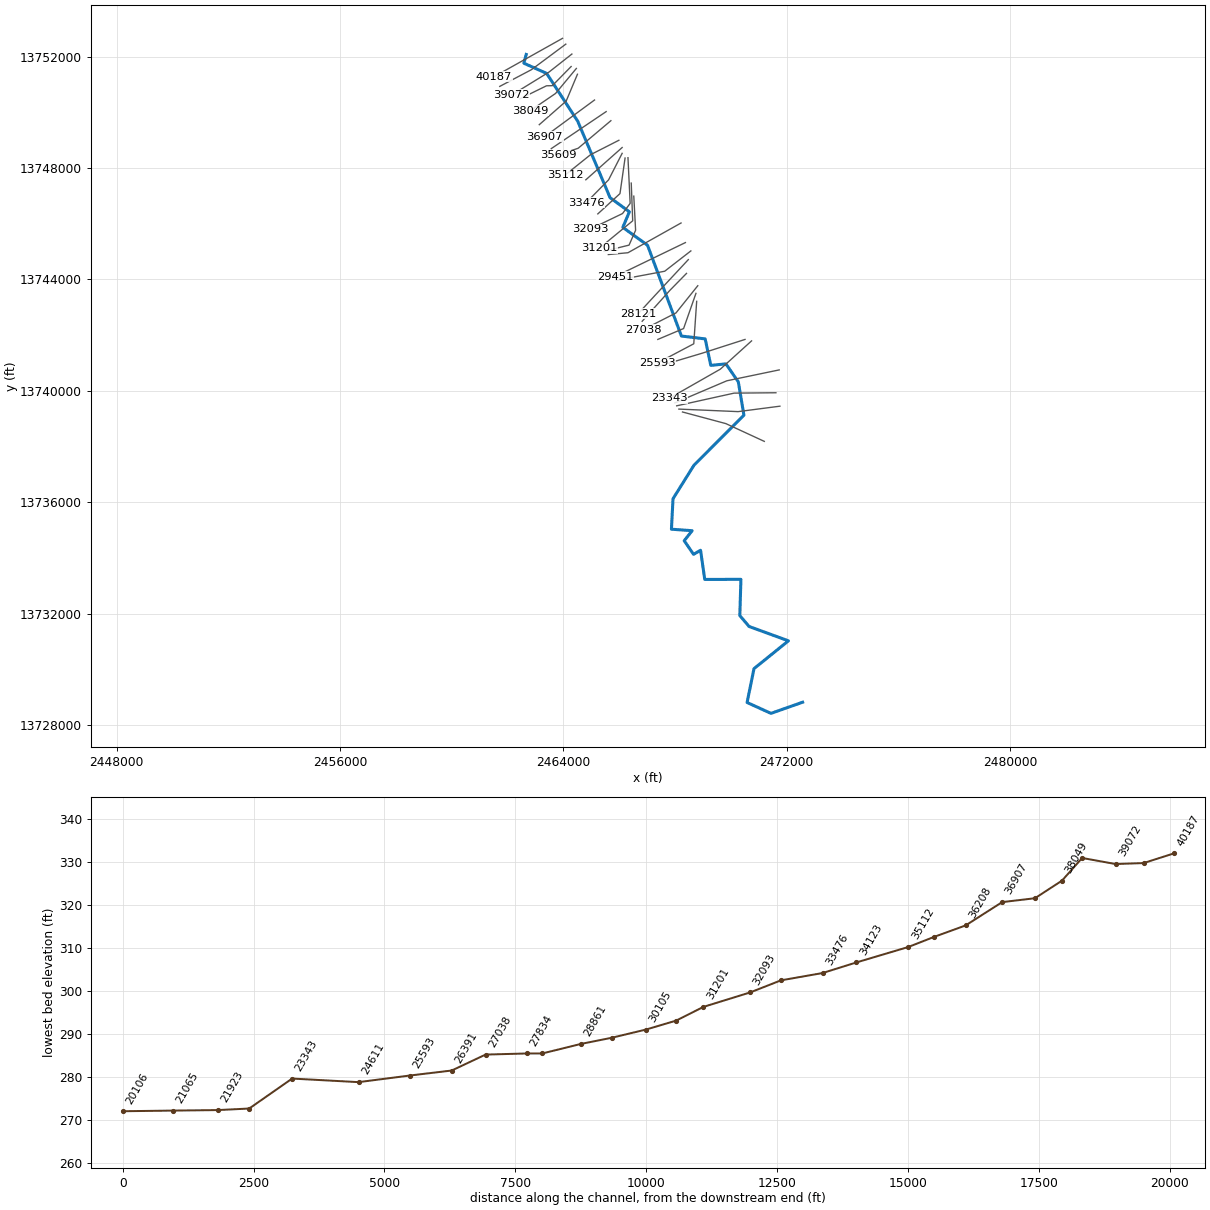
--- KERR CREEK.prj (project) ---

Proj Title=KERR CREEK Base Level Engineering
Current Plan=p01
Default Exp/Contr=0.3,0.1
English Units
Geom File=g01
Flow File=f01
Plan File=p01
Y Axis Title=Elevation
X Axis Title(PF)=Main Channel Distance
X Axis Title(XS)=Station
BEGIN DESCRIPTION:
KERR CREEK
END DESCRIPTION:
DSS Export Rating Curves= 0
DSS Export Rating Curve Sorted= 0
DSS Export Volume Flow Curves= 0
DXF OffsetX= 0
DXF OffsetY= 0
DXF ScaleX= 1
DXF ScaleY= 10

--- KERR CREEK.p01 (plan) ---

Plan Title=Multiple Run
Short Identifier=Multiple
Geom File=g01
Flow File=f01
Subcritical Flow
K Sum by GR= 0
Std Step Tol= 0.01
Critical Tol= 0.01
Num of Std Step Trials= 20
Max Error Tol= 0.3
Flow Tol Ratio= 0.001
Split Flow NTrial= 30
Split Flow Tol= 0.02
Split Flow Ratio= 0.02
Log Output Level= 0
Friction Slope Method= 1
Unsteady Friction Slope Method= 2
Unsteady Bridges Friction Slope Method= 1
Parabolic Critical Depth
Global Vel Dist=  1 , 1 , 1
Global Log Level= 0
CheckData=True
Encroach Param= -1, 0, 0, 0
BEGIN DESCRIPTION:
Multiple Run
END DESCRIPTION:

--- KERR CREEK.f01 (steady flow) ---

Flow Title=Multiple
Number of Profiles=7
Profile Names=10-year,25-year,50-year,1pct_min,100-year,1pct_plu,500-year
River Rch & RM= KERR CREEK,Reach-1,40187
     832    1351    1823    1190    2374    4737    3987
River Rch & RM= KERR CREEK,Reach-1,36208
    1008    1651    2240    1469    2932    5850    4974
River Rch & RM= KERR CREEK,Reach-1,30105
    1790    3005    4144    2757    5501   10976    9607
River Rch & RM= KERR CREEK,Reach-1,24611
    2339    3964    5502    3680    7343   14652   12966
River Rch & RM= KERR CREEK,Reach-1,20106
    2372    4010    5555    3708    7399   14762   13009
River Rch & RM= KERR CREEK,Reach-1,14242
    2375    4009    5547    3698    7378   14721   12938
River Rch & RM= KERR CREEK,Reach-1,12891
    2468    4161    5752    3829    7641   15245   13364
Boundary for River Rch & Prof#=KERR CREEK,Reach-1,1
Up Type=0
Dn Type=3
Dn Slope=0.005
Boundary for River Rch & Prof#=KERR CREEK,Reach-1,2
Up Type=0
Dn Type=3
Dn Slope=0.005
Boundary for River Rch & Prof#=KERR CREEK,Reach-1,3
Up Type=0
Dn Type=3
Dn Slope=0.005
Boundary for River Rch & Prof#=KERR CREEK,Reach-1,4
Up Type=0
Dn Type=3
Dn Slope=0.005
Boundary for River Rch & Prof#=KERR CREEK,Reach-1,5
Up Type=0
Dn Type=3
Dn Slope=0.005
Boundary for River Rch & Prof#=KERR CREEK,Reach-1,6
Up Type=0
Dn Type=3
Dn Slope=0.005
Boundary for River Rch & Prof#=KERR CREEK,Reach-1,7
Up Type=0
Dn Type=3
Dn Slope=0.005

--- KERR CREEK.g01 (geometry) ---

Geom Title=Existing Conditions
Program Version=4.10

River Reach=KERR CREEK      ,Reach-1
Reach XY= 30
        2462675.       13752075.      2462588.52     13751761.59
      2463405.91     13751395.53       2464519.6     13749677.43
      2465678.51     13746933.48      2466369.94     13746427.29
      2466133.97     13745868.34      2467019.53     13745227.45
      2468233.13     13741968.93      2469084.85     13741864.58
      2469285.65     13740914.89      2469827.58     13740969.31
      2470271.45     13740323.53      2470471.64     13739126.25
      2468682.81     13737331.23       2467932.8     13736128.42
      2467875.74      13735035.1      2468616.86     13734981.06
      2468332.79     13734621.97      2468668.05     13734133.84
      2468919.48       13734278.      2469068.79     13733232.76
      2470364.52      13733234.8      2470325.49     13731935.49
      2470654.83      13731544.6      2472067.76     13731028.35
      2470833.14     13730031.06      2470585.47     13728815.18
      2471440.26     13728424.49        2472575.       13728825.

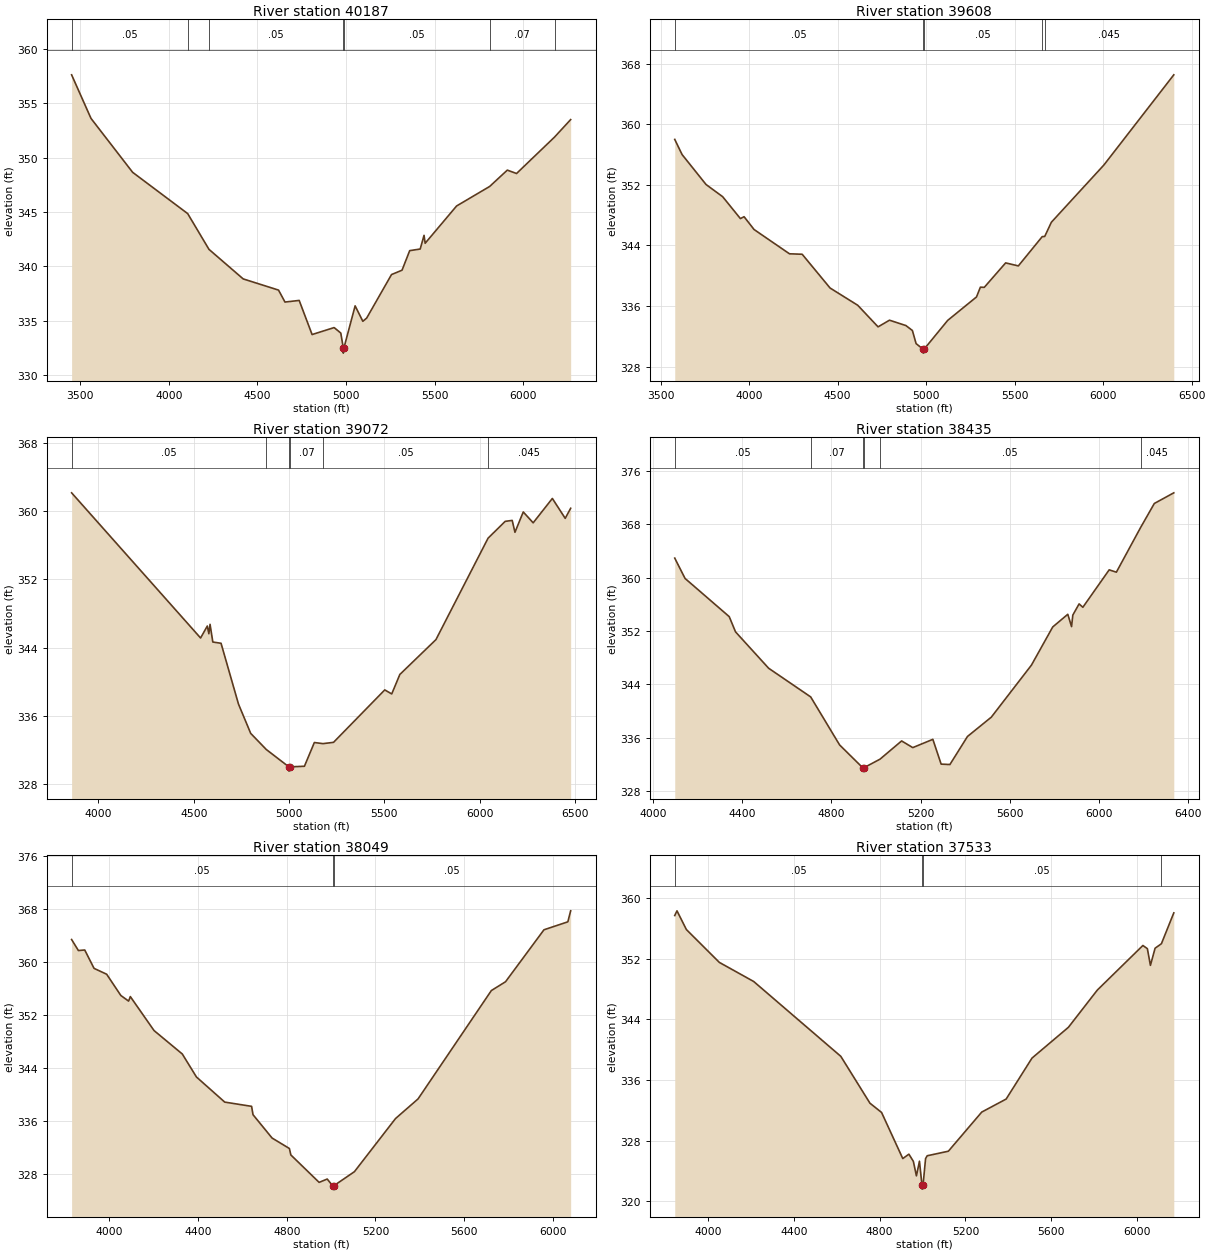
Type RM Length L Ch R = 1 ,40187   ,579,579,579
BEGIN DESCRIPTION:
KERR CREEK 9049
END DESCRIPTION:
XS GIS Cut Line= 2
      2463975.29     13752653.66      2461518.71     13751274.59
#Sta/Elev= 30
  3451.4  357.63  3560.8  353.62  3795.8  348.66  4106.6  344.86  4226.8  341.57
  4419.9  338.85  4619.5  337.82  4655.9  336.72  4736.1  336.87  4808.9  333.73
  4933.3  334.37  4970.9  333.87  4984.8  332.52  4985.1  332.02    4989  332.52
  5051.9  336.37  5095.3  334.95  5116.9  335.24  5257.3  339.25  5316.6  339.65
  5359.9  341.45  5419.2   341.6  5440.9  342.86  5447.2  342.13  5624.6  345.56
  5811.6  347.36  5910.9  348.86  5963.2  348.55  6177.5   351.9  6268.6  353.51
#Mann= 7 ,-1 , 0
  3451.4     .05       0  4106.6     .07       0  4226.8     .05       0
  4984.8     .05       0    4989     .05       0  5811.6     .07       0
  6177.5     .05       0
Bank Sta=4984.8,4989
XS Rating Curve= 0 ,0
Exp/Cntr=0.3,0.1

Type RM Length L Ch R = 1 ,39608   ,536,536,536
BEGIN DESCRIPTION:
KERR CREEK 9048
END DESCRIPTION:
XS GIS Cut Line= 3
      2464092.43      13752445.3      2462865.02     13751530.97
      2461725.74     13750928.08
#Sta/Elev= 30
  3579.6     358    3621     356  3756.5  352.04  3850.4  350.43  3950.5  347.54
  3971.3  347.79  4027.6   346.1  4227.8  342.89  4299.6  342.83  4457.2  338.37
  4613.6  336.09  4728.3  333.24  4792.9  334.12  4885.7  333.41  4922.2  332.76
  4943.1  331.03  4983.4  330.27  4983.6  329.77  4987.6  330.27  5121.5  334.09
  5284.4  337.19  5306.4  338.48  5328.4  338.46  5449.1  341.69  5520.8  341.29
  5655.9  345.16  5669.8  345.18  5707.5  347.06  6003.9  354.61  6399.1  366.53
#Mann= 5 ,-1 , 0
  3579.6     .05       0  4983.4     .05       0  4987.6     .05       0
  5655.9     .07       0  5669.8    .045       0
Bank Sta=4983.4,4987.6
XS Rating Curve= 0 ,0
Exp/Cntr=0.3,0.1

Type RM Length L Ch R = 1 ,39072   ,637,637,637
BEGIN DESCRIPTION:
KERR CREEK 9047
END DESCRIPTION:
XS GIS Cut Line= 3
       2464310.2     13752089.55      2463490.07     13751442.31
      2462151.28     13750617.76
#Sta/Elev= 30
  3859.8  362.14  4536.1  345.14  4571.4  346.54  4579.5  345.64  4585.8  346.74
  4600.3  344.67  4643.5  344.52  4734.9   337.4    4799  333.97  4880.8  332.08
  4999.2  330.05  4999.5  329.55  5003.7  330.05  5080.7  330.12  5132.8   332.9
  5177.7  332.77  5233.3  332.92  5501.9  339.06  5538.6  338.59  5581.1  340.87
  5770.4  344.95  6043.8  356.83  6133.6   358.8  6170.3  358.91  6184.8  357.52
  6228.3   359.9  6280.3  358.63  6380.9  361.48  6448.4  359.15  6476.9  360.33
#Mann= 6 ,-1 , 0
  3859.8     .05       0  4880.8     .07       0  4999.2     .05       0
  5003.7     .07       0  5177.7     .05       0  6043.8    .045       0
Bank Sta=4999.2,5003.7
XS Rating Curve= 0 ,0
Exp/Cntr=0.3,0.1

Type RM Length L Ch R = 1 ,38435   ,386,386,386
BEGIN DESCRIPTION:
A19524
END DESCRIPTION:
XS GIS Cut Line= 4
      2464283.55     13751641.78      2463609.76     13750954.69
      2463401.41     13750950.25      2462443.93     13750480.38
#Sta/Elev= 30
  4098.2  362.93  4144.4  359.88  4342.4  354.15  4370.7  351.86  4519.2   346.4
  4707.6   342.1  4837.3  334.89  4941.2  331.46  4941.5  330.96  4945.7  331.46
  5018.2  332.75  5115.3  335.49  5165.3  334.49  5255.3  335.73  5292.5  332.01
  5331.8  331.95  5410.5  336.16  5517.4  339.06  5697.3  346.87  5792.8   352.6
  5860.3   354.5  5877.2  352.65  5882.8  354.38    5911  356.06  5927.8  355.55
  6045.8  361.17  6078.1  360.82  6186.3   367.5  6248.2  371.13  6335.5  372.73
#Mann= 6 ,-1 , 0
  4098.2     .05       0  4707.6     .07       0  4941.2     .05       0
  4945.7     .07       0  5018.2     .05       0  6186.3    .045       0
Bank Sta=4941.2,4945.7
XS Rating Curve= 0 ,0
Exp/Cntr=0.3,0.1

Type RM Length L Ch R = 1 ,38049   ,516,516,516
BEGIN DESCRIPTION:
KERR CREEK 9046
END DESCRIPTION:
XS GIS Cut Line= 3
      2464470.02     13751572.88        2463725.       13750675.
      2462829.69     13750062.68
#Sta/Elev= 30
  3829.2  363.34  3859.7  361.68  3888.4  361.76  3930.4  358.99  3987.4   358.1
  4051.2   354.9  4086.3  354.05  4094.1  354.73  4200.9  349.61  4328.5  346.07
  4392.4   342.6    4520  338.81  4641.1  338.17  4647.6  336.91  4733.5  333.39
  4811.7  331.81  4818.2  330.84  4945.8   326.7  4982.3   327.2  5007.1  326.18
  5007.5  325.68  5011.7  326.18    5105  328.31  5290.5  336.33  5392.1  339.29
  5722.8  355.64  5786.8  356.97  5960.2  364.81  6067.9  366.01  6080.6  367.67
#Mann= 3 ,-1 , 0
  3829.2     .05       0  5007.1     .05       0  5011.7     .05       0
Bank Sta=5007.1,5011.7
XS Rating Curve= 0 ,0
Exp/Cntr=0.3,0.1

Type RM Length L Ch R = 1 ,37533   ,626,626,626
BEGIN DESCRIPTION:
KERR CREEK 9045
END DESCRIPTION:
XS GIS Cut Line= 3
      2464509.11     13751364.58      2464105.47     13750401.04
      2463141.96     13749554.71
#Sta/Elev= 30
  3844.4  357.67  3854.8  358.29  3898.7  355.82  4052.3  351.49  4212.6  348.97
  4618.8   339.1  4754.7  332.92  4808.9   331.7  4907.7  325.62  4936.2   326.2
  4957.1  325.25  4971.3  323.34  4985.5  325.27  4997.4  322.09  4997.7  321.59
  5002.1  322.09    5014  325.61  5021.6  325.99  5120.3  326.59  5275.9  331.75
  5389.8  333.47  5510.3  338.87  5680.1  342.93  5814.9  347.84  6027.4  353.72
  6048.3   353.3  6062.5   351.1  6084.3  353.36  6113.7  353.95  6171.5  358.02
#Mann= 4 ,-1 , 0
  3844.4     .05       0  4997.4     .05       0  5002.1     .05       0
  6113.7    .045       0
Bank Sta=4997.4,5002.1
XS Rating Curve= 0 ,0
Exp/Cntr=0.3,0.1

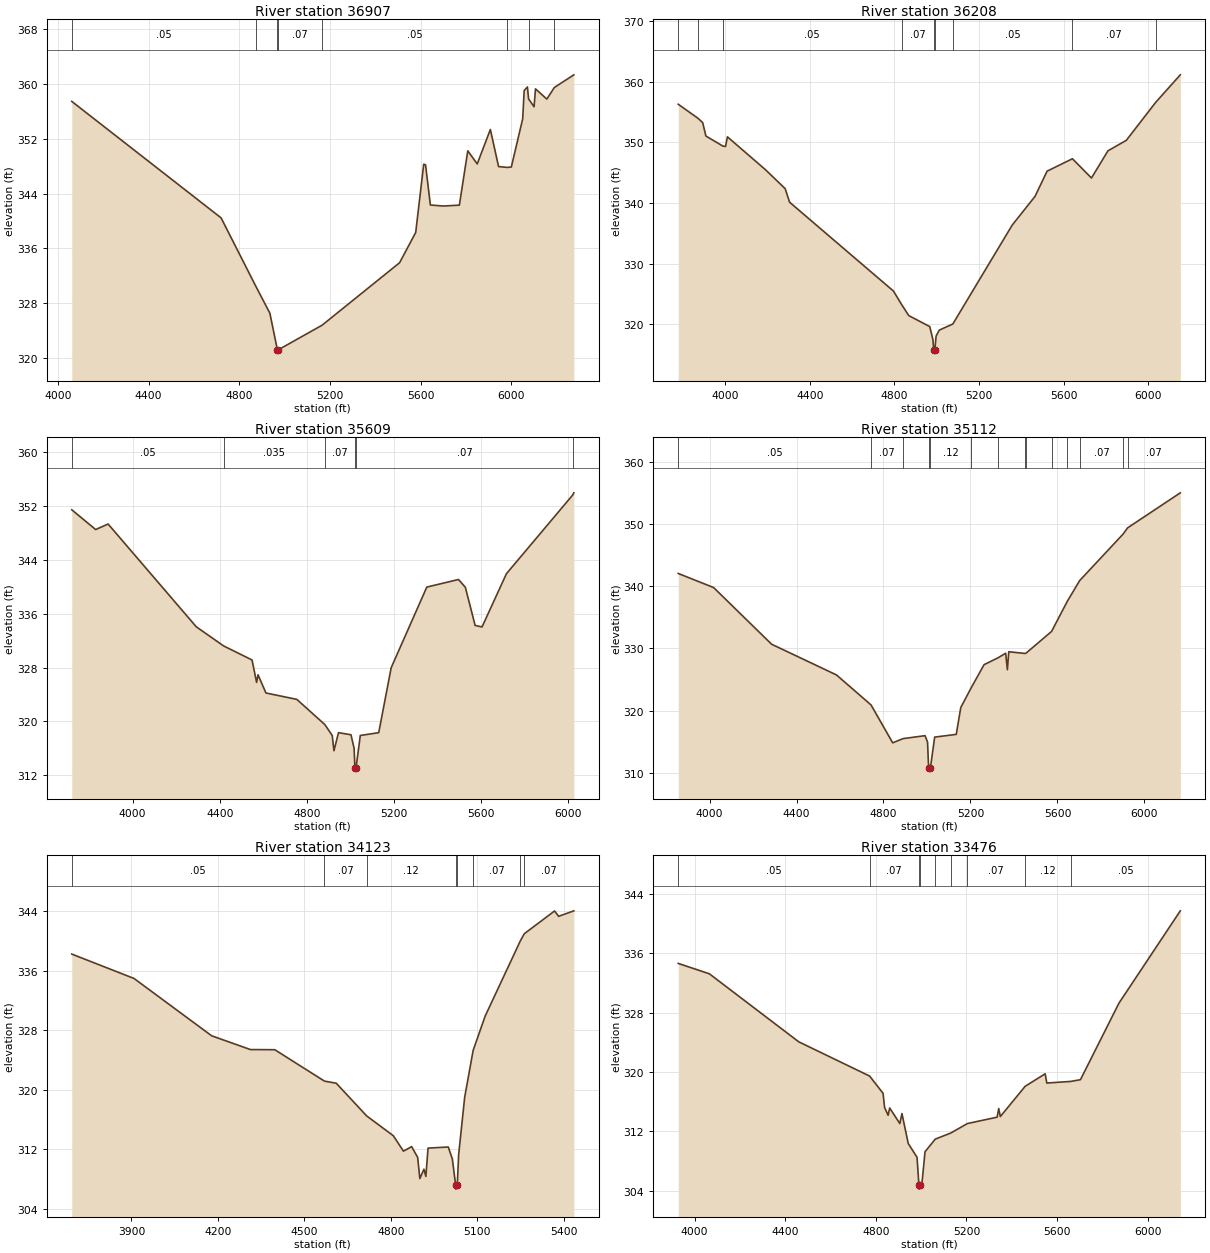
Type RM Length L Ch R = 1 ,36907   ,699,699,699
BEGIN DESCRIPTION:
KERR CREEK 9044
END DESCRIPTION:
XS GIS Cut Line= 2
      2465121.09      13750440.1      2463338.62     13749126.02
#Sta/Elev= 30
  4061.5  357.45  4720.1  340.44    4872  330.54  4935.3  326.52  4968.3  321.19
  4968.6  320.69  4973.2  321.19  5165.7  324.77  5507.5  333.89  5578.5  338.31
  5613.9  348.28    5622  348.18  5643.2  342.32  5699.6  342.17  5771.1   342.3
  5808.2  350.23  5849.9  348.32  5907.8  353.35    5944  347.93  5982.7  347.81
  6000.3  347.87  6050.4  354.91  6056.9  359.03  6071.3  359.56  6076.4  357.81
  6100.6  356.66  6106.8  359.28  6156.9  357.79    6190  359.48    6276  361.33
#Mann= 8 ,-1 , 0
  4061.5     .05       0    4872     .07       0  4968.3     .05       0
  4973.2     .07       0  5165.7     .05       0  5982.7     .07       0
  6076.4     .05       0    6190    .045       0
Bank Sta=4968.3,4973.2
XS Rating Curve= 0 ,0
Exp/Cntr=0.3,0.1

Type RM Length L Ch R = 1 ,36208   ,599,599,599
BEGIN DESCRIPTION:
KERR CREEK 9043
END DESCRIPTION:
XS GIS Cut Line= 2
      2465537.77     13750023.45      2463571.62     13748695.31
#Sta/Elev= 30
  3778.2  356.31  3872.4  353.97  3893.9  353.27  3908.8  351.07    3989  349.41
  4001.8  349.35  4010.7  350.93  4190.5  345.51  4283.5  342.39  4304.5  340.15
  4795.2   325.5  4833.6  323.29  4867.6  321.45  4966.8  319.64  4981.8  317.49
  4985.8  315.76  4986.2  315.26  4990.8  315.76  4996.8  318.07  5011.7  319.05
  5075.8  320.06  5356.4  336.37  5464.3  341.11  5521.3  345.27  5641.1  347.32
  5731.1  344.14    5809  348.63  5895.9  350.36  6034.8  356.63  6150.9  361.16
#Mann= 9 ,-1 , 0
  3778.2     .05       0  3872.4    .035       0    3989     .05       0
  4833.6     .07       0  4985.8     .05       0  4990.8     .07       0
  5075.8     .05       0  5641.1     .07       0  6034.8     .05       0
Bank Sta=4985.8,4990.8
XS Rating Curve= 0 ,0
Exp/Cntr=0.3,0.1

Type RM Length L Ch R = 1 ,35609   ,497,497,497
BEGIN DESCRIPTION:
KERR CREEK 9042
END DESCRIPTION:
XS GIS Cut Line= 3
      2465707.07     13749697.95      2464535.16     13748708.33
      2463806.03     13748460.95
#Sta/Elev= 30
  3721.2  351.48  3830.8  348.54    3888  349.36  4292.4  334.08  4417.9  331.23
  4548.5  329.14  4569.3   325.8  4575.8  326.94  4612.2  324.23  4753.9  323.28
    4882  319.55  4916.5   317.9  4924.2  315.64  4945.1  318.33  5002.3  318.02
  5016.6  316.02  5020.5  313.11  5020.9  312.61  5025.6  313.11  5045.1  317.91
  5129.7  318.33  5186.9  327.99  5350.3  339.98  5495.8  341.11  5527.2  339.95
    5572  334.28  5603.7  334.05  5715.7  341.97  6020.6  353.71    6025     354
#Mann= 6 ,-1 , 0
  3721.2     .05       0  4417.9    .035       0    4882     .07       0
  5020.5     .05       0  5025.6     .07       0  6020.6     .05       0
Bank Sta=5020.5,5025.6
XS Rating Curve= 0 ,0
Exp/Cntr=0.3,0.1

Type RM Length L Ch R = 1 ,35112   ,989,989,989
BEGIN DESCRIPTION:
KERR CREEK 9041
END DESCRIPTION:
XS GIS Cut Line= 3
      2465993.48     13748994.79        2464975.       13748475.
      2464066.41     13747744.79
#Sta/Elev= 30
    3856  342.08  4018.8  339.81  4285.5  330.68    4584  325.73  4742.8   320.9
  4842.3   314.8  4890.6  315.48  4991.1  315.95  5002.7  314.91  5006.6   311.5
  5010.5  310.74  5010.9  310.24  5015.7  310.74  5035.4  315.72  5134.6  316.16
  5155.5  320.49  5202.5  323.61  5262.6  327.39    5326  328.48  5361.9  329.23
  5369.8  326.58  5376.2  329.47  5449.5   329.2  5455.5  329.24    5573  332.74
  5645.2  337.58  5702.2  340.93  5901.8  348.42  5922.5  349.42  6165.1  355.07
#Mann= 14 ,-1 , 0
    3856     .05       0  4742.8     .07       0  4890.6     .12       0
  5010.5     .05       0  5015.7     .12       0  5202.5     .07       0
    5326    .035       0  5449.5     .07       0  5455.5    .035       0
    5573     .07       0  5645.2    .035       0  5702.2     .07       0
  5901.8    .035       0  5922.5     .07       0
Bank Sta=5010.5,5015.7
XS Rating Curve= 0 ,0
Exp/Cntr=0.3,0.1

Type RM Length L Ch R = 1 ,34123   ,647,647,647
BEGIN DESCRIPTION:
KERR CREEK 9040
END DESCRIPTION:
XS GIS Cut Line= 2
       2466110.7     13748734.39      2464809.28     13747576.13
#Sta/Elev= 30
  3692.9  338.24  3909.1  334.96  4178.3  327.26  4312.9  325.41  4397.4  325.39
  4569.8  321.17  4610.6  320.89  4716.1   316.5  4808.8  313.83  4843.9  311.76
  4872.3  312.37  4893.2  310.92  4900.7  308.08    4915  309.34  4921.6  308.37
  4929.2  312.17  4999.4  312.32  5013.6   310.7  5025.1  307.16  5025.5  306.66
  5030.5  307.16  5035.4  311.29  5056.3  319.01  5085.7   325.3  5127.3   329.9
  5249.8  340.04  5263.1  340.97  5368.2  344.03  5382.4  343.31  5435.1  344.05
#Mann= 8 ,-1 , 0
  3692.9     .05       0  4569.8     .07       0  4716.1     .12       0
  5025.1     .05       0  5030.5     .12       0  5085.7     .07       0
  5249.8     .12       0  5263.1     .07       0
Bank Sta=5025.1,5030.5
XS Rating Curve= 0 ,0
Exp/Cntr=0.3,0.1

Type RM Length L Ch R = 1 ,33476   ,795,795,795
BEGIN DESCRIPTION:
KERR CREEK 9039
END DESCRIPTION:
XS GIS Cut Line= 3
      2466110.66     13748526.01        2465625.       13747575.
      2464821.59     13746755.18
#Sta/Elev= 30
    3928  334.62  4065.4  333.22  4459.8  324.05  4772.8  319.43    4832   317.1
  4838.6   315.2  4854.2  314.15  4861.1  315.13    4906  313.03  4915.3  314.38
  4943.1  310.34  4981.9  308.48  4990.3  304.69  4990.7  304.19  4995.8  304.69
  5002.9  304.78  5017.1  309.23  5062.3  310.93  5130.5  311.75  5204.1  313.03
  5335.2  313.89  5342.4  315.06  5349.4  313.97  5458.9  318.05  5547.4  319.74
  5554.5  318.49  5659.8  318.71    5703  318.94  5872.7  329.25  6143.7  341.71
#Mann= 9 ,-1 , 0
    3928     .05       0  4772.8     .07       0  4990.3     .05       0
  4995.8     .07       0  5062.3     .07       0  5130.5     .12       0
  5204.1     .07       0  5458.9     .12       0  5659.8     .05       0
Bank Sta=4990.3,4995.8
XS Rating Curve= 0 ,0
Exp/Cntr=0.3,0.1

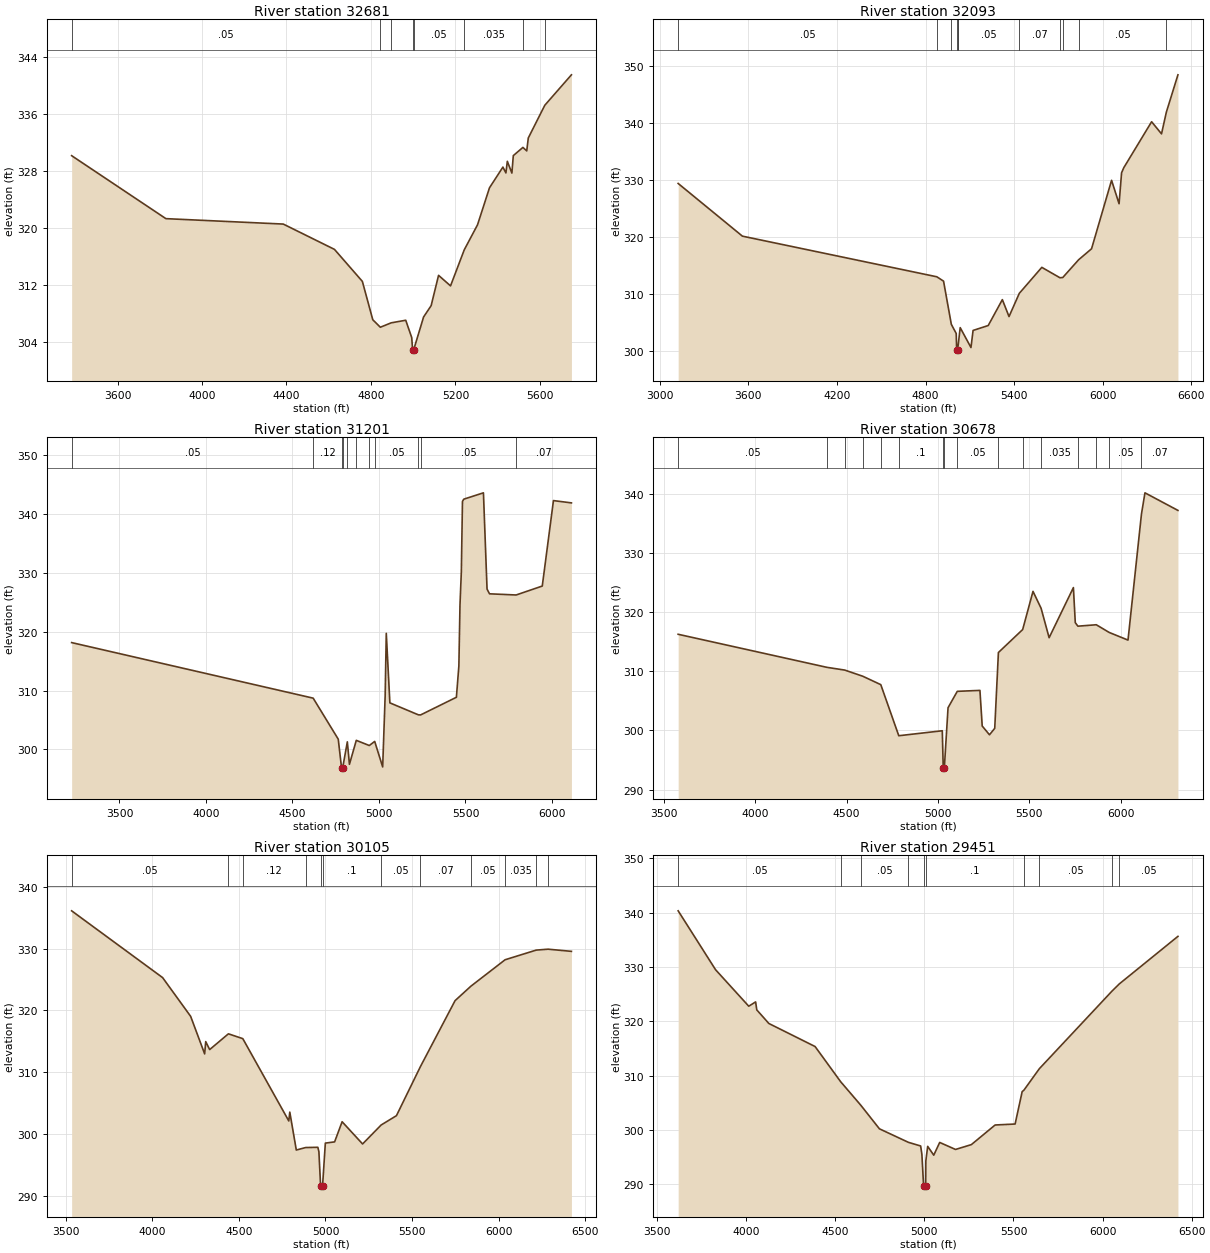
Type RM Length L Ch R = 1 ,32681   ,588,588,588
BEGIN DESCRIPTION:
KERR CREEK 9038
END DESCRIPTION:
XS GIS Cut Line= 3
      2466214.84     13748356.73      2466032.55     13747080.73
      2465239.14     13746352.35
#Sta/Elev= 30
  3382.9  330.18  3829.1  321.35  4384.7  320.59  4627.1  317.04  4759.2  312.55
  4808.5  307.17  4844.3  306.12  4895.8  306.74  4964.5   307.1  4992.9  304.67
  4996.9  302.99  4997.3  302.49  5002.5  302.99    5049  307.56  5084.8  309.15
  5119.9   313.4  5176.6  311.92  5241.6  316.98  5304.3  320.48  5360.9  325.67
  5424.5  328.58  5438.7  327.76  5445.5  329.39    5467  327.74  5473.8  330.19
  5519.2  331.34  5537.3  330.85  5544.7  332.66  5622.8  337.25  5748.9  341.52
#Mann= 8 ,-1 , 0
  3382.9     .05       0  4844.3     .07       0  4895.8     .05       0
  4996.9     .05       0  5002.5     .05       0  5241.6    .035       0
  5519.2     .05       0  5622.8    .035       0
Bank Sta=4996.9,5002.5
XS Rating Curve= 0 ,0
Exp/Cntr=0.3,0.1

Type RM Length L Ch R = 1 ,32093   ,892,892,892
BEGIN DESCRIPTION:
KERR CREEK 9037
END DESCRIPTION:
XS GIS Cut Line= 4
      2466319.01     13748369.75      2466397.14     13746729.17
       2466123.7     13746364.58      2464964.84     13745804.68
#Sta/Elev= 30
  3124.5  329.37  3559.7  320.15  4876.3  313.04  4922.1  312.28  4974.8  304.72
  5007.8  303.12  5011.2  300.18  5011.6  299.68  5016.9  300.18  5017.1  300.19
  5034.9  304.14  5107.8  300.66  5122.1  303.65  5224.7  304.51  5320.4  309.04
  5365.6  306.08  5435.2  310.14  5587.7  314.69  5710.5  312.87  5729.6  312.91
  5837.5  316.03  5924.6  317.94  6060.2  329.92    6111  325.82    6128  331.24
    6143  332.13  6331.4  340.17  6398.5  338.05  6431.3  341.85  6509.7  348.38
#Mann= 11 ,-1 , 0
  3124.5     .05       0  4876.3     .07       0  4974.8     .12       0
  5011.2     .05       0  5016.9     .12       0  5017.1     .05       0
  5435.2     .07       0  5710.5    .035       0  5729.6     .07       0
  5837.5     .05       0  6431.3     .07       0
Bank Sta=5011.2,5016.9
XS Rating Curve= 0 ,0
Exp/Cntr=0.3,0.1

Type RM Length L Ch R = 1 ,31201   ,523,523,523
BEGIN DESCRIPTION:
KERR CREEK 9036
END DESCRIPTION:
XS GIS Cut Line= 3
       2466436.2     13747458.37      2466488.28     13746104.17
      2465304.83     13745128.79
#Sta/Elev= 30
  3223.5  318.16  4619.5  308.72  4764.5  301.75  4783.8  296.82  4784.3  296.32
  4789.7  296.82    4817   301.3  4829.2  297.48  4868.8  301.55  4943.9  300.67
  4975.2  301.37  5021.3  297.03  5035.6  309.09  5042.1  319.74  5062.9  307.92
  5227.3  305.89  5240.6  305.87  5447.4  308.87  5461.7  314.19  5468.2   324.6
    5476   330.2  5482.5  342.15  5490.1  342.53  5603.7  343.61  5624.6  327.25
  5638.9  326.45  5792.7  326.25  5943.8  327.77  6008.4  342.29  6112.3   341.9
#Mann= 11 ,-1 , 0
  3223.5     .05       0  4619.5     .12       0  4783.8     .05       0
  4789.7     .12       0    4817      .1       0  4868.8     .12       0
  4943.9      .1       0  4975.2     .05       0  5227.3    .035       0
  5240.6     .05       0  5792.7     .07       0
Bank Sta=4783.8,4789.7
XS Rating Curve= 0 ,0
Exp/Cntr=0.3,0.1

Type RM Length L Ch R = 1 ,30678   ,573,573,573
BEGIN DESCRIPTION:
KERR CREEK 9035
END DESCRIPTION:
XS GIS Cut Line= 4
      2466527.35     13746989.54      2466592.45     13745765.63
      2466358.07     13745231.77      2465459.82     13745010.46
#Sta/Elev= 30
  3578.7  316.24  4391.8  310.66  4490.2  310.19  4588.7  309.15  4687.1  307.73
  4785.5   299.1  5023.5  299.94  5028.7  293.62  5029.2  293.12  5034.6  293.62
    5055  303.83  5105.5   306.6  5229.4  306.76  5241.9  300.74  5281.6  299.26
  5310.4  300.35  5330.5  313.16  5463.2  317.04  5519.7  323.49  5563.9  320.64
  5607.9  315.66  5740.7  324.13    5751   318.2  5765.3  317.61  5865.9  317.85
  5936.5  316.55  6039.4  315.26  6112.9  336.53  6132.1  340.14  6312.5  337.17
#Mann= 16 ,-1 , 0
  3578.7     .05       0  4391.8     .07       0  4490.2     .12       0
  4588.7     .07       0  4687.1     .12       0  4785.5      .1       0
  5028.7     .05       0  5034.6      .1       0  5105.5     .05       0
  5330.5    .035       0  5463.2     .05       0  5563.9    .035       0
  5765.3     .05       0  5865.9    .035       0  5936.5     .05       0
  6112.9     .07       0
Bank Sta=5028.7,5034.6
XS Rating Curve= 0 ,0
Exp/Cntr=0.3,0.1

Type RM Length L Ch R = 1 ,30105   ,654,654,654
BEGIN DESCRIPTION:
KERR CREEK 9034
END DESCRIPTION:
XS GIS Cut Line= 3
      2468220.08     13746026.06      2466319.01     13744958.33
      2465615.91     13744893.23
#Sta/Elev= 30
    3534   336.1  4059.3  325.29  4221.3  319.02  4302.2  312.94  4308.3  314.93
  4331.2  313.64  4439.4  316.19  4522.5  315.41  4788.1  302.09  4793.9  303.52
  4831.5  297.38  4885.2  297.78  4955.9  297.82    4962  297.11  4971.9  291.55
  4972.4  291.05  4983.1  291.55  4999.2   298.5  5052.8   298.7  5096.1  301.96
  5214.3  298.36  5321.5  301.43  5409.9  302.94  5548.1  310.87  5748.5  321.56
  5840.3  323.91  6037.5  328.18  6216.9  329.74  6285.5  329.89  6420.5  329.54
#Mann= 12 ,-1 , 0
    3534     .05       0  4439.4     .07       0  4522.5     .12       0
  4885.2      .1       0  4971.9     .05       0  4983.1      .1       0
  5321.5     .05       0  5548.1     .07       0  5840.3     .05       0
  6037.5    .035       0  6216.9     .05       0  6285.5     .07       0
Bank Sta=4971.9,4983.1
XS Rating Curve= 0 ,0
Exp/Cntr=0.3,0.1

Type RM Length L Ch R = 1 ,29451   ,590,590,590
BEGIN DESCRIPTION:
KERR CREEK 9033
END DESCRIPTION:
XS GIS Cut Line= 2
      2468376.35     13745322.94      2465851.34     13744099.48
#Sta/Elev= 30
  3617.4  340.35  3827.5  329.51  4013.7   322.8  4052.3  323.59  4058.8  322.12
  4126.6  319.62  4386.1  315.38  4529.6  308.91  4642.5  304.59  4747.3  300.24
    4910  297.75  4978.7  297.08  4985.7  295.55  4995.5  289.64    4996  289.14
    5007  289.64  5007.9  294.33  5018.3  297.01  5052.4  295.39  5085.7  297.73
  5174.6  296.44  5263.5  297.33  5396.8  300.94  5509.1  301.12  5548.7  307.08
  5558.3  307.34  5644.9  311.29  6053.1  325.58    6094   326.9  6423.2  335.65
#Mann= 10 ,-1 , 0
  3617.4     .05       0  4529.6    .035       0  4642.5     .05       0
    4910      .1       0  4995.5     .05       0    5007      .1       0
  5558.3     .12       0  5644.9     .05       0  6053.1     .12       0
    6094     .05       0
Bank Sta=4995.5,5007
XS Rating Curve= 0 ,0
Exp/Cntr=0.3,0.1

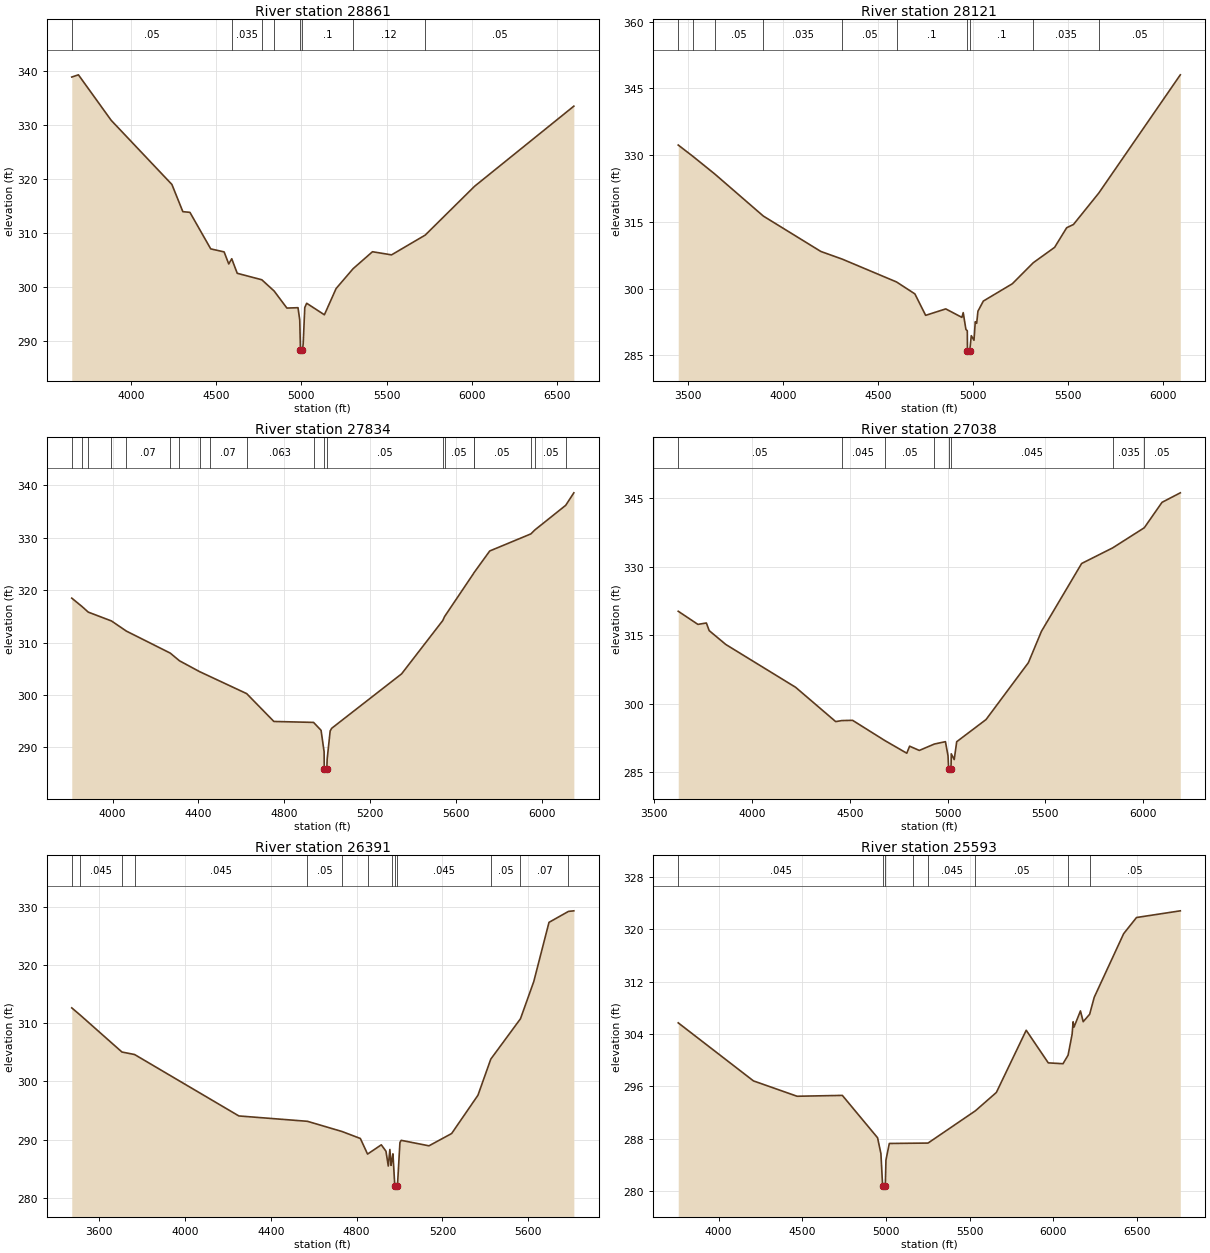
Type RM Length L Ch R = 1 ,28861   ,740,740,740
BEGIN DESCRIPTION:
KERR CREEK 9032
END DESCRIPTION:
XS GIS Cut Line= 3
       2468571.6     13745023.43      2467634.11     13744294.27
      2465902.31     13743968.74
#Sta/Elev= 30
  3650.8  338.81  3689.9  339.22  3882.6  330.79  4239.2  318.92  4303.4  313.89
    4345  313.76  4467.2     307  4545.9  306.44  4573.1  304.21  4590.7  305.17
  4622.9  302.48  4767.4  301.28  4839.7   299.2  4914.8  296.04    4980  296.11
  4990.2  293.84  4994.6   288.2  4995.1   287.7  5006.2   288.2  5010.5  289.47
  5019.8  296.14  5030.9  296.93    5135   294.8  5203.9  299.66    5304  303.34
  5417.5  306.47  5529.5  305.89  5727.3  309.55  6017.9   318.6  6600.6  333.42
#Mann= 8 ,-1 , 0
  3650.8     .05       0  4590.7    .035       0  4767.4     .05       0
  4839.7      .1       0  4994.6     .05       0  5006.2      .1       0
    5304     .12       0  5727.3     .05       0
Bank Sta=4994.6,5006.2
XS Rating Curve= 0 ,0
Exp/Cntr=0.3,0.1

Type RM Length L Ch R = 1 ,28121   ,287,287,287
BEGIN DESCRIPTION:
KERR CREEK 9031
END DESCRIPTION:
XS GIS Cut Line= 3
      2468480.45     13744710.92      2467282.55     13743421.88
      2466683.57     13742770.81
#Sta/Elev= 30
  3448.9  332.24  3524.7  329.75    3642  325.71  3897.1  316.28  4199.9  308.33
    4313   306.6  4598.8  301.47  4695.3  298.79    4752  293.97    4858  295.42
    4943  293.51  4949.9  294.58    4964  290.83  4971.4  290.49  4972.3  285.98
  4972.8  285.48  4984.2  285.98  4992.4   289.4  5006.6  288.37  5013.4  292.54
  5020.7  292.18  5027.5  294.91  5055.9  297.18  5208.6  301.07  5318.7  305.79
  5431.3  309.25  5494.8  313.66  5530.5  314.39  5663.7  321.44  6093.3  348.02
#Mann= 10 ,-1 , 0
  3448.9     .05       0  3524.7    .035       0    3642     .05       0
  3897.1    .035       0    4313     .05       0  4598.8      .1       0
  4972.3     .05       0  4984.2      .1       0  5318.7    .035       0
  5663.7     .05       0
Bank Sta=4972.3,4984.2
XS Rating Curve= 0 ,0
Exp/Cntr=0.3,0.1

Type RM Length L Ch R = 1 ,27834   ,796,796,796
BEGIN DESCRIPTION:
KERR CREEK 9030
END DESCRIPTION:
XS GIS Cut Line= 3
      2468415.35     13744216.13      2467816.41     13743604.17
      2466827.99      13742498.7
#Sta/Elev= 30
    3810   318.5  3858.3  316.88  3886.8  315.83  3995.1  314.14  4064.3  312.21
  4268.7  308.01  4311.9  306.54  4405.5  304.47  4453.6  303.55    4625  300.27
  4751.6  294.96  4936.5  294.78  4971.5  293.27  4985.7  289.16  4986.4  285.98
  4986.9  285.48  4998.3  285.98  4999.9  287.79  5013.9  293.14  5020.8  293.65
  5346.8  304.05  5538.6  314.23  5546.9  314.98  5681.7  323.19  5682.4  323.26
  5757.3   327.5    5949  330.76    5968  331.53  6111.2  336.21  6149.2   338.6
#Mann= 20 ,-1 , 0
    3810     .05       0  3858.3    .063       0  3886.8     .07       0
  3995.1    .063       0  4064.3     .07       0  4268.7    .035       0
  4311.9     .05       0  4405.5    .035       0  4453.6     .07       0
    4625    .063       0  4936.5     .05       0  4986.4     .05       0
  4998.3     .05       0  5538.6    .063       0  5546.9     .05       0
  5681.7    .063       0  5682.4     .05       0    5949    .045       0
    5968     .05       0  6111.2    .063       0
Bank Sta=4986.4,4998.3
XS Rating Curve= 0 ,0
Exp/Cntr=0.3,0.1

Type RM Length L Ch R = 1 ,27038   ,647,647,647
BEGIN DESCRIPTION:
KERR CREEK 9029
END DESCRIPTION:
XS GIS Cut Line= 3
      2468819.01     13743773.43      2468037.76     13742796.88
      2466865.86      13742197.9
#Sta/Elev= 30
  3623.2  320.22  3723.8  317.35  3767.1  317.65  3781.5  315.98  3866.3  312.95
  4223.1  303.58  4428.2  296.06  4459.9  296.29  4514.6  296.34    4680   291.9
  4791.6  289.14    4806  290.68  4855.6  289.75  4932.5  291.15  4989.2  291.67
  5002.4  288.58  5005.7  285.72  5006.2  285.22  5017.7  285.72    5019  289.01
  5034.1  287.75  5046.8  291.66  5196.7  296.51  5413.3  308.97    5480  315.83
  5685.5  330.68  5843.8  334.09  6005.7   338.5  6096.4  344.07  6189.9  346.15
#Mann= 8 ,-1 , 0
  3623.2     .05       0  4459.9    .045       0    4680     .05       0
  4932.5    .045       0  5005.7    .045       0  5017.7    .045       0
  5843.8    .035       0  6005.7     .05       0
Bank Sta=5005.7,5017.7
XS Rating Curve= 0 ,0
Exp/Cntr=0.3,0.1

Type RM Length L Ch R = 1 ,26391   ,798,798,798
BEGIN DESCRIPTION:
KERR CREEK 9028
END DESCRIPTION:
XS GIS Cut Line= 3
      2468753.89     13743499.96       2468311.2     13742236.98
      2467388.32     13741847.03
#Sta/Elev= 30
  3472.5  312.64  3512.1   311.4  3706.3  305.06  3765.3  304.63  4251.3  294.08
  4570.7  293.16  4731.9  291.41  4817.6  290.21  4851.2  287.53  4915.3  289.12
    4937  288.02  4947.8  285.48  4955.2  288.32  4960.7  285.59  4964.3   286.4
  4969.5  287.57  4978.3  282.01  4978.8  281.51  4990.4  282.01  5002.1  289.52
  5008.1  289.89  5137.4  288.95  5243.1  291.06  5365.8  297.64  5425.6  303.84
  5563.9  310.77  5625.8  317.15  5696.9  327.33  5787.6  329.21  5812.7  329.31
#Mann= 13 ,-1 , 0
  3472.5     .05       0  3512.1    .045       0  3706.3     .05       0
  3765.3    .045       0  4570.7     .05       0  4731.9    .045       0
  4851.2     .05       0  4964.3    .045       0  4978.3    .045       0
  4990.4    .045       0  5425.6     .05       0  5563.9     .07       0
  5787.6     .05       0
Bank Sta=4978.3,4990.4
XS Rating Curve= 0 ,0
Exp/Cntr=0.3,0.1

Type RM Length L Ch R = 1 ,25593   ,982,982,982
BEGIN DESCRIPTION:
KERR CREEK 9027
END DESCRIPTION:
XS GIS Cut Line= 3
      2468779.95     13743213.51      2468675.78      13741690.1
      2467373.72     13741000.01
#Sta/Elev= 30
  3759.1   305.7  4208.7  296.85  4469.3  294.51  4739.9  294.64  4950.4  288.18
  4970.4  285.77  4980.5  280.87  4984.4  280.85  4984.9  280.35  4996.6  280.85
  5000.5  284.79  5020.6  287.31  5160.6  287.35  5251.8  287.37    5535  292.29
  5660.4  295.09  5838.7  304.57  5970.6   299.6  6058.6  299.47    6089  300.77
  6113.1  303.97    6119  305.86  6124.6  305.06  6162.9  307.52  6179.3  305.88
  6217.9  307.01  6245.3   309.6  6421.2   319.3  6497.9  321.76  6759.7  322.78
#Mann= 8 ,-1 , 0
  3759.1    .045       0  4984.4    .045       0  4996.6    .045       0
  5160.6     .05       0  5251.8    .045       0    5535     .05       0
    6089     .07       0  6217.9     .05       0
Bank Sta=4984.4,4996.6
XS Rating Curve= 0 ,0
Exp/Cntr=0.3,0.1

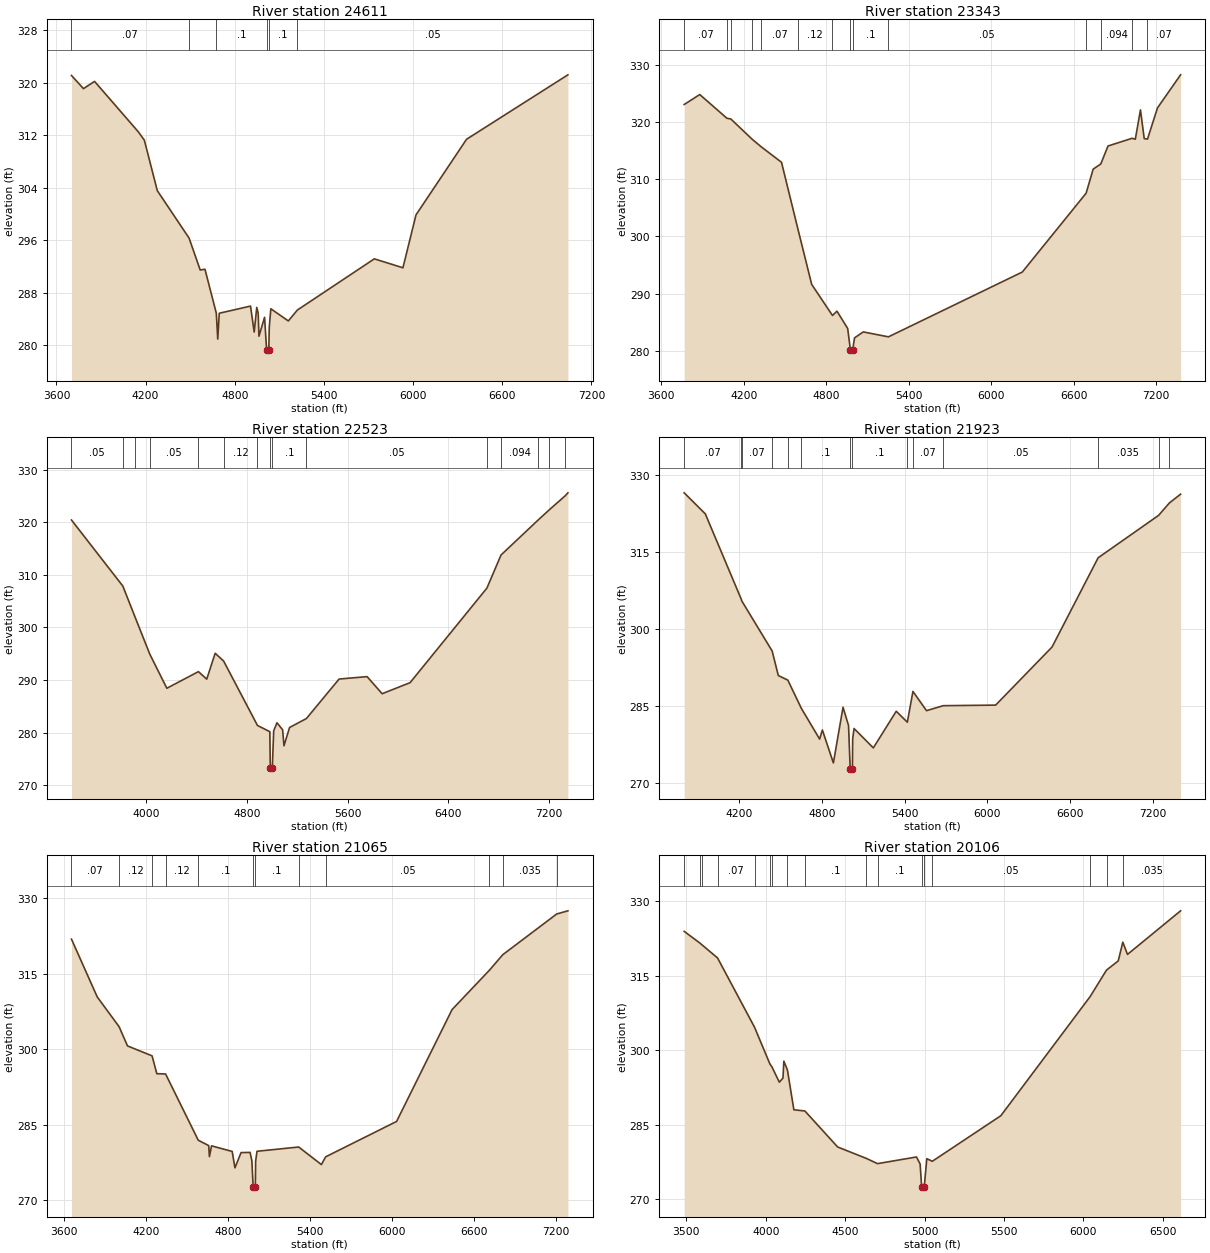
Type RM Length L Ch R = 1 ,24611   ,1268,1268,1268
BEGIN DESCRIPTION:
KERR CREEK 9026
END DESCRIPTION:
XS GIS Cut Line= 3
      2470511.68     13741846.34      2468975.26     13741351.56
      2467321.62     13740856.77
#Sta/Elev= 30
  3701.2  321.07  3781.8  319.07  3856.5  320.17  4150.4  312.51  4191.5  311.22
  4278.6  303.54  4492.5  296.32  4567.3  291.46  4599.3  291.58  4675.7  284.89
  4685.3  280.95  4695.5  284.88  4905.9  285.97  4930.5  282.02  4947.9  285.77
  4957.4  284.89  4962.6  281.39  5000.4  284.27  5014.1  279.31  5014.6  278.81
  5028.8  279.31    5032  282.74  5042.4  285.56  5160.3  283.71  5221.3  285.37
  5738.9  293.16  5931.4   291.8  6019.3  299.85  6359.4  311.36  7041.4  321.17
#Mann= 6 ,-1 , 0
  3701.2     .07       0  4492.5     .12       0  4675.7      .1       0
  5014.1     .05       0  5028.8      .1       0  5221.3     .05       0
Bank Sta=5014.1,5028.8
XS Rating Curve= 0 ,0
Exp/Cntr=0.3,0.1

Type RM Length L Ch R = 1 ,23343   ,820,820,820
BEGIN DESCRIPTION:
KERR CREEK 9025
END DESCRIPTION:
XS GIS Cut Line= 3
      2470746.08     13741794.26       2469626.3     13740778.65
      2467803.38     13739736.97
#Sta/Elev= 30
  3767.1  323.02  3880.5  324.76  4078.1  320.62  4106.3   320.5  4261.3  316.97
  4327.6  315.64  4475.2  312.94  4595.7  301.18  4694.8  291.63  4845.9  286.21
  4878.6  286.96  4956.6  283.94  4976.9  280.14  4977.4  279.64  4992.5  280.14
  5006.4   282.3  5069.9  283.34  5253.1  282.48    6227  293.79  6691.3  307.55
  6742.4  311.74  6797.9  312.65  6850.4  315.78    7026  317.13    7049  316.96
  7086.5  322.08  7113.8  317.08  7137.6  316.98  7210.3  322.43  7378.4   328.2
#Mann= 14 ,-1 , 0
  3767.1     .07       0  4078.1    .035       0  4106.3     .07       0
  4261.3    .035       0  4327.6     .07       0  4595.7     .12       0
  4845.9      .1       0  4976.9     .05       0  4992.5      .1       0
  5253.1     .05       0  6691.3    .063       0  6797.9    .094       0
    7026    .063       0  7137.6     .07       0
Bank Sta=4976.9,4992.5
XS Rating Curve= 0 ,0
Exp/Cntr=0.3,0.1

Type RM Length L Ch R = 1 ,22523   ,600,600,600
BEGIN DESCRIPTION:
KERR CREEK 9024
END DESCRIPTION:
XS GIS Cut Line= 3
      2471735.65      13740752.6      2469860.68     13740361.98
      2467999.38       13739568.
#Sta/Elev= 30
    3409  320.42  3816.4  307.86  3916.4  301.79  4030.9  294.88  4165.6  288.43
  4416.3  291.59  4482.2  290.16    4549  295.08  4616.2   293.6  4884.6  281.36
  4982.7  280.17  4986.5  273.17    4987  272.67  5002.2  273.17  5013.4  280.33
  5039.3  281.86  5084.3  280.53  5095.1   277.5  5139.4  280.97    5273  282.67
  5532.3  290.18  5754.4  290.64    5874  287.39  6095.4  289.49  6704.8  307.46
  6817.3  313.77  7113.5  320.46  7199.2  322.34    7325     325  7347.8  325.59
#Mann= 15 ,-1 , 0
    3409     .05       0  3816.4    .035       0  3916.4     .12       0
  4030.9     .05       0  4416.3    .035       0  4616.2     .12       0
  4884.6      .1       0  4986.5     .05       0  5002.2      .1       0
    5273     .05       0  6704.8    .035       0  6817.3    .094       0
  7113.5    .063       0  7199.2    .094       0    7325    .035       0
Bank Sta=4986.5,5002.2
XS Rating Curve= 0 ,0
Exp/Cntr=0.3,0.1

Type RM Length L Ch R = 1 ,21923   ,858,858,858
BEGIN DESCRIPTION:
KERR CREEK 9023
END DESCRIPTION:
XS GIS Cut Line= 3
       2471618.5     13739932.29      2470121.09     13739919.27
      2468063.82     13739463.55
#Sta/Elev= 30
  3798.9  326.57  3952.4  322.47    4213  305.86  4216.6  305.52  4437.7  295.73
  4482.4  290.95  4551.7  290.05  4650.2  284.53  4782.4  278.56  4802.4  280.33
  4882.4  273.91  4952.4  284.76  4992.4  281.21  5004.4  272.81  5004.9  272.31
  5020.5  272.81  5022.4  278.57  5032.4  280.62  5172.4  276.84  5338.8  283.98
  5419.4  281.85    5460  287.85  5558.7   284.1  5680.3  285.07  6060.5  285.18
  6470.2  296.51  6804.6   313.9    7244  322.18  7322.4   324.6  7403.5  326.31
#Mann= 14 ,-1 , 0
  3798.9     .07       0    4213     .05       0  4216.6     .07       0
  4437.7     .05       0  4551.7    .035       0  4650.2      .1       0
  5004.4     .05       0  5020.5      .1       0  5419.4     .05       0
    5460     .07       0  5680.3     .05       0  6804.6    .035       0
    7244    .094       0  7322.4    .063       0
Bank Sta=5004.4,5020.5
XS Rating Curve= 0 ,0
Exp/Cntr=0.3,0.1

Type RM Length L Ch R = 1 ,21065   ,959,959,959
BEGIN DESCRIPTION:
KERR CREEK 9022
END DESCRIPTION:
XS GIS Cut Line= 3
      2471761.75     13739450.52      2470264.32     13739255.21
      2468141.89     13739346.36
#Sta/Elev= 30
  3656.2  321.87  3844.5   310.4  4004.8  304.47  4066.4  300.65  4246.2  298.68
    4281  295.13  4345.1  295.08  4584.3  281.91  4660.9  280.84  4665.9  278.65
  4681.6  280.79  4832.8  279.68    4853  276.42  4897.8  279.45  4963.9  279.49
  4976.8  277.85  4986.1  272.69  4986.6  272.19  5002.2  272.69  5004.3  277.72
  5014.4  279.71  5319.5  280.56  5485.9  277.07  5517.1  278.61  6036.4  285.64
  6442.6  307.87  6715.2  315.67  6813.9  318.78  7208.6  326.87  7290.7   327.5
#Mann= 12 ,-1 , 0
  3656.2     .07       0  4004.8     .12       0  4246.2    .035       0
  4345.1     .12       0  4584.3      .1       0  4986.1     .05       0
  5002.2      .1       0  5319.5     .12       0  5517.1     .05       0
  6715.2     .12       0  6813.9    .035       0  7208.6    .094       0
Bank Sta=4986.1,5002.2
XS Rating Curve= 0 ,0
Exp/Cntr=0.3,0.1

Type RM Length L Ch R = 1 ,20106   ,764,764,764
BEGIN DESCRIPTION:
KERR CREEK 9021
END DESCRIPTION:
XS GIS Cut Line= 3
      2471201.83      13738187.5        2469825.       13738825.
      2468272.12     13739242.19
#Sta/Elev= 30
  3486.4  323.91  3586.6  321.53  3597.1  321.23  3696.6  318.56  3929.2  304.63
  4026.4  297.21  4038.5  296.67  4085.4  293.56  4108.3  294.37  4113.9  297.79
  4136.4  296.02  4177.1     288  4246.3  287.77  4452.7  280.52  4631.9  278.24
  4703.6  277.17  4949.1  278.51    4972  277.08  4981.2  272.54  4981.7  272.04
  4997.7  272.54    5014  278.17  5048.5  277.64    5480  286.81  6042.5   310.8
  6145.2  316.11    6219  317.96  6247.9  321.73  6277.3  319.27  6611.6  328.04
#Mann= 17 ,-1 , 0
  3486.4    .035       0  3586.6     .07       0  3597.1    .035       0
  3696.6     .07       0  3929.2     .12       0  4026.4     .07       0
  4038.5     .12       0  4136.4     .07       0  4246.3      .1       0
  4631.9     .12       0  4703.6      .1       0  4981.2     .05       0
  4997.7      .1       0  5048.5     .05       0  6042.5     .12       0
  6145.2     .05       0  6247.9    .035       0
Bank Sta=4981.2,4997.7
XS Rating Curve= 0 ,0
Exp/Cntr=0.3,0.1