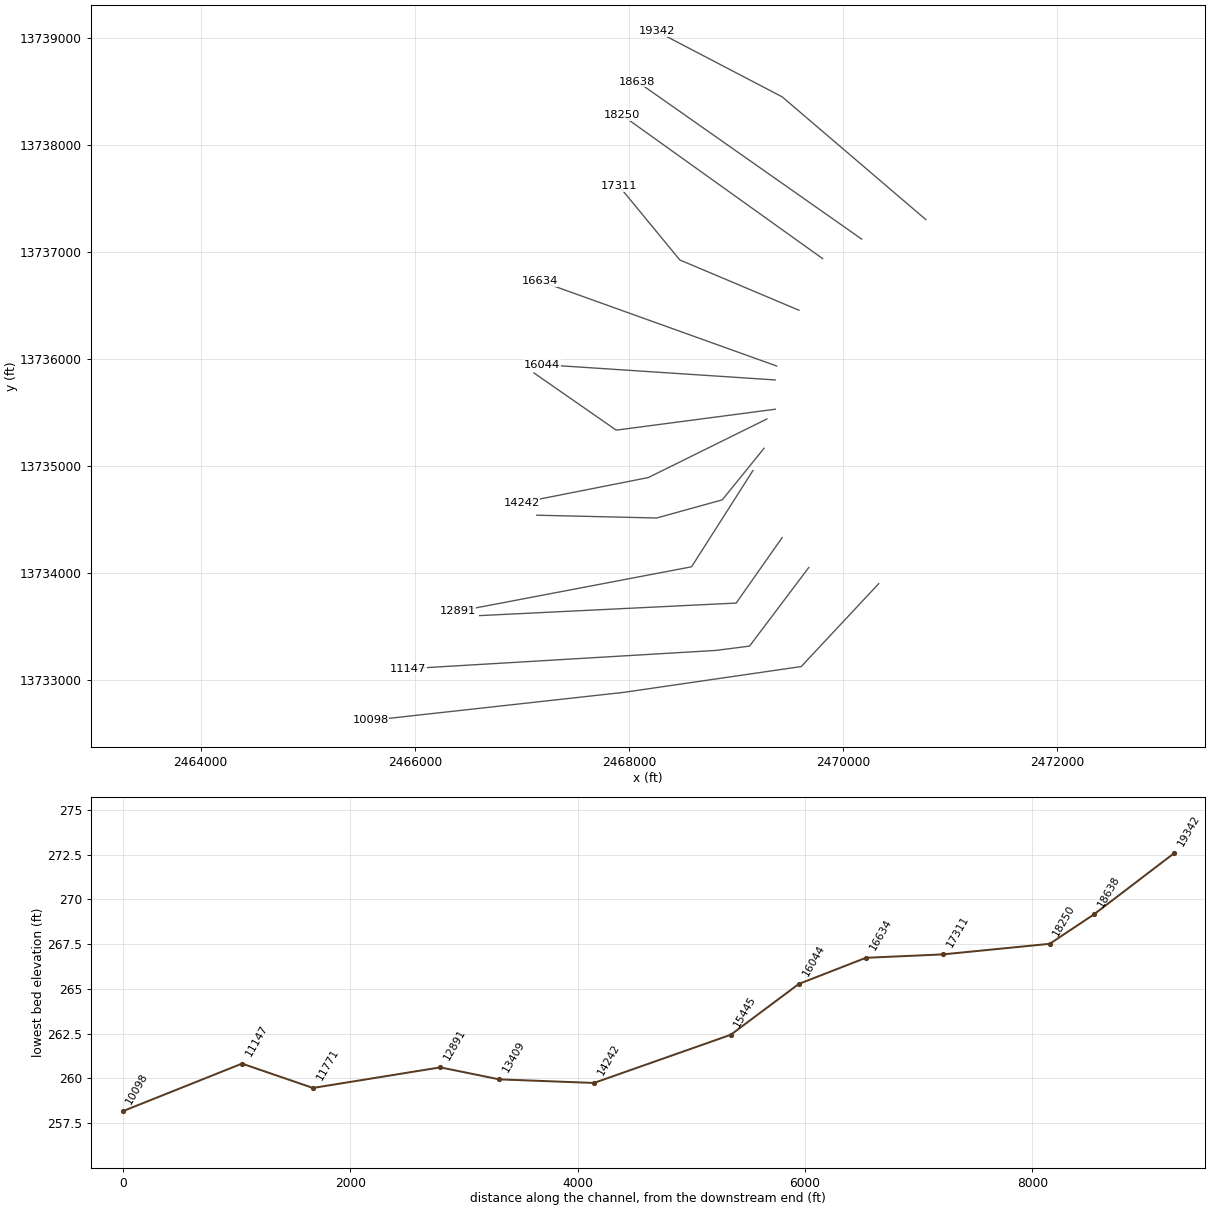
HEC-RAS study KERR CREEK.prj: KERR CREEK Base Level Engineering

--- KERR CREEK.g01 (geometry) --- (continued)

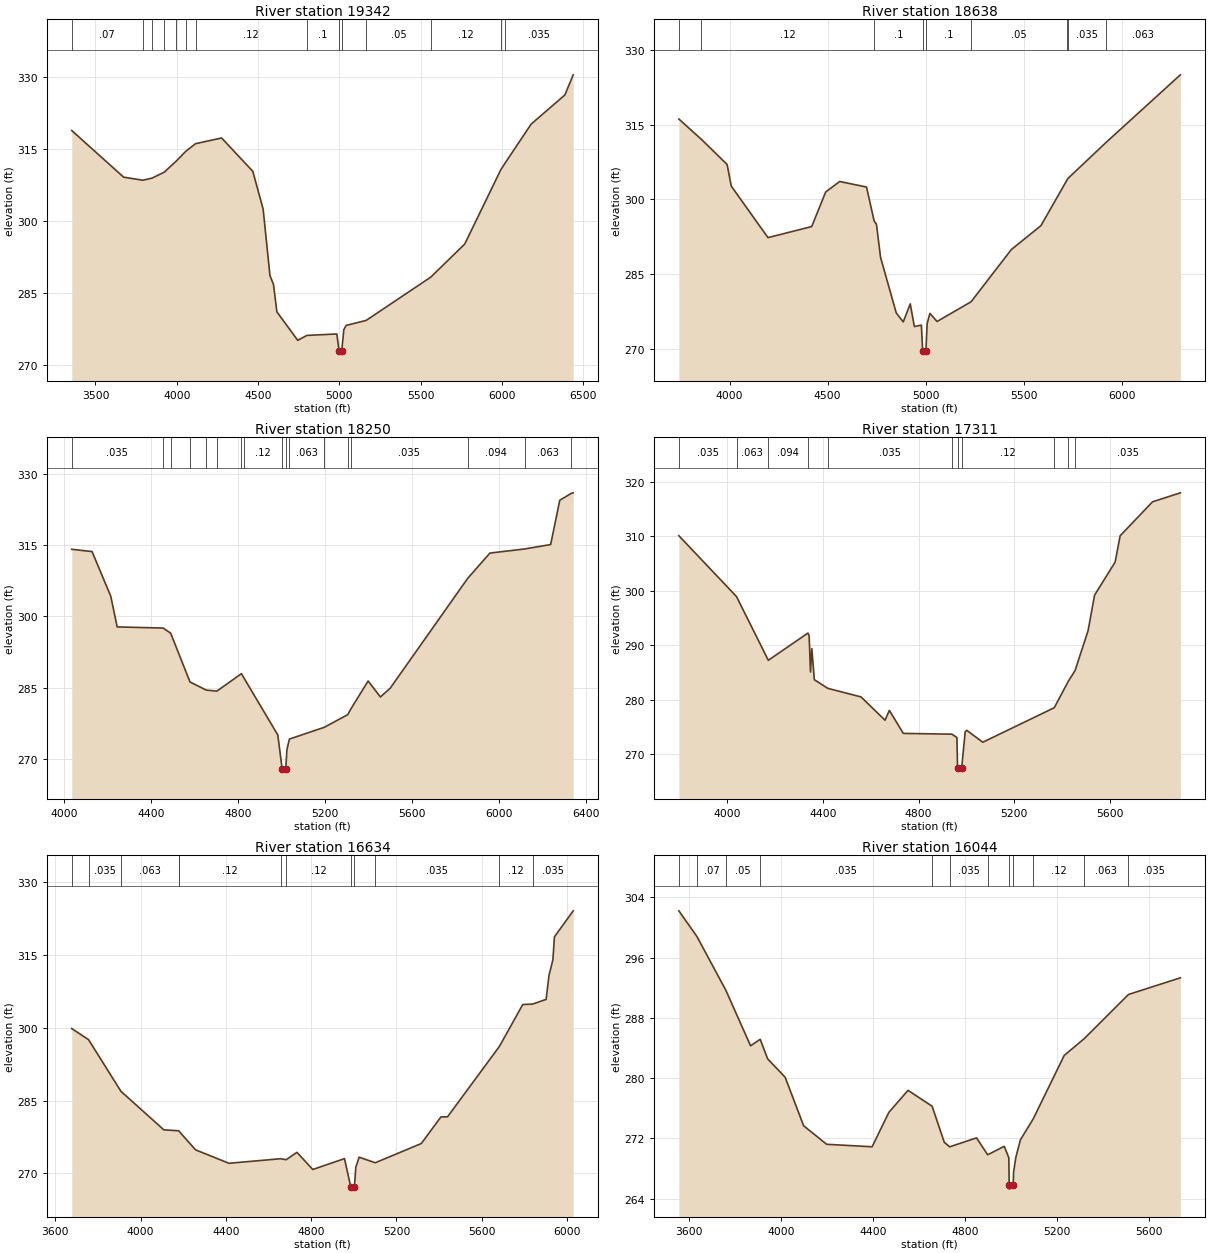
Type RM Length L Ch R = 1 ,19342   ,704,704,704
BEGIN DESCRIPTION:
KERR CREEK 9020
END DESCRIPTION:
XS GIS Cut Line= 3
      2470772.14     13737302.08      2469430.99     13738447.92
      2468259.59     13739059.65
#Sta/Elev= 30
    3354  318.93  3673.3  309.22  3790.9  308.58  3848.4  309.02  3923.6  310.27
  3995.1   312.5  4056.3  314.62    4116  316.19    4276  317.38  4468.1  310.44
  4531.8  302.55  4573.5  288.75  4595.5  286.85  4616.3  281.17  4744.4  275.24
  4800.8  276.26  4985.2  276.56  4998.8  273.07  4999.3  272.57  5015.5  273.07
    5028  277.43  5042.3  278.34  5165.6  279.38  5562.7  288.39    5772  295.28
  5994.1  310.77  6020.1  312.13  6180.3  320.25  6388.3  326.34  6439.5  330.53
#Mann= 14 ,-1 , 0
    3354     .07       0  3790.9    .035       0  3848.4     .12       0
  3923.6    .035       0  3995.1     .12       0  4056.3    .035       0
    4116     .12       0  4800.8      .1       0  4998.8     .05       0
  5015.5      .1       0  5165.6     .05       0  5562.7     .12       0
  5994.1     .05       0  6020.1    .035       0
Bank Sta=4998.8,5015.5
XS Rating Curve= 0 ,0
Exp/Cntr=0.3,0.1

Type RM Length L Ch R = 1 ,18638   ,388,388,388
BEGIN DESCRIPTION:
KERR CREEK 9019
END DESCRIPTION:
XS GIS Cut Line= 2
       2470173.2     13737119.78      2468079.19     13738589.48
#Sta/Elev= 30
    3741  316.12  3856.3  312.03  3987.2     307  4008.1  302.68  4195.5  292.33
  4418.6  294.55    4490  301.49  4561.5  303.59  4698.3  302.48  4737.3  295.65
  4748.9  295.04  4769.8   288.4  4849.9  277.23  4885.7  275.42  4921.4  279.04
  4942.3  274.49  4978.1  274.79  4984.5  269.66    4985  269.16  5001.3  269.66
  5007.7   275.1  5021.6  277.13  5058.2  275.51  5231.7  279.46    5437  289.93
  5588.1  294.73  5722.9  304.01  5725.4  304.18  5917.9  311.34  6299.3  324.99
#Mann= 9 ,-1 , 0
    3741    .063       0  3856.3     .12       0  4737.3      .1       0
  4984.5     .05       0  5001.3      .1       0  5231.7     .05       0
  5722.9    .063       0  5725.4    .035       0  5917.9    .063       0
Bank Sta=4984.5,5001.3
XS Rating Curve= 0 ,0
Exp/Cntr=0.3,0.1

Type RM Length L Ch R = 1 ,18250   ,939,939,939
BEGIN DESCRIPTION:
KERR CREEK 9018
END DESCRIPTION:
XS GIS Cut Line= 2
      2469808.58     13736937.51      2467933.56     13738278.67
#Sta/Elev= 30
  4036.6  314.11    4130  313.63    4216  304.26  4245.5  297.81  4456.6  297.57
  4491.5  296.49  4580.2  286.25  4654.3  284.55  4703.7  284.32    4817     288
  4827.3  287.15  4983.9  275.12  5003.8  268.02  5004.3  267.52  5020.7  268.02
  5025.7  272.01  5037.3  274.25    5198  276.73  5305.3  279.38  5321.6  280.71
  5399.2  286.45  5455.7   283.1  5499.9  284.89  5856.1  307.96    5959  313.32
    6119  314.18  6238.3  315.11  6280.1  324.41  6332.8  325.85  6341.9  325.97
#Mann= 17 ,-1 , 0
  4036.6    .035       0  4456.6    .063       0  4491.5    .035       0
  4580.2    .063       0  4654.3    .035       0  4703.7    .063       0
    4817    .035       0  4827.3     .12       0  5003.8     .05       0
  5020.7     .12       0  5037.3    .063       0    5198    .035       0
  5305.3    .063       0  5321.6    .035       0  5856.1    .094       0
    6119    .063       0  6332.8    .035       0
Bank Sta=5003.8,5020.7
XS Rating Curve= 0 ,0
Exp/Cntr=0.3,0.1

Type RM Length L Ch R = 1 ,17311   ,677,677,677
BEGIN DESCRIPTION:
KERR CREEK 9017
END DESCRIPTION:
XS GIS Cut Line= 3
       2469587.2     13736455.75        2468475.       13736925.
      2467908.75     13737613.13
#Sta/Elev= 30
  3796.7  310.11  4037.9  298.95  4170.9  287.26  4336.6  292.25  4341.8  291.73
  4347.5  285.11    4353  289.41  4363.5   283.7  4419.6  282.12    4559  280.54
  4659.3  276.27  4677.5  278.07  4735.8  273.85  4939.1  273.71  4960.1  273.09
  4962.8  267.43  4963.3  266.93  4979.8  267.43  4994.7  274.13  5001.1  274.42
  5068.4  272.23  5367.4  278.56  5424.9   283.3  5454.7   285.4  5508.9  292.69
  5536.2  299.22  5622.2  305.27  5643.1   310.1  5778.6  316.33    5895  317.98
#Mann= 11 ,-1 , 0
  3796.7    .035       0  4037.9    .063       0  4170.9    .094       0
  4336.6    .063       0  4419.6    .035       0  4939.1     .12       0
  4962.8     .05       0  4979.8     .12       0  5367.4    .035       0
  5424.9     .12       0  5454.7    .035       0
Bank Sta=4962.8,4979.8
XS Rating Curve= 0 ,0
Exp/Cntr=0.3,0.1

Type RM Length L Ch R = 1 ,16634   ,590,590,590
BEGIN DESCRIPTION:
KERR CREEK 9016
END DESCRIPTION:
XS GIS Cut Line= 2
      2469378.91      13735934.9      2467165.39     13736729.16
#Sta/Elev= 30
    3677  299.87  3755.7  297.58  3907.9  286.91    4109  278.97    4178  278.78
  4178.5  278.77  4257.4  274.85  4414.2  272.07  4656.4  273.01  4682.5  272.81
  4733.3  274.33  4807.3  270.79  4956.1  273.03  4985.4  267.24  4985.9  266.74
  5002.7  267.24  5009.2  271.25  5024.8  273.33  5100.5  272.18  5316.3  276.15
  5408.5  281.64  5439.2  281.65  5682.8  296.19  5792.2  304.82  5838.4  304.91
  5901.6  305.88  5915.2  310.83  5933.5  314.06  5940.6  318.77  6028.7  324.15
#Mann= 12 ,-1 , 0
    3677     .07       0  3755.7    .035       0  3907.9    .063       0
    4178    .035       0  4178.5     .12       0  4656.4    .035       0
  4682.5     .12       0  4985.4     .05       0  5002.7     .12       0
  5100.5    .035       0  5682.8     .12       0  5838.4    .035       0
Bank Sta=4985.4,5002.7
XS Rating Curve= 0 ,0
Exp/Cntr=0.3,0.1

Type RM Length L Ch R = 1 ,16044   ,599,599,599
BEGIN DESCRIPTION:
KERR CREEK 9015
END DESCRIPTION:
XS GIS Cut Line= 2
      2469365.84     13735804.69      2467191.45     13735947.91
#Sta/Elev= 30
    3556  302.21  3634.7  298.79  3759.8  291.69  3867.5   284.3  3909.4  285.16
  3941.9  282.56  4017.8  280.13  4098.1  273.69  4198.2  271.23  4395.6   270.9
  4468.8  275.48  4551.8  278.39  4656.5  276.28  4709.3   271.5  4732.7  270.89
  4849.3  272.08  4897.9  269.84  4969.9  270.96  4989.9  269.43  4991.3  265.78
  4991.8  265.28  5008.7  265.78  5010.5  267.54    5020  269.46    5040  271.81
  5095.6  274.59  5230.5  283.02  5317.5  285.25  5509.8  291.11  5735.1  293.32
#Mann= 12 ,-1 , 0
    3556     .05       0  3634.7     .07       0  3759.8     .05       0
  3909.4    .035       0  4656.5     .12       0  4732.7    .035       0
  4897.9     .07       0  4991.3     .05       0  5008.7     .07       0
  5095.6     .12       0  5317.5    .063       0  5509.8    .035       0
Bank Sta=4991.3,5008.7
XS Rating Curve= 0 ,0
Exp/Cntr=0.3,0.1

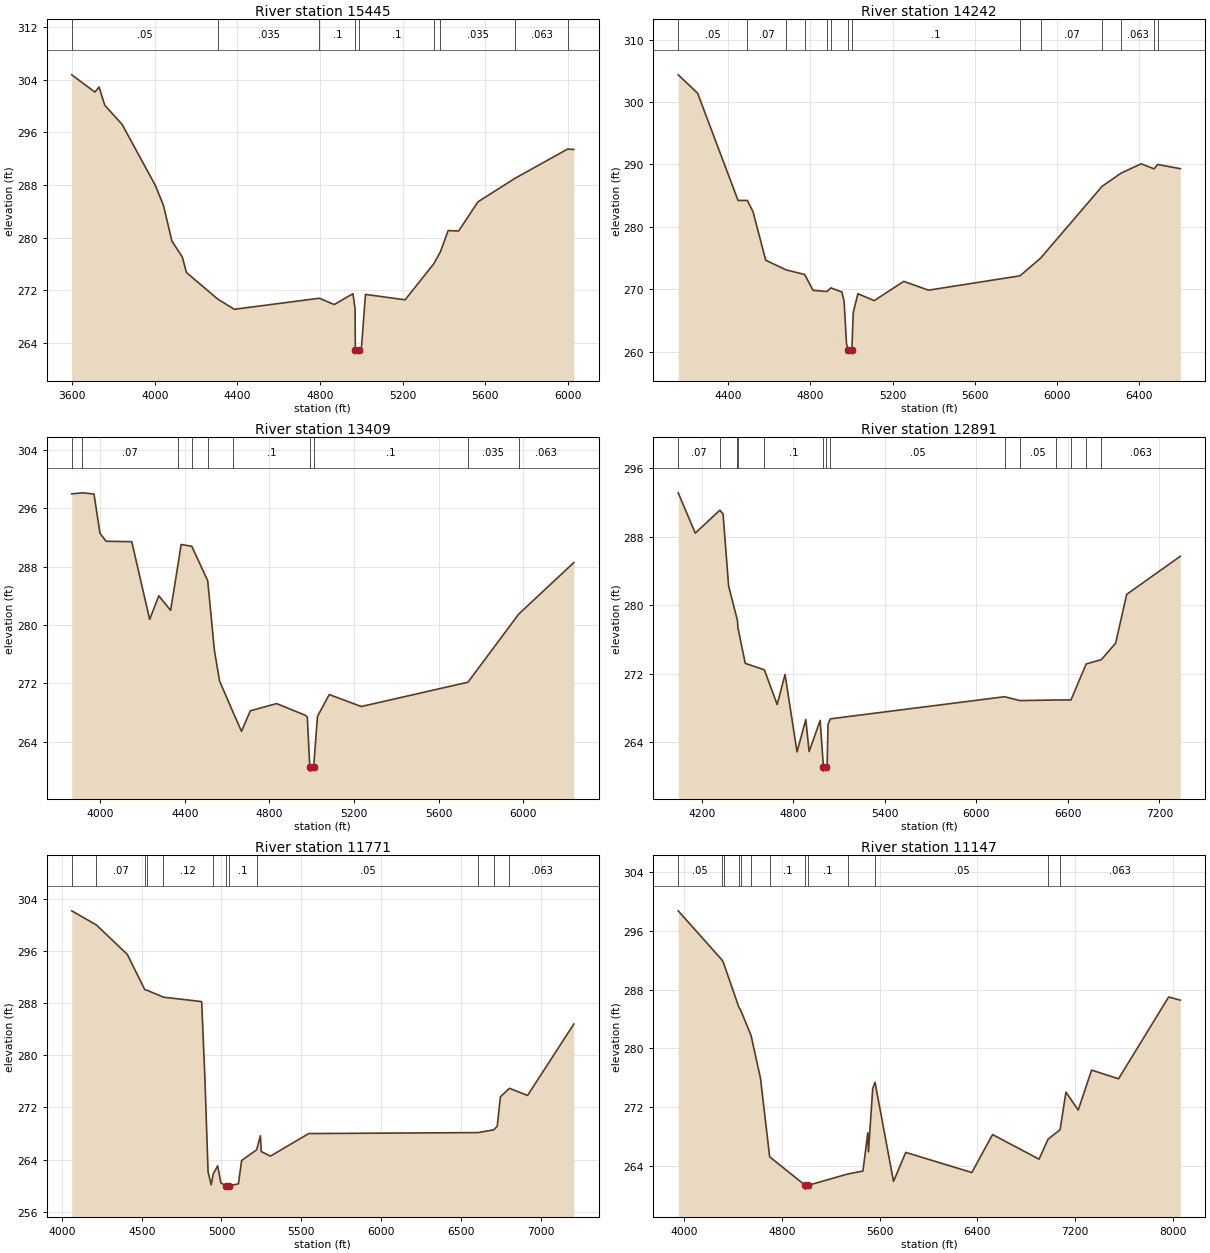
Type RM Length L Ch R = 1 ,15445   ,1203,1203,1203
BEGIN DESCRIPTION:
KERR CREEK 9014
END DESCRIPTION:
XS GIS Cut Line= 3
      2469365.92     13735531.26      2467881.51     13735335.94
      2467113.29     13735869.78
#Sta/Elev= 30
  3597.5  304.72  3709.4   302.1  3729.6  302.87  3757.6  300.09  3841.3  297.19
  4001.9  287.96  4042.2  284.85  4082.6  279.47    4133  277.05  4153.2  274.69
  4304.9  270.65  4385.2   269.1  4796.9  270.78  4869.3  269.82  4960.1  271.47
  4970.2  269.14  4971.5  262.94    4972  262.44  4988.9  262.94  5000.4  263.01
  5020.6  271.36  5212.6  270.54  5351.2     276  5383.7  277.83  5421.3  281.06
  5471.9  280.99  5565.4  285.42  5747.3  289.04  5999.5  293.43  6030.2  293.39
#Mann= 9 ,-1 , 0
  3597.5     .05       0  4304.9    .035       0  4796.9      .1       0
  4971.5     .05       0  4988.9      .1       0  5351.2    .063       0
  5383.7    .035       0  5747.3    .063       0  5999.5    .035       0
Bank Sta=4971.5,4988.9
XS Rating Curve= 0 ,0
Exp/Cntr=0.3,0.1

Type RM Length L Ch R = 1 ,14242   ,833,833,833
BEGIN DESCRIPTION:
KERR CREEK 9013
END DESCRIPTION:
XS GIS Cut Line= 3
       2469287.8     13735440.13      2468180.99     13734893.23
      2466998.07     13734659.24
#Sta/Elev= 30
    4158  304.35  4252.3   301.4  4448.7  284.22  4493.9  284.22  4521.6   282.4
  4583.3  274.63  4682.8  273.09  4772.7  272.35  4813.3  269.81    4881  269.62
  4899.8  270.21  4953.5  269.55  4964.2  268.05  4975.9  261.28  4983.9  260.25
  4984.4  259.75  5001.8  260.25  5008.8  266.28  5031.2  269.27  5110.6  268.16
  5254.2  271.25  5374.3  269.84  5819.3  272.14  5919.1  274.97  6218.5  286.49
  6310.9   288.6  6407.8  290.09    6471  289.29  6488.2  289.98  6598.4  289.31
#Mann= 14 ,-1 , 0
    4158     .05       0  4493.9     .07       0  4682.8     .05       0
  4772.7    .035       0    4881     .05       0  4899.8      .1       0
  4983.9     .05       0  5001.8      .1       0  5819.3    .035       0
  5919.1     .07       0  6218.5    .035       0  6310.9    .063       0
    6471    .035       0  6488.2    .063       0
Bank Sta=4983.9,5001.8
XS Rating Curve= 0 ,0
Exp/Cntr=0.3,0.1

Type RM Length L Ch R = 1 ,13409   ,518,518,518
BEGIN DESCRIPTION:
KERR CREEK 9012
END DESCRIPTION:
XS GIS Cut Line= 4
      2469261.71     13735166.65      2468871.09      13734684.9
      2468259.11     13734515.63      2467139.69     13734541.66
#Sta/Elev= 30
    3865  297.97  3914.9  298.11  3970.1  297.95  3998.5  292.56  4027.3  291.47
  4148.7  291.41  4233.5  280.76  4276.6  283.99  4332.6     282  4368.3  288.41
  4382.2  291.03  4432.7  290.78  4508.1  286.05  4539.7  276.52  4564.2   272.3
  4628.2  268.01  4667.9  265.41  4709.4  268.22  4833.9  269.21  4968.8  267.62
  4979.2  267.36    4991  260.45  4991.5  259.95  5008.9  260.45  5027.3  267.46
  5082.9  270.45  5234.3  268.81    5739  272.14    5979  281.48  6239.9  288.55
#Mann= 10 ,-1 , 0
    3865     .05       0  3914.9     .07       0  4368.3     .12       0
  4432.7     .07       0  4508.1     .12       0  4628.2      .1       0
    4991     .05       0  5008.9      .1       0    5739    .035       0
    5979    .063       0
Bank Sta=4991,5008.9
XS Rating Curve= 0 ,0
Exp/Cntr=0.3,0.1

Type RM Length L Ch R = 1 ,12891   ,1120,1120,1120
BEGIN DESCRIPTION:
KERR CREEK 9011
END DESCRIPTION:
XS GIS Cut Line= 3
      2469157.55     13734958.33      2468584.64      13734059.9
       2466398.6     13733643.51
#Sta/Elev= 30
  4046.1  293.13  4157.9  288.42  4318.4   291.1  4339.9  290.67  4376.3  282.25
  4434.2  278.22  4437.3  277.38  4485.4  273.21    4611  272.45  4694.5   268.4
  4746.1  271.91  4824.8  262.87  4882.3  266.65    4904   262.9  4976.3  266.54
  4997.7  261.12  4998.2  260.62  5015.8  261.12    5022  261.25  5027.9   266.1
  5043.8  266.73  6184.8  269.31  6285.6  268.86  6520.7  268.93  6620.4  268.94
  6720.1  273.14  6819.7  273.65  6913.1  275.57  6985.6  281.27    7337  285.72
#Mann= 14 ,-1 , 0
  4046.1     .07       0  4318.4      .1       0  4434.2     .07       0
  4437.3     .12       0    4611      .1       0  4997.7     .05       0
  5015.8      .1       0  5043.8     .05       0  6184.8     .07       0
  6285.6     .05       0  6520.7    .035       0  6620.4     .05       0
  6720.1    .035       0  6819.7    .063       0
Bank Sta=4997.7,5015.8
XS Rating Curve= 0 ,0
Exp/Cntr=0.3,0.1

Type RM Length L Ch R = 1 ,11771   ,624,624,624
BEGIN DESCRIPTION:
KERR CREEK 9010
END DESCRIPTION:
XS GIS Cut Line= 3
      2469430.99     13734333.33       2469001.3     13733721.35
      2466605.43     13733604.16
#Sta/Elev= 30
  4061.7  302.15  4216.6  299.97  4409.7  295.47    4519  290.07  4535.8  289.94
  4636.5  288.91  4875.8  288.23  4895.9  276.57  4915.9  262.11  4935.9  260.13
  4947.3  261.74    4976  263.05    4996  260.44    5027  259.97  5027.5  259.47
  5045.1  259.97  5106.1  260.28  5126.1  263.86  5220.4   265.5  5243.9  267.66
  5248.9  265.24  5306.4  264.53  5546.6  267.99  6607.8  268.14  6706.2  268.56
  6728.1  269.12  6748.1  273.64  6804.7  274.93  6918.3  273.84  7208.2  284.79
#Mann= 12 ,-1 , 0
  4061.7     .05       0  4216.6     .07       0    4519     .12       0
  4535.8     .07       0  4636.5     .12       0  4947.3      .1       0
    5027     .05       0  5045.1      .1       0  5220.4     .05       0
  6607.8    .035       0  6706.2     .05       0  6804.7    .063       0
Bank Sta=5027,5045.1
XS Rating Curve= 0 ,0
Exp/Cntr=0.3,0.1

Type RM Length L Ch R = 1 ,11147   ,1049,1049,1049
BEGIN DESCRIPTION:
A19523
END DESCRIPTION:
XS GIS Cut Line= 4
      2469678.99     13734053.24      2469126.17     13733319.49
      2468814.57     13733279.29      2465939.91     13733108.42
#Sta/Elev= 30
  3950.4  298.72  4308.8  292.03  4321.4  291.63  4447.4  285.58  4462.6  285.17
    4547  281.74  4624.1  275.92  4699.3  265.23    4992  261.33  4992.5  260.83
  5010.6  261.33  5341.5   262.9  5463.3  263.29  5503.4   268.5  5508.4  265.92
  5543.5  274.52  5562.3  275.39  5713.8  261.88    5814  265.83  6355.5  263.09
  6525.2  268.26  6905.9  264.91  6979.7  267.63  7078.1  268.92  7126.3  274.04
  7226.4  271.59  7336.6  277.04    7557  275.85  7967.7  286.99    8063  286.56
#Mann= 13 ,-1 , 0
  3950.4     .05       0  4308.8     .07       0  4321.4     .05       0
  4447.4     .12       0  4462.6      .1       0    4547     .12       0
  4699.3      .1       0    4992     .05       0  5010.6      .1       0
  5341.5     .12       0  5562.3     .05       0  6979.7    .035       0
  7078.1    .063       0
Bank Sta=4992,5010.6
XS Rating Curve= 0 ,0
Exp/Cntr=0.3,0.1

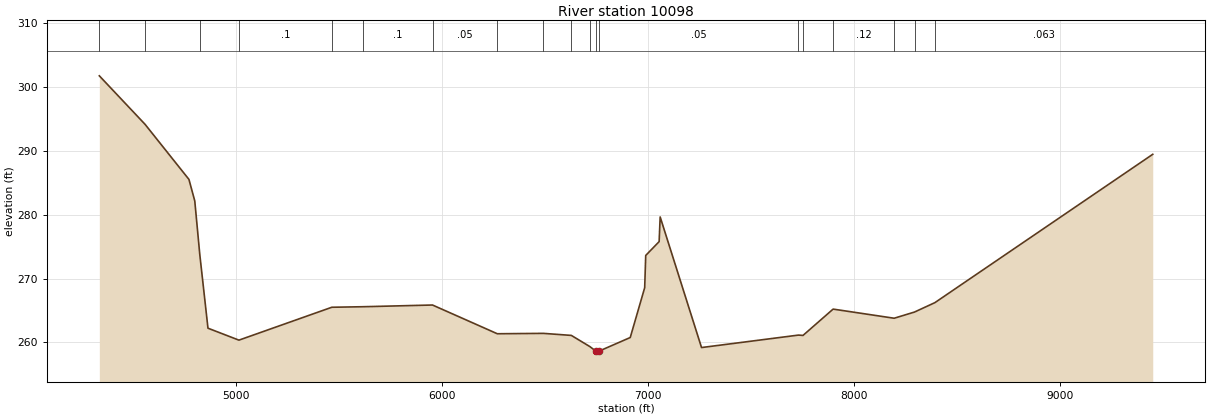
Type RM Length L Ch R = 1 ,10098   ,633,633,633
BEGIN DESCRIPTION:
A19522
END DESCRIPTION:
XS GIS Cut Line= 4
      2470332.33     13733902.48      2469608.63     13733128.52
      2467950.16     13732887.29      2465589.09     13732626.06
#Sta/Elev= 30
  4336.7  301.75  4558.4  294.16  4771.5  285.53  4799.8  282.15  4824.2  273.74
  4863.8  262.23    5014  260.36  5464.8  265.51  5614.2  265.59  5953.2  265.86
  6267.6  261.36  6491.3  261.42  6626.9   261.1  6716.2  259.36  6744.8  258.67
  6745.3  258.17  6763.4  258.67  6912.6  260.77  6982.7  268.57  6987.7  273.62
  7052.8  275.79  7057.8  279.65  7258.5   259.2  7728.7  261.15  7750.9   261.1
  7896.9  265.22  8193.1  263.79  8291.8  264.76  8390.6  266.23  9447.7  289.46
#Mann= 19 ,-1 , 0
  4336.7    .035       0  4558.4     .07       0  4824.2    .035       0
    5014      .1       0  5464.8     .05       0  5614.2      .1       0
  5953.2     .05       0  6267.6      .1       0  6491.3     .05       0
  6626.9     .12       0  6716.2     .05       0  6744.8    .035       0
  6763.4     .05       0  7728.7    .045       0  7750.9     .05       0
  7896.9     .12       0  8193.1     .05       0  8291.8    .035       0
  8390.6    .063       0
Bank Sta=6744.8,6763.4
XS Rating Curve= 0 ,0
Exp/Cntr=0.3,0.1