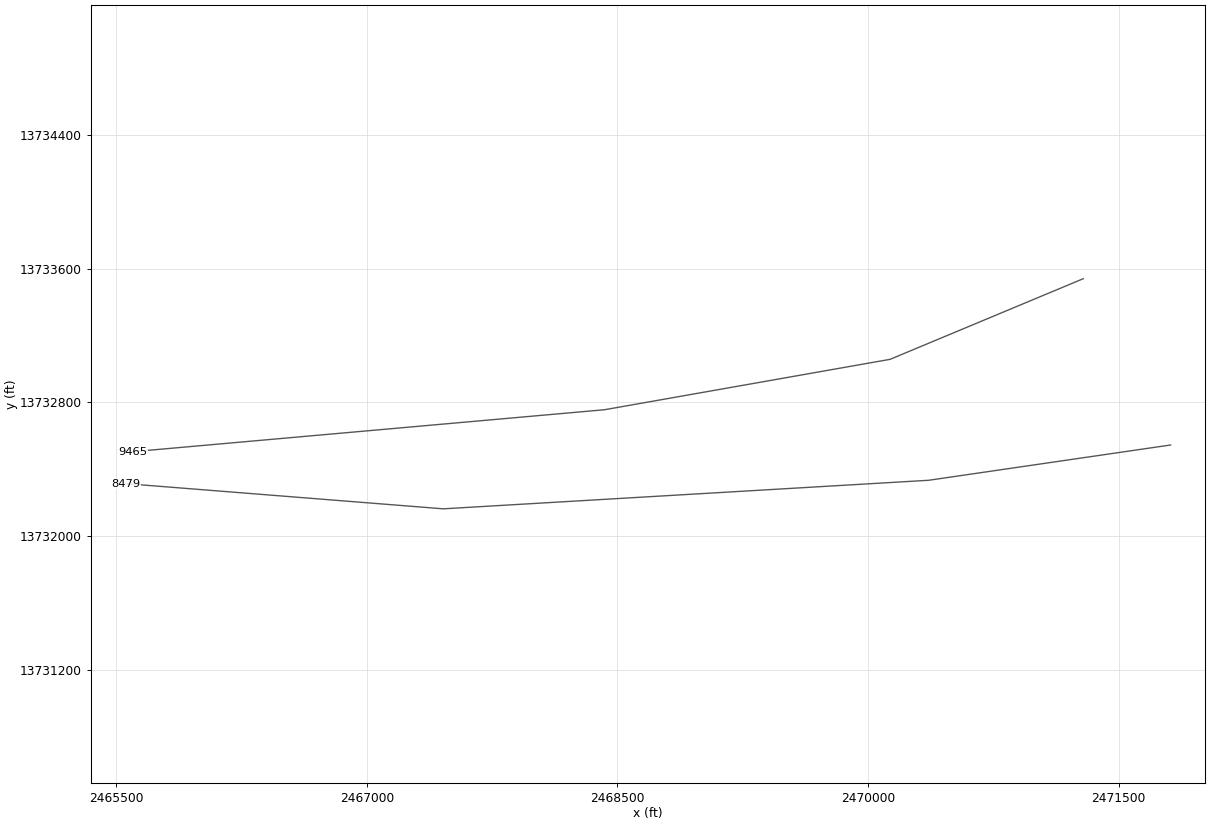
HEC-RAS study KERR CREEK.prj: KERR CREEK Base Level Engineering

--- KERR CREEK.g01 (geometry) --- (continued)

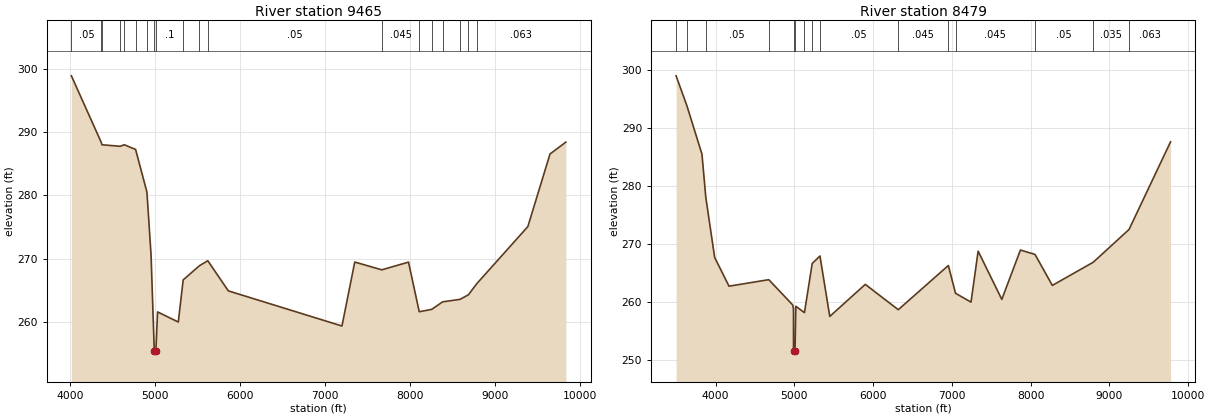
Type RM Length L Ch R = 1 ,9465    ,986,986,986
BEGIN DESCRIPTION:
A19521
END DESCRIPTION:
XS GIS Cut Line= 4
      2471287.18     13733540.61       2470131.3     13733058.16
      2468422.57     13732756.62      2465599.08     13732505.42
#Sta/Elev= 30
  4011.9  298.92  4364.4  288.36  4371.4  288.01    4585  287.77  4635.5  288.01
  4767.9  287.27  4901.3  280.53  4949.8  270.62    4988  255.38  4988.5  254.88
  5006.9  255.38  5026.7  261.56  5270.8  259.96    5328  266.62  5518.6  268.86
  5618.1  269.66  5859.8  264.89  7197.9  259.33  7348.5  269.45  7666.4  268.22
  7981.5  269.44  8107.6  261.59  8254.1  261.96    8383  263.15  8588.1  263.55
  8686.7  264.27  8785.3  266.03  9386.5  275.06  9647.5  286.55  9834.2  288.43
#Mann= 19 ,-1 , 0
  4011.9     .05       0  4364.4    .035       0  4371.4     .05       0
    4585    .035       0  4635.5     .05       0  4767.9    .035       0
  4901.3      .1       0    4988     .05       0  5006.9      .1       0
    5328     .05       0  5518.6    .035       0  5618.1     .05       0
  7666.4    .045       0  8107.6     .05       0  8254.1    .045       0
    8383     .05       0  8588.1     .12       0  8686.7    .035       0
  8785.3    .063       0
Bank Sta=4988,5006.9
XS Rating Curve= 0 ,0
Exp/Cntr=0.3,0.1

Type RM Length L Ch R = 1 ,8479    ,0,0,0
BEGIN DESCRIPTION:
A19520
END DESCRIPTION:
XS GIS Cut Line= 4
      2471809.87     13732545.54      2470362.48     13732334.46
      2467457.64     13732163.59      2465558.98     13732314.28
#Sta/Elev= 30
  3498.9  299.05  3634.9  293.94  3827.2  285.54  3876.2  278.08  3988.9  267.69
  4170.8  262.74  4675.9  263.86  4979.1   259.5  4989.1   258.9  4989.7  251.51
  4990.2  251.01  5008.6  251.51  5019.2  259.27  5128.4  258.17  5226.9  266.65
  5325.3  267.95  5449.9  257.52  5900.7  263.05  6319.7  258.68  6955.1  266.31
  7046.2  261.52    7243  259.98  7333.2  268.79  7633.7  260.46  7870.3  268.98
  8055.6  268.22  8275.4  262.87  8794.3  266.87  9248.6  272.52  9776.1  287.66
#Mann= 15 ,-1 , 0
  3498.9     .05       0  3634.9     .07       0  3876.2     .05       0
  4675.9      .1       0  4989.7     .05       0  5008.6      .1       0
  5128.4     .05       0  5226.9    .035       0  5325.3     .05       0
  6319.7    .045       0  6955.1     .05       0  7046.2    .045       0
  8055.6     .05       0  8794.3    .035       0  9248.6    .063       0
Bank Sta=4989.7,5008.6
XS Rating Curve= 0 ,0
Exp/Cntr=0.3,0.1

Chan Stop Cuts=-1
Use User Specified Reach Order=0
Composite Channel Slope=5