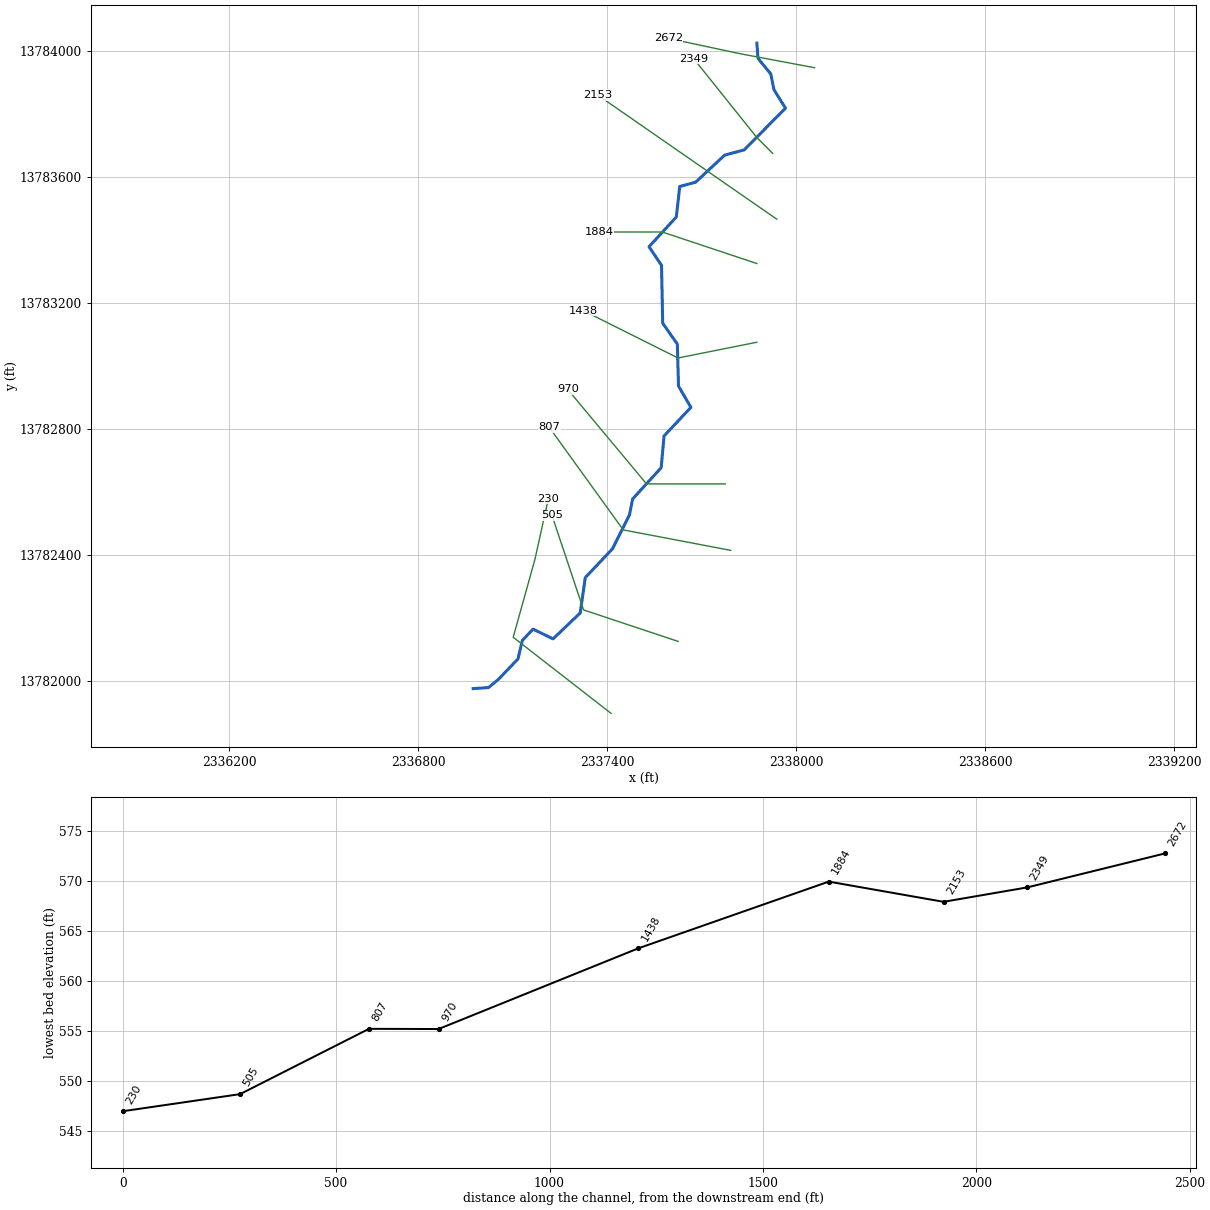
--- LONG BRANCH TRIBUTARY 1A.prj (project) ---

Proj Title=LONG BRANCH TRIBUTARY 1A Base Level Engineering
Current Plan=p01
Default Exp/Contr=0.3,0.1
English Units
Geom File=g01
Flow File=f01
Plan File=p01
BEGIN DESCRIPTION:
LONG BRANCH TRIBUTARY 1A
END DESCRIPTION:

--- LONG BRANCH TRIBUTARY 1A.p01 (plan) ---

Plan Title=Multiple Run
Short Identifier=Multiple
Geom File=g01
Flow File=f01
Subcritical Flow
K Sum by GR= 0
Std Step Tol= 0.01
Critical Tol= 0.01
Num of Std Step Trials= 20
Max Error Tol= 0.3
Flow Tol Ratio= 0.001
Split Flow NTrial= 30
Split Flow Tol= 0.02
Split Flow Ratio= 0.02
Log Output Level= 0
Friction Slope Method= 1
Unsteady Friction Slope Method= 2
Unsteady Bridges Friction Slope Method= 1
Parabolic Critical Depth
Global Vel Dist=  1 , 1 , 1
Global Log Level= 0
CheckData=True
Encroach Param= -1, 0, 0, 0
BEGIN DESCRIPTION:
Multiple Run
END DESCRIPTION:

--- LONG BRANCH TRIBUTARY 1A.f01 (steady flow) ---

Flow Title=Multiple
Number of Profiles=7
Profile Names=10-year,25-year,50-year,1pct_min,100-year,1pct_plu,500-year
River Rch & RM= LONG BRANCH TRIB,Reach-1,2672
     429     675     890     569    1135    2265    1830
Boundary for River Rch & Prof#=LONG BRANCH TRIB,Reach-1,1
Up Type=0
Dn Type=3
Dn Slope=0.005
Boundary for River Rch & Prof#=LONG BRANCH TRIB,Reach-1,2
Up Type=0
Dn Type=3
Dn Slope=0.005
Boundary for River Rch & Prof#=LONG BRANCH TRIB,Reach-1,3
Up Type=0
Dn Type=3
Dn Slope=0.005
Boundary for River Rch & Prof#=LONG BRANCH TRIB,Reach-1,4
Up Type=0
Dn Type=3
Dn Slope=0.005
Boundary for River Rch & Prof#=LONG BRANCH TRIB,Reach-1,5
Up Type=0
Dn Type=3
Dn Slope=0.005
Boundary for River Rch & Prof#=LONG BRANCH TRIB,Reach-1,6
Up Type=0
Dn Type=3
Dn Slope=0.005
Boundary for River Rch & Prof#=LONG BRANCH TRIB,Reach-1,7
Up Type=0
Dn Type=3
Dn Slope=0.005

--- LONG BRANCH TRIBUTARY 1A.g01 (geometry) ---

Geom Title=Existing Conditions

River Reach=LONG BRANCH TRIB,Reach-1
Reach XY= 30
      2337875.00     13784025.00      2337878.60     13783976.49
      2337919.08     13783927.24      2337929.42     13783876.63
      2337965.89     13783818.27      2337834.68     13783685.78
      2337772.72     13783669.13      2337680.70     13783583.32
      2337630.26     13783569.53      2337619.42     13783472.63
      2337532.81     13783378.41      2337572.53     13783319.15
      2337576.22     13783135.51      2337622.73     13783069.06
      2337626.40     13782935.44      2337665.85     13782868.27
      2337580.55     13782777.43      2337571.37     13782676.50
      2337480.85     13782577.29      2337470.81     13782526.73
      2337416.84     13782418.95      2337330.54     13782327.42
      2337314.48     13782215.17      2337228.34     13782133.00
      2337164.68     13782163.89      2337130.85     13782127.83
      2337116.86     13782068.98      2337055.22     13782004.65
      2337023.66     13781978.27      2336975.00     13781975.00

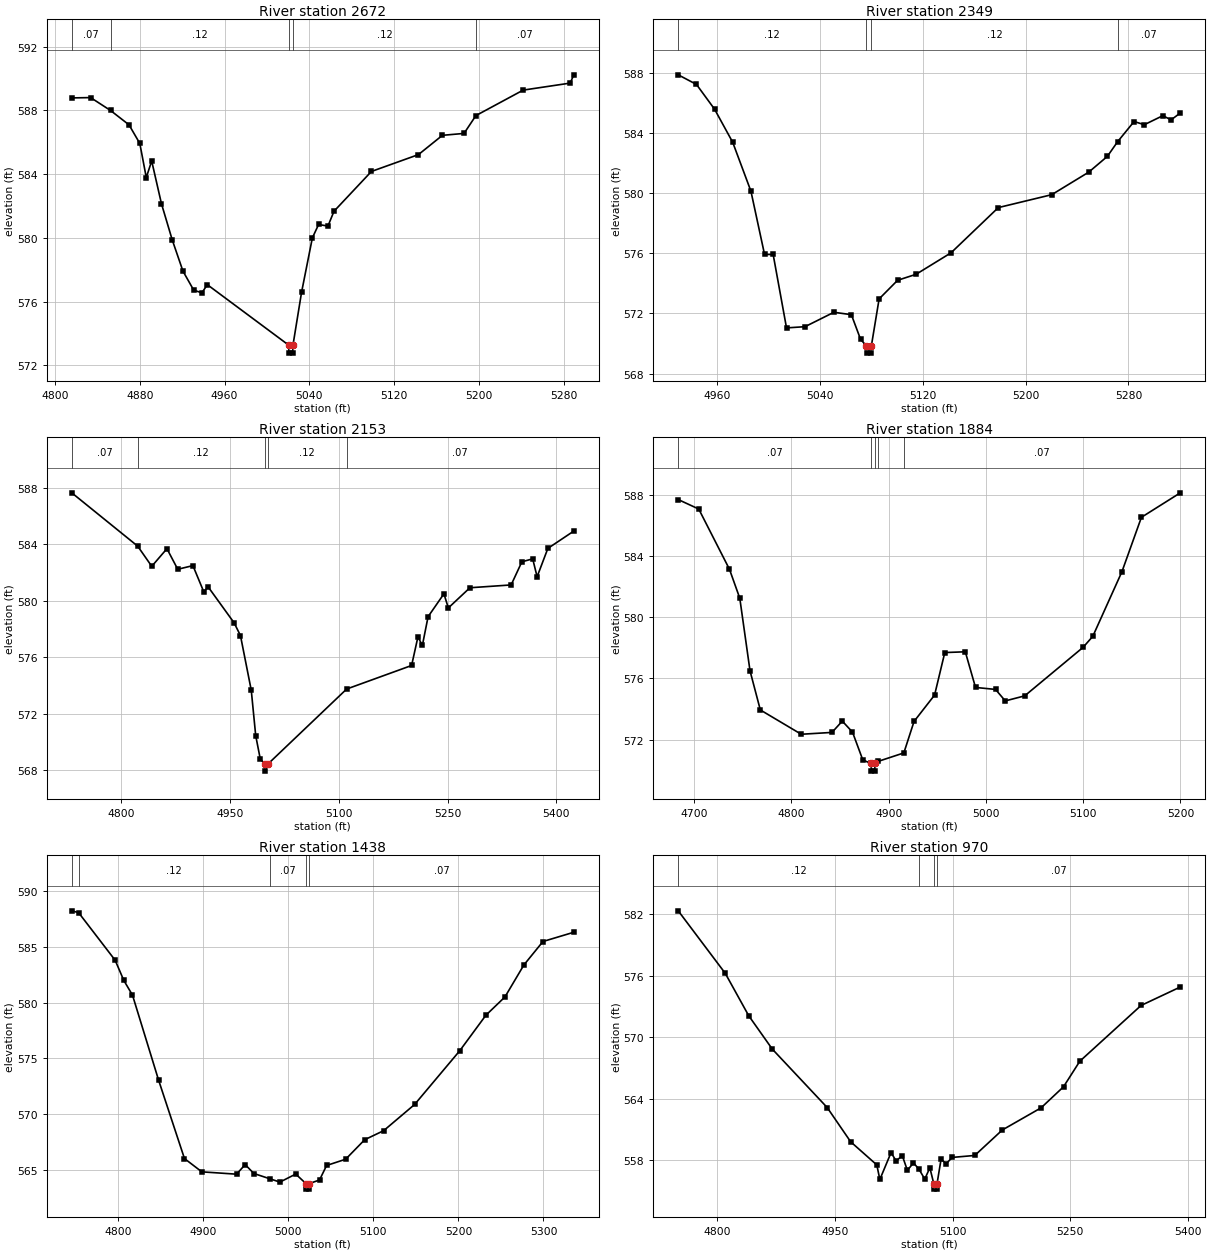
Type RM Length L Ch R = 1,2672,323,323,323
BEGIN DESCRIPTION:
A19728
END DESCRIPTION:
XS GIS Cut Line= 3
      2338058.11     13783946.83      2337820.55     13783991.50
      2337593.73     13784040.11
#Sta/Elev= 30
  4815.8  588.79  4833.6  588.81  4852.4  588.00  4869.8  587.10  4880.0  585.93
  4886.1  583.79  4891.2  584.83  4900.4  582.15  4910.5  579.89  4920.7  577.91
  4930.9  576.71  4938.6  576.55  4943.7  577.06  5020.5  573.26  5020.7  572.76
  5024.2  572.76  5024.5  573.26  5032.6  576.58  5042.8  580.00  5048.7  580.84
  5057.5  580.74  5063.2  581.67  5098.5  584.17  5142.9  585.23  5165.5  586.44
  5185.9  586.56  5197.1  587.68  5241.7  589.28  5286.0  589.72  5289.5  590.24
#Mann=5,-1,0
  4815.8    0.07       0  4852.4    0.12       0  5020.5    0.05       0
  5024.5    0.12       0  5197.1    0.07       0
Bank Sta=5020.5,5024.5
Exp/Cntr=0.3,0.1

Type RM Length L Ch R = 1,2349,196,196,196
BEGIN DESCRIPTION:
LONG BRANCH TRIBUTARY 1A 5.0
END DESCRIPTION:
XS GIS Cut Line= 3
      2337925.01     13783674.99      2337875.00     13783725.00
      2337674.99     13783975.01
#Sta/Elev= 30
  4929.5  587.89  4943.7  587.25  4957.8  585.60  4971.9  583.40  4986.1  580.14
  4996.7  575.93  5003.4  575.93  5013.8  571.04  5028.2  571.12  5050.7  572.08
  5064.3  571.92  5071.5  570.27  5075.9  569.86  5076.1  569.36  5079.6  569.36
  5079.9  569.86  5085.9  572.97  5100.3  574.21  5114.7  574.61  5141.9  576.04
  5178.7  579.05  5220.3  579.91  5249.1  581.41  5263.6  582.46  5271.6  583.44
  5284.4  584.78  5292.4  584.57  5306.8  585.17  5313.2  584.89  5320.4  585.35
#Mann=4,-1,0
  4929.5    0.12       0  5075.9    0.05       0  5079.9    0.12       0
  5271.6    0.07       0
Bank Sta=5075.9,5079.9
Exp/Cntr=0.3,0.1

Type RM Length L Ch R = 1,2153,269,269,269
BEGIN DESCRIPTION:
A19729
END DESCRIPTION:
XS GIS Cut Line= 2
      2337938.32     13783465.67      2337370.05     13783860.02
#Sta/Elev= 30
  4732.3  587.65  4823.1  583.87  4842.5  582.44  4863.4  583.69  4878.3  582.23
  4899.2  582.49  4914.1  580.64  4920.2  580.98  4956.0  578.43  4964.7  577.53
  4979.6  573.65  4985.7  570.44  4992.0  568.78  4998.5  568.42  4998.8  567.92
  5002.5  568.42  5111.0  573.74  5200.5  575.41  5209.2  577.44  5215.3  576.83
  5223.2  578.87  5245.0  580.49  5251.1  579.49  5280.8  580.92  5337.6  581.12
  5352.4  582.76  5367.3  582.97  5373.4  581.70  5388.2  583.71  5424.0  584.94
#Mann=5,-1,0
  4732.3    0.07       0  4823.1    0.12       0  4998.5    0.05       0
  5002.5    0.12       0  5111.0    0.07       0
Bank Sta=4998.5,5002.5
Exp/Cntr=0.3,0.1

Type RM Length L Ch R = 1,1884,446,446,446
BEGIN DESCRIPTION:
LONG BRANCH TRIBUTARY 1A 4.0
END DESCRIPTION:
XS GIS Cut Line= 3
      2337875.03     13783324.99      2337575.00     13783425.00
      2337374.96     13783425.00
#Sta/Elev= 30
  4683.6  587.69  4704.7  587.07  4736.3  583.13  4746.9  581.24  4757.4  576.50
  4768.0  573.94  4810.1  572.35  4841.7  572.47  4852.3  573.21  4862.8  572.49
  4873.4  570.67  4881.9  570.44  4882.2  569.94  4885.7  569.94  4885.9  570.44
  4889.3  570.58  4915.6  571.13  4926.1  573.19  4947.2  574.91  4957.7  577.69
  4978.8  577.74  4989.3  575.41  5009.9  575.28  5019.9  574.53  5039.9  574.86
  5099.9  578.03  5109.9  578.75  5139.9  582.98  5159.9  586.53  5199.9  588.13
#Mann=5,-1,0
  4683.6    0.07       0  4881.9    0.05       0  4885.9    0.07       0
  4889.3    0.12       0  4915.6    0.07       0
Bank Sta=4881.9,4885.9
Exp/Cntr=0.3,0.1

Type RM Length L Ch R = 1,1438,468,468,468
BEGIN DESCRIPTION:
LONG BRANCH TRIBUTARY 1A 3.0
END DESCRIPTION:
XS GIS Cut Line= 3
      2337874.97     13783074.99      2337625.00     13783025.00
      2337325.03     13783174.98
#Sta/Elev= 30
  4745.4  588.22  4753.4  588.06  4796.4  583.79  4806.6  581.98  4816.8  580.66
  4847.4  573.06  4877.9  566.01  4898.3  564.82  4939.1  564.61  4949.3  565.47
  4959.5  564.67  4978.6  564.19  4990.1  563.90  5008.7  564.62  5020.7  563.77
  5020.9  563.27  5024.4  563.27  5024.7  563.77  5036.7  564.09  5045.0  565.39
  5067.4  565.95  5089.8  567.70  5112.1  568.51  5148.5  570.86  5201.6  575.68
  5232.3  578.86  5254.7  580.50  5277.0  583.37  5299.4  585.47  5335.7  586.30
#Mann=5,-1,0
  4745.4    0.07       0  4753.4    0.12       0  4978.6    0.07       0
  5020.7    0.05       0  5024.7    0.07       0
Bank Sta=5020.7,5024.7
Exp/Cntr=0.3,0.1

Type RM Length L Ch R = 1,970,163,163,163
BEGIN DESCRIPTION:
LONG BRANCH TRIBUTARY 1A 2.0
END DESCRIPTION:
XS GIS Cut Line= 3
      2337775.03     13782625.00      2337525.00     13782625.00
      2337275.03     13782924.96
#Sta/Elev= 30
  4750.0  582.31  4810.0  576.22  4840.0  572.08  4870.0  568.84  4940.0  563.15
  4970.0  559.81  5003.3  557.56  5007.2  556.14  5021.5  558.76  5028.0  557.94
  5035.8  558.47  5042.3  557.03  5050.1  557.76  5057.2  557.13  5064.5  556.18
  5071.0  557.28  5076.1  555.70  5076.4  555.20  5079.9  555.20  5080.1  555.70
  5085.3  558.11  5091.8  557.68  5099.6  558.29  5128.3  558.48  5163.4  560.96
  5212.9  563.12  5241.5  565.17  5262.3  567.66  5340.4  573.09  5390.5  574.89
#Mann=4,-1,0
  4750.0    0.12       0  5057.2    0.07       0  5076.1    0.05       0
  5080.1    0.07       0
Bank Sta=5076.1,5080.1
Exp/Cntr=0.3,0.1

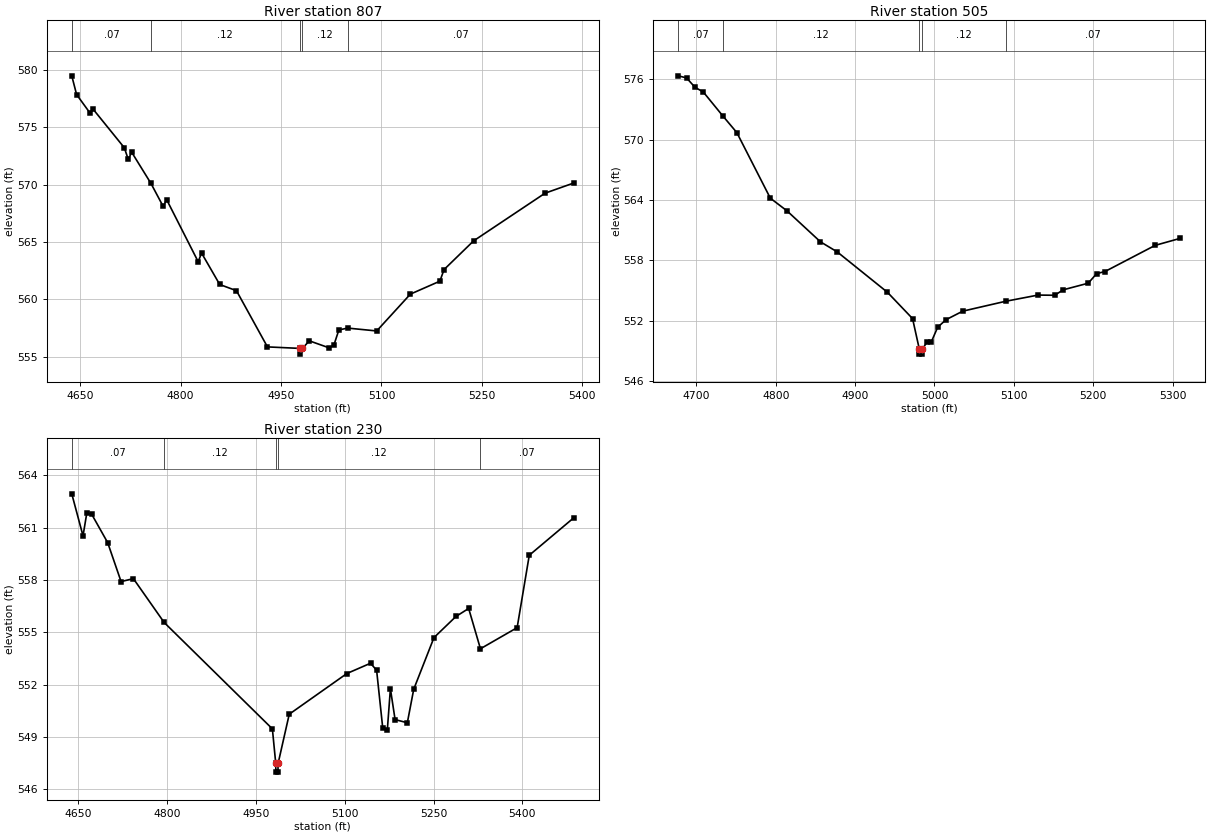
Type RM Length L Ch R = 1,807,302,302,302
BEGIN DESCRIPTION:
A19727
END DESCRIPTION:
XS GIS Cut Line= 3
      2337792.09     13782414.04      2337451.06     13782479.00
      2337215.57     13782805.84
#Sta/Elev= 30
  4637.4  579.48  4644.6  577.85  4664.6  576.24  4669.6  576.55  4715.9  573.21
  4721.8  572.19  4726.9  572.82  4755.6  570.11  4774.0  568.09  4779.1  568.69
  4826.2  563.28  4831.3  564.03  4858.4  561.29  4883.4  560.75  4929.7  555.85
  4978.0  555.72  4978.3  555.22  4982.0  555.72  4992.2  556.38  5021.7  555.77
  5028.9  556.00  5036.4  557.33  5049.6  557.49  5092.9  557.24  5143.2  560.45
  5187.3  561.58  5193.5  562.59  5237.6  565.09  5344.4  569.25  5387.4  570.14
#Mann=5,-1,0
  4637.4    0.07       0  4755.6    0.12       0  4978.0    0.05       0
  4982.0    0.12       0  5049.6    0.07       0
Bank Sta=4978,4982
Exp/Cntr=0.3,0.1

Type RM Length L Ch R = 1,505,275,275,275
BEGIN DESCRIPTION:
LONG BRANCH TRIBUTARY 1A 1.0
END DESCRIPTION:
XS GIS Cut Line= 3
      2337625.01     13782125.00      2337325.00     13782225.00
      2337224.99     13782525.04
#Sta/Elev= 30
  4677.2  576.35  4687.7  576.14  4698.3  575.21  4708.8  574.74  4733.1  572.39
  4751.0  570.71  4793.2  564.19  4814.2  562.93  4856.4  559.85  4877.5  558.85
  4940.7  554.84  4972.4  552.22  4980.9  549.19  4981.1  548.69  4984.6  548.69
  4984.9  549.19  4990.8  549.92  4996.1  549.92  5004.0  551.36  5014.5  552.11
  5035.6  552.96  5089.5  553.94  5130.5  554.56  5151.5  554.54  5162.1  555.08
  5193.7  555.74  5204.3  556.69  5214.8  556.90  5278.0  559.50  5309.7  560.20
#Mann=5,-1,0
  4677.2    0.07       0  4733.1    0.12       0  4980.9    0.05       0
  4984.9    0.12       0  5089.5    0.07       0
Bank Sta=4980.9,4984.9
Exp/Cntr=0.3,0.1

Type RM Length L Ch R = 1,230,0,0,0
BEGIN DESCRIPTION:
A19726
END DESCRIPTION:
XS GIS Cut Line= 4
      2337412.48     13781896.34      2337101.86     13782137.93
      2337170.89     13782385.61      2337213.53     13782578.53
#Sta/Elev= 30
  4638.7  562.93  4657.7  560.52  4664.1  561.83  4672.2  561.77  4699.4  560.13
  4722.0  557.90  4742.8  558.07  4794.7  555.56  4977.6  549.46  4983.3  547.48
  4983.5  546.98  4987.0  546.98  4987.3  547.48  5006.1  550.30  5103.4  552.63
  5143.4  553.22  5153.7  552.82  5164.1  549.49  5171.8  549.40  5177.0  551.76
  5184.9  549.99  5205.6  549.81  5216.4  551.73  5250.6  554.69  5287.7  555.90
  5309.2  556.36  5329.1  554.05  5391.1  555.26  5411.6  559.41  5486.9  561.56
#Mann=5,-1,0
  4638.7    0.07       0  4794.7    0.12       0  4983.3    0.05       0
  4987.3    0.12       0  5329.1    0.07       0
Bank Sta=4983.3,4987.3
Exp/Cntr=0.3,0.1

Chan Stop Cuts=-1