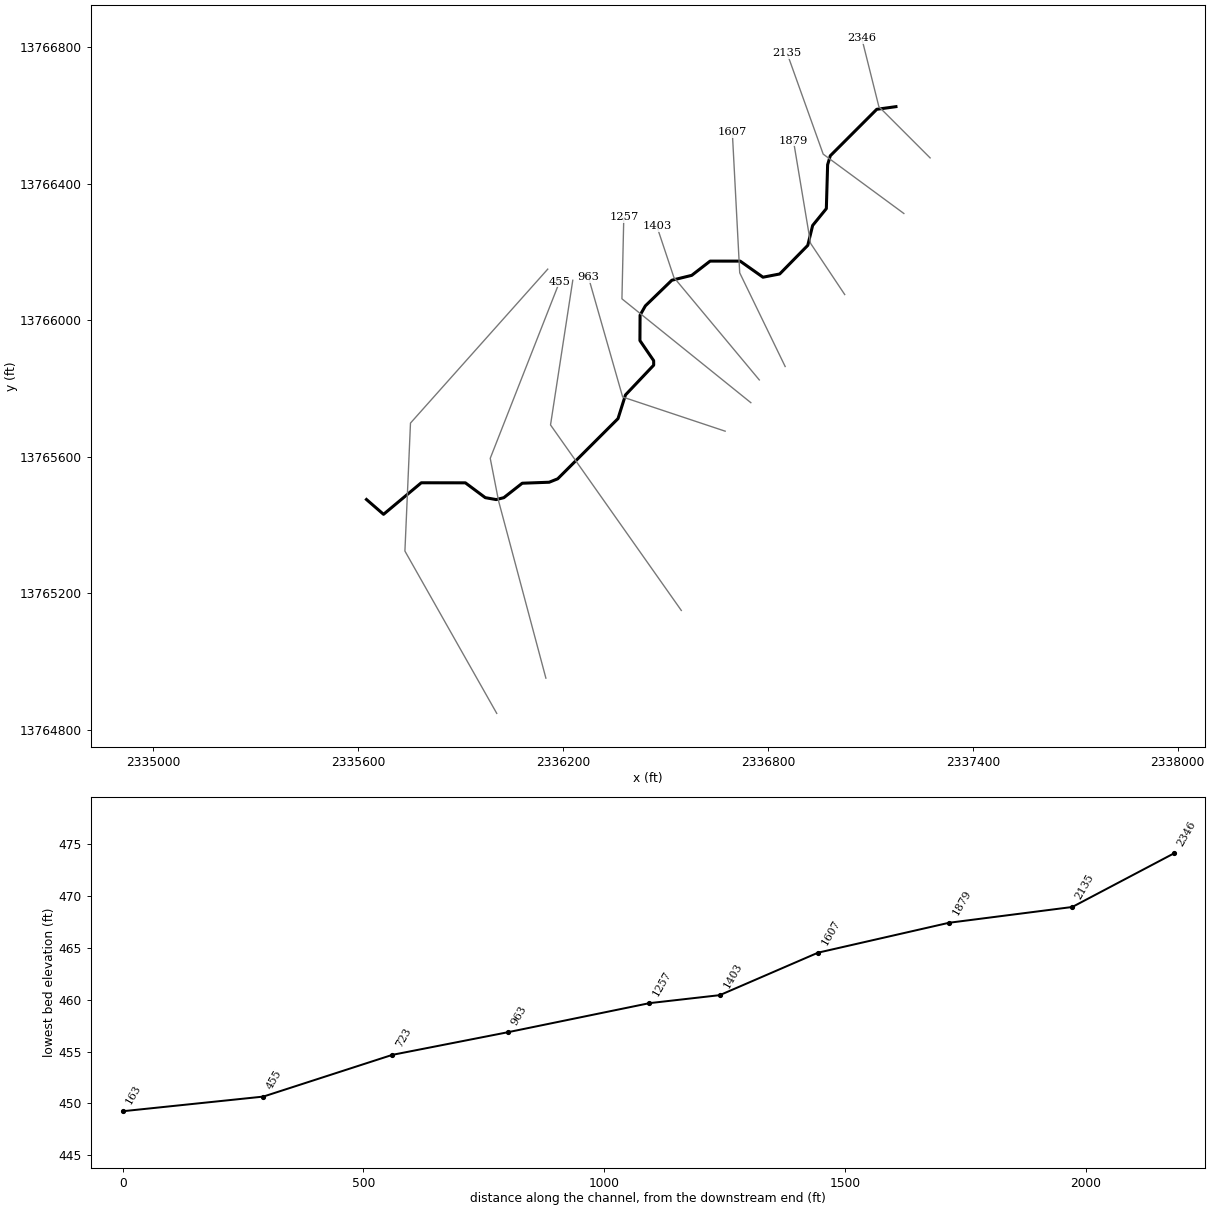
--- LONG BRANCH TRIBUTARY 1B 2.prj (project) ---

Proj Title=LONG BRANCH TRIBUTARY 1B 2 Base Level Engineering
Current Plan=p01
Default Exp/Contr=0.3,0.1
English Units
Geom File=g01
Flow File=f01
Plan File=p01
BEGIN DESCRIPTION:
LONG BRANCH TRIBUTARY 1B 2
END DESCRIPTION:

--- LONG BRANCH TRIBUTARY 1B 2.p01 (plan) ---

Plan Title=Multiple Run
Short Identifier=Multiple
Geom File=g01
Flow File=f01
Subcritical Flow
K Sum by GR= 0
Std Step Tol= 0.01
Critical Tol= 0.01
Num of Std Step Trials= 20
Max Error Tol= 0.3
Flow Tol Ratio= 0.001
Split Flow NTrial= 30
Split Flow Tol= 0.02
Split Flow Ratio= 0.02
Log Output Level= 0
Friction Slope Method= 1
Unsteady Friction Slope Method= 2
Unsteady Bridges Friction Slope Method= 1
Parabolic Critical Depth
Global Vel Dist=  1 , 1 , 1
Global Log Level= 0
CheckData=True
Encroach Param= -1, 0, 0, 0
BEGIN DESCRIPTION:
Multiple Run
END DESCRIPTION:

--- LONG BRANCH TRIBUTARY 1B 2.f01 (steady flow) ---

Flow Title=Multiple
Number of Profiles=7
Profile Names=10-year,25-year,50-year,1pct_min,100-year,1pct_plu,500-year
River Rch & RM= LONG BRANCH TRIB,Reach-1,2346
     223     339     438     276     550    1097     856
Boundary for River Rch & Prof#=LONG BRANCH TRIB,Reach-1,1
Up Type=0
Dn Type=3
Dn Slope=0.005
Boundary for River Rch & Prof#=LONG BRANCH TRIB,Reach-1,2
Up Type=0
Dn Type=3
Dn Slope=0.005
Boundary for River Rch & Prof#=LONG BRANCH TRIB,Reach-1,3
Up Type=0
Dn Type=3
Dn Slope=0.005
Boundary for River Rch & Prof#=LONG BRANCH TRIB,Reach-1,4
Up Type=0
Dn Type=3
Dn Slope=0.005
Boundary for River Rch & Prof#=LONG BRANCH TRIB,Reach-1,5
Up Type=0
Dn Type=3
Dn Slope=0.005
Boundary for River Rch & Prof#=LONG BRANCH TRIB,Reach-1,6
Up Type=0
Dn Type=3
Dn Slope=0.005
Boundary for River Rch & Prof#=LONG BRANCH TRIB,Reach-1,7
Up Type=0
Dn Type=3
Dn Slope=0.005

--- LONG BRANCH TRIBUTARY 1B 2.g01 (geometry) ---

Geom Title=Existing Conditions

River Reach=LONG BRANCH TRIB,Reach-1
Reach XY= 30
      2337175.00     13766625.00      2337118.79     13766617.24
      2336982.81     13766481.19      2336974.98     13766455.01
      2336971.24     13766326.56      2336931.14     13766277.17
      2336916.87     13766218.92      2336834.71     13766135.18
      2336785.71     13766125.72      2336719.03     13766172.81
      2336630.97     13766172.86      2336577.17     13766131.15
      2336518.92     13766116.87      2336441.39     13766041.79
      2336425.94     13766014.52      2336425.52     13765940.22
      2336465.70     13765881.53      2336465.85     13765868.27
      2336383.20     13765781.05      2336361.37     13765711.79
      2336184.79     13765535.52      2336159.78     13765525.52
      2336080.97     13765522.62      2336027.18     13765480.37
      2336004.82     13765474.72      2335972.82     13765480.38
      2335914.50     13765523.77      2335785.44     13765523.95
      2335674.99     13765431.59      2335625.00     13765475.00

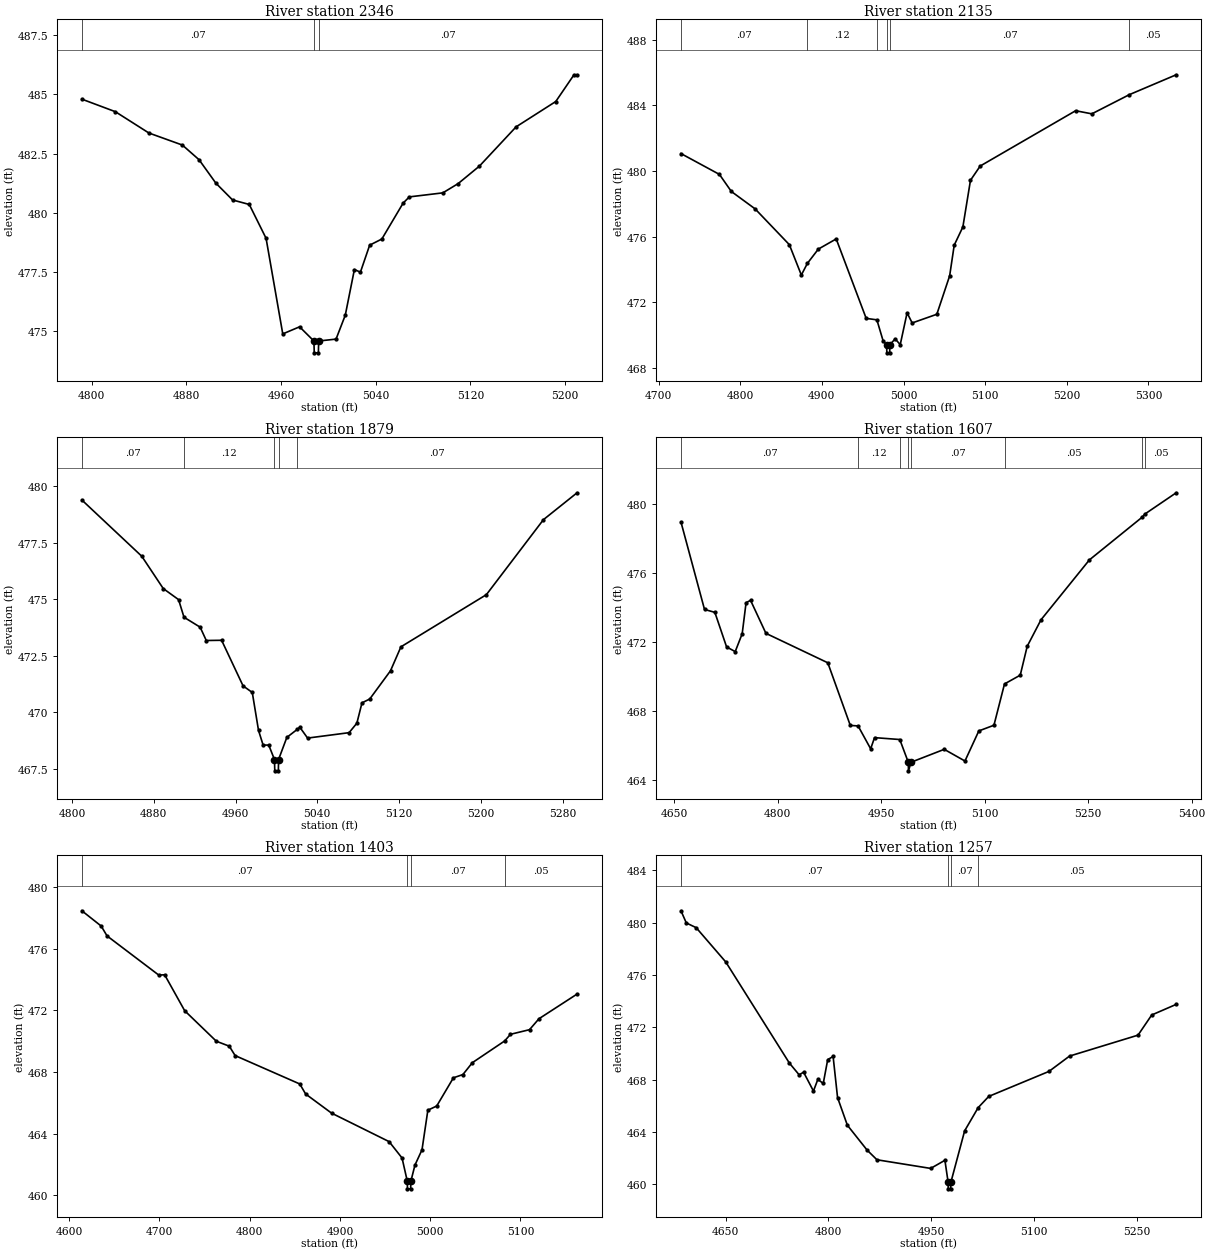
Type RM Length L Ch R = 1,2346,211,211,211
BEGIN DESCRIPTION:
LONG BRANCH TRIBUTARY 1B 2 4.0
END DESCRIPTION:
XS GIS Cut Line= 3
      2337275.01     13766474.99      2337125.00     13766625.00
      2337075.00     13766825.00
#Sta/Elev= 30
  4791.8  484.80  4820.1  484.27  4848.4  483.37  4876.7  482.86  4890.8  482.24
  4905.0  481.25  4919.1  480.54  4933.2  480.35  4947.4  478.92  4961.5  474.88
  4975.7  475.18  4987.8  474.58  4988.1  474.08  4991.6  474.08  4991.8  474.58
  5006.5  474.66  5014.3  475.67  5022.0  477.60  5027.1  477.49  5034.9  478.63
  5045.2  478.89  5063.2  480.41  5068.4  480.67  5096.7  480.84  5109.6  481.23
  5127.6  481.97  5158.6  483.63  5192.1  484.70  5207.5  485.83  5210.1  485.83
#Mann=3,-1,0
  4791.8    0.07       0  4987.8    0.05       0  4991.8    0.07       0
Bank Sta=4987.8,4991.8
Exp/Cntr=0.3,0.1

Type RM Length L Ch R = 1,2135,256,256,256
BEGIN DESCRIPTION:
A19741
END DESCRIPTION:
XS GIS Cut Line= 3
      2337198.16     13766312.29      2336962.00     13766486.02
      2336856.48     13766780.93
#Sta/Elev= 30
  4727.5  481.06  4774.6  479.79  4789.2  478.75  4818.3  477.69  4860.2  475.51
  4874.9  473.66  4882.3  474.37  4895.7  475.24  4917.6  475.86  4954.3  471.02
  4967.4  470.93  4975.1  469.64  4979.3  469.42  4979.6  468.92  4983.1  468.92
  4983.3  469.42  4989.8  469.77  4996.0  469.42  5004.4  471.36  5010.6  470.74
  5040.8  471.27  5056.5  473.61  5062.1  475.48  5072.7  476.59  5082.0  479.43
  5093.9  480.30  5210.8  483.67  5230.6  483.48  5276.6  484.65  5333.9  485.86
#Mann=6,-1,0
  4727.5    0.07       0  4882.3    0.12       0  4967.4    0.07       0
  4979.3    0.05       0  4983.3    0.07       0  5276.6    0.05       0
Bank Sta=4979.3,4983.3
Exp/Cntr=0.3,0.1

Type RM Length L Ch R = 1,1879,272,272,272
BEGIN DESCRIPTION:
LONG BRANCH TRIBUTARY 1B 2 3.0
END DESCRIPTION:
XS GIS Cut Line= 3
      2337024.99     13766075.01      2336925.00     13766225.00
      2336875.00     13766525.00
#Sta/Elev= 30
  4809.7  479.39  4868.3  476.90  4889.3  475.47  4904.3  474.98  4909.6  474.20
  4925.4  473.76  4931.4  473.17  4946.4  473.18  4967.4  471.16  4976.4  470.87
  4982.5  469.19  4987.0  468.54  4992.5  468.54  4998.1  467.90  4998.4  467.40
  5001.9  467.40  5002.1  467.90  5010.2  468.88  5020.5  469.24  5022.9  469.33
  5030.5  468.85  5071.1  469.09  5078.7  469.51  5083.7  470.41  5091.3  470.58
  5111.6  471.83  5121.8  472.89  5205.4  475.20  5261.2  478.52  5294.1  479.71
#Mann=5,-1,0
  4809.7    0.07       0  4909.6    0.12       0  4998.1    0.05       0
  5002.1    0.12       0  5020.5    0.07       0
Bank Sta=4998.1,5002.1
Exp/Cntr=0.3,0.1

Type RM Length L Ch R = 1,1607,204,204,204
BEGIN DESCRIPTION:
A19740
END DESCRIPTION:
XS GIS Cut Line= 3
      2336850.69     13765864.28      2336717.65     13766138.50
      2336695.97     13766550.54
#Sta/Elev= 30
  4660.1  478.98  4694.2  473.90  4709.2  473.73  4726.2  471.72  4738.7  471.45
  4748.8  472.49  4754.4  474.29  4760.9  474.43  4783.2  472.51  4872.8  470.80
  4905.4  467.16  4916.7  467.13  4934.9  465.80  4940.5  466.45  4977.1  466.34
  4989.4  465.02  4989.7  464.52  4993.4  465.02  5041.5  465.77  5071.5  465.09
  5091.6  466.84  5113.5  467.17  5128.8  469.57  5151.6  470.08  5161.7  471.76
  5181.7  473.30  5251.8  476.78  5328.5  479.27  5332.0  479.44  5377.5  480.68
#Mann=8,-1,0
  4660.1    0.07       0  4916.7    0.12       0  4977.1    0.07       0
  4989.4    0.05       0  4993.4    0.07       0  5128.8    0.05       0
  5328.5    0.07       0  5332.0    0.05       0
Bank Sta=4989.4,4993.4
Exp/Cntr=0.3,0.1

Type RM Length L Ch R = 1,1403,146,146,146
BEGIN DESCRIPTION:
LONG BRANCH TRIBUTARY 1B 2 2.0
END DESCRIPTION:
XS GIS Cut Line= 3
      2336774.97     13765825.03      2336525.00     13766125.00
      2336474.99     13766275.02
#Sta/Elev= 30
  4614.1  478.46  4635.5  477.47  4642.0  476.83  4699.3  474.29  4705.8  474.31
  4728.0  471.98  4763.1  470.00  4777.4  469.68  4783.9  469.07  4855.5  467.23
  4862.0  466.58  4890.7  465.34  4954.5  463.49  4968.8  462.43  4974.6  460.93
  4974.8  460.43  4978.3  460.43  4978.6  460.93  4983.1  461.97  4990.9  462.96
  4997.4  465.53  5007.2  465.80  5025.7  467.63  5036.2  467.84  5046.7  468.61
  5082.5  470.02  5088.9  470.45  5110.0  470.75  5120.5  471.46  5162.7  473.06
#Mann=4,-1,0
  4614.1    0.07       0  4974.6    0.05       0  4978.6    0.07       0
  5082.5    0.05       0
Bank Sta=4974.6,4978.6
Exp/Cntr=0.3,0.1

Type RM Length L Ch R = 1,1257,294,294,294
BEGIN DESCRIPTION:
A19739
END DESCRIPTION:
XS GIS Cut Line= 3
      2336750.23     13765758.41      2336372.85     13766062.48
      2336378.26     13766300.69
#Sta/Elev= 30
  4584.8  480.90  4592.6  479.97  4607.0  479.61  4650.2  476.99  4743.0  469.27
  4757.3  468.37  4763.8  468.57  4778.2  467.13  4784.6  468.02  4792.5  467.71
  4799.0  469.53  4806.9  469.77  4813.4  466.63  4827.7  464.52  4856.5  462.62
  4870.9  461.88  4949.3  461.22  4970.1  461.84  4974.8  460.16  4975.0  459.66
  4978.5  459.66  4978.8  460.16  4998.9  464.09  5018.6  465.86  5034.1  466.72
  5122.0  468.63  5152.0  469.80  5252.0  471.40  5272.0  472.94  5307.7  473.75
#Mann=4,-1,0
  4584.8    0.07       0  4974.8    0.05       0  4978.8    0.07       0
  5018.6    0.05       0
Bank Sta=4974.8,4978.8
Exp/Cntr=0.3,0.1

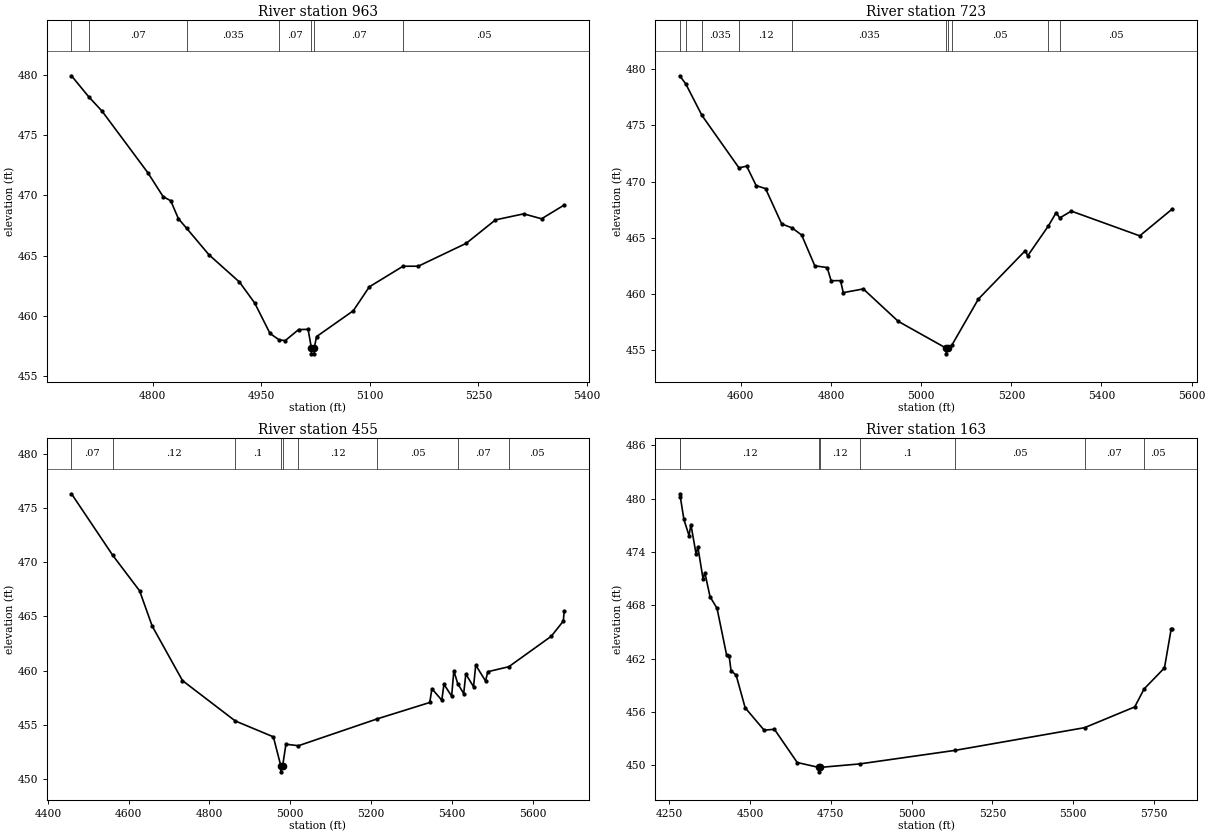
Type RM Length L Ch R = 1,963,240,240,240
BEGIN DESCRIPTION:
LONG BRANCH TRIBUTARY 1B 2 1.0
END DESCRIPTION:
XS GIS Cut Line= 3
      2336675.02     13765674.99      2336375.00     13765775.00
      2336274.99     13766125.04
#Sta/Elev= 30
  4688.1  479.90  4711.6  478.18  4730.3  476.97  4793.5  471.87  4814.6  469.89
  4825.2  469.54  4835.7  468.06  4847.0  467.27  4877.9  465.07  4920.0  462.81
  4941.1  461.07  4962.2  458.55  4975.0  458.01  4983.3  457.96  5001.7  458.87
  5014.8  458.89  5019.3  457.36  5019.5  456.86  5023.0  456.86  5023.3  457.36
  5026.5  458.29  5077.2  460.43  5099.3  462.41  5145.9  464.12  5166.9  464.12
  5233.2  466.02  5273.5  467.96  5312.5  468.46  5337.2  468.05  5368.4  469.19
#Mann=7,-1,0
  4688.1   0.035       0  4711.6    0.07       0  4847.0   0.035       0
  4975.0    0.07       0  5019.3    0.05       0  5023.3    0.07       0
  5145.9    0.05       0
Bank Sta=5019.3,5023.3
Exp/Cntr=0.3,0.1

Type RM Length L Ch R = 1,723,268,268,268
BEGIN DESCRIPTION:
A19738
END DESCRIPTION:
XS GIS Cut Line= 3
      2336546.63     13765150.23      2336163.80     13765693.25
      2336228.95     13766116.76
#Sta/Elev= 30
  4464.5  479.40  4477.9  478.67  4513.8  475.87  4595.9  471.21  4612.9  471.37
  4633.9  469.64  4654.8  469.37  4690.6  466.23  4713.9  465.87  4734.9  465.24
  4764.0  462.51  4791.5  462.35  4800.2  461.18  4821.1  461.19  4827.2  460.12
  4871.6  460.45  4949.1  457.57  5055.6  455.18  5055.9  454.68  5059.6  455.18
  5067.9  455.44  5126.9  459.55  5231.1  463.86  5236.2  463.39  5282.0  466.04
  5299.4  467.23  5307.4  466.76  5333.0  467.37  5484.8  465.17  5557.4  467.57
#Mann=10,-1,0
  4464.5    0.07       0  4477.9    0.12       0  4513.8   0.035       0
  4595.9    0.12       0  4713.9   0.035       0  5055.6   0.035       0
  5059.6   0.035       0  5067.9    0.05       0  5282.0    0.07       0
  5307.4    0.05       0
Bank Sta=5055.6,5059.6
Exp/Cntr=0.3,0.1

Type RM Length L Ch R = 1,455,292,292,292
BEGIN DESCRIPTION:
A19737
END DESCRIPTION:
XS GIS Cut Line= 4
      2336150.23     13764952.03      2336011.76     13765470.62
      2335987.32     13765595.51      2336190.46     13766112.84
#Sta/Elev= 30
  4458.5  476.32  4560.5  470.65  4627.2  467.36  4658.3  464.11  4733.3  459.08
  4863.8  455.36  4958.3  453.89  4977.1  451.16  4977.3  450.66  4981.1  451.16
  4989.4  453.21  5020.4  453.07  5215.6  455.55  5345.5  457.06  5350.8  458.33
  5375.3  457.27  5380.6  458.74  5399.7  457.65  5405.1  459.99  5414.7  458.80
  5429.5  457.88  5434.8  459.69  5453.9  458.51  5459.3  460.51  5483.7  459.04
  5489.1  459.90  5541.2  460.36  5646.3  463.17  5676.1  464.57  5678.3  465.46
#Mann=9,-1,0
  4458.5    0.07       0  4560.5    0.12       0  4863.8     0.1       0
  4977.1    0.05       0  4981.1     0.1       0  5020.4    0.12       0
  5215.6    0.05       0  5414.7    0.07       0  5541.2    0.05       0
Bank Sta=4977.1,4981.1
Exp/Cntr=0.3,0.1

Type RM Length L Ch R = 1,163,0,0,0
BEGIN DESCRIPTION:
A19736
END DESCRIPTION:
XS GIS Cut Line= 4
      2336006.34     13764848.88      2335737.55     13765324.01
      2335753.84     13765698.68      2336155.64     13766149.35
#Sta/Elev= 30
  4282.4  480.55  4284.0  480.23  4295.2  477.66  4311.1  475.84  4316.9  477.09
  4332.8  473.79  4338.5  474.55  4354.4  470.98  4360.2  471.64  4376.1  468.96
  4397.7  467.66  4427.3  462.41  4435.2  462.30  4441.0  460.65  4456.9  460.13
  4484.8  456.46  4543.5  453.94  4575.3  454.04  4645.9  450.30  4712.5  449.75
  4712.8  449.25  4716.5  449.75  4838.9  450.14  5134.8  451.67  5535.1  454.22
  5690.4  456.56  5719.3  458.58  5782.4  460.95  5802.9  465.28  5807.1  465.28
#Mann=8,-1,0
  4282.4    0.07       0  4284.0    0.12       0  4712.5    0.05       0
  4716.5    0.12       0  4838.9     0.1       0  5134.8    0.05       0
  5535.1    0.07       0  5719.3    0.05       0
Bank Sta=4712.5,4716.5
Exp/Cntr=0.3,0.1

Chan Stop Cuts=-1