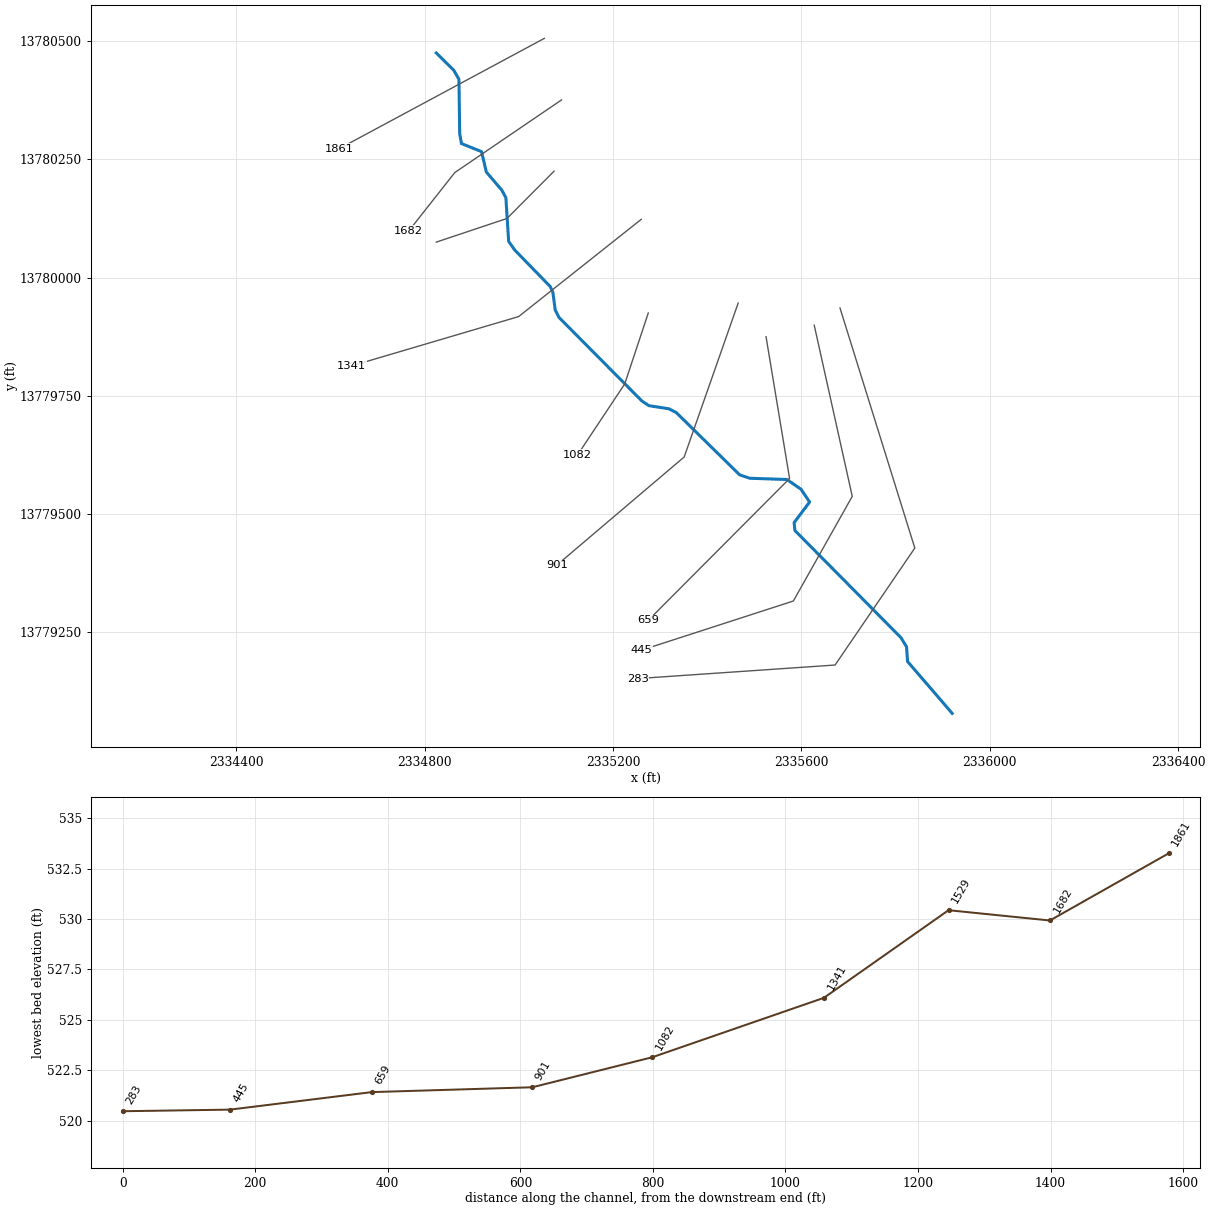
--- LONG BRANCH TRIBUTARY 1B.prj (project) ---

Proj Title=LONG BRANCH TRIBUTARY 1B Base Level Engineering
Current Plan=p01
Default Exp/Contr=0.3,0.1
English Units
Geom File=g01
Flow File=f01
Plan File=p01
BEGIN DESCRIPTION:
LONG BRANCH TRIBUTARY 1B
END DESCRIPTION:

--- LONG BRANCH TRIBUTARY 1B.p01 (plan) ---

Plan Title=Multiple Run
Short Identifier=Multiple
Geom File=g01
Flow File=f01
Subcritical Flow
K Sum by GR= 0
Std Step Tol= 0.01
Critical Tol= 0.01
Num of Std Step Trials= 20
Max Error Tol= 0.3
Flow Tol Ratio= 0.001
Split Flow NTrial= 30
Split Flow Tol= 0.02
Split Flow Ratio= 0.02
Log Output Level= 0
Friction Slope Method= 1
Unsteady Friction Slope Method= 2
Unsteady Bridges Friction Slope Method= 1
Parabolic Critical Depth
Global Vel Dist=  1 , 1 , 1
Global Log Level= 0
CheckData=True
Encroach Param= -1, 0, 0, 0
BEGIN DESCRIPTION:
Multiple Run
END DESCRIPTION:

--- LONG BRANCH TRIBUTARY 1B.f01 (steady flow) ---

Flow Title=Multiple
Number of Profiles=7
Profile Names=10-year,25-year,50-year,1pct_min,100-year,1pct_plu,500-year
River Rch & RM= LONG BRANCH TRIB,Reach-1,1861
     240     368     478     302     604    1204     950
Boundary for River Rch & Prof#=LONG BRANCH TRIB,Reach-1,1
Up Type=0
Dn Type=3
Dn Slope=0.005
Boundary for River Rch & Prof#=LONG BRANCH TRIB,Reach-1,2
Up Type=0
Dn Type=3
Dn Slope=0.005
Boundary for River Rch & Prof#=LONG BRANCH TRIB,Reach-1,3
Up Type=0
Dn Type=3
Dn Slope=0.005
Boundary for River Rch & Prof#=LONG BRANCH TRIB,Reach-1,4
Up Type=0
Dn Type=3
Dn Slope=0.005
Boundary for River Rch & Prof#=LONG BRANCH TRIB,Reach-1,5
Up Type=0
Dn Type=3
Dn Slope=0.005
Boundary for River Rch & Prof#=LONG BRANCH TRIB,Reach-1,6
Up Type=0
Dn Type=3
Dn Slope=0.005
Boundary for River Rch & Prof#=LONG BRANCH TRIB,Reach-1,7
Up Type=0
Dn Type=3
Dn Slope=0.005

--- LONG BRANCH TRIBUTARY 1B.g01 (geometry) ---

Geom Title=Existing Conditions

River Reach=LONG BRANCH TRIB,Reach-1
Reach XY= 30
      2334825.00     13780475.00      2334862.08     13780438.50
      2334873.09     13780419.20      2334874.64     13780304.63
      2334878.41     13780283.44      2334921.10     13780266.35
      2334931.21     13780223.13      2334964.18     13780184.70
      2334972.67     13780169.06      2334978.62     13780076.50
      2334991.49     13780058.26      2335066.82     13779981.04
      2335072.46     13779968.95      2335077.53     13779931.05
      2335085.78     13779915.32      2335261.79     13779738.63
      2335276.65     13779728.98      2335318.95     13779722.46
      2335334.68     13779714.22      2335468.83     13779582.86
      2335490.23     13779575.53      2335569.50     13779572.85
      2335599.41     13779552.12      2335617.54     13779525.24
      2335584.62     13779481.69      2335586.25     13779465.01
      2335811.53     13779238.27      2335823.32     13779218.86
      2335825.43     13779187.98      2335920.30     13779078.20

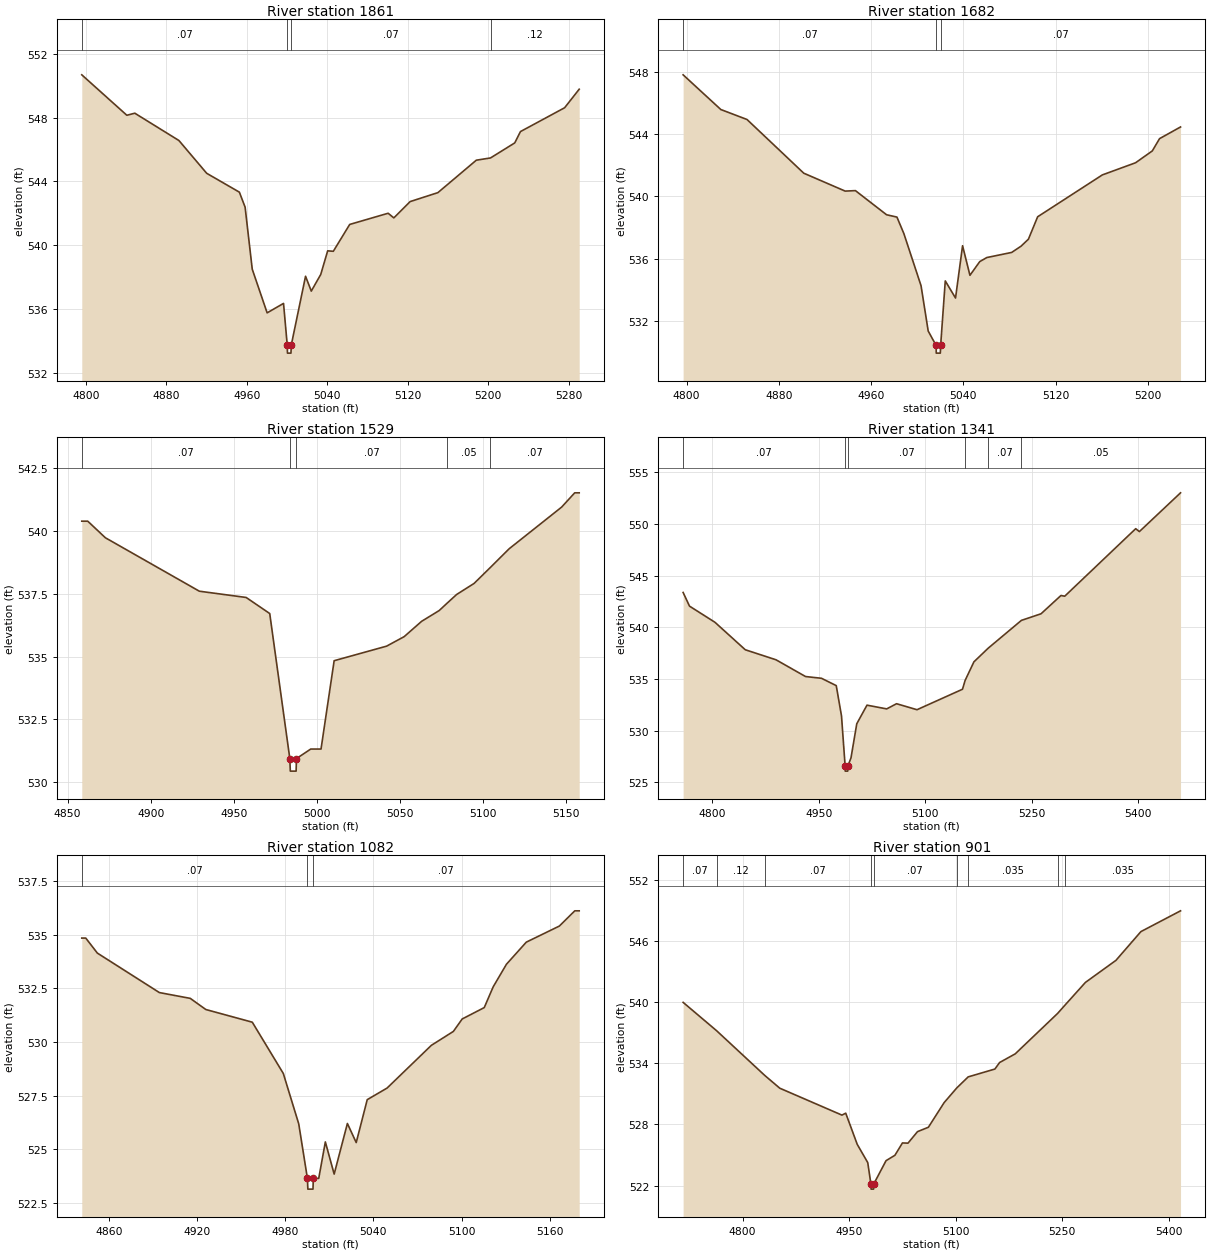
Type RM Length L Ch R = 1,1861,179,179,179
BEGIN DESCRIPTION:
A19734
END DESCRIPTION:
XS GIS Cut Line= 2
      2335054.45     13780506.01      2334618.47     13780272.45
#Sta/Elev= 30
  4796.0  550.67  4840.8  548.14  4848.7  548.27  4892.6  546.56  4920.2  544.51
  4952.7  543.33  4958.4  542.39  4965.5  538.51  4980.3  535.78  4996.6  536.37
  5000.3  533.76  5000.5  533.26  5004.0  533.26  5004.3  533.76  5018.5  538.07
  5024.2  537.14  5033.6  538.18  5040.5  539.66  5046.1  539.63  5062.4  541.31
  5100.6  542.01  5106.3  541.72  5122.5  542.74  5150.1  543.30  5188.3  545.33
  5202.4  545.47  5226.5  546.41  5232.2  547.12  5276.1  548.61  5290.6  549.77
#Mann=4,-1,0
  4796.0    0.07       0  5000.3    0.05       0  5004.3    0.07       0
  5202.4    0.12       0
Bank Sta=5000.3,5004.3
Exp/Cntr=0.3,0.1

Type RM Length L Ch R = 1,1682,153,153,153
BEGIN DESCRIPTION:
A19733
END DESCRIPTION:
XS GIS Cut Line= 3
      2335090.85     13780375.77      2334864.31     13780222.14
      2334766.50     13780098.59
#Sta/Elev= 30
  4797.0  547.81  4829.7  545.58  4852.4  544.94  4901.6  541.49  4937.5  540.34
  4946.4  540.37  4973.4  538.82  4982.4  538.67  4988.4  537.61  5003.3  534.26
  5009.5  531.35  5016.3  530.43  5016.5  529.93  5020.0  529.93  5020.3  530.43
  5024.3  534.57  5033.2  533.47  5039.3  536.83  5045.7  534.93  5054.2  535.81
  5060.3  536.07  5081.9  536.40  5090.0  536.80  5096.4  537.25  5104.4  538.69
  5160.5  541.38  5189.3  542.16  5203.8  542.92  5210.1  543.71  5228.3  544.46
#Mann=3,-1,0
  4797.0    0.07       0  5016.3    0.05       0  5020.3    0.07       0
Bank Sta=5016.3,5020.3
Exp/Cntr=0.3,0.1

Type RM Length L Ch R = 1,1529,188,188,188
BEGIN DESCRIPTION:
LONG BRANCH TRIBUTARY 1B 3.0
END DESCRIPTION:
XS GIS Cut Line= 3
      2335075.03     13780225.03      2334975.00     13780125.00
      2334824.98     13780074.99
#Sta/Elev= 26
  4858.5  540.40  4862.1  540.40  4872.7  539.74  4929.3  537.61  4957.5  537.36
  4971.7  536.72  4983.8  530.94  4984.1  530.44  4987.6  530.44  4987.8  530.94
  4996.4  531.32  5000.0  531.32  5002.6  531.32  5010.5  534.84  5042.1  535.42
  5052.7  535.80  5063.2  536.41  5073.8  536.84  5078.5  537.13  5084.3  537.48
  5094.8  537.92  5104.5  538.55  5115.9  539.30  5147.5  540.96  5155.4  541.53
  5158.1  541.53
#Mann=5,-1,0
  4858.5    0.07       0  4983.8    0.05       0  4987.8    0.07       0
  5078.5    0.05       0  5104.5    0.07       0
Bank Sta=4983.8,4987.8
Exp/Cntr=0.3,0.1

Type RM Length L Ch R = 1,1341,259,259,259
BEGIN DESCRIPTION:
A19732
END DESCRIPTION:
XS GIS Cut Line= 3
      2335260.13     13780123.17      2334999.73     13779917.45
      2334645.59     13779813.29
#Sta/Elev= 30
  4758.8  543.37  4767.8  542.05  4803.6  540.49  4846.4  537.83  4889.7  536.86
  4931.3  535.24  4953.8  535.07  4974.6  534.36  4982.0  531.43  4987.1  526.59
  4987.3  526.09  4990.8  526.09  4991.1  526.59  4995.4  527.38  5003.5  530.67
  5017.9  532.47  5045.7  532.11  5059.6  532.61  5088.4  532.03  5152.5  534.01
  5156.2  534.86  5168.6  536.66  5188.7  537.98  5235.5  540.67  5263.2  541.31
  5291.3  543.08  5296.6  543.01  5396.6  549.54  5401.8  549.26  5459.8  553.01
#Mann=6,-1,0
  4758.8    0.07       0  4987.1    0.05       0  4991.1    0.07       0
  5156.2    0.05       0  5188.7    0.07       0  5235.5    0.05       0
Bank Sta=4987.1,4991.1
Exp/Cntr=0.3,0.1

Type RM Length L Ch R = 1,1082,181,181,181
BEGIN DESCRIPTION:
LONG BRANCH TRIBUTARY 1B 2.0
END DESCRIPTION:
XS GIS Cut Line= 3
      2335275.02     13779925.05      2335225.00     13779775.00
      2335125.02     13779625.03
#Sta/Elev= 30
  4841.6  534.84  4844.3  534.84  4852.2  534.14  4894.4  532.30  4915.4  532.03
  4926.0  531.51  4957.6  530.92  4978.7  528.53  4989.2  526.18  4995.1  523.64
  4995.4  523.14  4998.9  523.14  4999.1  523.64  5002.8  523.64  5007.3  525.34
  5013.3  523.84  5022.3  526.20  5028.3  525.31  5035.8  527.31  5049.3  527.85
  5079.4  529.84  5094.4  530.49  5100.4  531.07  5115.4  531.60  5121.5  532.57
  5130.5  533.62  5144.0  534.65  5166.5  535.40  5177.0  536.11  5180.0  536.11
#Mann=3,-1,0
  4841.6    0.07       0  4995.1    0.05       0  4999.1    0.07       0
Bank Sta=4995.1,4999.1
Exp/Cntr=0.3,0.1

Type RM Length L Ch R = 1,901,242,242,242
BEGIN DESCRIPTION:
A19731
END DESCRIPTION:
XS GIS Cut Line= 3
      2335465.89     13779946.13      2335351.29     13779620.57
      2335080.47     13779391.42
#Sta/Elev= 30
  4716.4  539.97  4763.5  537.19  4831.3  532.80  4852.4  531.55  4939.9  528.91
  4945.2  529.10  4961.4  526.04  4976.2  524.25  4980.6  522.15  4980.9  521.65
  4984.4  521.65  4984.6  522.15  5001.9  524.44  5014.4  524.97  5025.0  526.18
  5032.8  526.16  5046.2  527.29  5061.5  527.72  5083.7  530.14  5101.5  531.58
  5117.5  532.66  5155.1  533.43  5161.7  534.07  5183.7  534.92  5243.4  538.89
  5253.2  539.66  5282.5  541.93  5325.4  544.09  5360.5  546.91  5416.3  548.95
#Mann=9,-1,0
  4716.4    0.07       0  4763.5    0.12       0  4831.3    0.07       0
  4980.6    0.05       0  4984.6    0.07       0  5101.5    0.05       0
  5117.5   0.035       0  5243.4    0.07       0  5253.2   0.035       0
Bank Sta=4980.6,4984.6
Exp/Cntr=0.3,0.1

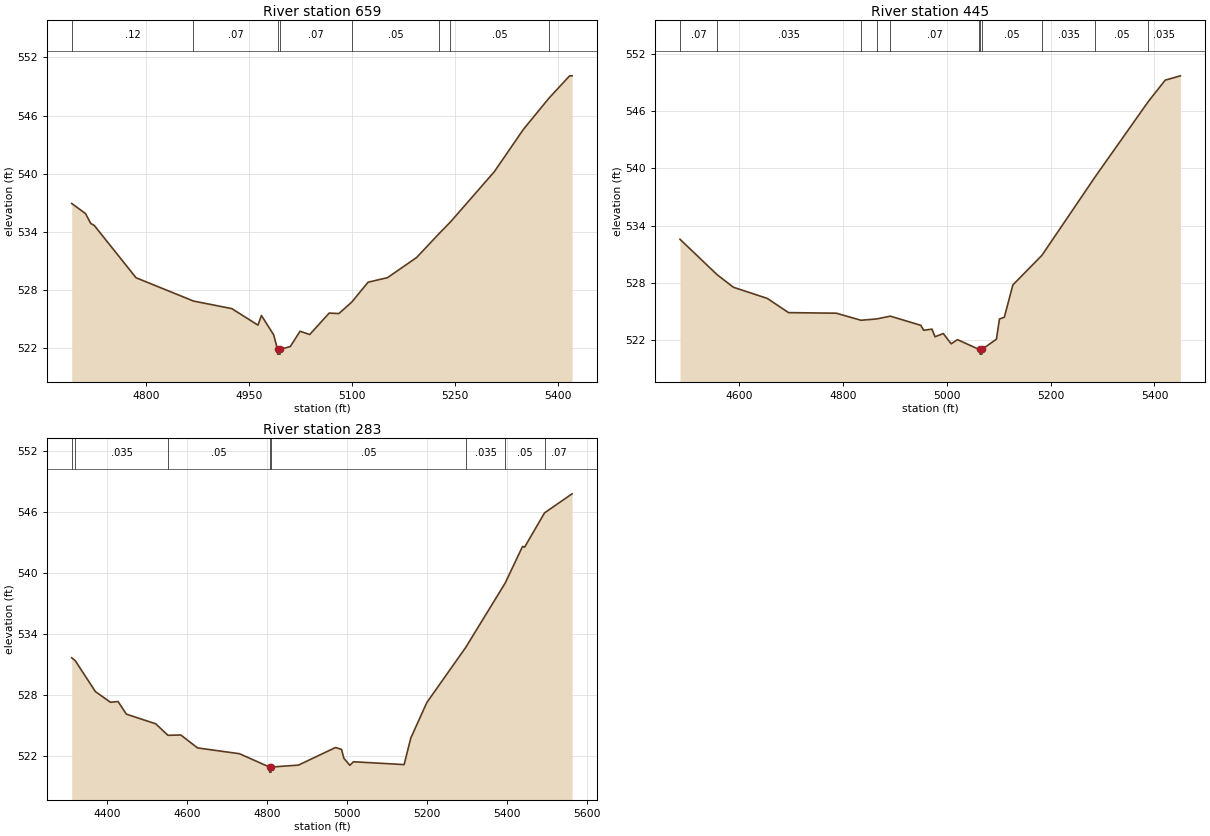
Type RM Length L Ch R = 1,659,214,214,214
BEGIN DESCRIPTION:
LONG BRANCH TRIBUTARY 1B 1.0
END DESCRIPTION:
XS GIS Cut Line= 3
      2335525.01     13779874.95      2335575.00     13779575.00
      2335274.97     13779274.97
#Sta/Elev= 30
  4691.7  536.94  4711.9  535.89  4719.5  534.87  4724.6  534.67  4785.4  529.28
  4869.0  526.88  4924.8  526.10  4962.8  524.40  4967.9  525.39  4985.7  523.40
  4991.3  521.91  4991.5  521.41  4995.0  521.41  4995.3  521.91  5009.9  522.19
  5024.1  523.77  5038.2  523.43  5066.5  525.64  5080.6  525.59  5099.5  526.78
  5123.1  528.82  5151.4  529.29  5193.8  531.37  5226.2  533.81  5242.9  535.02
  5306.9  540.21  5349.3  544.58  5386.3  547.78  5416.5  550.09  5420.1  550.09
#Mann=8,-1,0
  4691.7    0.12       0  4869.0    0.07       0  4991.3    0.05       0
  4995.3    0.07       0  5099.5    0.05       0  5226.2   0.035       0
  5242.9    0.05       0  5386.3   0.035       0
Bank Sta=4991.3,4995.3
Exp/Cntr=0.3,0.1

Type RM Length L Ch R = 1,445,162,162,162
BEGIN DESCRIPTION:
A19735
END DESCRIPTION:
XS GIS Cut Line= 4
      2335627.33     13779899.22      2335708.06     13779537.24
      2335583.06     13779315.89      2335260.13     13779211.71
#Sta/Elev= 30
  4485.6  532.58  4557.1  528.87  4588.5  527.55  4653.9  526.38  4694.8  524.89
  4787.0  524.83  4834.3  524.09  4864.6  524.23  4891.0  524.52  4949.7  523.56
  4955.4  523.04  4971.3  523.16  4977.1  522.36  4993.0  522.70  5008.3  521.62
  5020.4  522.06  5061.2  521.05  5063.8  521.04  5064.0  520.54  5067.5  520.54
  5067.8  521.04  5095.5  522.11  5101.3  524.22  5110.7  524.41  5127.1  527.79
  5183.2  530.90  5285.7  539.12  5388.2  547.02  5420.8  549.26  5450.0  549.71
#Mann=11,-1,0
  4485.6    0.07       0  4557.1   0.035       0  4834.3    0.05       0
  4864.6   0.035       0  4891.0    0.07       0  5061.2    0.05       0
  5063.8    0.05       0  5067.8    0.05       0  5183.2   0.035       0
  5285.7    0.05       0  5388.2   0.035       0
Bank Sta=5063.8,5067.8
Exp/Cntr=0.3,0.1

Type RM Length L Ch R = 1,283,0,0,0
BEGIN DESCRIPTION:
A19730
END DESCRIPTION:
XS GIS Cut Line= 4
      2335682.02     13779935.68      2335840.87     13779427.86
      2335671.60     13779180.47      2335252.32     13779151.82
#Sta/Elev= 30
  4310.6  531.70  4319.5  531.42  4369.9  528.38  4407.6  527.33  4426.6  527.40
  4447.5  526.16  4520.9  525.21  4551.4  524.08  4583.7  524.11  4625.6  522.84
  4730.4  522.27  4805.6  520.96  4805.9  520.46  4809.4  520.46  4809.6  520.96
  4878.0  521.15  4970.8  522.88  4985.7  522.70  4991.8  521.81  5006.7  521.13
  5015.5  521.48  5142.4  521.20  5159.1  523.81  5199.2  527.30  5296.7  532.73
  5395.3  539.05  5438.7  542.65  5443.7  542.57  5493.8  545.95  5562.7  547.82
#Mann=8,-1,0
  4310.6    0.07       0  4319.5   0.035       0  4551.4    0.05       0
  4805.6    0.05       0  4809.6    0.05       0  5296.7   0.035       0
  5395.3    0.05       0  5493.8    0.07       0
Bank Sta=4805.6,4809.6
Exp/Cntr=0.3,0.1

Chan Stop Cuts=-1