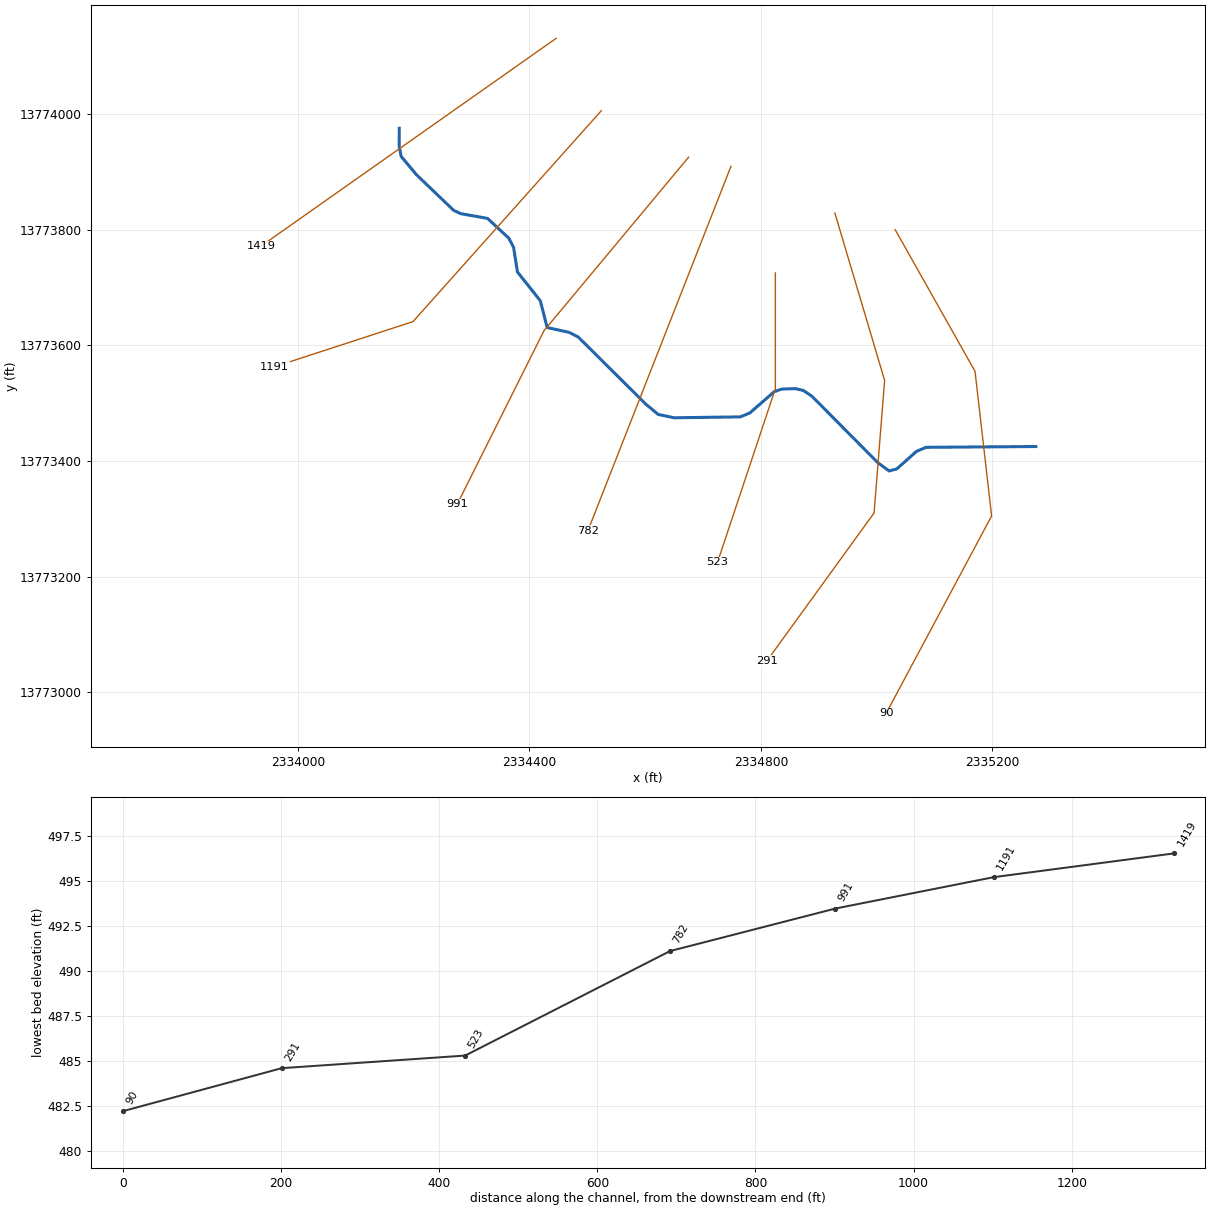
--- LONG BRANCH TRIBUTARY 1C.prj (project) ---

Proj Title=LONG BRANCH TRIBUTARY 1C Base Level Engineering
Current Plan=p01
Default Exp/Contr=0.3,0.1
English Units
Geom File=g01
Flow File=f01
Plan File=p01
BEGIN DESCRIPTION:
LONG BRANCH TRIBUTARY 1C
END DESCRIPTION:

--- LONG BRANCH TRIBUTARY 1C.p01 (plan) ---

Plan Title=Multiple Run
Short Identifier=Multiple
Geom File=g01
Flow File=f01
Subcritical Flow
K Sum by GR= 0
Std Step Tol= 0.01
Critical Tol= 0.01
Num of Std Step Trials= 20
Max Error Tol= 0.3
Flow Tol Ratio= 0.001
Split Flow NTrial= 30
Split Flow Tol= 0.02
Split Flow Ratio= 0.02
Log Output Level= 0
Friction Slope Method= 1
Unsteady Friction Slope Method= 2
Unsteady Bridges Friction Slope Method= 1
Parabolic Critical Depth
Global Vel Dist=  1 , 1 , 1
Global Log Level= 0
CheckData=True
Encroach Param= -1, 0, 0, 0
BEGIN DESCRIPTION:
Multiple Run
END DESCRIPTION:

--- LONG BRANCH TRIBUTARY 1C.f01 (steady flow) ---

Flow Title=Multiple
Number of Profiles=7
Profile Names=10-year,25-year,50-year,1pct_min,100-year,1pct_plu,500-year
River Rch & RM= LONG BRANCH TRIB,Reach-1,1419
     269     413     537     339     677    1351    1065
Boundary for River Rch & Prof#=LONG BRANCH TRIB,Reach-1,1
Up Type=0
Dn Type=3
Dn Slope=0.005
Boundary for River Rch & Prof#=LONG BRANCH TRIB,Reach-1,2
Up Type=0
Dn Type=3
Dn Slope=0.005
Boundary for River Rch & Prof#=LONG BRANCH TRIB,Reach-1,3
Up Type=0
Dn Type=3
Dn Slope=0.005
Boundary for River Rch & Prof#=LONG BRANCH TRIB,Reach-1,4
Up Type=0
Dn Type=3
Dn Slope=0.005
Boundary for River Rch & Prof#=LONG BRANCH TRIB,Reach-1,5
Up Type=0
Dn Type=3
Dn Slope=0.005
Boundary for River Rch & Prof#=LONG BRANCH TRIB,Reach-1,6
Up Type=0
Dn Type=3
Dn Slope=0.005
Boundary for River Rch & Prof#=LONG BRANCH TRIB,Reach-1,7
Up Type=0
Dn Type=3
Dn Slope=0.005

--- LONG BRANCH TRIBUTARY 1C.g01 (geometry) ---

Geom Title=Existing Conditions

River Reach=LONG BRANCH TRIB,Reach-1
Reach XY= 30
      2334175.00     13773975.00      2334174.92     13773943.11
      2334178.27     13773926.34      2334204.65     13773894.78
      2334268.95     13773833.15      2334281.08     13773827.54
      2334327.54     13773819.25      2334364.37     13773785.00
      2334372.57     13773769.14      2334379.19     13773726.74
      2334418.76     13773676.86      2334430.59     13773630.61
      2334468.56     13773622.31      2334484.41     13773614.11
      2334601.47     13773497.86      2334622.55     13773480.45
      2334649.89     13773474.68      2334764.50     13773476.23
      2334781.07     13773483.19      2334822.83     13773519.65
      2334835.71     13773524.28      2334859.66     13773525.05
      2334873.37     13773521.87      2334888.22     13773511.88
      2335001.64     13773397.45      2335021.58     13773382.79
      2335034.84     13773386.33      2335068.81     13773416.53
      2335085.43     13773423.62      2335275.00     13773425.00

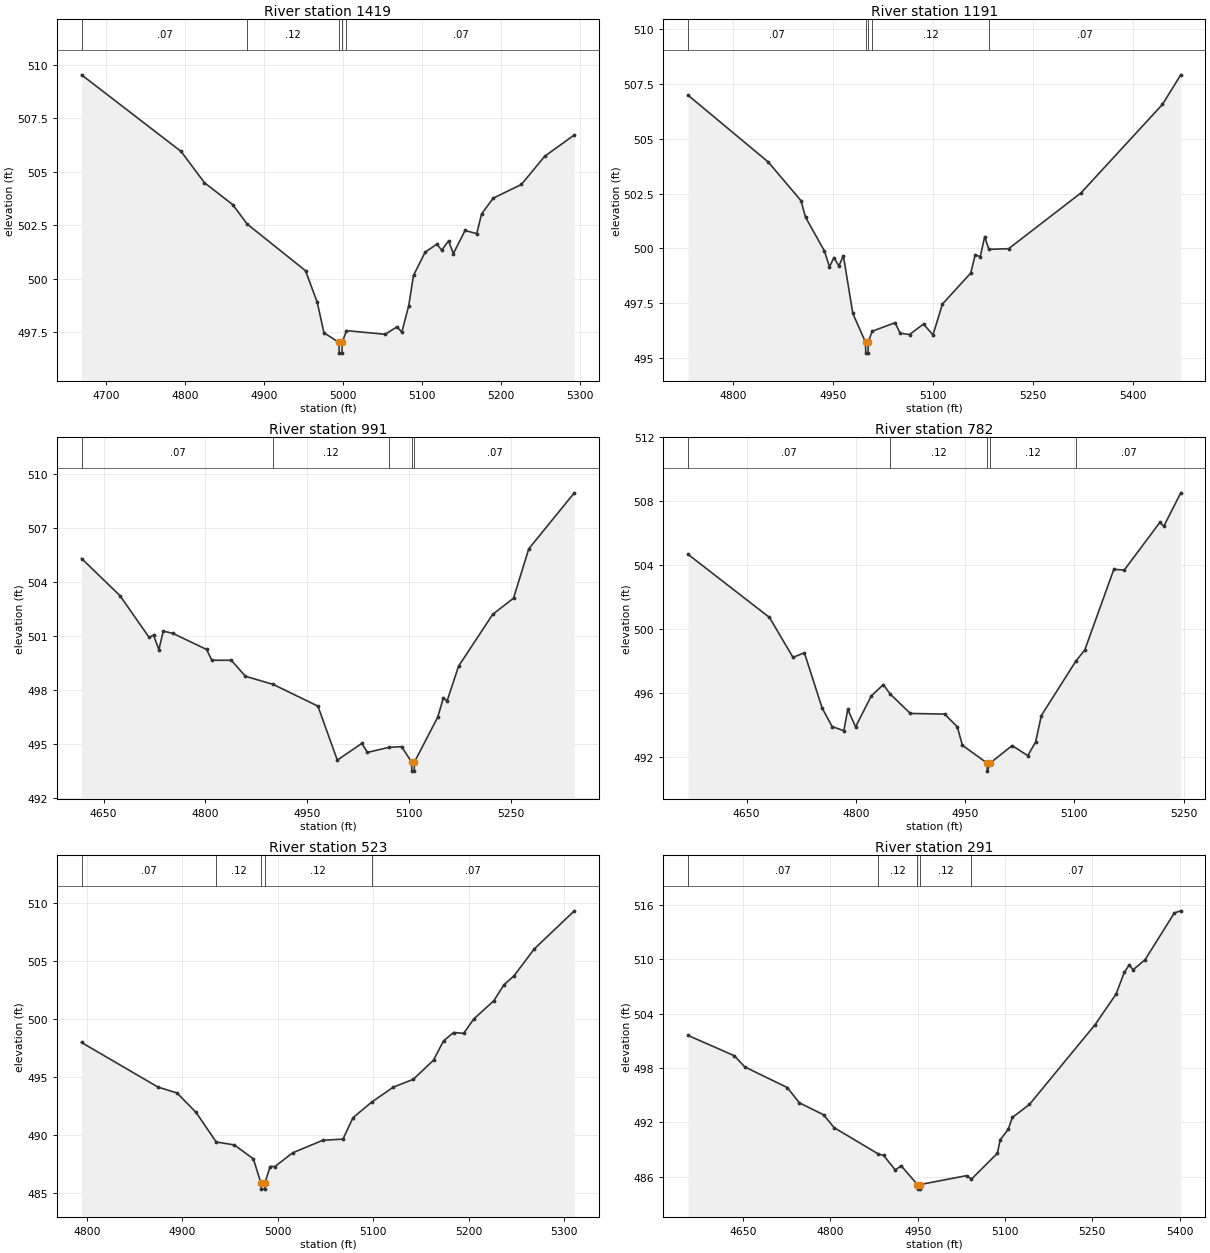
Type RM Length L Ch R = 1,1419,228,228,228
BEGIN DESCRIPTION:
A19746
END DESCRIPTION:
XS GIS Cut Line= 2
      2334446.08     13774130.47      2333935.70     13773771.11
#Sta/Elev= 30
  4668.8  509.53  4794.9  505.95  4824.5  504.49  4860.2  503.47  4878.6  502.56
  4952.5  500.38  4967.3  498.91  4975.9  497.48  4994.9  497.03  4995.2  496.53
  4998.7  496.53  4998.9  497.03  5004.4  497.58  5053.6  497.41  5068.4  497.76
  5074.5  497.51  5083.2  498.74  5089.3  500.16  5104.1  501.25  5118.9  501.62
  5125.0  501.34  5133.7  501.77  5139.8  501.18  5154.6  502.26  5169.4  502.11
  5175.5  503.03  5190.3  503.77  5226.0  504.41  5255.6  505.73  5293.0  506.72
#Mann=5,-1,0
  4668.8    0.07       0  4878.6    0.12       0  4994.9    0.05       0
  4998.9    0.12       0  5004.4    0.07       0
Bank Sta=4994.9,4998.9
Exp/Cntr=0.3,0.1

Type RM Length L Ch R = 1,1191,200,200,200
BEGIN DESCRIPTION:
A19745
END DESCRIPTION:
XS GIS Cut Line= 3
      2334524.21     13774005.46      2334198.71     13773640.90
      2333959.54     13773562.91
#Sta/Elev= 30
  4731.7  506.99  4852.2  503.94  4901.5  502.17  4908.2  501.42  4936.7  499.87
  4944.2  499.15  4950.9  499.57  4958.4  499.19  4965.1  499.66  4979.3  497.02
  4998.4  495.71  4998.7  495.21  5002.2  495.21  5002.4  495.71  5008.3  496.21
  5042.8  496.60  5050.3  496.12  5064.6  496.06  5085.5  496.54  5099.7  496.04
  5113.9  497.45  5156.5  498.87  5163.2  499.71  5170.7  499.61  5177.4  500.53
  5183.7  499.95  5213.4  499.98  5322.2  502.53  5444.5  506.57  5472.0  507.92
#Mann=5,-1,0
  4731.7    0.07       0  4998.4    0.05       0  5002.4    0.07       0
  5008.3    0.12       0  5183.7    0.07       0
Bank Sta=4998.4,5002.4
Exp/Cntr=0.3,0.1

Type RM Length L Ch R = 1,991,209,209,209
BEGIN DESCRIPTION:
LONG BRANCH TRIBUTARY 1C 2.0
END DESCRIPTION:
XS GIS Cut Line= 3
      2334674.97     13773924.97      2334425.00     13773625.00
      2334274.99     13773324.98
#Sta/Elev= 30
  4617.6  505.28  4674.2  503.22  4717.1  500.90  4723.6  501.03  4731.5  500.22
  4738.0  501.25  4752.3  501.12  4801.7  500.23  4809.6  499.63  4838.2  499.63
  4859.0  498.74  4899.8  498.29  4965.8  497.08  4994.4  494.08  5030.4  495.01
  5038.8  494.51  5070.3  494.79  5089.1  494.83  5103.9  493.97  5104.1  493.47
  5107.6  493.47  5107.9  493.97  5142.2  496.46  5150.6  497.53  5156.2  497.38
  5173.0  499.30  5223.3  502.18  5254.0  503.08  5276.4  505.82  5343.5  508.93
#Mann=5,-1,0
  4617.6    0.07       0  4899.8    0.12       0  5070.3    0.07       0
  5103.9    0.05       0  5107.9    0.07       0
Bank Sta=5103.9,5107.9
Exp/Cntr=0.3,0.1

Type RM Length L Ch R = 1,782,259,259,259
BEGIN DESCRIPTION:
A19744
END DESCRIPTION:
XS GIS Cut Line= 2
      2334748.18     13773909.10      2334501.01     13773279.48
#Sta/Elev= 30
  4569.6  504.68  4681.4  500.73  4713.7  498.23  4729.3  498.52  4753.7  495.06
  4767.4  493.90  4783.5  493.64  4788.9  494.98  4799.6  493.88  4821.1  495.81
  4837.7  496.53  4847.0  495.94  4874.8  494.72  4921.8  494.68  4939.3  493.88
  4946.2  492.73  4980.2  491.61  4980.5  491.11  4984.2  491.61  5014.5  492.71
  5036.0  492.08  5046.7  492.93  5054.6  494.59  5102.3  498.02  5114.2  498.69
  5154.1  503.74  5168.5  503.70  5217.3  506.68  5222.7  506.44  5246.0  508.53
#Mann=5,-1,0
  4569.6    0.07       0  4847.0    0.12       0  4980.2    0.05       0
  4984.2    0.12       0  5102.3    0.07       0
Bank Sta=4980.2,4984.2
Exp/Cntr=0.3,0.1

Type RM Length L Ch R = 1,523,232,232,232
BEGIN DESCRIPTION:
LONG BRANCH TRIBUTARY 1C 1.0
END DESCRIPTION:
XS GIS Cut Line= 3
      2334825.00     13773725.01      2334825.00     13773525.00
      2334725.01     13773225.04
#Sta/Elev= 30
  4794.6  497.95  4874.6  494.11  4894.6  493.60  4914.6  491.92  4935.6  489.38
  4954.6  489.12  4974.6  487.92  4982.6  485.81  4982.9  485.31  4986.4  485.31
  4986.6  485.81  4992.1  487.26  4997.2  487.26  5015.7  488.44  5047.3  489.52
  5068.4  489.62  5078.9  491.46  5098.5  492.81  5121.1  494.10  5142.2  494.78
  5163.3  496.43  5173.8  498.09  5184.3  498.81  5194.9  498.74  5205.4  499.97
  5226.5  501.55  5237.1  502.93  5247.6  503.69  5268.7  506.00  5310.8  509.30
#Mann=5,-1,0
  4794.6    0.07       0  4935.6    0.12       0  4982.6    0.05       0
  4986.6    0.12       0  5098.5    0.07       0
Bank Sta=4982.6,4986.6
Exp/Cntr=0.3,0.1

Type RM Length L Ch R = 1,291,201,201,201
BEGIN DESCRIPTION:
A19743
END DESCRIPTION:
XS GIS Cut Line= 4
      2334927.87     13773828.41      2335013.81     13773539.34
      2334995.58     13773310.17      2334810.70     13773054.98
#Sta/Elev= 30
  4555.3  501.60  4635.0  499.35  4652.8  498.12  4725.8  495.84  4746.6  494.15
  4788.4  492.82  4806.2  491.41  4882.4  488.49  4891.3  488.34  4911.4  486.72
  4921.4  487.20  4949.5  485.11  4949.8  484.61  4953.3  484.61  4953.5  485.11
  5033.9  486.10  5042.3  485.72  5086.8  488.57  5091.6  490.06  5105.5  491.22
  5112.5  492.53  5141.9  493.97  5254.8  502.80  5290.7  506.17  5305.0  508.58
  5313.6  509.42  5319.7  508.84  5340.6  509.97  5390.9  515.14  5401.9  515.37
#Mann=5,-1,0
  4555.3    0.07       0  4882.4    0.12       0  4949.5    0.05       0
  4953.5    0.12       0  5042.3    0.07       0
Bank Sta=4949.5,4953.5
Exp/Cntr=0.3,0.1

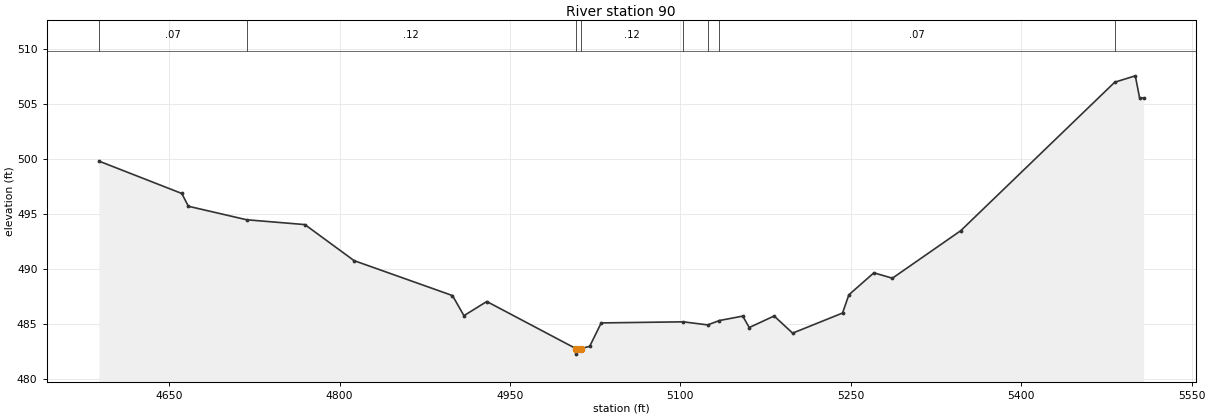
Type RM Length L Ch R = 1,90,0,0,0
BEGIN DESCRIPTION:
A19742
END DESCRIPTION:
XS GIS Cut Line= 4
      2335032.03     13773799.78      2335170.06     13773554.96
      2335198.71     13773304.96      2335016.41     13772963.80
#Sta/Elev= 30
  4588.2  499.79  4661.2  496.84  4666.9  495.68  4718.2  494.45  4769.5  494.01
  4812.8  490.73  4899.4  487.55  4909.5  485.72  4929.6  487.01  5008.1  482.72
  5008.4  482.22  5012.1  482.72  5020.2  482.93  5030.3  485.06  5102.5  485.16
  5124.0  484.88  5134.4  485.28  5154.9  485.68  5160.6  484.64  5182.5  485.69
  5198.8  484.13  5242.7  485.96  5248.3  487.62  5270.3  489.62  5286.6  489.13
  5346.7  493.45  5482.3  506.97  5500.4  507.55  5504.2  505.53  5507.7  505.53
#Mann=8,-1,0
  4588.2    0.07       0  4718.2    0.12       0  5008.1    0.05       0
  5012.1    0.12       0  5102.5     0.1       0  5124.0    0.12       0
  5134.4    0.07       0  5482.3   0.035       0
Bank Sta=5008.1,5012.1
Exp/Cntr=0.3,0.1

Chan Stop Cuts=-1