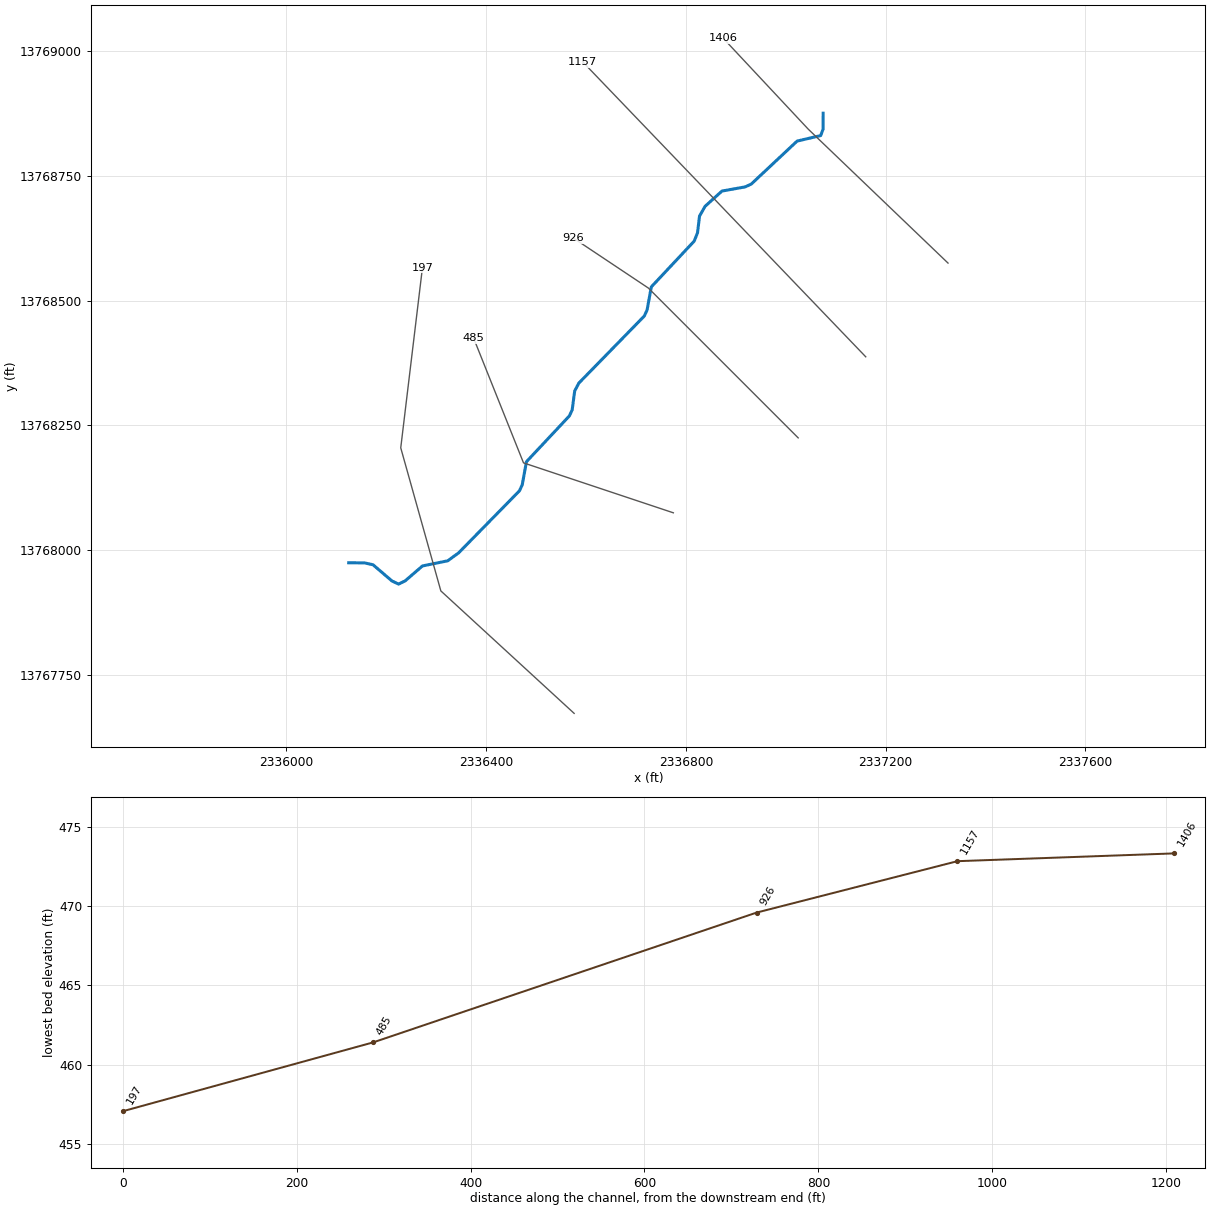
--- LONG BRANCH TRIBUTARY 1E.prj (project) ---

Proj Title=LONG BRANCH TRIBUTARY 1E Base Level Engineering
Current Plan=p01
Default Exp/Contr=0.3,0.1
English Units
Geom File=g01
Flow File=f01
Plan File=p01
BEGIN DESCRIPTION:
LONG BRANCH TRIBUTARY 1E
END DESCRIPTION:

--- LONG BRANCH TRIBUTARY 1E.p01 (plan) ---

Plan Title=Multiple Run
Short Identifier=Multiple
Geom File=g01
Flow File=f01
Subcritical Flow
K Sum by GR= 0
Std Step Tol= 0.01
Critical Tol= 0.01
Num of Std Step Trials= 20
Max Error Tol= 0.3
Flow Tol Ratio= 0.001
Split Flow NTrial= 30
Split Flow Tol= 0.02
Split Flow Ratio= 0.02
Log Output Level= 0
Friction Slope Method= 1
Unsteady Friction Slope Method= 2
Unsteady Bridges Friction Slope Method= 1
Parabolic Critical Depth
Global Vel Dist=  1 , 1 , 1
Global Log Level= 0
CheckData=True
Encroach Param= -1, 0, 0, 0
BEGIN DESCRIPTION:
Multiple Run
END DESCRIPTION:

--- LONG BRANCH TRIBUTARY 1E.f01 (steady flow) ---

Flow Title=Multiple
Number of Profiles=7
Profile Names=10-year,25-year,50-year,1pct_min,100-year,1pct_plu,500-year
River Rch & RM= LONG BRANCH TRIB,Reach-1,1406
     279     432     564     359     716    1428    1137
Boundary for River Rch & Prof#=LONG BRANCH TRIB,Reach-1,1
Up Type=0
Dn Type=3
Dn Slope=0.005
Boundary for River Rch & Prof#=LONG BRANCH TRIB,Reach-1,2
Up Type=0
Dn Type=3
Dn Slope=0.005
Boundary for River Rch & Prof#=LONG BRANCH TRIB,Reach-1,3
Up Type=0
Dn Type=3
Dn Slope=0.005
Boundary for River Rch & Prof#=LONG BRANCH TRIB,Reach-1,4
Up Type=0
Dn Type=3
Dn Slope=0.005
Boundary for River Rch & Prof#=LONG BRANCH TRIB,Reach-1,5
Up Type=0
Dn Type=3
Dn Slope=0.005
Boundary for River Rch & Prof#=LONG BRANCH TRIB,Reach-1,6
Up Type=0
Dn Type=3
Dn Slope=0.005
Boundary for River Rch & Prof#=LONG BRANCH TRIB,Reach-1,7
Up Type=0
Dn Type=3
Dn Slope=0.005

--- LONG BRANCH TRIBUTARY 1E.g01 (geometry) ---

Geom Title=Existing Conditions

River Reach=LONG BRANCH TRIB,Reach-1
Reach XY= 30
      2337075.00     13768875.00      2337074.93     13768843.46
      2337070.08     13768830.32      2337022.87     13768819.27
      2336931.02     13768733.18      2336918.91     13768727.56
      2336872.46     13768719.25      2336838.49     13768688.56
      2336827.46     13768669.13      2336823.43     13768635.69
      2336816.82     13768618.98      2336730.87     13768527.28
      2336722.47     13768481.05      2336716.84     13768468.95
      2336585.78     13768334.68      2336577.53     13768318.95
      2336572.46     13768281.05      2336566.82     13768268.96
      2336480.87     13768177.28      2336472.47     13768131.05
      2336466.84     13768118.95      2336345.09     13767994.77
      2336323.35     13767978.91      2336272.71     13767968.60
      2336238.21     13767938.83      2336224.97     13767932.28
      2336211.73     13767938.47      2336173.64     13767971.00
      2336156.88     13767974.69      2336125.00     13767975.00

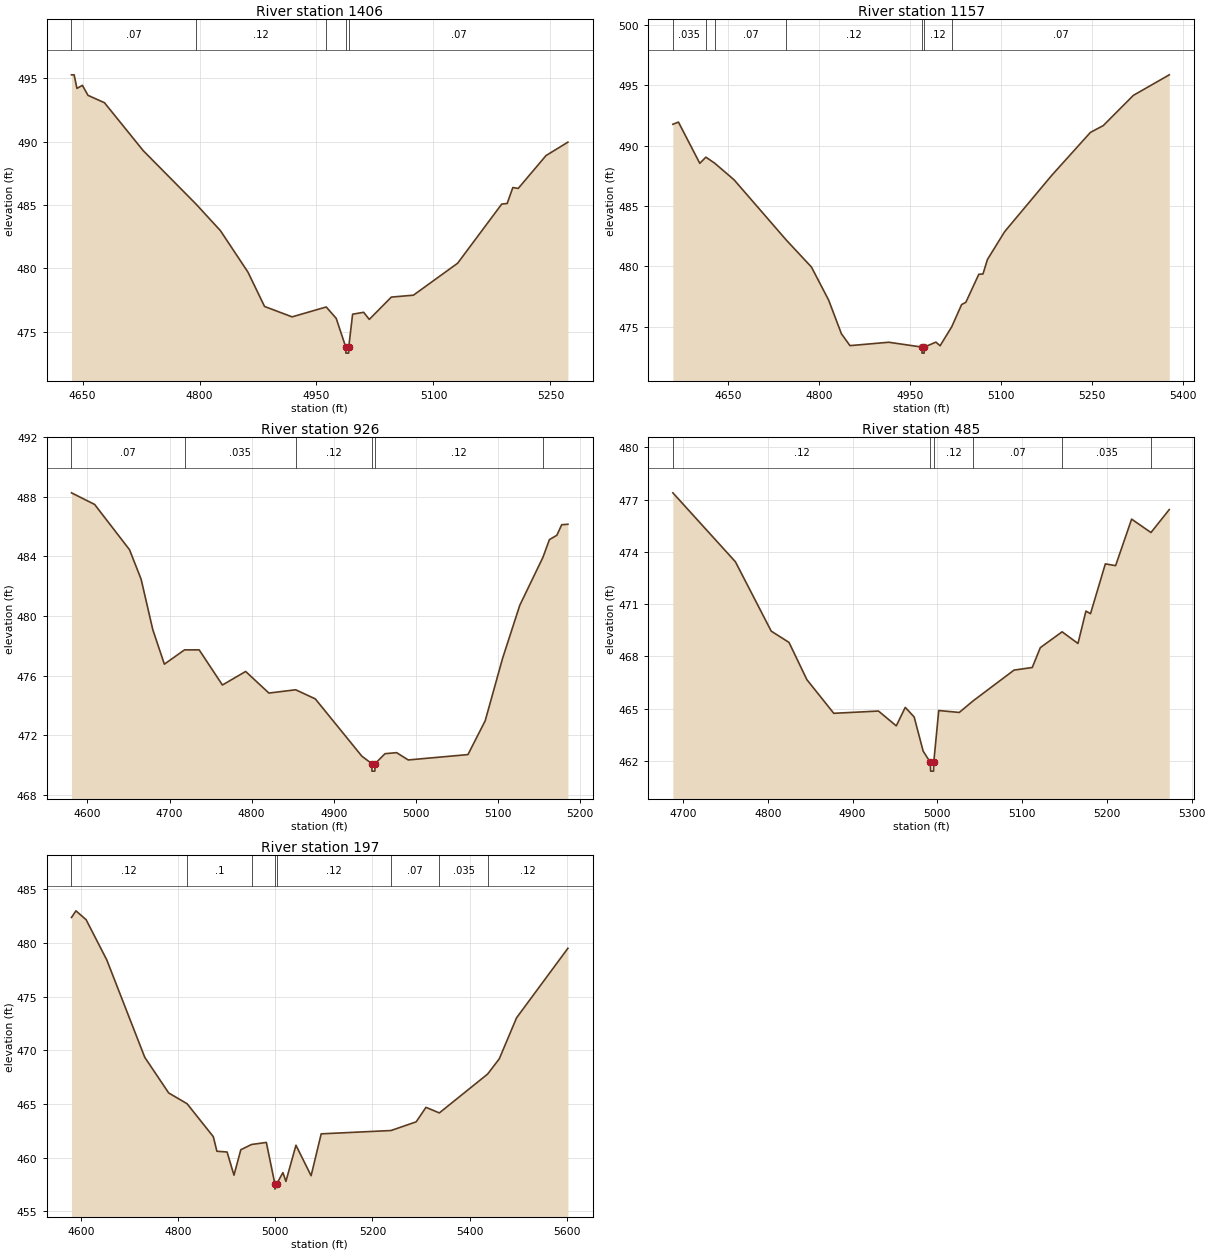
Type RM Length L Ch R = 1,1406,249,249,249
BEGIN DESCRIPTION:
LONG BRANCH TRIBUTARY 1E 3.0
END DESCRIPTION:
XS GIS Cut Line= 3
      2337324.98     13768575.02      2337045.19     13768843.09
      2336875.00     13769025.00
#Sta/Elev= 30
  4635.8  495.27  4639.2  495.27  4642.8  494.20  4649.8  494.44  4657.0  493.65
  4678.1  493.07  4727.8  489.29  4795.6  485.07  4826.8  482.98  4862.1  479.71
  4883.4  477.00  4918.7  476.18  4962.5  476.96  4975.3  476.06  4987.4  473.82
  4987.7  473.32  4991.2  473.32  4991.4  473.82  4996.3  476.39  5010.5  476.54
  5017.7  475.98  5046.0  477.74  5074.3  477.89  5131.0  480.41  5187.6  485.08
  5194.5  485.12  5201.8  486.38  5208.7  486.31  5244.3  488.90  5272.4  489.96
#Mann=5,-1,0
  4635.8    0.07       0  4795.6    0.12       0  4962.5    0.07       0
  4987.4    0.05       0  4991.4    0.07       0
Bank Sta=4987.4,4991.4
Exp/Cntr=0.3,0.1

Type RM Length L Ch R = 1,1157,231,231,231
BEGIN DESCRIPTION:
A19748
END DESCRIPTION:
XS GIS Cut Line= 2
      2337160.22     13768387.35      2336593.79     13768977.65
#Sta/Elev= 30
  4558.9  491.76  4568.1  491.94  4603.3  488.53  4613.3  489.04  4627.9  488.54
  4659.9  487.16  4745.9  482.18  4787.3  479.95  4815.6  477.22  4836.7  474.43
  4850.8  473.45  4914.7  473.73  4969.3  473.33  4969.5  472.83  4973.0  472.83
  4973.3  473.33  4992.4  473.74  4999.3  473.44  5018.4  475.00  5034.8  476.85
  5041.7  477.03  5063.1  479.35  5070.0  479.38  5077.3  480.57  5105.6  482.87
  5183.2  487.53  5247.1  491.09  5268.2  491.65  5317.8  494.15  5377.0  495.85
#Mann=7,-1,0
  4558.9   0.035       0  4613.3    0.12       0  4627.9    0.07       0
  4745.9    0.12       0  4969.3    0.05       0  4973.3    0.12       0
  5018.4    0.07       0
Bank Sta=4969.3,4973.3
Exp/Cntr=0.3,0.1

Type RM Length L Ch R = 1,926,441,441,441
BEGIN DESCRIPTION:
LONG BRANCH TRIBUTARY 1E 2.0
END DESCRIPTION:
XS GIS Cut Line= 3
      2337024.97     13768225.03      2336725.00     13768525.00
      2336575.00     13768625.00
#Sta/Elev= 30
  4580.6  488.27  4608.8  487.49  4651.3  484.45  4665.4  482.47  4679.6  479.09
  4693.7  476.77  4718.3  477.73  4736.1  477.73  4764.4  475.37  4792.7  476.28
  4821.0  474.83  4853.6  475.05  4877.5  474.44  4934.1  470.60  4946.3  470.09
  4946.5  469.59  4950.0  469.59  4950.3  470.09  4962.4  470.76  4976.5  470.83
  4990.7  470.34  5063.4  470.70  5084.4  472.97  5105.5  477.15  5126.5  480.72
  5154.7  483.94  5162.6  485.13  5171.6  485.42  5177.6  486.13  5185.1  486.16
#Mann=6,-1,0
  4580.6    0.07       0  4718.3   0.035       0  4853.6    0.12       0
  4946.3    0.05       0  4950.3    0.12       0  5154.7    0.07       0
Bank Sta=4946.3,4950.3
Exp/Cntr=0.3,0.1

Type RM Length L Ch R = 1,485,288,288,288
BEGIN DESCRIPTION:
LONG BRANCH TRIBUTARY 1E 1.0
END DESCRIPTION:
XS GIS Cut Line= 3
      2336775.01     13768075.00      2336475.00     13768175.00
      2336375.00     13768425.00
#Sta/Elev= 30
  4688.1  477.39  4761.9  473.43  4804.1  469.45  4825.1  468.80  4846.2  466.66
  4877.9  464.73  4930.6  464.86  4951.6  464.01  4962.2  465.07  4972.7  464.52
  4983.3  462.56  4991.8  461.91  4992.1  461.41  4995.6  461.41  4995.8  461.91
  5001.7  464.89  5025.9  464.78  5042.4  465.45  5090.5  467.21  5112.0  467.36
  5121.5  468.50  5147.2  469.41  5165.9  468.74  5175.3  470.60  5180.7  470.45
  5198.2  473.31  5210.3  473.21  5229.2  475.88  5252.0  475.11  5273.6  476.43
#Mann=6,-1,0
  4688.1    0.12       0  4991.8    0.05       0  4995.8    0.12       0
  5042.4    0.07       0  5147.2   0.035       0  5252.0    0.12       0
Bank Sta=4991.8,4995.8
Exp/Cntr=0.3,0.1

Type RM Length L Ch R = 1,197,0,0,0
BEGIN DESCRIPTION:
A19747
END DESCRIPTION:
XS GIS Cut Line= 4
      2336576.40     13767673.42      2336309.51     13767918.61
      2336229.22     13768205.07      2336272.62     13768565.35
#Sta/Elev= 30
  4579.8  482.38  4589.0  483.00  4610.0  482.17  4652.5  478.43  4730.8  469.35
  4780.1  466.03  4817.9  465.03  4872.0  461.96  4879.4  460.60  4900.4  460.53
  4914.6  458.37  4928.7  460.74  4950.8  461.23  4981.3  461.42  4998.8  457.57
  4999.0  457.07  5002.8  457.57  5015.4  458.61  5021.6  457.79  5042.3  461.16
  5073.5  458.32  5094.3  462.22  5238.2  462.53  5290.0  463.34  5310.2  464.69
  5337.7  464.17  5437.2  467.79  5461.2  469.21  5496.8  473.03  5602.6  479.51
#Mann=8,-1,0
  4579.8    0.12       0  4817.9     0.1       0  4950.8    0.12       0
  4998.8    0.05       0  5002.8    0.12       0  5238.2    0.07       0
  5337.7   0.035       0  5437.2    0.12       0
Bank Sta=4998.8,5002.8
Exp/Cntr=0.3,0.1

Chan Stop Cuts=-1