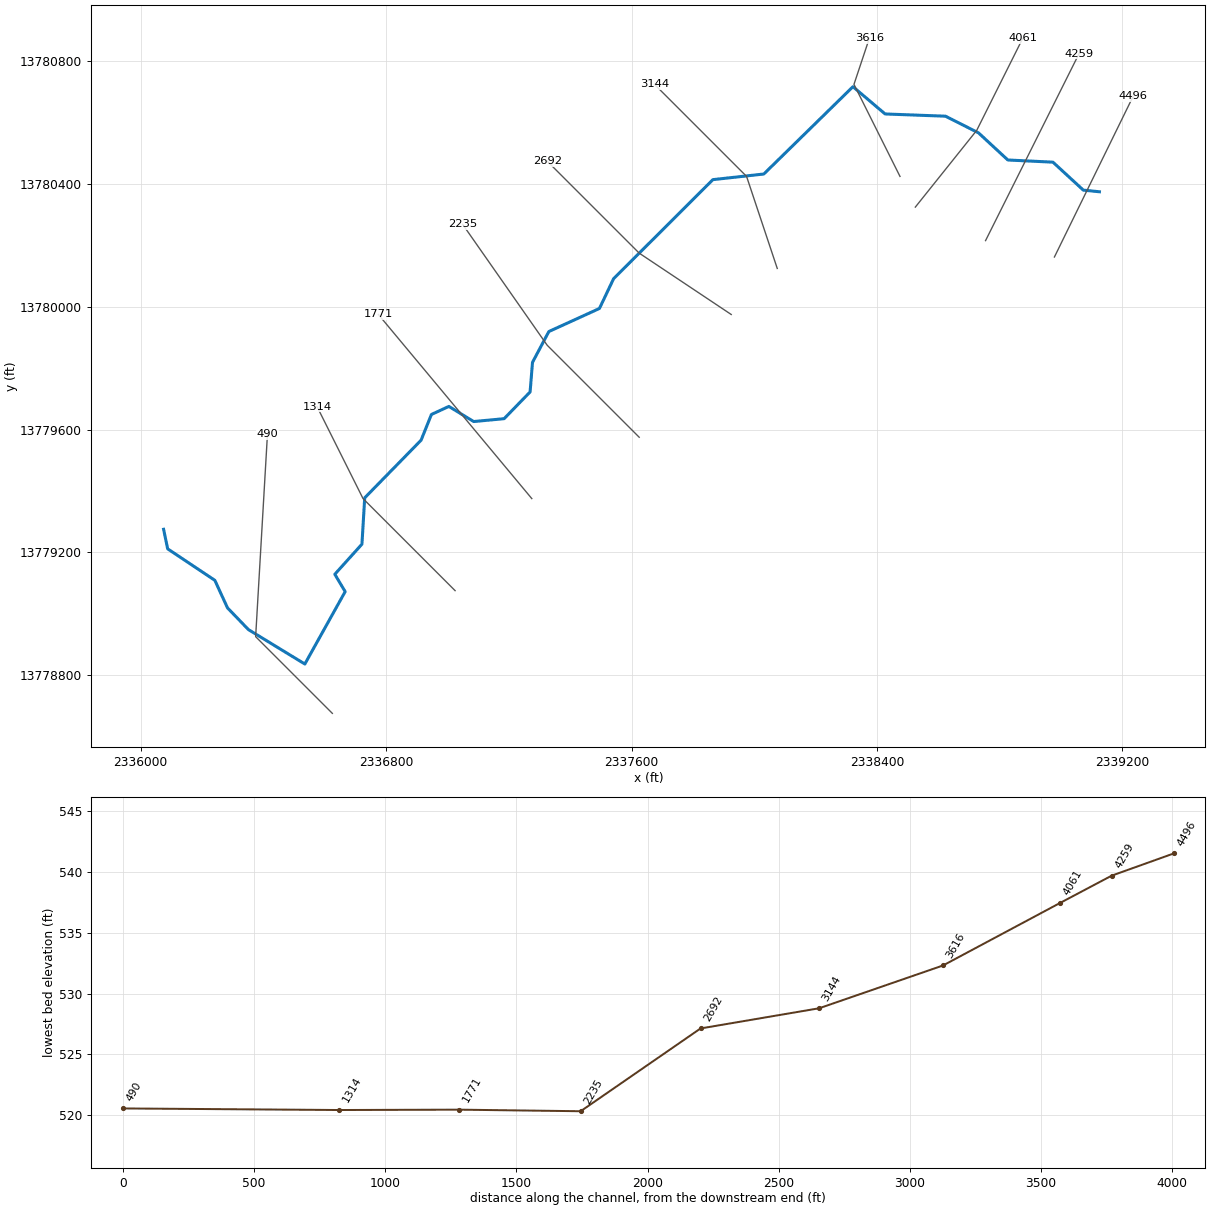
--- LONG BRANCH TRIBUTARY 2.prj (project) ---

Proj Title=LONG BRANCH TRIBUTARY 2 Base Level Engineering
Current Plan=p01
Default Exp/Contr=0.3,0.1
English Units
Geom File=g01
Flow File=f01
Plan File=p01
BEGIN DESCRIPTION:
LONG BRANCH TRIBUTARY 2
END DESCRIPTION:

--- LONG BRANCH TRIBUTARY 2.p01 (plan) ---

Plan Title=Multiple Run
Short Identifier=Multiple
Geom File=g01
Flow File=f01
Subcritical Flow
K Sum by GR= 0
Std Step Tol= 0.01
Critical Tol= 0.01
Num of Std Step Trials= 20
Max Error Tol= 0.3
Flow Tol Ratio= 0.001
Split Flow NTrial= 30
Split Flow Tol= 0.02
Split Flow Ratio= 0.02
Log Output Level= 0
Friction Slope Method= 1
Unsteady Friction Slope Method= 2
Unsteady Bridges Friction Slope Method= 1
Parabolic Critical Depth
Global Vel Dist=  1 , 1 , 1
Global Log Level= 0
CheckData=True
Encroach Param= -1, 0, 0, 0
BEGIN DESCRIPTION:
Multiple Run
END DESCRIPTION:

--- LONG BRANCH TRIBUTARY 2.f01 (steady flow) ---

Flow Title=Multiple
Number of Profiles=7
Profile Names=10-year,25-year,50-year,1pct_min,100-year,1pct_plu,500-year
River Rch & RM= LONG BRANCH TRIB,Reach-1,4496
     532     852    1140     739    1474    2941    2443
Boundary for River Rch & Prof#=LONG BRANCH TRIB,Reach-1,1
Up Type=0
Dn Type=3
Dn Slope=0.005
Boundary for River Rch & Prof#=LONG BRANCH TRIB,Reach-1,2
Up Type=0
Dn Type=3
Dn Slope=0.005
Boundary for River Rch & Prof#=LONG BRANCH TRIB,Reach-1,3
Up Type=0
Dn Type=3
Dn Slope=0.005
Boundary for River Rch & Prof#=LONG BRANCH TRIB,Reach-1,4
Up Type=0
Dn Type=3
Dn Slope=0.005
Boundary for River Rch & Prof#=LONG BRANCH TRIB,Reach-1,5
Up Type=0
Dn Type=3
Dn Slope=0.005
Boundary for River Rch & Prof#=LONG BRANCH TRIB,Reach-1,6
Up Type=0
Dn Type=3
Dn Slope=0.005
Boundary for River Rch & Prof#=LONG BRANCH TRIB,Reach-1,7
Up Type=0
Dn Type=3
Dn Slope=0.005

--- LONG BRANCH TRIBUTARY 2.g01 (geometry) ---

Geom Title=Existing Conditions

River Reach=LONG BRANCH TRIB,Reach-1
Reach XY= 30
      2339125.00     13780375.00      2339072.49     13780380.33
      2338973.53     13780471.46      2338826.47     13780478.55
      2338731.05     13780566.84      2338623.45     13780621.25
      2338426.46     13780628.56      2338321.66     13780717.40
      2338031.19     13780432.82      2337865.20     13780414.52
      2337541.66     13780091.66      2337495.47     13779994.62
      2337330.58     13779919.42      2337277.32     13779819.06
      2337269.48     13779722.56      2337184.81     13779635.42
      2337085.55     13779626.12      2337004.72     13779675.39
      2336947.86     13779649.09      2336914.21     13779565.34
      2336730.47     13779377.45      2336721.43     13779226.47
      2336633.01     13779128.33      2336666.75     13779071.77
      2336535.32     13778835.82      2336351.49     13778947.99
      2336283.15     13779018.94      2336242.08     13779108.58
      2336088.27     13779211.22      2336075.00     13779275.00

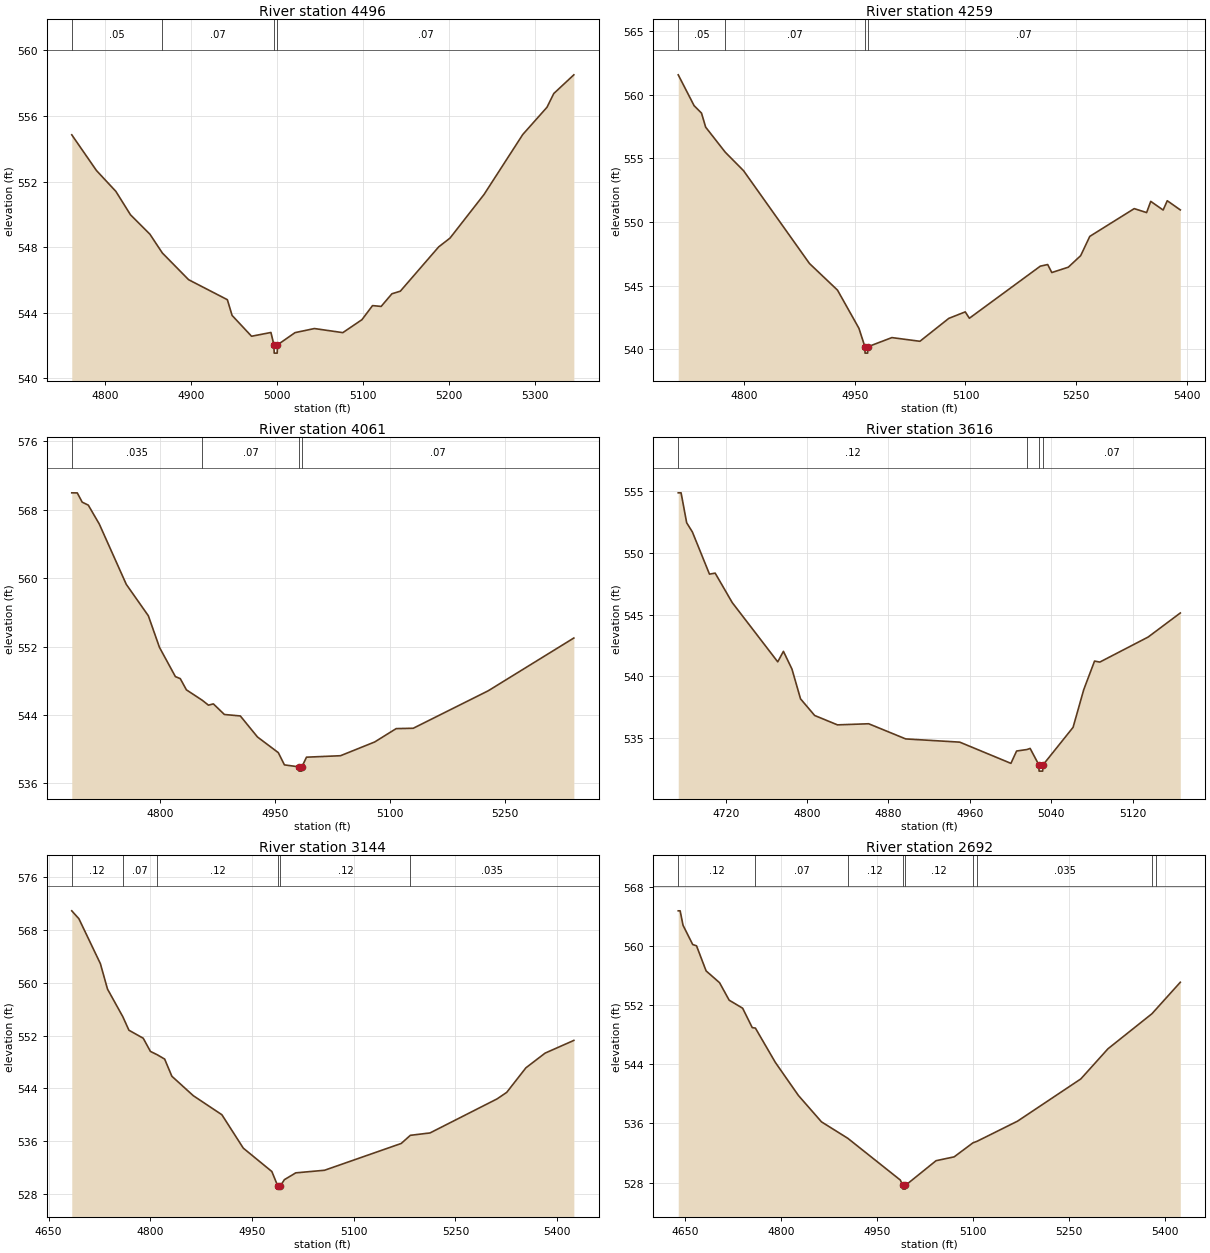
Type RM Length L Ch R = 1,4496,237,237,237
BEGIN DESCRIPTION:
A19749
END DESCRIPTION:
XS GIS Cut Line= 2
      2338978.28     13780162.31      2339234.77     13780685.97
#Sta/Elev= 30
  4761.7  554.85  4790.4  552.67  4812.9  551.40  4829.9  549.97  4852.4  548.79
  4866.9  547.64  4897.4  546.01  4942.4  544.79  4947.9  543.83  4970.5  542.56
  4993.0  542.79  4996.5  542.03  4996.8  541.53  5000.3  541.53  5000.5  542.03
  5021.0  542.78  5043.5  543.03  5076.5  542.78  5098.7  543.57  5111.0  544.43
  5121.0  544.38  5133.5  545.15  5143.3  545.31  5187.8  548.01  5201.0  548.55
  5240.5  551.21  5285.5  554.87  5313.6  556.53  5321.5  557.37  5344.8  558.51
#Mann=4,-1,0
  4761.7    0.05       0  4866.9    0.07       0  4996.5    0.05       0
  5000.5    0.07       0
Bank Sta=4996.5,5000.5
Exp/Cntr=0.3,0.1

Type RM Length L Ch R = 1,4259,198,198,198
BEGIN DESCRIPTION:
A19750
END DESCRIPTION:
XS GIS Cut Line= 2
      2338753.88     13780215.77      2339058.43     13780824.88
#Sta/Elev= 30
  4710.4  561.56  4731.9  559.14  4742.0  558.55  4747.6  557.45  4774.2  555.48
  4799.0  554.03  4888.4  546.74  4926.4  544.65  4955.5  541.65  4963.6  540.20
  4963.8  539.70  4967.3  539.70  4967.6  540.20  5000.2  540.92  5038.2  540.63
  5077.4  542.43  5099.7  542.94  5105.3  542.44  5201.5  546.53  5211.5  546.66
  5217.1  546.03  5239.5  546.45  5256.3  547.36  5268.6  548.87  5328.9  551.05
  5345.7  550.74  5351.3  551.62  5368.1  550.94  5373.7  551.67  5391.4  550.95
#Mann=4,-1,0
  4710.4    0.05       0  4774.2    0.07       0  4963.6    0.05       0
  4967.6    0.07       0
Bank Sta=4963.6,4967.6
Exp/Cntr=0.3,0.1

Type RM Length L Ch R = 1,4061,445,445,445
BEGIN DESCRIPTION:
LONG BRANCH TRIBUTARY 2 8.0
END DESCRIPTION:
XS GIS Cut Line= 3
      2338525.00     13780325.00      2338725.00     13780575.00
      2338875.02     13780875.03
#Sta/Elev= 30
  4684.4  569.97  4691.6  569.96  4698.0  568.88  4706.0  568.53  4720.4  566.31
  4755.6  559.27  4784.4  555.60  4798.9  551.91  4819.7  548.49  4826.1  548.25
  4834.1  546.94  4854.7  545.73  4862.9  545.15  4869.3  545.30  4883.7  544.06
  4904.5  543.89  4926.9  541.43  4954.1  539.60  4962.1  538.17  4980.9  537.94
  4981.2  537.44  4984.7  537.44  4984.9  537.94  4990.9  539.07  5035.3  539.24
  5080.0  540.85  5108.0  542.41  5130.3  542.45  5228.2  546.83  5340.0  553.00
#Mann=4,-1,0
  4684.4   0.035       0  4854.7    0.07       0  4980.9    0.05       0
  4984.9    0.07       0
Bank Sta=4980.9,4984.9
Exp/Cntr=0.3,0.1

Type RM Length L Ch R = 1,3616,472,472,472
BEGIN DESCRIPTION:
LONG BRANCH TRIBUTARY 2 7.0
END DESCRIPTION:
XS GIS Cut Line= 3
      2338474.98     13780425.03      2338325.00     13780725.00
      2338375.00     13780875.01
#Sta/Elev= 30
  4673.4  554.87  4676.2  554.87  4681.7  552.44  4687.3  551.70  4704.1  548.28
  4709.7  548.36  4726.5  545.97  4771.2  541.17  4776.8  542.02  4785.2  540.58
  4793.6  538.17  4807.5  536.82  4829.9  536.06  4860.6  536.15  4897.0  534.92
  4950.1  534.66  5000.4  532.94  5006.0  533.94  5016.1  534.06  5019.3  534.15
  5027.9  532.81  5028.1  532.31  5031.6  532.31  5031.9  532.81  5061.5  535.86
  5072.0  538.92  5082.6  541.23  5087.8  541.15  5135.3  543.18  5166.9  545.13
#Mann=4,-1,0
  4673.4    0.12       0  5016.1    0.07       0  5027.9    0.05       0
  5031.9    0.07       0
Bank Sta=5027.9,5031.9
Exp/Cntr=0.3,0.1

Type RM Length L Ch R = 1,3144,452,452,452
BEGIN DESCRIPTION:
LONG BRANCH TRIBUTARY 2 6.0
END DESCRIPTION:
XS GIS Cut Line= 3
      2338075.00     13780125.00      2337975.00     13780425.00
      2337675.00     13780725.00
#Sta/Elev= 30
  4684.1  570.84  4694.6  569.65  4726.3  562.86  4736.8  559.02  4759.4  554.84
  4768.4  552.80  4789.5  551.59  4800.1  549.60  4810.2  549.09  4821.1  548.44
  4831.7  545.85  4863.3  542.91  4905.5  540.03  4937.1  534.98  4979.2  531.45
  4987.8  529.29  4988.0  528.79  4991.5  528.79  4991.8  529.29  4997.7  530.22
  5014.5  531.25  5056.9  531.64  5170.0  535.69  5183.5  536.92  5212.5  537.28
  5311.5  542.43  5325.6  543.41  5353.9  547.12  5382.2  549.34  5424.6  551.26
#Mann=6,-1,0
  4684.1    0.12       0  4759.4    0.07       0  4810.2    0.12       0
  4987.8    0.05       0  4991.8    0.12       0  5183.5   0.035       0
Bank Sta=4987.8,4991.8
Exp/Cntr=0.3,0.1

Type RM Length L Ch R = 1,2692,457,457,457
BEGIN DESCRIPTION:
LONG BRANCH TRIBUTARY 2 5.0
END DESCRIPTION:
XS GIS Cut Line= 3
      2337925.02     13779974.99      2337625.00     13780175.00
      2337325.03     13780474.97
#Sta/Elev= 30
  4639.4  564.73  4642.4  564.73  4646.9  562.78  4662.0  560.18  4668.0  560.00
  4683.0  556.61  4704.0  555.02  4719.0  552.66  4740.1  551.57  4755.1  548.95
  4760.0  548.89  4791.2  544.25  4827.2  539.79  4863.3  536.22  4904.4  534.00
  4986.5  528.36  4990.5  527.63  4990.7  527.13  4994.2  527.13  4994.5  527.63
  5042.4  530.97  5070.7  531.49  5100.0  533.38  5106.9  533.61  5169.7  536.31
  5268.7  542.02  5311.1  546.09  5379.9  550.83  5386.9  551.50  5424.2  555.08
#Mann=9,-1,0
  4639.4    0.12       0  4760.0    0.07       0  4904.4    0.12       0
  4990.5    0.05       0  4994.5    0.12       0  5100.0    0.07       0
  5106.9   0.035       0  5379.9    0.07       0  5386.9    0.12       0
Bank Sta=4990.5,4994.5
Exp/Cntr=0.3,0.1

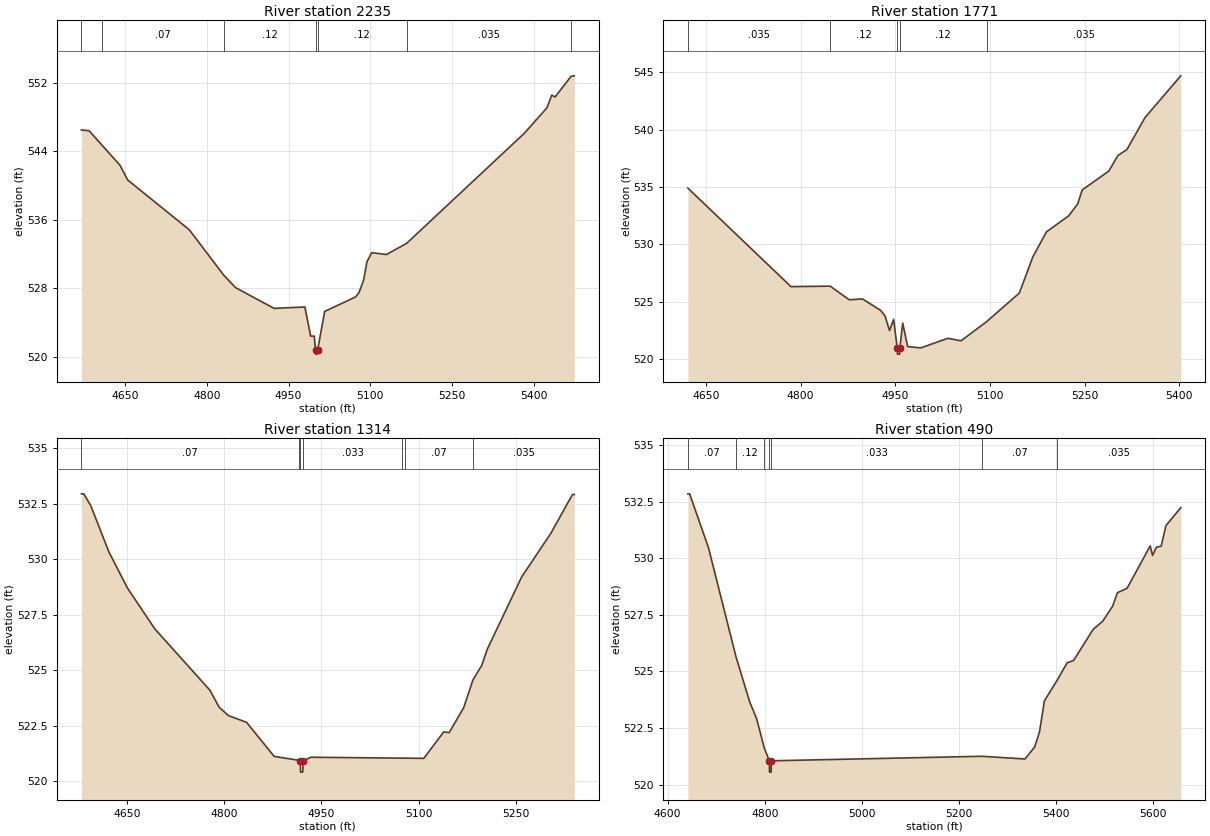
Type RM Length L Ch R = 1,2235,464,464,464
BEGIN DESCRIPTION:
LONG BRANCH TRIBUTARY 2 4.0
END DESCRIPTION:
XS GIS Cut Line= 3
      2337625.03     13779574.97      2337325.00     13779875.00
      2337049.67     13780268.79
#Sta/Elev= 30
  4569.7  546.48  4583.9  546.38  4607.9  544.67  4640.5  542.36  4654.6  540.64
  4767.7  534.83  4830.7  529.55  4852.6  528.08  4923.3  525.66  4979.9  525.82
  4990.5  522.42  4997.1  522.42  4999.4  520.82  4999.7  520.32  5003.2  520.32
  5003.4  520.82  5016.2  525.30  5072.9  526.99  5079.4  527.51  5087.8  528.98
  5093.9  531.11  5102.6  532.16  5129.6  531.94  5166.6  533.24  5382.5  546.07
  5424.4  549.07  5433.1  550.55  5439.2  550.32  5468.7  552.74  5474.5  552.79
#Mann=7,-1,0
  4569.7   0.035       0  4607.9    0.07       0  4830.7    0.12       0
  4999.4    0.05       0  5003.4    0.12       0  5166.6   0.035       0
  5468.7    0.07       0
Bank Sta=4999.4,5003.4
Exp/Cntr=0.3,0.1

Type RM Length L Ch R = 1,1771,457,457,457
BEGIN DESCRIPTION:
LONG BRANCH TRIBUTARY 2 3.0
END DESCRIPTION:
XS GIS Cut Line= 3
      2337274.97     13779375.03      2337025.00     13779675.00
      2336774.99     13779975.01
#Sta/Elev= 30
  4621.3  534.91  4784.6  526.33  4846.8  526.37  4877.0  525.18  4897.9  525.26
  4926.5  524.27  4933.7  523.77  4940.8  522.50  4947.3  523.48  4953.1  520.95
  4953.4  520.45  4956.9  520.45  4957.1  520.95  4961.7  523.15  4969.5  521.11
  4990.3  520.99  5033.2  521.83  5054.1  521.61  5094.7  523.28  5146.5  525.77
  5168.0  528.93  5189.5  531.10  5224.6  532.49  5238.9  533.53  5246.1  534.75
  5288.4  536.40  5302.7  537.75  5317.0  538.27  5345.7  541.06  5402.3  544.69
#Mann=5,-1,0
  4621.3   0.035       0  4846.8    0.12       0  4953.1    0.05       0
  4957.1    0.12       0  5094.7   0.035       0
Bank Sta=4953.1,4957.1
Exp/Cntr=0.3,0.1

Type RM Length L Ch R = 1,1314,824,824,824
BEGIN DESCRIPTION:
LONG BRANCH TRIBUTARY 2 2.0
END DESCRIPTION:
XS GIS Cut Line= 3
      2337025.01     13779074.99      2336725.00     13779375.00
      2336574.99     13779675.02
#Sta/Elev= 30
  4580.0  532.95  4583.5  532.95  4594.2  532.43  4622.4  530.33  4650.7  528.72
  4693.1  526.87  4778.0  524.11  4792.1  523.35  4806.3  522.97  4834.6  522.66
  4877.0  521.13  4915.6  520.95  4917.4  520.92  4917.7  520.42  4921.2  520.42
  4921.4  520.92  4933.6  521.09  5074.8  521.05  5079.2  521.05  5107.7  521.04
  5138.4  522.23  5146.8  522.20  5169.2  523.32  5183.3  524.56  5197.1  525.23
  5205.5  525.95  5258.6  529.21  5303.3  531.16  5336.9  532.92  5339.7  532.92
#Mann=7,-1,0
  4580.0    0.07       0  4915.6   0.033       0  4917.4   0.033       0
  4921.4   0.033       0  5074.8    0.12       0  5079.2    0.07       0
  5183.3   0.035       0
Bank Sta=4917.4,4921.4
Exp/Cntr=0.3,0.1

Type RM Length L Ch R = 1,490,0,0,0
BEGIN DESCRIPTION:
LONG BRANCH TRIBUTARY 2 1.0
END DESCRIPTION:
XS GIS Cut Line= 3
      2336625.01     13778674.99      2336375.00     13778925.00
      2336413.52     13779585.31
#Sta/Elev= 30
  4641.8  532.84  4645.4  532.84  4684.2  530.46  4740.9  525.64  4769.1  523.65
  4783.2  522.92  4799.2  521.61  4809.5  521.05  4809.8  520.55  4813.3  520.55
  4813.5  521.05  5247.4  521.25  5335.9  521.13  5356.0  521.66  5366.0  522.34
  5376.0  523.70  5402.1  524.60  5422.8  525.38  5436.1  525.48  5476.2  526.85
  5496.2  527.22  5516.3  527.87  5526.3  528.47  5546.3  528.67  5593.8  530.54
  5598.8  530.12  5606.4  530.48  5616.4  530.53  5626.4  531.44  5656.8  532.23
#Mann=7,-1,0
  4641.8    0.07       0  4740.9    0.12       0  4799.2   0.033       0
  4809.5   0.033       0  4813.5   0.033       0  5247.4    0.07       0
  5402.1   0.035       0
Bank Sta=4809.5,4813.5
Exp/Cntr=0.3,0.1

Chan Stop Cuts=-1