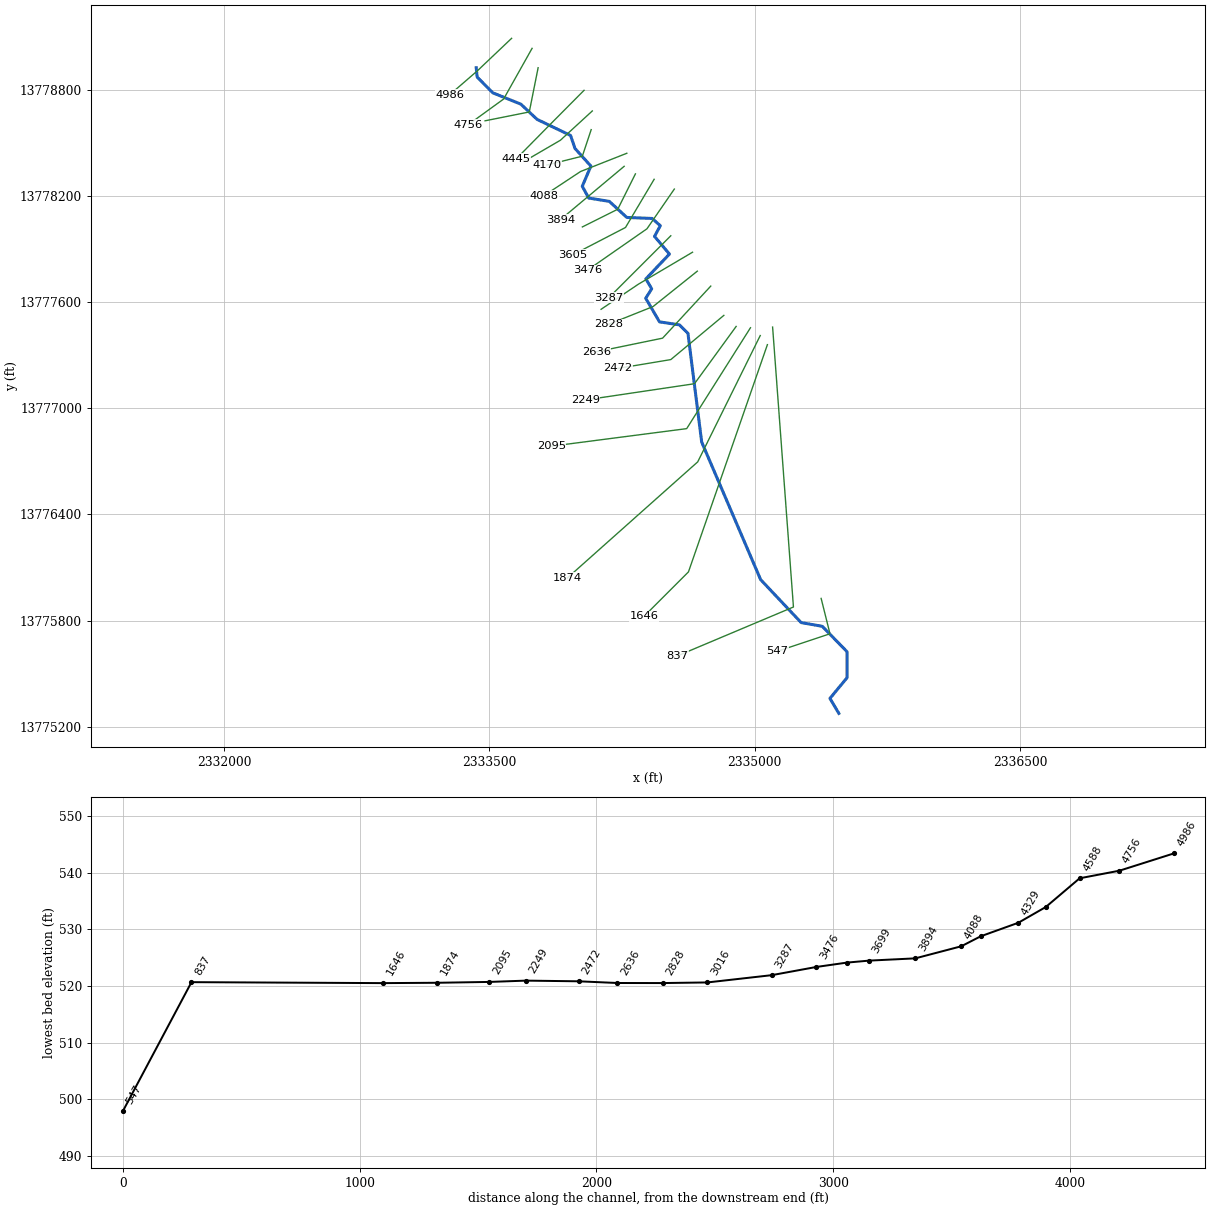
--- LONG BRANCH TRIBUTARY 3.prj (project) ---

Proj Title=LONG BRANCH TRIBUTARY 3 Base Level Engineering
Current Plan=p01
Default Exp/Contr=0.3,0.1
English Units
Geom File=g01
Flow File=f01
Plan File=p01
BEGIN DESCRIPTION:
LONG BRANCH TRIBUTARY 3
END DESCRIPTION:

--- LONG BRANCH TRIBUTARY 3.p01 (plan) ---

Plan Title=Multiple Run
Short Identifier=Multiple
Geom File=g01
Flow File=f01
Subcritical Flow
K Sum by GR= 0
Std Step Tol= 0.01
Critical Tol= 0.01
Num of Std Step Trials= 20
Max Error Tol= 0.3
Flow Tol Ratio= 0.001
Split Flow NTrial= 30
Split Flow Tol= 0.02
Split Flow Ratio= 0.02
Log Output Level= 0
Friction Slope Method= 1
Unsteady Friction Slope Method= 2
Unsteady Bridges Friction Slope Method= 1
Parabolic Critical Depth
Global Vel Dist=  1 , 1 , 1
Global Log Level= 0
CheckData=True
Encroach Param= -1, 0, 0, 0
BEGIN DESCRIPTION:
Multiple Run
END DESCRIPTION:

--- LONG BRANCH TRIBUTARY 3.f01 (steady flow) ---

Flow Title=Multiple
Number of Profiles=7
Profile Names=10-year,25-year,50-year,1pct_min,100-year,1pct_plu,500-year
River Rch & RM= LONG BRANCH TRIB,Reach-1,4986
     291     448     585     370     739    1475    1168
Boundary for River Rch & Prof#=LONG BRANCH TRIB,Reach-1,1
Up Type=0
Dn Type=3
Dn Slope=0.005
Boundary for River Rch & Prof#=LONG BRANCH TRIB,Reach-1,2
Up Type=0
Dn Type=3
Dn Slope=0.005
Boundary for River Rch & Prof#=LONG BRANCH TRIB,Reach-1,3
Up Type=0
Dn Type=3
Dn Slope=0.005
Boundary for River Rch & Prof#=LONG BRANCH TRIB,Reach-1,4
Up Type=0
Dn Type=3
Dn Slope=0.005
Boundary for River Rch & Prof#=LONG BRANCH TRIB,Reach-1,5
Up Type=0
Dn Type=3
Dn Slope=0.005
Boundary for River Rch & Prof#=LONG BRANCH TRIB,Reach-1,6
Up Type=0
Dn Type=3
Dn Slope=0.005
Boundary for River Rch & Prof#=LONG BRANCH TRIB,Reach-1,7
Up Type=0
Dn Type=3
Dn Slope=0.005

--- LONG BRANCH TRIBUTARY 3.g01 (geometry) ---

Geom Title=Existing Conditions

River Reach=LONG BRANCH TRIB,Reach-1
Reach XY= 30
      2333425.00     13778925.00      2333430.30     13778872.46
      2333518.93     13778783.13      2333677.29     13778719.15
      2333768.95     13778633.16      2333958.51     13778542.05
      2333983.19     13778468.98      2334073.37     13778368.96
      2334024.62     13778254.72      2334061.20     13778188.26
      2334177.42     13778169.46      2334276.47     13778078.56
      2334419.54     13778072.93      2334465.83     13778032.00
      2334433.04     13777971.68      2334517.39     13777871.67
      2334384.29     13777731.67      2334416.96     13777675.00
      2334383.23     13777621.77      2334461.34     13777488.26
      2334573.78     13777471.47      2334622.00     13777423.60
      2334699.65     13776808.80      2335032.98     13776031.02
      2335261.71     13775788.43      2335381.17     13775767.14
      2335521.47     13775623.53      2335521.46     13775476.47
      2335424.82     13775359.74      2335475.00     13775275.00

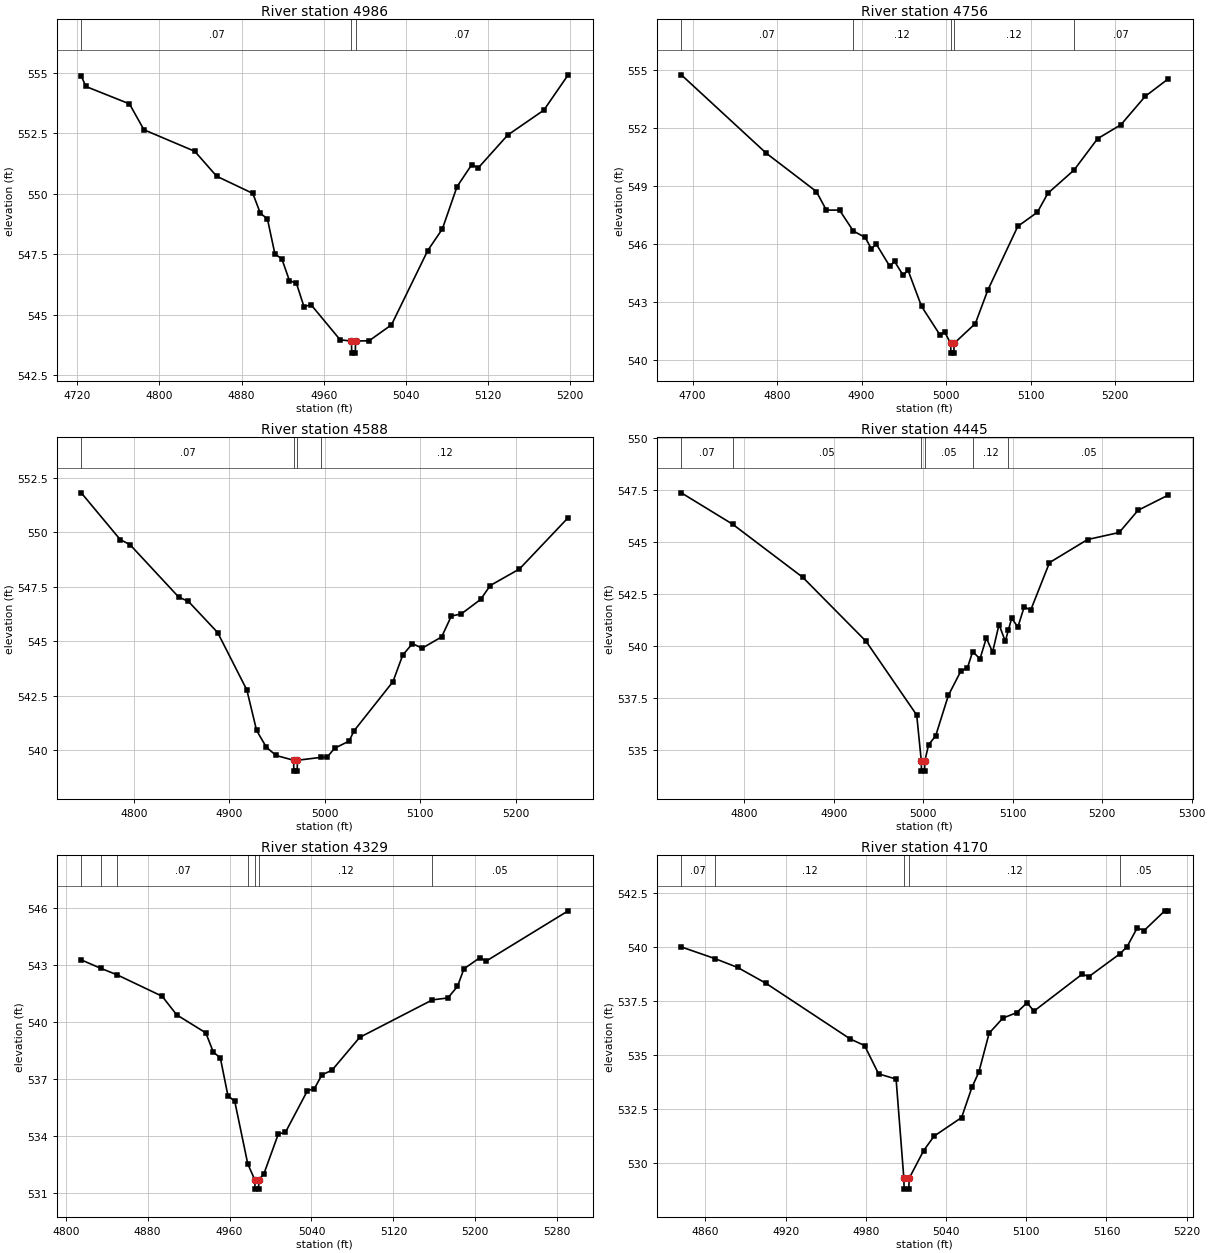
Type RM Length L Ch R = 1,4986,230,230,230
BEGIN DESCRIPTION:
A19766
END DESCRIPTION:
XS GIS Cut Line= 3
      2333625.13     13779091.21      2333431.63     13778907.59
      2333274.88     13778772.02
#Sta/Elev= 30
  4723.9  554.88  4728.3  554.44  4770.8  553.72  4784.9  552.65  4834.4  551.76
  4855.7  550.73  4890.9  550.02  4898.2  549.20  4905.1  548.97  4912.4  547.52
  4919.2  547.31  4926.5  546.42  4933.4  546.30  4940.7  545.34  4947.6  545.42
  4975.9  543.97  4986.9  543.92  4987.2  543.42  4990.7  543.42  4990.9  543.92
  5004.1  543.93  5025.9  544.59  5061.2  547.66  5075.4  548.55  5089.7  550.30
  5103.9  551.20  5110.5  551.08  5139.0  552.43  5174.2  553.46  5197.9  554.92
#Mann=3,-1,0
  4723.9    0.07       0  4986.9    0.05       0  4990.9    0.07       0
Bank Sta=4986.9,4990.9
Exp/Cntr=0.3,0.1

Type RM Length L Ch R = 1,4756,168,168,168
BEGIN DESCRIPTION:
A19765
END DESCRIPTION:
XS GIS Cut Line= 3
      2333740.90     13779034.66      2333579.92     13778748.00
      2333379.71     13778602.78
#Sta/Elev= 30
  4686.7  554.75  4787.2  550.70  4846.5  548.72  4858.3  547.76  4873.9  547.76
  4890.2  546.68  4904.2  546.35  4911.6  545.76  4917.3  546.01  4933.3  544.86
  4939.0  545.11  4949.2  544.39  4954.9  544.66  4970.9  542.79  4992.6  541.32
  4998.3  541.46  5005.4  540.87  5005.7  540.37  5009.2  540.37  5009.4  540.87
  5034.6  541.90  5049.3  543.62  5084.8  546.92  5108.0  547.65  5120.4  548.63
  5151.4  549.83  5179.2  551.45  5206.8  552.17  5235.6  553.64  5262.8  554.54
#Mann=5,-1,0
  4686.7    0.07       0  4890.2    0.12       0  5005.4    0.05       0
  5009.4    0.12       0  5151.4    0.07       0
Bank Sta=5005.4,5009.4
Exp/Cntr=0.3,0.1

Type RM Length L Ch R = 1,4588,143,143,143
BEGIN DESCRIPTION:
LONG BRANCH TRIBUTARY 3 9.0
END DESCRIPTION:
XS GIS Cut Line= 3
      2333775.01     13778925.03      2333725.00     13778675.00
      2333475.03     13778625.01
#Sta/Elev= 30
  4745.0  551.82  4785.8  549.67  4796.0  549.44  4847.0  547.03  4857.2  546.83
  4887.8  545.40  4918.4  542.76  4928.6  540.90  4938.8  540.13  4949.0  539.75
  4967.4  539.53  4967.6  539.03  4971.1  539.03  4971.4  539.53  4995.7  539.66
  5002.5  539.67  5010.2  540.08  5025.5  540.41  5030.6  540.88  5071.4  543.14
  5081.6  544.36  5091.8  544.89  5102.0  544.68  5122.4  545.20  5132.6  546.16
  5142.8  546.25  5163.2  546.92  5173.3  547.56  5203.9  548.32  5254.9  550.68
#Mann=4,-1,0
  4745.0    0.07       0  4967.4    0.05       0  4971.4    0.07       0
  4995.7    0.12       0
Bank Sta=4967.4,4971.4
Exp/Cntr=0.3,0.1

Type RM Length L Ch R = 1,4445,116,116,116
BEGIN DESCRIPTION:
A19764
END DESCRIPTION:
XS GIS Cut Line= 3
      2334034.64     13778797.40      2333839.78     13778601.12
      2333651.96     13778410.48
#Sta/Elev= 30
  4729.6  547.36  4786.9  545.85  4865.4  543.29  4936.1  540.21  4992.7  536.66
  4997.8  534.46  4998.0  533.96  5001.5  533.96  5001.8  534.46  5006.0  535.23
  5013.9  535.66  5028.1  537.61  5042.2  538.79  5049.2  538.91  5055.3  539.72
  5063.4  539.36  5070.5  540.37  5077.5  539.69  5084.7  541.02  5091.7  540.21
  5095.2  540.76  5098.8  541.32  5105.8  540.90  5112.9  541.88  5120.0  541.70
  5141.1  544.00  5183.6  545.11  5219.0  545.45  5240.1  546.52  5273.8  547.25
#Mann=6,-1,0
  4729.6    0.07       0  4786.9    0.05       0  4997.8    0.05       0
  5001.8    0.05       0  5055.3    0.12       0  5095.2    0.05       0
Bank Sta=4997.8,5001.8
Exp/Cntr=0.3,0.1

Type RM Length L Ch R = 1,4329,159,159,159
BEGIN DESCRIPTION:
A19763
END DESCRIPTION:
XS GIS Cut Line= 3
      2334081.28     13778680.66      2333900.91     13778515.02
      2333701.58     13778399.04
#Sta/Elev= 30
  4815.2  543.28  4834.5  542.83  4850.3  542.49  4894.2  541.36  4908.4  540.38
  4936.8  539.43  4944.2  538.41  4951.0  538.11  4958.4  536.12  4965.1  535.81
  4977.8  532.51  4984.6  531.68  4984.9  531.18  4988.4  531.18  4988.6  531.68
  4993.5  531.98  5007.7  534.10  5014.5  534.17  5036.1  536.38  5042.8  536.48
  5050.2  537.21  5060.1  537.46  5087.1  539.19  5158.1  541.17  5173.2  541.27
  5182.6  541.88  5188.9  542.81  5204.6  543.40  5210.4  543.21  5290.7  545.87
#Mann=7,-1,0
  4815.2    0.07       0  4834.5    0.12       0  4850.3    0.07       0
  4977.8    0.12       0  4984.6    0.05       0  4988.6    0.12       0
  5158.1    0.05       0
Bank Sta=4984.6,4988.6
Exp/Cntr=0.3,0.1

Type RM Length L Ch R = 1,4170,82,82,82
BEGIN DESCRIPTION:
LONG BRANCH TRIBUTARY 3 8.0
END DESCRIPTION:
XS GIS Cut Line= 3
      2334075.01     13778575.04      2334025.00     13778425.00
      2333825.01     13778375.00
#Sta/Elev= 30
  4841.9  539.99  4867.1  539.45  4884.1  539.04  4905.2  538.31  4968.4  535.73
  4979.0  535.43  4989.5  534.12  5002.6  533.88  5008.4  529.29  5008.6  528.79
  5012.1  528.79  5012.4  529.29  5023.2  530.57  5031.0  531.24  5051.6  532.10
  5059.3  533.49  5064.5  534.20  5072.2  536.00  5082.5  536.70  5092.8  536.95
  5100.6  537.41  5105.7  537.02  5141.8  538.73  5146.9  538.62  5169.8  539.66
  5175.3  539.99  5183.0  540.87  5188.2  540.75  5203.6  541.66  5206.2  541.66
#Mann=5,-1,0
  4841.9    0.07       0  4867.1    0.12       0  5008.4    0.05       0
  5012.4    0.12       0  5169.8    0.05       0
Bank Sta=5008.4,5012.4
Exp/Cntr=0.3,0.1

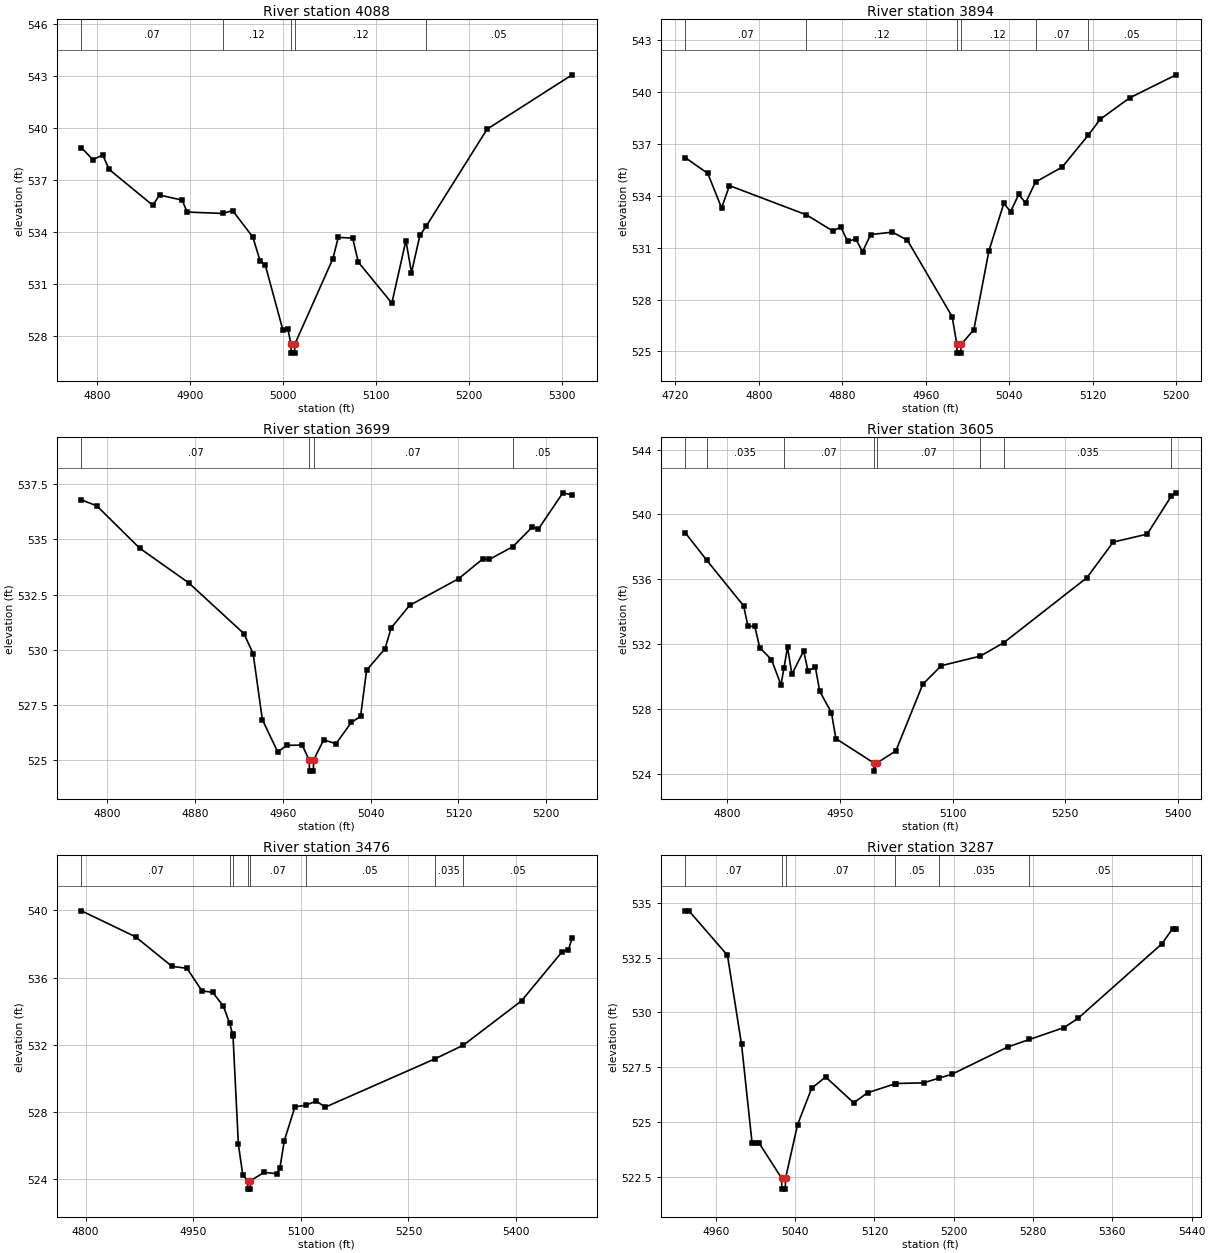
Type RM Length L Ch R = 1,4088,194,194,194
BEGIN DESCRIPTION:
A19762
END DESCRIPTION:
XS GIS Cut Line= 3
      2334276.32     13778441.43      2334015.00     13778338.37
      2333809.42     13778202.55
#Sta/Elev= 30
  4783.3  538.87  4795.5  538.18  4806.2  538.45  4813.0  537.62  4860.0  535.55
  4867.2  536.14  4891.5  535.85  4896.9  535.16  4935.3  535.08  4945.7  535.25
  4967.5  533.72  4975.4  532.33  4980.8  532.12  4999.7  528.38  5005.2  528.41
  5008.5  527.53  5008.8  527.03  5012.3  527.03  5012.5  527.53  5053.5  532.47
  5059.3  533.70  5074.8  533.66  5080.8  532.28  5116.9  529.91  5132.0  533.52
  5138.0  531.67  5147.0  533.81  5154.1  534.37  5219.3  539.94  5310.6  543.07
#Mann=5,-1,0
  4783.3    0.07       0  4935.3    0.12       0  5008.5    0.05       0
  5012.5    0.12       0  5154.1    0.05       0
Bank Sta=5008.5,5012.5
Exp/Cntr=0.3,0.1

Type RM Length L Ch R = 1,3894,195,195,195
BEGIN DESCRIPTION:
A19761
END DESCRIPTION:
XS GIS Cut Line= 2
      2334261.55     13778367.79      2333900.93     13778066.06
#Sta/Elev= 30
  4729.8  536.20  4751.2  535.30  4764.4  533.30  4772.0  534.59  4845.7  532.90
  4870.9  531.97  4878.7  532.19  4885.2  531.37  4893.0  531.50  4899.5  530.77
  4907.3  531.76  4928.2  531.90  4942.5  531.43  4985.4  527.01  4989.9  525.40
  4990.2  524.90  4993.7  524.90  4993.9  525.40  5006.2  526.26  5020.6  530.81
  5034.9  533.56  5041.4  533.09  5049.2  534.08  5055.7  533.59  5065.3  534.80
  5090.8  535.66  5116.0  537.52  5127.3  538.43  5155.6  539.67  5200.0  541.00
#Mann=6,-1,0
  4729.8    0.07       0  4845.7    0.12       0  4989.9    0.05       0
  4993.9    0.12       0  5065.3    0.07       0  5116.0    0.05       0
Bank Sta=4989.9,4993.9
Exp/Cntr=0.3,0.1

Type RM Length L Ch R = 1,3699,94,94,94
BEGIN DESCRIPTION:
LONG BRANCH TRIBUTARY 3 7.0
END DESCRIPTION:
XS GIS Cut Line= 3
      2334325.00     13778325.00      2334225.00     13778125.00
      2334025.01     13778025.01
#Sta/Elev= 30
  4776.4  536.79  4790.4  536.52  4829.5  534.60  4874.2  533.03  4924.5  530.73
  4932.9  529.82  4941.3  526.83  4955.3  525.37  4963.7  525.67  4977.6  525.68
  4984.0  525.00  4984.3  524.50  4987.8  524.50  4988.0  525.00  4997.2  525.92
  5008.4  525.74  5022.4  526.71  5030.8  526.98  5036.3  529.07  5053.1  530.05
  5058.7  530.99  5075.5  532.01  5120.2  533.22  5142.6  534.13  5148.1  534.09
  5169.6  534.67  5187.3  535.56  5192.9  535.47  5215.2  537.11  5223.6  537.01
#Mann=4,-1,0
  4776.4    0.07       0  4984.0    0.05       0  4988.0    0.07       0
  5169.6    0.05       0
Bank Sta=4984,4988
Exp/Cntr=0.3,0.1

Type RM Length L Ch R = 1,3605,129,129,129
BEGIN DESCRIPTION:
A19760
END DESCRIPTION:
XS GIS Cut Line= 3
      2334430.88     13778294.25      2334268.93     13778021.88
      2333970.80     13777867.30
#Sta/Elev= 30
  4744.6  538.85  4773.1  537.16  4822.0  534.35  4827.8  533.08  4836.8  533.10
  4843.4  531.77  4859.0  531.04  4871.7  529.47  4875.6  530.51  4880.4  531.80
  4886.2  530.13  4901.8  531.57  4907.6  530.34  4917.4  530.57  4923.2  529.08
  4938.8  527.76  4944.7  526.16  4995.3  524.65  4995.5  524.15  4999.3  524.65
  5024.5  525.40  5060.4  529.52  5085.0  530.66  5136.9  531.25  5168.4  532.09
  5278.6  536.09  5313.7  538.29  5358.8  538.78  5390.7  541.11  5397.3  541.33
#Mann=8,-1,0
  4744.6    0.07       0  4773.1   0.035       0  4875.6    0.07       0
  4995.3    0.05       0  4999.3    0.07       0  5136.9    0.05       0
  5168.4   0.035       0  5390.7    0.05       0
Bank Sta=4995.3,4999.3
Exp/Cntr=0.3,0.1

Type RM Length L Ch R = 1,3476,189,189,189
BEGIN DESCRIPTION:
A19759
END DESCRIPTION:
XS GIS Cut Line= 3
      2334544.94     13778239.01      2334390.37     13778014.52
      2334052.54     13777779.50
#Sta/Elev= 30
  4794.1  539.98  4869.5  538.43  4920.3  536.67  4941.2  536.55  4962.2  535.20
  4977.1  535.12  4992.0  534.29  5000.7  533.28  5004.8  532.63  5005.4  532.54
  5012.9  526.05  5019.0  524.25  5025.8  523.88  5026.1  523.38  5029.6  523.38
  5029.8  523.88  5048.8  524.38  5066.7  524.30  5070.8  524.64  5076.9  526.26
  5091.8  528.29  5106.6  528.38  5121.5  528.63  5134.1  528.27  5286.5  531.14
  5326.4  531.96  5407.7  534.61  5464.5  537.55  5473.2  537.67  5478.2  538.34
#Mann=8,-1,0
  4794.1    0.07       0  5000.7   0.035       0  5004.8    0.07       0
  5025.8    0.05       0  5029.8    0.07       0  5106.6    0.05       0
  5286.5   0.035       0  5326.4    0.05       0
Bank Sta=5025.8,5029.8
Exp/Cntr=0.3,0.1

Type RM Length L Ch R = 1,3287,271,271,271
BEGIN DESCRIPTION:
LONG BRANCH TRIBUTARY 3 6.0
END DESCRIPTION:
XS GIS Cut Line= 3
      2334525.00     13777975.00      2334475.00     13777925.00
      2334174.98     13777624.98
#Sta/Elev= 28
  4929.3  534.63  4932.8  534.63  4971.7  532.60  4985.9  528.53  4996.5  524.04
  5000.0  524.04  5003.5  524.04  5026.3  522.43  5026.5  521.93  5030.0  521.93
  5030.3  522.43  5042.4  524.87  5056.6  526.53  5070.7  527.05  5099.0  525.87
  5113.2  526.33  5141.0  526.74  5141.4  526.75  5169.7  526.78  5184.6  526.99
  5198.0  527.17  5254.6  528.42  5276.4  528.76  5311.1  529.30  5325.3  529.72
  5410.1  533.13  5420.7  533.81  5424.3  533.81
#Mann=6,-1,0
  4929.3    0.07       0  5026.3    0.05       0  5030.3    0.07       0
  5141.0    0.05       0  5184.6   0.035       0  5276.4    0.05       0
Bank Sta=5026.3,5030.3
Exp/Cntr=0.3,0.1

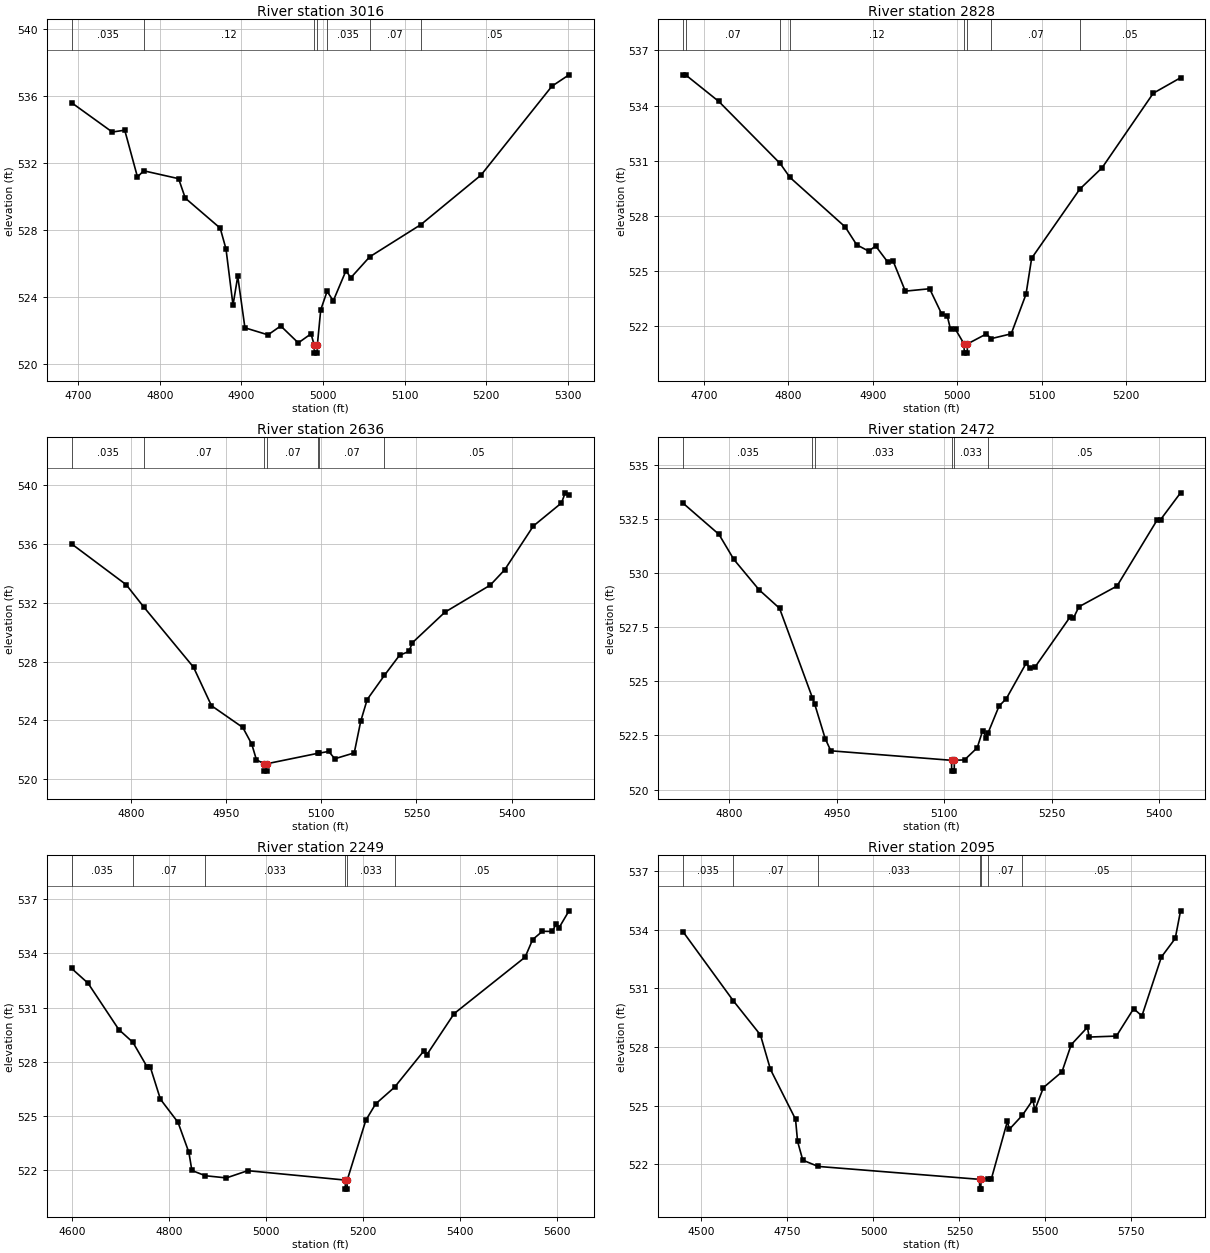
Type RM Length L Ch R = 1,3016,188,188,188
BEGIN DESCRIPTION:
A19758
END DESCRIPTION:
XS GIS Cut Line= 3
      2334647.99     13777882.03      2334342.53     13777701.71
      2334130.93     13777559.42
#Sta/Elev= 30
  4691.8  535.58  4741.7  533.83  4757.0  533.94  4772.6  531.15  4780.2  531.52
  4823.0  531.05  4831.2  529.89  4874.0  528.10  4881.1  526.86  4889.7  523.51
  4895.5  525.23  4904.3  522.16  4932.6  521.74  4948.2  522.27  4969.7  521.26
  4985.3  521.80  4989.1  521.15  4989.4  520.65  4992.9  520.65  4993.1  521.15
  4997.2  523.23  5005.0  524.33  5012.6  523.77  5028.2  525.57  5034.0  525.14
  5057.2  526.39  5119.9  528.31  5193.6  531.26  5280.5  536.56  5301.5  537.24
#Mann=7,-1,0
  4691.8   0.035       0  4780.2    0.12       0  4989.1    0.05       0
  4993.1    0.12       0  5005.0   0.035       0  5057.2    0.07       0
  5119.9    0.05       0
Bank Sta=4989.1,4993.1
Exp/Cntr=0.3,0.1

Type RM Length L Ch R = 1,2828,192,192,192
BEGIN DESCRIPTION:
LONG BRANCH TRIBUTARY 3 5.0
END DESCRIPTION:
XS GIS Cut Line= 3
      2334674.98     13777774.99      2334425.00     13777575.00
      2334174.99     13777475.00
#Sta/Elev= 30
  4675.1  535.67  4678.6  535.65  4717.5  534.22  4790.1  530.85  4801.8  530.09
  4867.2  527.40  4880.8  526.43  4895.2  526.08  4903.2  526.37  4917.6  525.49
  4924.0  525.54  4938.4  523.91  4967.2  524.04  4981.6  522.66  4988.0  522.58
  4992.0  521.83  4997.9  521.83  5008.0  521.04  5008.3  520.54  5011.8  520.54
  5012.0  521.04  5034.3  521.58  5040.4  521.33  5063.9  521.59  5081.4  523.74
  5088.1  525.70  5145.2  529.46  5171.6  530.62  5232.2  534.67  5264.5  535.51
#Mann=8,-1,0
  4675.1   0.035       0  4678.6    0.07       0  4790.1   0.035       0
  4801.8    0.12       0  5008.0    0.05       0  5012.0    0.12       0
  5040.4    0.07       0  5145.2    0.05       0
Bank Sta=5008,5012
Exp/Cntr=0.3,0.1

Type RM Length L Ch R = 1,2636,164,164,164
BEGIN DESCRIPTION:
A19757
END DESCRIPTION:
XS GIS Cut Line= 3
      2334751.02     13777690.66      2334478.70     13777396.25
      2334103.31     13777318.97
#Sta/Elev= 30
  4706.3  536.01  4792.5  533.23  4819.9  531.73  4898.6  527.62  4926.9  525.00
  4976.3  523.52  4990.4  522.39  4997.8  521.32  5010.0  521.05  5010.2  520.55
  5013.7  520.55  5014.0  521.05  5095.5  521.77  5096.4  521.77  5111.8  521.89
  5121.3  521.39  5152.0  521.79  5162.2  523.94  5172.4  525.42  5199.5  527.06
  5223.4  528.43  5238.1  528.69  5243.8  529.29  5294.9  531.36  5366.4  533.20
  5389.1  534.24  5434.3  537.22  5478.7  538.79  5484.6  539.48  5490.6  539.31
#Mann=7,-1,0
  4706.3   0.035       0  4819.9    0.07       0  5010.0    0.05       0
  5014.0    0.07       0  5095.5   0.033       0  5096.4    0.07       0
  5199.5    0.05       0
Bank Sta=5010,5014
Exp/Cntr=0.3,0.1

Type RM Length L Ch R = 1,2472,223,223,223
BEGIN DESCRIPTION:
LONG BRANCH TRIBUTARY 3 4.0
END DESCRIPTION:
XS GIS Cut Line= 3
      2334824.97     13777524.97      2334525.00     13777275.00
      2334225.01     13777225.00
#Sta/Elev= 30
  4735.3  533.24  4785.4  531.80  4806.2  530.64  4841.3  529.24  4870.0  528.38
  4915.8  524.25  4919.0  523.96  4933.8  522.35  4941.6  521.79  5110.1  521.35
  5110.4  520.85  5113.9  520.85  5114.1  521.35  5128.3  521.37  5146.0  521.93
  5153.6  522.72  5158.7  522.40  5161.2  522.62  5176.5  523.86  5186.6  524.20
  5214.5  525.85  5219.5  525.60  5227.1  525.68  5275.3  527.96  5280.4  527.93
  5288.0  528.45  5341.2  529.41  5397.0  532.45  5402.0  532.48  5429.9  533.72
#Mann=6,-1,0
  4735.3   0.035       0  4915.8    0.07       0  4919.0   0.033       0
  5110.1   0.033       0  5114.1   0.033       0  5161.2    0.05       0
Bank Sta=5110.1,5114.1
Exp/Cntr=0.3,0.1

Type RM Length L Ch R = 1,2249,154,154,154
BEGIN DESCRIPTION:
A19756
END DESCRIPTION:
XS GIS Cut Line= 3
      2334894.55     13777462.50      2334659.02     13777138.64
      2334040.78     13777046.64
#Sta/Elev= 30
  4598.5  533.17  4632.5  532.35  4695.9  529.79  4725.1  529.08  4754.6  527.71
  4760.8  527.72  4781.7  525.94  4818.0  524.66  4840.4  523.00  4846.6  522.00
  4874.4  521.71  4917.7  521.59  4961.7  521.99  5162.8  521.47  5163.0  520.97
  5166.5  520.97  5166.8  521.47  5205.2  524.78  5225.4  525.68  5264.3  526.60
  5325.4  528.63  5330.5  528.38  5387.2  530.67  5533.5  533.79  5549.0  534.76
  5569.2  535.22  5589.4  535.21  5597.8  535.64  5602.9  535.39  5624.0  536.35
#Mann=6,-1,0
  4598.5   0.035       0  4725.1    0.07       0  4874.4   0.033       0
  5162.8   0.033       0  5166.8   0.033       0  5264.3    0.05       0
Bank Sta=5162.8,5166.8
Exp/Cntr=0.3,0.1

Type RM Length L Ch R = 1,2095,221,221,221
BEGIN DESCRIPTION:
A19755
END DESCRIPTION:
XS GIS Cut Line= 3
      2334975.50     13777455.11      2334614.86     13776884.71
      2333849.73     13776785.39
#Sta/Elev= 30
  4446.5  533.89  4592.7  530.36  4671.4  528.62  4700.5  526.86  4773.5  524.31
  4779.4  523.18  4794.6  522.22  4839.1  521.90  5308.5  521.24  5308.8  520.74
  5312.3  520.74  5312.5  521.24  5334.3  521.27  5343.1  521.28  5389.7  524.22
  5394.8  523.79  5433.3  524.52  5463.9  525.31  5468.9  524.77  5494.3  525.93
  5548.1  526.73  5575.0  528.12  5622.2  529.01  5627.2  528.51  5706.4  528.56
  5756.5  529.96  5780.6  529.59  5837.2  532.60  5877.5  533.55  5892.9  534.96
#Mann=7,-1,0
  4446.5   0.035       0  4592.7    0.07       0  4839.1   0.033       0
  5308.5   0.033       0  5312.5   0.033       0  5334.3    0.07       0
  5433.3    0.05       0
Bank Sta=5308.5,5312.5
Exp/Cntr=0.3,0.1

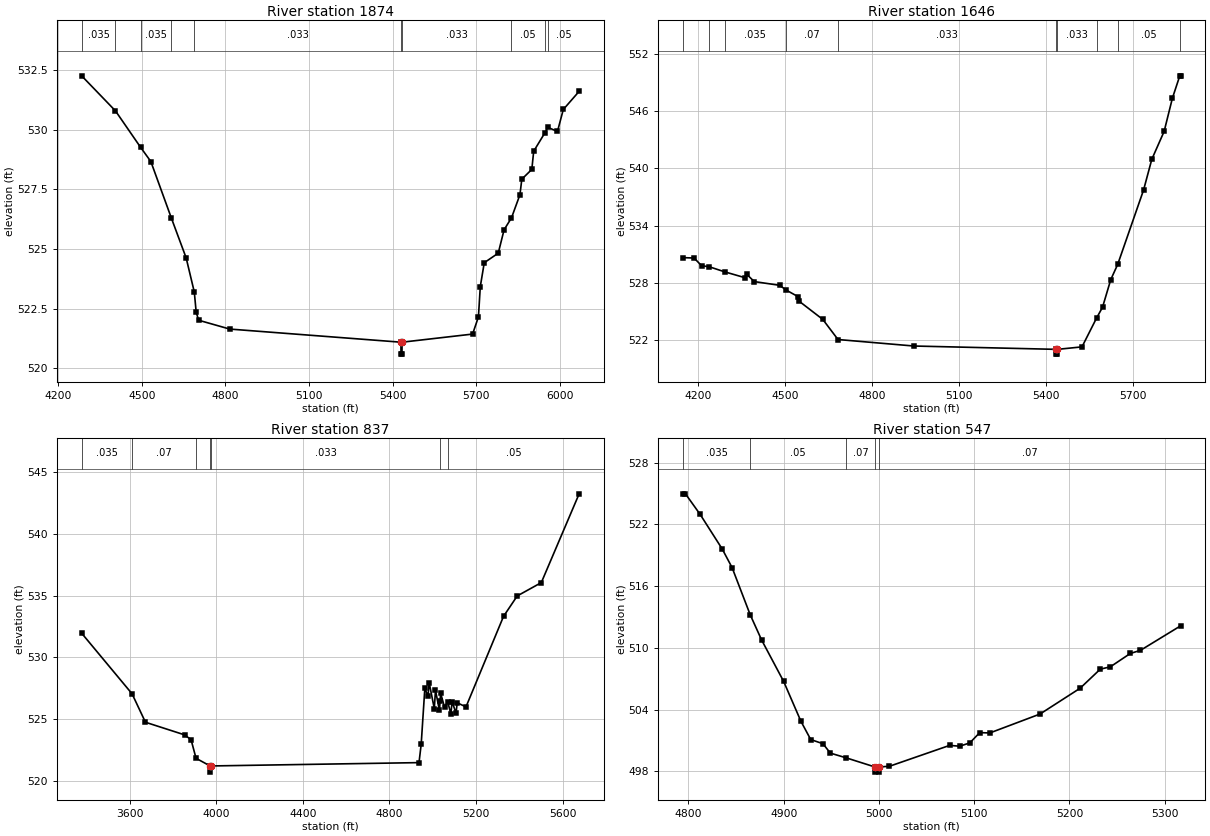
Type RM Length L Ch R = 1,1874,228,228,228
BEGIN DESCRIPTION:
A19754
END DESCRIPTION:
XS GIS Cut Line= 3
      2335030.70     13777410.94      2334677.42     13776697.02
      2333939.85     13776040.18
#Sta/Elev= 30
  4284.2  532.25  4405.5  530.78  4495.8  529.25  4532.3  528.66  4605.3  526.31
  4659.0  524.62  4688.2  523.19  4694.9  522.35  4703.7  522.01  4815.2  521.64
  5429.3  521.09  5429.5  520.59  5433.0  520.59  5433.3  521.09  5686.3  521.43
  5707.2  522.15  5713.9  523.42  5728.1  524.42  5778.3  524.82  5799.2  525.80
  5825.8  526.30  5856.1  527.27  5862.8  527.92  5898.7  528.33  5905.4  529.09
  5946.0  529.87  5956.1  530.09  5990.7  529.92  6011.6  530.84  6068.4  531.60
#Mann=10,-1,0
  4284.2   0.035       0  4405.5    0.07       0  4495.8   0.035       0
  4605.3    0.07       0  4688.2   0.033       0  5429.3   0.033       0
  5433.3   0.033       0  5825.8    0.05       0  5946.0   0.035       0
  5956.1    0.05       0
Bank Sta=5429.3,5433.3
Exp/Cntr=0.3,0.1

Type RM Length L Ch R = 1,1646,809,809,809
BEGIN DESCRIPTION:
LONG BRANCH TRIBUTARY 3 3.0
END DESCRIPTION:
XS GIS Cut Line= 3
      2335071.21     13777359.49      2334625.00     13776075.00
      2334375.03     13775825.03
#Sta/Elev= 30
  4149.7  530.64  4187.7  530.60  4213.5  529.79  4239.3  529.69  4293.3  529.15
  4363.8  528.53  4369.1  528.89  4394.9  528.13  4482.6  527.74  4503.8  527.26
  4545.2  526.56  4550.5  526.05  4630.8  524.17  4683.3  522.06  4944.4  521.38
  5435.0  521.03  5435.2  520.53  5438.7  520.53  5439.0  521.03  5523.6  521.29
  5573.6  524.30  5594.3  525.44  5622.6  528.33  5646.8  529.95  5735.8  537.74
  5764.0  540.94  5806.5  543.87  5834.8  547.33  5860.4  549.69  5863.0  549.69
#Mann=10,-1,0
  4149.7   0.035       0  4239.3    0.07       0  4293.3   0.035       0
  4503.8    0.07       0  4683.3   0.033       0  5435.0   0.033       0
  5439.0   0.033       0  5573.6    0.07       0  5646.8    0.05       0
  5860.4   0.035       0
Bank Sta=5435,5439
Exp/Cntr=0.3,0.1

Type RM Length L Ch R = 1,837,290,290,290
BEGIN DESCRIPTION:
LONG BRANCH TRIBUTARY 3 2.0
END DESCRIPTION:
XS GIS Cut Line= 3
      2335100.64     13777458.81      2335218.41     13775876.35
      2334563.32     13775600.33
#Sta/Elev= 30
  3378.7  531.95  3611.6  527.04  3673.3  524.74  3853.8  523.72  3883.9  523.33
  3907.0  521.82  3972.2  521.20  3972.4  520.70  3976.2  521.20  4936.8  521.47
  4946.8  522.94  4963.7  527.48  4978.3  526.85  4983.7  527.95  5007.4  525.84
  5012.9  527.32  5031.2  525.70  5034.2  526.47  5036.6  527.09  5054.9  525.95
  5069.1  526.41  5084.0  525.41  5089.5  526.41  5107.8  525.47  5113.2  526.32
  5153.7  525.98  5327.3  533.32  5390.5  534.97  5501.7  536.05  5676.4  543.24
#Mann=7,-1,0
  3378.7   0.035       0  3611.6    0.07       0  3907.0   0.033       0
  3972.2   0.033       0  3976.2   0.033       0  5034.2   0.035       0
  5069.1    0.05       0
Bank Sta=3972.2,3976.2
Exp/Cntr=0.3,0.1

Type RM Length L Ch R = 1,547,0,0,0
BEGIN DESCRIPTION:
LONG BRANCH TRIBUTARY 3 1.0
END DESCRIPTION:
XS GIS Cut Line= 3
      2335375.01     13775924.97      2335425.00     13775725.00
      2335125.05     13775625.02
#Sta/Elev= 30
  4794.4  524.98  4796.9  524.98  4812.4  522.97  4835.6  519.60  4845.9  517.80
  4864.8  513.24  4876.8  510.78  4900.0  506.74  4918.1  502.87  4928.4  501.09
  4941.3  500.68  4949.0  499.77  4965.6  499.31  4995.9  498.42  4996.2  497.92
  4999.7  497.92  4999.9  498.42  5011.1  498.49  5074.3  500.52  5084.8  500.44
  5095.4  500.76  5105.9  501.76  5116.5  501.73  5169.2  503.57  5211.3  506.08
  5232.4  507.93  5243.0  508.16  5264.0  509.46  5274.6  509.76  5316.7  512.14
#Mann=5,-1,0
  4794.4   0.035       0  4864.8    0.05       0  4965.6    0.07       0
  4995.9    0.05       0  4999.9    0.07       0
Bank Sta=4995.9,4999.9
Exp/Cntr=0.3,0.1

Chan Stop Cuts=-1