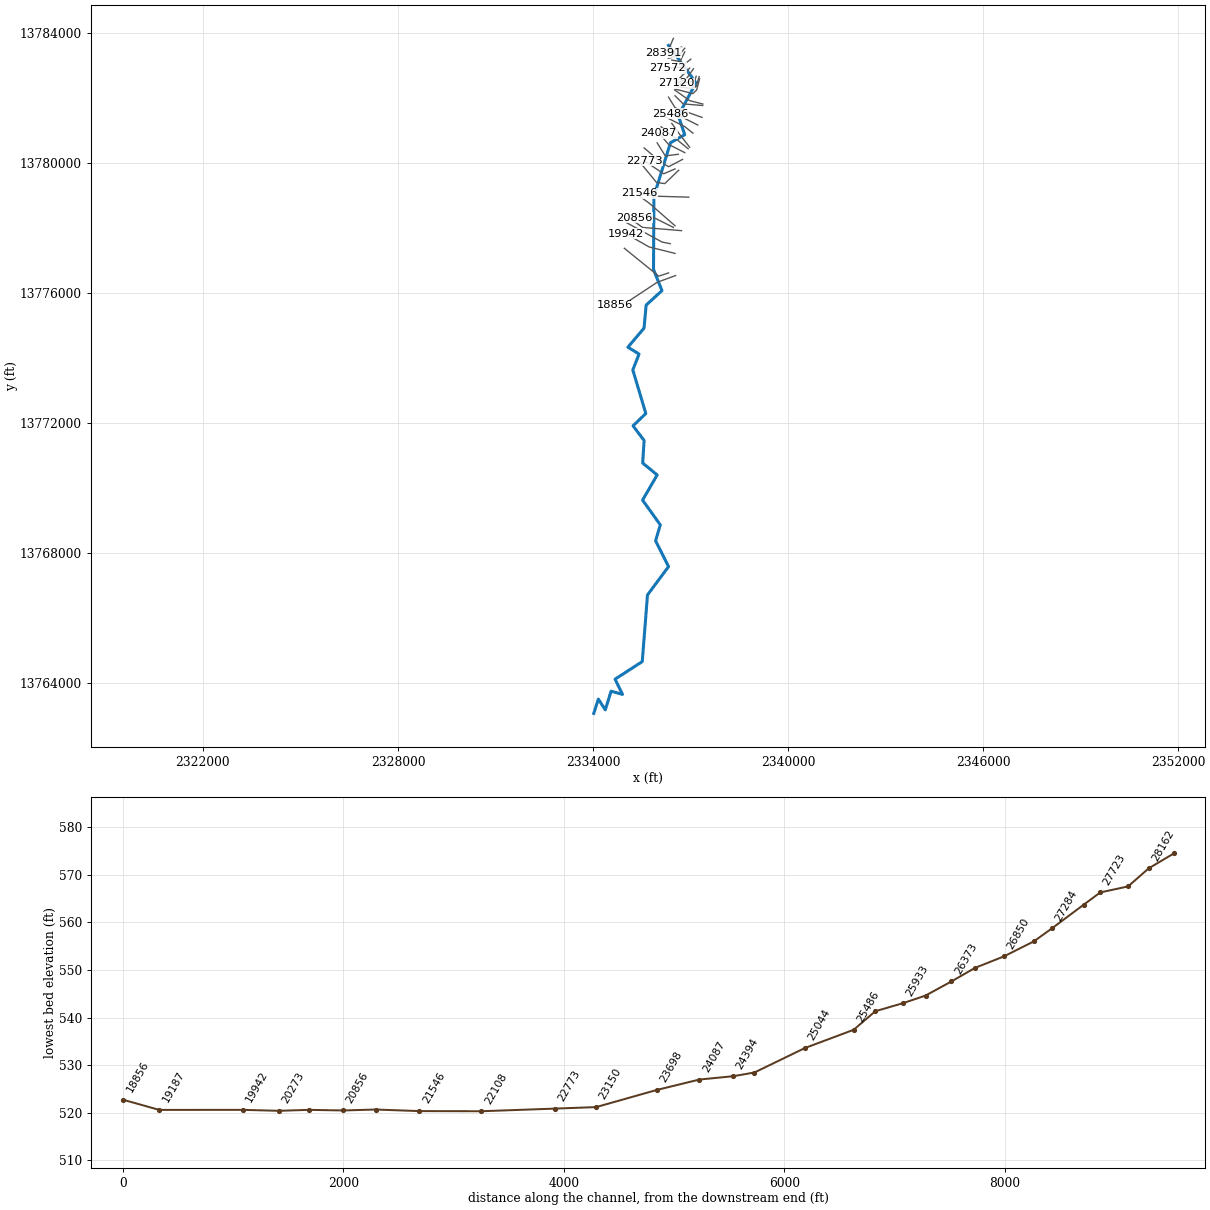
--- LONG BRANCH.prj (project) ---

Proj Title=LONG BRANCH Base Level Engineering
Current Plan=p01
Default Exp/Contr=0.3,0.1
English Units
Geom File=g01
Flow File=f01
Plan File=p01
Y Axis Title=Elevation
X Axis Title(PF)=Main Channel Distance
X Axis Title(XS)=Station
BEGIN DESCRIPTION:
LONG BRANCH
END DESCRIPTION:
DSS Export Rating Curves= 0
DSS Export Rating Curve Sorted= 0
DSS Export Volume Flow Curves= 0
DXF OffsetX= 0
DXF OffsetY= 0
DXF ScaleX= 1
DXF ScaleY= 10

--- LONG BRANCH.p01 (plan) ---

Plan Title=Multiple Run
Short Identifier=Multiple
Geom File=g01
Flow File=f01
Subcritical Flow
K Sum by GR= 0
Std Step Tol= 0.01
Critical Tol= 0.01
Num of Std Step Trials= 20
Max Error Tol= 0.3
Flow Tol Ratio= 0.001
Split Flow NTrial= 30
Split Flow Tol= 0.02
Split Flow Ratio= 0.02
Log Output Level= 0
Friction Slope Method= 1
Unsteady Friction Slope Method= 2
Unsteady Bridges Friction Slope Method= 1
Parabolic Critical Depth
Global Vel Dist=  1 , 1 , 1
Global Log Level= 0
CheckData=True
Encroach Param= -1, 0, 0, 0
BEGIN DESCRIPTION:
Multiple Run
END DESCRIPTION:

--- LONG BRANCH.f01 (steady flow) ---

Flow Title=Multiple
Number of Profiles=7
Profile Names=10-year,25-year,50-year,1pct_min,100-year,1pct_plu,500-year
River Rch & RM= LONG BRANCH,Reach-1,28391
     246     376     488     308     614    1226     962
River Rch & RM= LONG BRANCH,Reach-1,26138
     685    1112    1500     979    1954    3899    3287
River Rch & RM= LONG BRANCH,Reach-1,21546
    1140    1895    2595    1717    3427    6837    5924
River Rch & RM= LONG BRANCH,Reach-1,17239
    1371    2309    3191    2130    4249    8478    7474
River Rch & RM= LONG BRANCH,Reach-1,14493
    1559    2642    3666    2456    4901    9778    8688
River Rch & RM= LONG BRANCH,Reach-1,12152
    1753    2980    4143    2780    5547   11068    9864
River Rch & RM= LONG BRANCH,Reach-1,7658
    1894    3232    4505    3030    6045   12061   10798
River Rch & RM= LONG BRANCH,Reach-1,4511
    1956    3340    4657    3133    6252   12474   11175
River Rch & RM= LONG BRANCH,Reach-1,2767
    2039    3484    4862    3272    6528   13026   11678
Boundary for River Rch & Prof#=LONG BRANCH,Reach-1,1
Up Type=0
Dn Type=3
Dn Slope=0.005
Boundary for River Rch & Prof#=LONG BRANCH,Reach-1,2
Up Type=0
Dn Type=3
Dn Slope=0.005
Boundary for River Rch & Prof#=LONG BRANCH,Reach-1,3
Up Type=0
Dn Type=3
Dn Slope=0.005
Boundary for River Rch & Prof#=LONG BRANCH,Reach-1,4
Up Type=0
Dn Type=3
Dn Slope=0.005
Boundary for River Rch & Prof#=LONG BRANCH,Reach-1,5
Up Type=0
Dn Type=3
Dn Slope=0.005
Boundary for River Rch & Prof#=LONG BRANCH,Reach-1,6
Up Type=0
Dn Type=3
Dn Slope=0.005
Boundary for River Rch & Prof#=LONG BRANCH,Reach-1,7
Up Type=0
Dn Type=3
Dn Slope=0.005

--- LONG BRANCH.g01 (geometry) ---

Geom Title=Existing Conditions
Program Version=4.10

River Reach=LONG BRANCH     ,Reach-1
Reach XY= 30
        2336325.       13783625.      2337167.96      13782475.2
      2336625.54     13781463.92      2336821.48     13780875.99
       2336384.3     13780631.67      2335874.82       13778981.
      2335862.17     13776730.68      2336123.18     13776081.12
      2335636.09     13775635.08      2335571.46     13774926.46
      2335074.44     13774340.25      2335417.35      13774128.7
      2335225.52     13773640.22       2335625.6     13772300.28
       2335232.6     13771921.68      2335573.14     13771469.23
      2335528.75     13770776.55      2335974.77     13770409.79
      2335525.75     13769635.68      2336071.54      13768873.5
      2335926.04     13768385.44      2336324.76     13767590.22
      2335677.14     13766719.03      2335515.97     13764667.98
      2334680.06     13764127.32      2334908.59      13763658.2
      2334557.92     13763758.88      2334378.58     13763182.48
      2334164.83     13763514.24        2334025.       13763075.

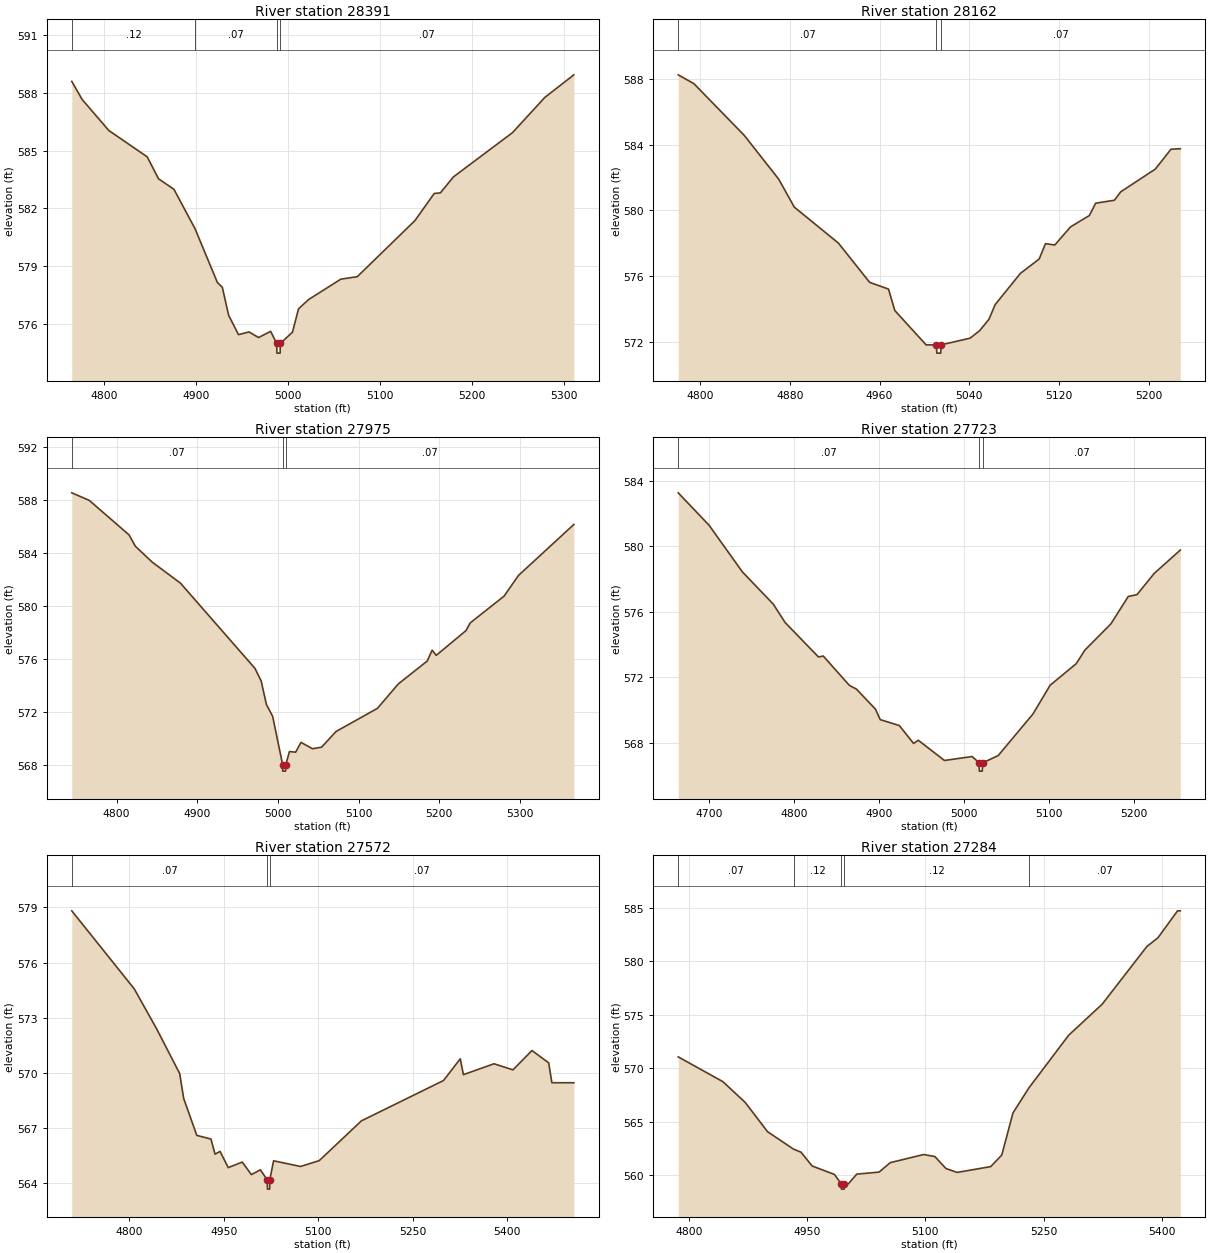
Type RM Length L Ch R = 1 ,28391   ,229,229,229
BEGIN DESCRIPTION:
A19725
END DESCRIPTION:
XS GIS Cut Line= 3
       2336473.8     13783841.86      2336351.85     13783556.24
      2336175.91      13783399.5
#Sta/Elev= 30
    4765  588.59  4776.3  587.65  4805.3  586.04  4847.1  584.67  4859.4  583.53
  4876.1  582.99  4899.1  580.94  4923.4  578.15  4928.8   577.9  4935.6  576.45
  4946.4  575.44  4957.8  575.58  4968.2  575.29  4981.4  575.61  4987.9  574.98
  4988.2  574.48  4991.7  574.48  4991.9  574.98  5005.1  575.57  5011.7  576.78
  5022.6  577.26  5057.7  578.32  5075.6  578.45  5138.3  581.36  5159.3  582.77
    5166   582.8  5180.2  583.63  5244.5  585.93  5279.7  587.76  5311.2  588.93
#Mann= 4 ,-1 , 0
    4765     .12       0  4899.1     .07       0  4987.9     .05       0
  4991.9     .07       0
Bank Sta=4987.9,4991.9
XS Rating Curve= 0 ,0
Exp/Cntr=0.3,0.1

Type RM Length L Ch R = 1 ,28162   ,187,187,187
BEGIN DESCRIPTION:
LONG BRANCH 56.0
END DESCRIPTION:
XS GIS Cut Line= 3
      2336725.03     13783575.01        2336525.       13783475.
      2336325.04     13783375.02
#Sta/Elev= 30
  4780.7  588.24  4794.7   587.7  4839.4  584.57  4870.2   581.9  4884.1   580.2
  4923.3  578.02  4951.2  575.63    4968  575.22  4973.6  573.92  5001.5  571.83
  5010.7  571.83    5011  571.33  5014.5  571.33  5014.7  571.83  5040.7  572.24
  5049.1  572.69  5057.4  573.38    5063  574.28  5085.4  576.17  5102.2  577.05
  5107.8  577.98  5116.1   577.9  5130.1     579  5146.9  579.69  5152.5  580.44
  5169.2  580.62  5174.8  581.13  5205.6  582.51  5219.6  583.72  5227.9  583.75
#Mann= 3 ,-1 , 0
  4780.7     .07       0  5010.7     .05       0  5014.7     .07       0
Bank Sta=5010.7,5014.7
XS Rating Curve= 0 ,0
Exp/Cntr=0.3,0.1

Type RM Length L Ch R = 1 ,27975   ,252,252,252
BEGIN DESCRIPTION:
A19724
END DESCRIPTION:
XS GIS Cut Line= 3
      2336823.66     13783536.99      2336624.66     13783302.69
      2336318.24     13783229.27
#Sta/Elev= 30
  4744.4  588.55  4766.1  587.98  4815.5  585.37  4823.2  584.52  4844.1  583.32
  4879.2  581.73  4971.5   575.3  4979.2  574.35  4985.7  572.58  4993.5  571.67
  5005.8  568.04    5006  567.54  5009.5  567.54  5009.8  568.04  5014.3  569.02
    5022  568.97  5028.6  569.71  5042.9  569.23  5054.2  569.35    5072  570.53
  5123.4  572.28  5149.2  574.12  5185.1  575.85  5191.2  576.67  5196.3  576.28
  5233.2  578.15  5238.4  578.73  5280.4  580.75  5298.2  582.31  5366.9  586.16
#Mann= 3 ,-1 , 0
  4744.4     .07       0  5005.8     .05       0  5009.8     .07       0
Bank Sta=5005.8,5009.8
XS Rating Curve= 0 ,0
Exp/Cntr=0.3,0.1

Type RM Length L Ch R = 1 ,27723   ,151,151,151
BEGIN DESCRIPTION:
LONG BRANCH 55.0
END DESCRIPTION:
XS GIS Cut Line= 3
      2336824.98     13783424.96        2336675.       13783125.
      2336425.02       13783175.
#Sta/Elev= 30
    4664  583.25  4700.3  581.27  4739.4  578.43  4775.8  576.46  4789.7  575.34
  4828.9  573.24  4834.5   573.3  4865.2  571.51  4873.6  571.28    4896  570.05
  4901.5  569.42  4923.9  569.06  4940.7  567.97  4946.3  568.16    4977  566.93
  5009.6  567.17  5017.8  566.78    5018  566.28  5021.5  566.28  5021.8  566.78
  5040.2  567.23    5081  569.76  5101.3  571.52  5131.9  572.83  5142.1  573.66
  5172.7  575.26  5193.1  576.93  5203.3  577.04  5223.7  578.34  5254.3  579.76
#Mann= 3 ,-1 , 0
    4664     .07       0  5017.8     .05       0  5021.8     .07       0
Bank Sta=5017.8,5021.8
XS Rating Curve= 0 ,0
Exp/Cntr=0.3,0.1

Type RM Length L Ch R = 1 ,27572   ,288,288,288
BEGIN DESCRIPTION:
A19723
END DESCRIPTION:
XS GIS Cut Line= 3
      2337009.78     13783199.95      2336701.69     13782956.05
      2336298.67     13782927.26
#Sta/Elev= 30
  4708.6  578.81  4807.8  574.57    4843  572.42  4879.9  569.97  4886.3  568.61
  4907.1  566.61  4929.6  566.41    4936  565.59    4944  565.74    4957  564.86
  4979.3  565.16  4993.7  564.48    5008  564.74  5018.9  564.19  5019.2  563.69
  5022.7  563.69  5022.9  564.19    5029  565.23  5071.8  564.92  5101.5  565.24
  5168.4   567.4  5298.7  569.59  5325.3  570.77  5330.3  569.91  5378.9   570.5
    5409  570.17  5439.1  571.22  5465.7  570.55  5470.7  569.47  5505.6  569.47
#Mann= 3 ,-1 , 0
  4708.6     .07       0  5018.9     .05       0  5022.9     .07       0
Bank Sta=5018.9,5022.9
XS Rating Curve= 0 ,0
Exp/Cntr=0.3,0.1

Type RM Length L Ch R = 1 ,27284   ,164,164,164
BEGIN DESCRIPTION:
LONG BRANCH 54.0
END DESCRIPTION:
XS GIS Cut Line= 3
      2336975.01     13782925.01        2336825.       13782775.
      2336525.01     13782475.01
#Sta/Elev= 30
  4786.7  571.06  4843.3  568.75  4871.6  566.81  4899.9  564.08  4932.9  562.45
  4942.3  562.17  4956.4  560.88  4984.7  560.09  4993.3  559.22  4993.6  558.72
  4997.1  558.72  4997.3  559.22  5002.4  559.22    5013  560.12  5041.3  560.31
  5055.4  561.19  5097.8  561.95    5112  561.76  5126.1  560.64  5140.3  560.28
  5182.7  560.82  5196.8   561.9    5211  565.83  5231.2  568.17  5281.7  573.09
  5324.1  575.98  5380.7  581.36  5394.8  582.18  5419.6  584.69  5423.1  584.69
#Mann= 5 ,-1 , 0
  4786.7     .07       0  4932.9     .12       0  4993.3     .05       0
  4997.3     .12       0  5231.2     .07       0
Bank Sta=4993.3,4997.3
XS Rating Curve= 0 ,0
Exp/Cntr=0.3,0.1

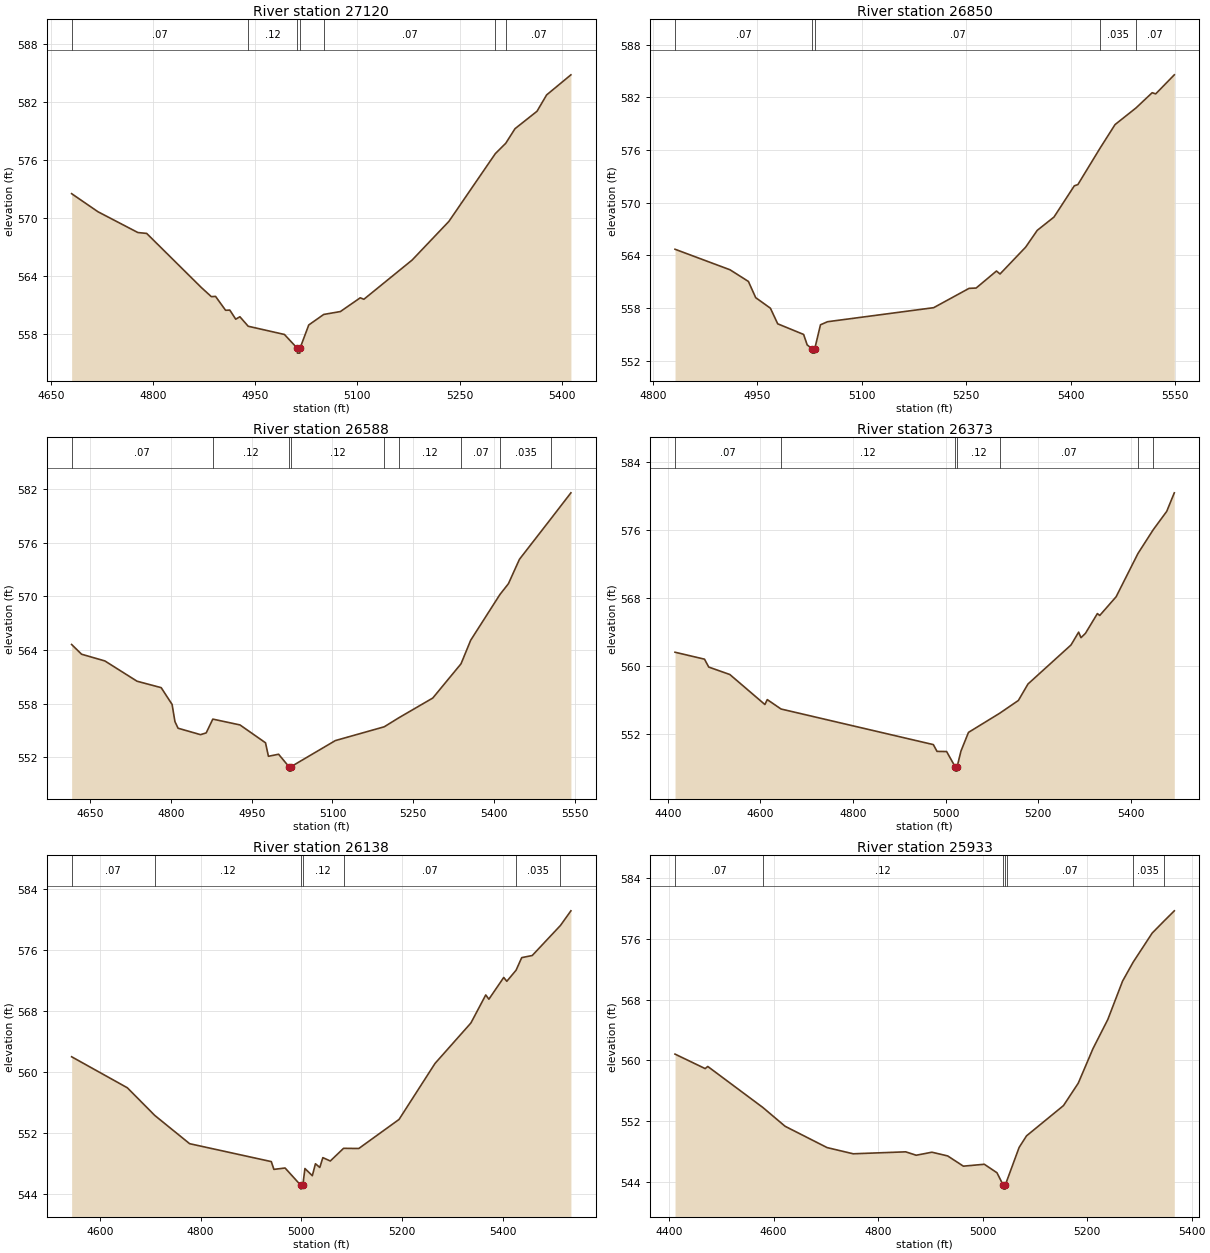
Type RM Length L Ch R = 1 ,27120   ,270,270,270
BEGIN DESCRIPTION:
A19722
END DESCRIPTION:
XS GIS Cut Line= 3
      2337090.07     13782904.72      2336865.38     13782583.74
      2336548.85     13782455.85
#Sta/Elev= 30
  4680.3  572.48    4719  570.61  4777.6  568.46  4790.5  568.37  4870.7  562.78
  4885.5  561.83  4891.6  561.86  4906.4  560.42  4912.6  560.44  4921.3   559.5
  4927.4  559.75  4939.6  558.77  4992.8  557.92  5011.7  556.49  5011.9  555.99
  5015.4  555.99  5015.7  556.49  5028.5   558.9  5050.5  559.99    5075  560.29
  5104.1  561.71  5109.5  561.56  5180.4  565.62  5234.3  569.61  5302.5  576.62
  5317.8  577.69  5331.4   579.2  5363.7     581  5377.8  582.69  5413.5  584.77
#Mann= 7 ,-1 , 0
  4680.3     .07       0  4939.6     .12       0  5011.7     .05       0
  5015.7     .12       0  5050.5     .07       0  5302.5    .035       0
  5317.8     .07       0
Bank Sta=5011.7,5015.7
XS Rating Curve= 0 ,0
Exp/Cntr=0.3,0.1

Type RM Length L Ch R = 1 ,26850   ,262,262,262
BEGIN DESCRIPTION:
LONG BRANCH 53.0
END DESCRIPTION:
XS GIS Cut Line= 3
      2337174.98     13782674.95        2337125.       13782525.
      2336574.98       13782425.
#Sta/Elev= 30
  4831.7  564.69  4910.7  562.35  4937.1  561.02  4947.6  559.17  4968.7  557.97
  4979.2  556.19  5016.4  554.98  5021.5  553.79  5028.4  553.35  5028.7  552.85
  5032.2  552.85  5032.4  553.35  5040.6  556.08  5050.8  556.43  5203.2  558.03
    5254  560.23  5264.2  560.27  5293.4  562.21  5298.5  561.87  5335.3  564.93
  5351.9  566.84    5376  568.36  5405.2  571.92  5410.3  572.06    5442  576.19
  5463.7   578.9  5493.7  580.79    5517  582.53  5522.1   582.4  5548.8  584.57
#Mann= 5 ,-1 , 0
  4831.7     .07       0  5028.4     .05       0  5032.4     .07       0
    5442    .035       0  5493.7     .07       0
Bank Sta=5028.4,5032.4
XS Rating Curve= 0 ,0
Exp/Cntr=0.3,0.1

Type RM Length L Ch R = 1 ,26588   ,215,215,215
BEGIN DESCRIPTION:
A19721
END DESCRIPTION:
XS GIS Cut Line= 4
      2337266.59     13782664.02      2337170.29     13782352.65
      2337029.07     13782301.29      2336579.89     13782352.63
#Sta/Elev= 30
    4615  564.61  4633.5  563.52  4676.8  562.77  4736.6   560.5  4781.5  559.78
  4801.8   557.9  4807.1  555.98  4812.9  555.24  4854.7  554.52  4865.2  554.72
  4877.5  556.26    4928  555.61  4975.5  553.61  4980.9   552.1  4999.8  552.33
    5019  550.94  5019.3  550.44  5022.8  550.44    5023  550.94  5105.4  553.86
  5196.2   555.4  5223.4  556.41  5286.5  558.62    5339  562.45    5357  565.09
  5411.3   570.2  5427.2  571.42  5447.6  574.14  5506.4   578.7  5543.3  581.58
#Mann= 9 ,-1 , 0
    4615     .07       0  4877.5     .12       0    5019     .05       0
    5023     .12       0  5196.2     .07       0  5223.4     .12       0
    5339     .07       0  5411.3    .035       0  5506.4     .07       0
Bank Sta=5019,5023
XS Rating Curve= 0 ,0
Exp/Cntr=0.3,0.1

Type RM Length L Ch R = 1 ,26373   ,235,235,235
BEGIN DESCRIPTION:
A19720
END DESCRIPTION:
XS GIS Cut Line= 4
      2337279.43     13782596.61      2337189.55     13782253.15
       2337070.8     13782140.81      2336529.15     13782281.83
#Sta/Elev= 30
  4415.5  561.61  4479.2  560.79  4488.3  559.86  4533.9  558.98  4609.6  555.44
  4614.7  556.02  4644.4  554.91  4973.3  550.71  4981.3  549.91    5002  549.89
  5020.6  548.08  5020.9  547.58  5024.4  547.58  5024.6  548.08    5033  549.95
  5049.2  552.15  5116.9  554.42    5157  555.92  5177.7  557.86  5270.7  562.47
  5287.1  563.98  5292.2  563.33  5301.7  563.83  5327.6  566.17  5332.7  565.95
  5368.1  568.16  5415.1  573.25  5448.1  576.06  5477.3  578.23  5493.7  580.42
#Mann= 7 ,-1 , 0
  4415.5     .07       0  4644.4     .12       0  5020.6     .05       0
  5024.6     .12       0  5116.9     .07       0  5415.1    .035       0
  5448.1     .07       0
Bank Sta=5020.6,5024.6
XS Rating Curve= 0 ,0
Exp/Cntr=0.3,0.1

Type RM Length L Ch R = 1 ,26138   ,205,205,205
BEGIN DESCRIPTION:
A19719
END DESCRIPTION:
XS GIS Cut Line= 3
      2337382.14     13781819.85      2336974.51     13781925.77
      2336509.55     13782256.05
#Sta/Elev= 30
  4543.9  561.97  4654.6   557.9  4709.1  554.27  4778.2  550.57  4940.4  548.22
  4945.6   547.2  4967.8  547.38    4999  545.11  4999.3  544.61    5003  545.11
  5007.2  547.31  5021.9  546.37  5028.1  547.94  5036.7  547.45  5042.8  548.74
  5057.6   548.3  5083.9  549.96  5114.2  549.94  5194.1  553.75  5265.5  561.09
  5336.8   566.4  5366.3  570.08  5372.5  569.52    5402  572.37  5408.1  571.87
  5426.5  573.32  5437.7  574.97  5458.6  575.25  5514.5  579.18  5535.4  581.11
#Mann= 7 ,-1 , 0
  4543.9     .07       0  4709.1     .12       0    4999     .05       0
    5003     .12       0  5083.9     .07       0  5426.5    .035       0
  5514.5     .07       0
Bank Sta=4999,5003
XS Rating Curve= 0 ,0
Exp/Cntr=0.3,0.1

Type RM Length L Ch R = 1 ,25933   ,251,251,251
BEGIN DESCRIPTION:
LONG BRANCH 52.0
END DESCRIPTION:
XS GIS Cut Line= 3
      2337374.97       13781775.        2336775.       13781825.
        2336525.       13782075.
#Sta/Elev= 30
  4411.2  560.82  4468.9  558.91  4473.9  559.19  4579.3  553.78  4621.9   551.3
  4702.2  548.49  4752.3  547.67  4852.7  547.93  4872.8  547.48  4902.9  547.88
    4933  547.39  4963.1  546.04  5003.2  546.29  5027.4  545.17  5039.5  543.51
  5039.8  543.01  5043.3  543.01  5043.5  543.51  5046.4  544.13  5069.8  548.51
    5084  550.04  5154.7  554.03    5183  556.99  5211.2  561.55  5239.5  565.38
  5267.8  570.45  5287.8  572.92  5324.4  576.78  5346.4  578.32  5366.8  579.72
#Mann= 7 ,-1 , 0
  4411.2     .07       0  4579.3     .12       0  5039.5     .05       0
  5043.5     .12       0  5046.4     .07       0  5287.8    .035       0
  5346.4     .07       0
Bank Sta=5039.5,5043.5
XS Rating Curve= 0 ,0
Exp/Cntr=0.3,0.1

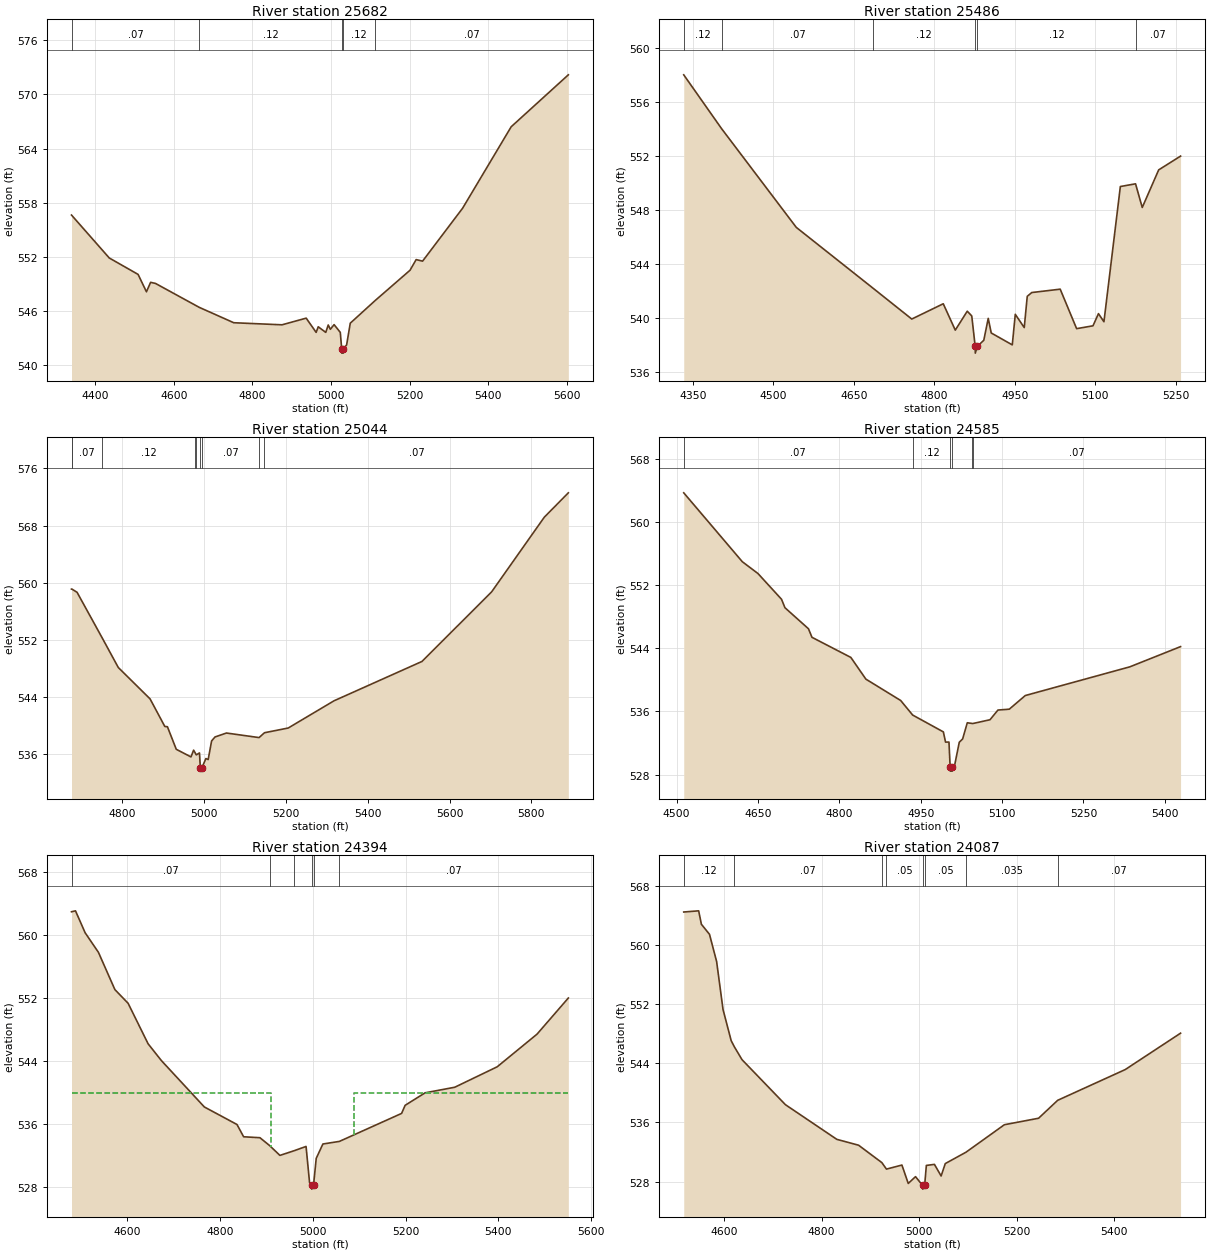
Type RM Length L Ch R = 1 ,25682   ,196,196,196
BEGIN DESCRIPTION:
A19717
END DESCRIPTION:
XS GIS Cut Line= 3
      2337354.69     13781408.99       2336526.6     13781705.86
      2336323.48     13782033.97
#Sta/Elev= 30
    4339  556.63  4435.2  551.87  4508.6  550.05  4529.9  548.12  4540.5  549.17
  4552.9  549.05  4664.2   546.4  4752.3  544.69  4875.3  544.46  4936.8   545.2
  4962.2  543.62  4967.5  544.24  4986.7  543.62    4993  544.44  4998.3  543.96
  5007.9  544.48  5023.7  543.62  5027.2  541.82  5027.4  541.32  5030.9  541.32
  5031.2  541.82  5039.8  542.22  5049.1  544.64  5112.2  547.14  5201.3  550.51
  5216.9  551.69  5233.3  551.52  5335.3  557.39    5459  566.42  5604.6  572.18
#Mann= 5 ,-1 , 0
    4339     .07       0  4664.2     .12       0  5027.2     .05       0
  5031.2     .12       0  5112.2     .07       0
Bank Sta=5027.2,5031.2
XS Rating Curve= 0 ,0
Exp/Cntr=0.3,0.1

Type RM Length L Ch R = 1 ,25486   ,442,442,442
BEGIN DESCRIPTION:
LONG BRANCH 51.0
END DESCRIPTION:
XS GIS Cut Line= 3
      2337225.04     13781174.98        2336625.       13781475.
      2336375.02       13781525.
#Sta/Elev= 30
  4332.9     558  4403.6  554.01  4542.6  546.72  4686.3   542.2  4757.8  539.94
  4816.5  541.07  4838.9  539.12  4861.2  540.52  4869.6  540.17    4876  537.92
  4876.2  537.42    4880  537.92    4892  538.37  4900.3  539.99  4905.9  538.91
  4945.1  538.03  4950.7  540.29  4967.4  539.31    4973  541.62  4981.4   541.9
  5034.4  542.15    5065  539.23  5095.5  539.44  5105.7  540.34  5115.9  539.74
  5146.5  549.74  5174.8  549.94  5187.3  548.19  5217.9  550.97  5258.7  551.99
#Mann= 6 ,-1 , 0
  4332.9     .12       0  4403.6     .07       0  4686.3     .12       0
    4876     .05       0    4880     .12       0  5174.8     .07       0
Bank Sta=4876,4880
XS Rating Curve= 0 ,0
Exp/Cntr=0.3,0.1

Type RM Length L Ch R = 1 ,25044   ,459,459,459
BEGIN DESCRIPTION:
LONG BRANCH 50.0
END DESCRIPTION:
XS GIS Cut Line= 3
      2337074.98     13780925.02        2336825.       13781125.
      2336024.96     13781525.02
#Sta/Elev= 30
  4675.9   559.1  4676.9   559.1  4689.5  558.65    4751  552.25  4790.3  548.11
    4868  543.71    4904  539.85  4910.4  539.81    4932  536.65    4968  535.58
  4974.4  536.53  4977.5  536.22  4980.9  535.87  4988.8  536.14  4990.8  534.09
    4991  533.59  4994.9  534.09  5004.4  535.35    5010  535.21  5018.4  537.82
  5026.8  538.38  5054.7  538.93  5134.4  538.29  5147.7  538.97  5205.7  539.63
  5317.5  543.44  5532.7  548.96  5703.2  558.73  5831.8  569.18  5890.5  572.59
#Mann= 9 ,-1 , 0
  4675.9    .035       0  4676.9     .07       0    4751     .12       0
  4977.5     .05       0  4980.9     .07       0  4990.8     .05       0
  4994.9     .07       0  5134.4     .12       0  5147.7     .07       0
Bank Sta=4990.8,4994.9
XS Rating Curve= 0 ,0
Exp/Cntr=0.3,0.1

Type RM Length L Ch R = 1 ,24585   ,191,191,191
BEGIN DESCRIPTION:
LONG BRANCH 49.0
END DESCRIPTION:
XS GIS Cut Line= 3
      2336974.49     13780492.35        2336675.       13780875.
      2336425.02     13781224.97
#Sta/Elev= 30
  4513.1  563.71  4621.1  554.98    4650  553.48  4693.4  550.22  4699.7  549.15
  4743.1  546.48  4749.5   545.4  4821.2  542.85  4848.9   540.1  4913.1  537.39
  4935.1  535.55  4991.8  533.41  4995.8  532.12  5002.1  532.12  5004.3  528.94
  5004.6  528.44  5008.2  528.44  5008.4  528.94  5012.5  529.17  5021.1   532.1
  5027.3  532.52  5035.9  534.57  5044.8  534.48  5045.9  534.47  5077.7  534.95
  5092.4  536.18  5113.3  536.29  5142.8  538.02  5335.7  541.66  5429.1  544.22
#Mann= 6 ,-1 , 0
  4513.1     .07       0  4935.1     .12       0  5004.3     .05       0
  5008.4     .12       0  5044.8     .05       0  5045.9     .07       0
Bank Sta=5004.3,5008.4
XS Rating Curve= 0 ,0
Exp/Cntr=0.3,0.1

Type RM Length L Ch R = 1 ,24394   ,307,307,307
BEGIN DESCRIPTION:
A19718
END DESCRIPTION:
XS GIS Cut Line= 2
      2336927.68     13780445.41      2336095.84     13781121.28
#Sta/Elev= 30
  4479.4  562.95    4488  563.07  4508.8  560.28  4537.5  557.79    4573  553.05
  4601.5  551.31  4644.6  546.16  4673.3  544.02    4766  538.12  4836.4  535.89
  4850.7  534.33  4885.9  534.21  4906.6  533.22    4929  531.96  4959.9  532.56
  4985.4   533.1    4993  528.48  4997.4  528.17  4997.6  527.67  5001.5  528.17
  5007.3  531.58  5021.7  533.41  5057.3  533.74  5191.5   537.3  5199.1  538.33
  5242.2  539.92  5306.2  540.63  5397.7  543.23  5483.6  547.38  5551.2  551.98
#Mann= 6 ,-1 , 0
  4479.4     .07       0  4906.6     .12       0  4959.9     .05       0
  4997.4     .05       0  5001.5     .05       0  5057.3     .07       0
#XS Ineff= 2 , 0
       0  4910.4  539.94  5089.6       0  539.94
Permanent Ineff=
       F       F
Bank Sta=4997.4,5001.5
XS Rating Curve= 0 ,0
Exp/Cntr=0.3,0.1

Type RM Length L Ch R = 1 ,24087   ,389,389,389
BEGIN DESCRIPTION:
LONG BRANCH 48.0
END DESCRIPTION:
XS GIS Cut Line= 3
      2336825.04     13780324.98      2336323.47     13780580.86
        2336025.     13780924.99
#Sta/Elev= 30
  4517.3   564.5  4547.9  564.66  4553.5  562.84  4570.1  561.48  4584.7   557.8
  4597.9  551.28  4614.6  547.07  4621.3  546.22  4636.8   544.5  4725.7  538.41
  4831.2  533.71  4875.7  532.92  4923.5  530.56  4932.9  529.68  4964.6  530.23
  4977.6  527.74  4992.5  528.66    5007  527.47  5007.3  526.97  5011.2  527.47
  5014.7  530.18  5031.3  530.32    5045  528.75  5053.5  530.43    5096  531.97
  5174.6  535.69  5244.8  536.57    5284     539  5422.4  543.16  5535.9  548.09
#Mann= 8 ,-1 , 0
  4517.3     .12       0  4621.3     .07       0  4923.5     .12       0
  4932.9     .05       0    5007     .05       0  5011.2     .05       0
    5096    .035       0    5284     .07       0
Bank Sta=5007,5011.2
XS Rating Curve= 0 ,0
Exp/Cntr=0.3,0.1

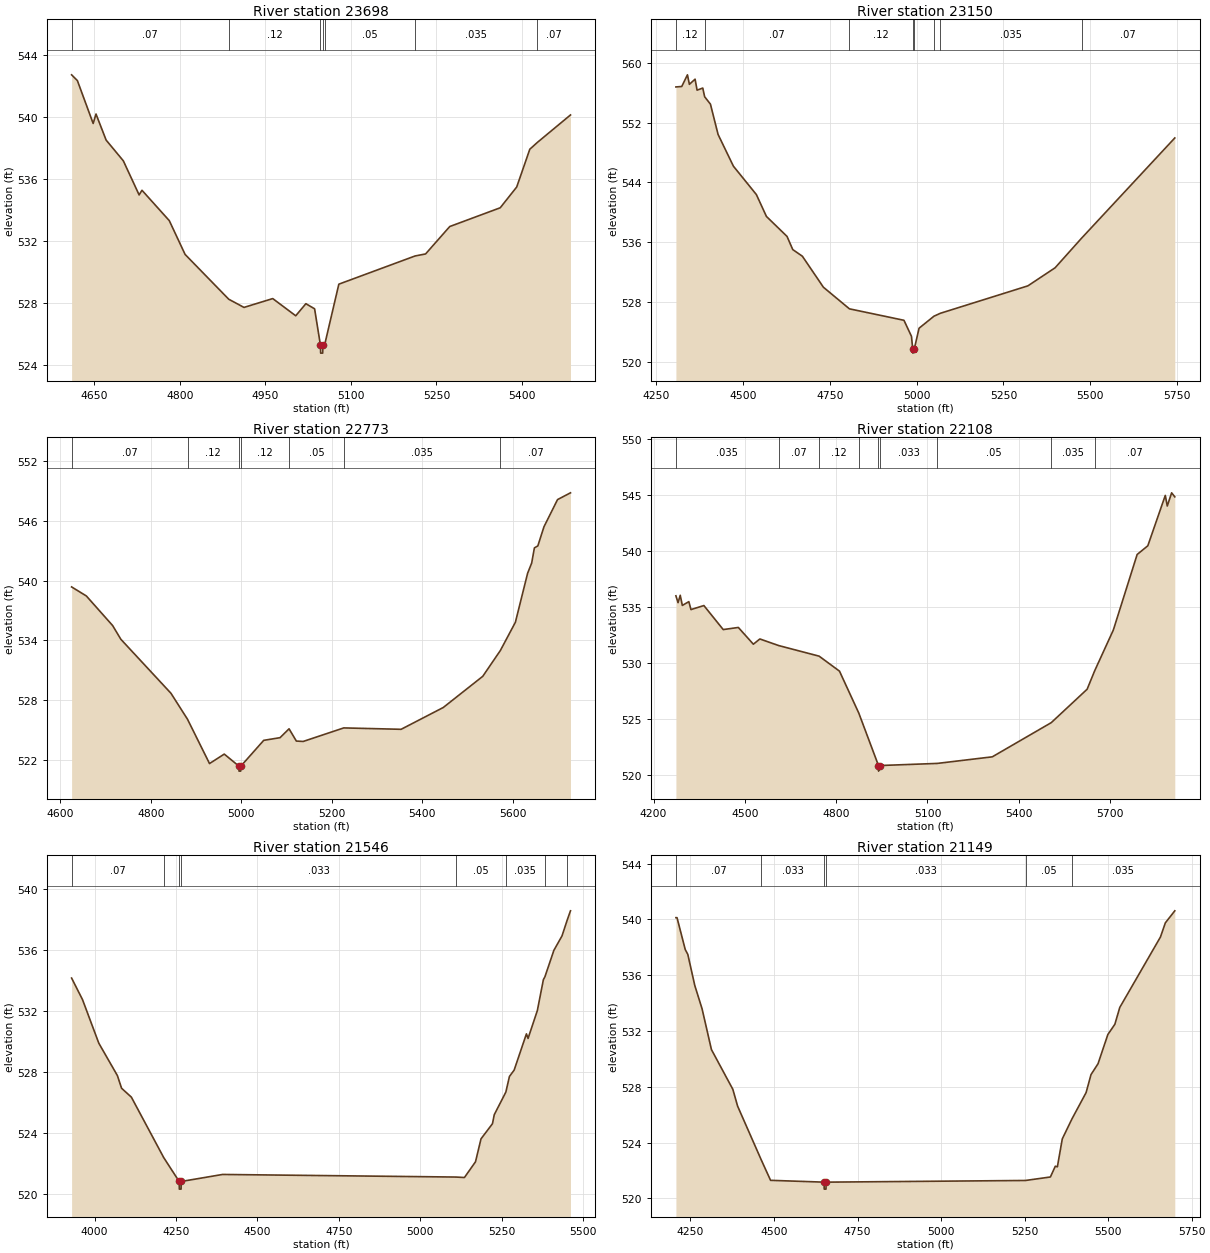
Type RM Length L Ch R = 1 ,23698   ,548,548,548
BEGIN DESCRIPTION:
LONG BRANCH 47.0
END DESCRIPTION:
XS GIS Cut Line= 3
      2336624.99       13780275.        2336225.       13780225.
        2335975.       13780625.
#Sta/Elev= 30
  4610.3  542.73  4620.4  542.36  4648.1  539.59  4653.1   540.2  4670.8  538.52
    4701  537.18  4728.7  534.98  4733.7  535.28  4781.6  533.32  4809.3  531.14
  4885.8  528.25  4912.6  527.72    4963  528.29  5003.3  527.18  5021.1  527.96
  5036.4  527.63  5046.7  525.27    5047  524.77  5050.6  524.77  5050.9  525.27
  5054.3  525.35  5078.9  529.22  5212.6  531.04    5231  531.17  5273.4  532.94
  5361.9  534.15  5390.8  535.49  5413.8  537.93  5427.1  538.37  5485.1  540.14
#Mann= 7 ,-1 , 0
  4610.3     .07       0  4885.8     .12       0  5046.7     .05       0
  5050.9     .12       0  5054.3     .05       0  5212.6    .035       0
  5427.1     .07       0
Bank Sta=5046.7,5050.9
XS Rating Curve= 0 ,0
Exp/Cntr=0.3,0.1

Type RM Length L Ch R = 1 ,23150   ,377,377,377
BEGIN DESCRIPTION:
A19716
END DESCRIPTION:
XS GIS Cut Line= 4
      2336755.77     13780117.31      2336328.68     13779893.36
      2336094.31     13780023.56      2335574.31     13780470.76
#Sta/Elev= 30
    4307  556.76  4323.8  556.82  4340.2  558.38  4345.8  557.11  4362.2   557.8
  4367.9  556.33  4384.3  556.61  4389.7  555.45  4406.4  554.46  4428.4  550.41
  4472.5  546.17  4538.7  542.37  4567.6  539.45  4626.9  536.78  4643.4  535.02
  4671.1  534.13  4731.6  529.99  4806.5   527.1  4963.5  525.57  4985.2  523.42
  4988.8  521.68  4989.1  521.18    4993  521.68    5007  524.51    5050  526.12
  5068.6  526.51  5320.2  530.17  5398.7  532.59  5474.8  536.54  5743.2  549.94
#Mann= 8 ,-1 , 0
    4307     .12       0  4389.7     .07       0  4806.5     .12       0
  4988.8     .05       0    4993     .12       0    5050     .05       0
  5068.6    .035       0  5474.8     .07       0
Bank Sta=4988.8,4993
XS Rating Curve= 0 ,0
Exp/Cntr=0.3,0.1

Type RM Length L Ch R = 1 ,22773   ,665,665,665
BEGIN DESCRIPTION:
LONG BRANCH 46.0
END DESCRIPTION:
XS GIS Cut Line= 3
      2336524.98     13779824.99        2336175.       13779675.
      2335574.98     13780075.02
#Sta/Elev= 30
  4625.3  539.36  4657.9  538.45  4715.9  535.48  4734.1   534.1  4844.7  528.68
  4881.3  526.07  4929.9  521.62  4962.5  522.57  4994.9  521.36  4995.1  520.86
  4998.8  520.86  4999.1  521.36  5049.6  523.95  5085.7  524.22  5105.6  525.11
  5121.7  523.88  5136.8  523.84  5226.4   525.2  5353.1  525.06  5446.2  527.25
  5533.4  530.38  5572.4  532.98  5605.5  535.81  5632.5  540.73  5641.5  541.76
  5647.5  543.28  5655.1  543.48  5668.6   545.4  5698.6  548.13  5727.2  548.81
#Mann= 7 ,-1 , 0
  4625.3     .07       0  4881.3     .12       0  4994.9     .05       0
  4999.1     .12       0  5105.6     .05       0  5226.4    .035       0
  5572.4     .07       0
Bank Sta=4994.9,4999.1
XS Rating Curve= 0 ,0
Exp/Cntr=0.3,0.1

Type RM Length L Ch R = 1 ,22108   ,562,562,562
BEGIN DESCRIPTION:
A19715
END DESCRIPTION:
XS GIS Cut Line= 4
      2336635.94     13779783.95      2336208.89     13779372.52
      2335953.68     13779408.98      2335453.71     13780018.32
#Sta/Elev= 30
  4273.6     536  4280.6  535.39  4287.8  536.05  4294.7  535.14  4316.1  535.48
    4323  534.77  4365.5  535.13    4429  532.98  4478.7  533.17  4528.1  531.67
  4549.4  532.14  4611.1  531.55  4744.1   530.6    4811  529.26  4874.5   525.5
  4939.1  520.81  4939.4  520.31  4943.4  520.81  5132.3     521  5313.1  521.59
  5506.8  524.65  5624.6  527.64  5649.4  529.29  5710.7  532.94  5788.9   539.7
    5824  540.48  5881.4  544.99  5887.9  544.04  5902.3  545.22  5912.6  544.86
#Mann= 9 ,-1 , 0
  4273.6    .035       0  4611.1     .07       0  4744.1     .12       0
  4874.5    .033       0  4939.1    .033       0  4943.4    .033       0
  5132.3     .05       0  5506.8    .035       0  5649.4     .07       0
Bank Sta=4939.1,4943.4
XS Rating Curve= 0 ,0
Exp/Cntr=0.3,0.1

Type RM Length L Ch R = 1 ,21546   ,397,397,397
BEGIN DESCRIPTION:
LONG BRANCH 45.0
END DESCRIPTION:
XS GIS Cut Line= 3
      2336948.44     13778955.86      2335887.88     13778986.65
      2335425.04     13779074.99
#Sta/Elev= 30
  3929.4  534.15  3962.9  532.74  4012.9  529.89    4070  527.77  4082.9  526.94
  4112.9  526.36  4212.4   522.4  4259.8  520.84  4260.3  520.34  4265.6  520.34
  4266.1  520.84    4393   521.3    5110  521.13  5135.9   521.1  5169.9  522.13
  5186.8  523.63    5222  524.62  5227.5  525.21  5263.1  526.69  5274.1  527.71
  5288.6  528.13  5326.3   530.5  5331.3   530.2  5359.8  532.02  5378.4  534.05
    5383  534.23  5410.7  535.97  5435.6  536.91  5451.6  537.95  5461.6  538.55
#Mann= 8 ,-1 , 0
  3929.4     .07       0  4212.4    .033       0  4259.8    .033       0
  4266.1    .033       0    5110     .05       0  5263.1    .035       0
    5383     .05       0  5451.6    .035       0
Bank Sta=4259.8,4266.1
XS Rating Curve= 0 ,0
Exp/Cntr=0.3,0.1

Type RM Length L Ch R = 1 ,21149   ,293,293,293
BEGIN DESCRIPTION:
LONG BRANCH 44.0
END DESCRIPTION:
XS GIS Cut Line= 3
      2336524.99     13778075.01        2335725.       13778775.
      2335375.02     13779024.99
#Sta/Elev= 30
  4206.5  540.12  4209.8  540.12  4234.5  537.83  4242.1  537.49    4263  535.26
  4284.8  533.59  4312.8  530.67  4376.9  527.82  4391.1  526.62    4462  522.76
  4489.8   521.3  4649.9  521.17  4650.4  520.67  4655.7  520.67  4656.2  521.17
  5252.8  521.29  5327.3  521.54    5342  522.31  5348.2  522.27  5362.9  524.27
  5391.6  525.69  5434.2  527.59  5448.9  528.88  5469.8  529.65  5499.3  531.75
  5520.2  532.48    5535  533.69  5656.6  538.73  5671.4  539.75  5699.6  540.61
#Mann= 6 ,-1 , 0
  4206.5     .07       0    4462    .033       0  4649.9    .033       0
  4656.2    .033       0  5252.8     .05       0  5391.6    .035       0
Bank Sta=4649.9,4656.2
XS Rating Curve= 0 ,0
Exp/Cntr=0.3,0.1

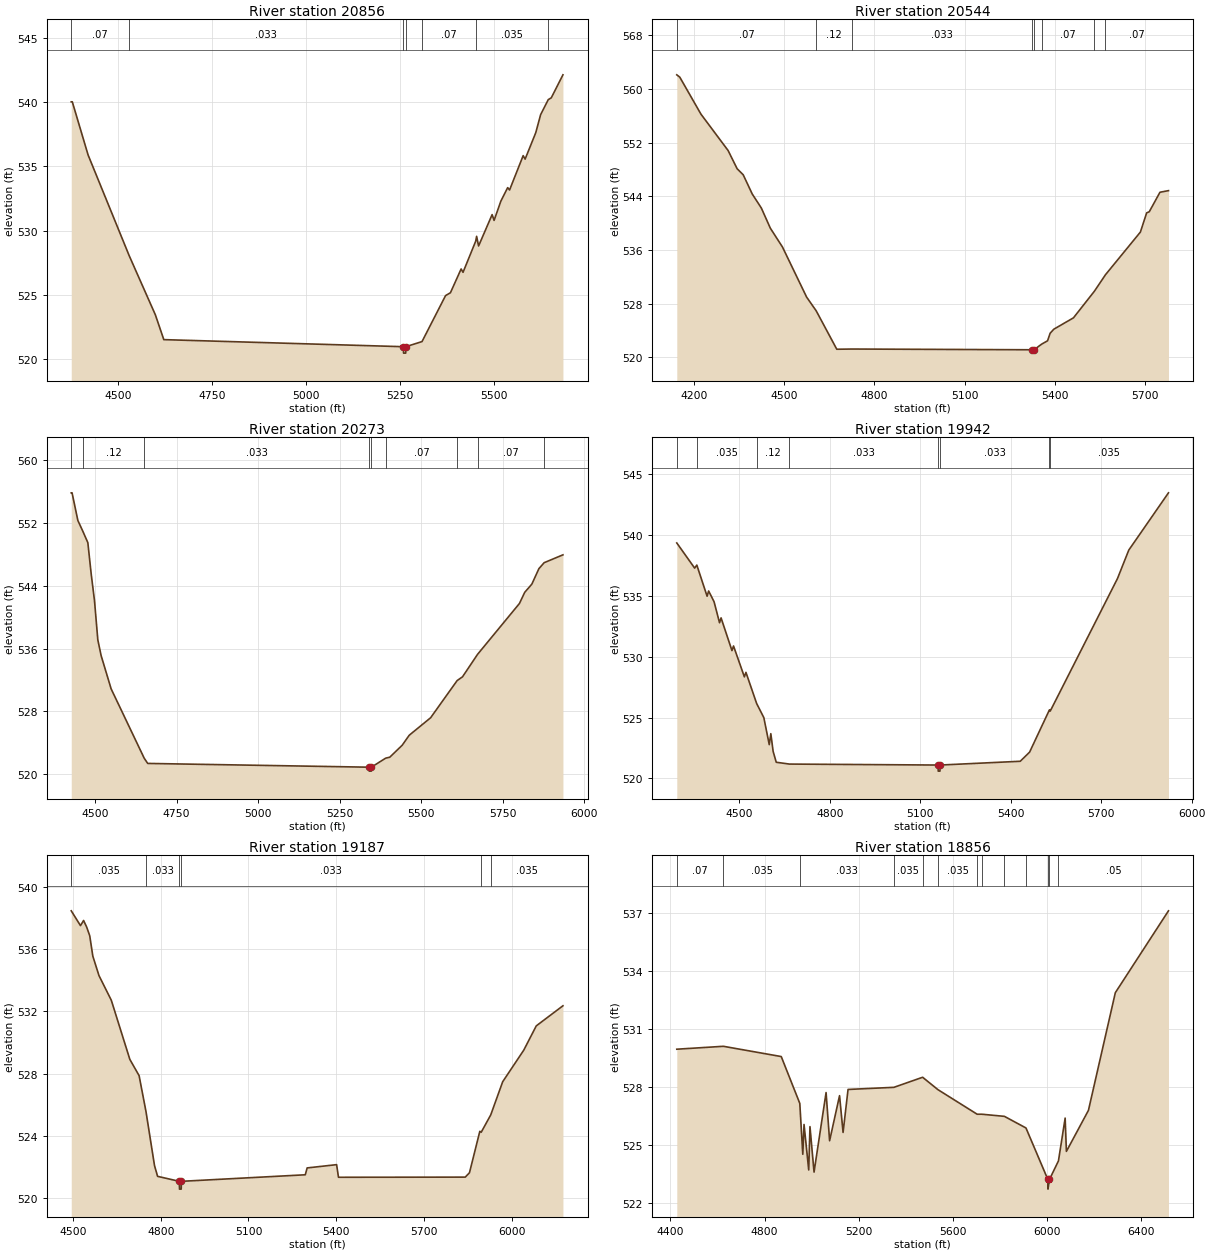
Type RM Length L Ch R = 1 ,20856   ,312,312,312
BEGIN DESCRIPTION:
LONG BRANCH 43.0
END DESCRIPTION:
XS GIS Cut Line= 3
      2336475.02     13778024.99        2335675.       13778425.
      2335274.96     13778324.99
#Sta/Elev= 30
  4375.6  540.03  4378.4  540.03  4420.3   535.9  4529.8  528.04  4599.2  523.45
  4621.6  521.52  5258.4  520.97  5258.9  520.47  5264.5  520.47    5265  520.97
  5307.9  521.37  5370.5  524.95  5383.4  525.17  5411.8  527.02  5416.9  526.76
  5450.5  529.18    5453  529.56  5458.2  528.81  5494.2  531.25  5499.4   530.8
  5517.4   532.3  5535.5  533.35  5540.6  533.17  5576.7  535.84  5581.9  535.57
  5610.2  537.63  5623.1  539.03  5643.4   540.2  5651.4  540.34  5682.4  542.13
#Mann= 7 ,-1 , 0
  4375.6     .07       0  4529.8    .033       0  5258.4    .033       0
    5265    .033       0  5307.9     .07       0  5450.5    .035       0
  5643.4     .07       0
Bank Sta=5258.4,5265
XS Rating Curve= 0 ,0
Exp/Cntr=0.3,0.1

Type RM Length L Ch R = 1 ,20544   ,271,271,271
BEGIN DESCRIPTION:
LONG BRANCH 42.0
END DESCRIPTION:
XS GIS Cut Line= 3
      2336724.98       13777925.        2335525.       13778025.
      2335174.97     13778275.02
#Sta/Elev= 30
  4143.1   562.1  4153.1  561.75  4223.4  556.24  4313.7  550.81  4343.8  548.09
  4363.8   547.2  4393.9  544.33  4424.1  542.24  4454.2  539.22  4494.3  536.43
  4574.6  528.96  4606.6   526.9  4674.9  521.18  4726.5  521.21  5323.8   521.1
  5324.3   520.6    5330   520.6  5330.5   521.1  5355.5  521.93  5375.5  522.44
  5384.1  523.57  5396.4  524.17  5461.5  525.86  5531.3  529.84    5568  532.29
    5684  538.65  5704.9  541.52  5713.5  541.68  5749.1  544.59  5777.4  544.83
#Mann= 8 ,-1 , 0
  4143.1     .07       0  4606.6     .12       0  4726.5    .033       0
  5323.8    .033       0  5330.5    .033       0  5355.5     .07       0
  5531.3    .035       0    5568     .07       0
Bank Sta=5323.8,5330.5
XS Rating Curve= 0 ,0
Exp/Cntr=0.3,0.1

Type RM Length L Ch R = 1 ,20273   ,331,331,331
BEGIN DESCRIPTION:
LONG BRANCH 41.0
END DESCRIPTION:
XS GIS Cut Line= 3
      2336374.95     13777525.01        2336125.       13777575.
        2335025.       13778175.
#Sta/Elev= 30
  4426.7  555.81  4429.2  555.81    4447  552.29  4461.6  550.98  4477.6  549.47
  4487.8  545.51    4498  542.09  4508.2   537.1  4518.4  535.09    4549  530.87
  4650.5  522.04  4661.2  521.38  5340.3   520.9  5340.8   520.4  5346.5   520.4
    5347   520.9    5391  522.05  5403.5  522.17  5441.5  523.69  5463.3  524.97
  5528.8  527.19  5610.1  531.92  5626.6   532.4  5672.6  535.25  5801.2  541.73
  5817.4  543.15  5839.2  544.19    5861  546.17    5877  546.92  5934.6  547.92
#Mann= 9 ,-1 , 0
  4426.7    .035       0  4461.6     .12       0  4650.5    .033       0
  5340.3    .033       0    5347    .033       0    5391     .07       0
  5610.1    .035       0  5672.6     .07       0    5877    .035       0
Bank Sta=5340.3,5347
XS Rating Curve= 0 ,0
Exp/Cntr=0.3,0.1

Type RM Length L Ch R = 1 ,19942   ,755,755,755
BEGIN DESCRIPTION:
LONG BRANCH 40.0
END DESCRIPTION:
XS GIS Cut Line= 3
      2336525.04     13777224.99        2335725.       13777425.
      2335024.99       13777825.
#Sta/Elev= 30
  4292.2  539.36  4351.5  537.29  4358.7  537.54  4392.7  534.98  4397.9  535.41
  4415.9  534.52    4434   532.8  4439.1   533.2  4475.2  530.51  4480.4  530.89
  4516.4  528.35  4521.6  528.72  4557.1  526.16  4580.9     525  4598.9  522.78
  4604.1  523.68  4611.8  522.22  4622.1  521.33  4665.5  521.18  5158.9   521.1
  5159.4   520.6  5165.1   520.6  5165.6   521.1  5431.4  521.41  5462.4  522.16
  5528.3  525.64    5531  525.54  5753.9  536.43  5791.4  538.77  5923.1  543.48
#Mann= 8 ,-1 , 0
  4292.2     .07       0  4358.7    .035       0  4557.1     .12       0
  4665.5    .033       0  5158.9    .033       0  5165.6    .033       0
  5528.3     .07       0    5531    .035       0
Bank Sta=5158.9,5165.6
XS Rating Curve= 0 ,0
Exp/Cntr=0.3,0.1

Type RM Length L Ch R = 1 ,19187   ,331,331,331
BEGIN DESCRIPTION:
LONG BRANCH 39.0
END DESCRIPTION:
XS GIS Cut Line= 3
        2336325.       13776625.        2336025.       13776525.
      2334964.12     13777382.93
#Sta/Elev= 30
  4494.3  538.44  4525.9  537.49  4536.5  537.82    4547   537.4  4557.5  536.84
  4568.1  535.53  4589.2  534.28  4631.3   532.7  4694.6  528.91  4726.2  527.87
  4749.8  525.56  4778.9   522.1  4789.4  521.41  4863.8  521.09  4864.3  520.59
  4870.2  520.59  4870.7  521.09  5294.2  521.51  5300.6  521.95  5401.3  522.16
  5407.7  521.35    5841  521.36  5855.4  521.64  5890.8   524.3  5895.6  524.24
  5928.1  525.35    5969  527.48  6040.9   529.5  6083.7  531.06  6174.9  532.35
#Mann= 6 ,-1 , 0
  4494.3    .035       0  4749.8    .033       0  4863.8    .033       0
  4870.7    .033       0  5895.6     .07       0  5928.1    .035       0
Bank Sta=4863.8,4870.7
XS Rating Curve= 0 ,0
Exp/Cntr=0.3,0.1

Type RM Length L Ch R = 1 ,18856   ,551,551,551
BEGIN DESCRIPTION:
LONG BRANCH 38.0
END DESCRIPTION:
XS GIS Cut Line= 4
      2336542.21     13776544.39      2335974.52     13776336.06
      2335140.79     13775785.63      2334682.89     13775627.75
#Sta/Elev= 30
  4426.9  529.97  4624.7  530.12  4870.5  529.59  4949.3  527.17    4962  524.54
  4967.3  526.08  4987.2  523.73  4992.5  525.97  5009.8  523.62  5060.9  527.73
  5075.9  525.24  5118.1  527.57  5133.1  525.67  5154.2  527.89    5349     528
    5471  528.52  5535.9  527.88  5702.6  526.61  5722.9  526.61  5818.3   526.5
  5909.8   525.9  6002.7  523.24  6003.2  522.74  6009.6  523.24  6047.8   524.2
  6076.2  526.41  6081.5  524.69  6175.1  526.81  6289.3  532.89    6515  537.12
#Mann= 13 ,-1 , 0
  4426.9     .07       0  4624.7    .035       0  4949.3    .033       0
    5349    .035       0    5471    .033       0  5535.9    .035       0
  5702.6    .033       0  5722.9    .035       0  5818.3    .033       0
  5909.8    .035       0  6002.7    .033       0  6009.6    .035       0
  6047.8     .05       0
Bank Sta=6002.7,6009.6
XS Rating Curve= 0 ,0
Exp/Cntr=0.3,0.1