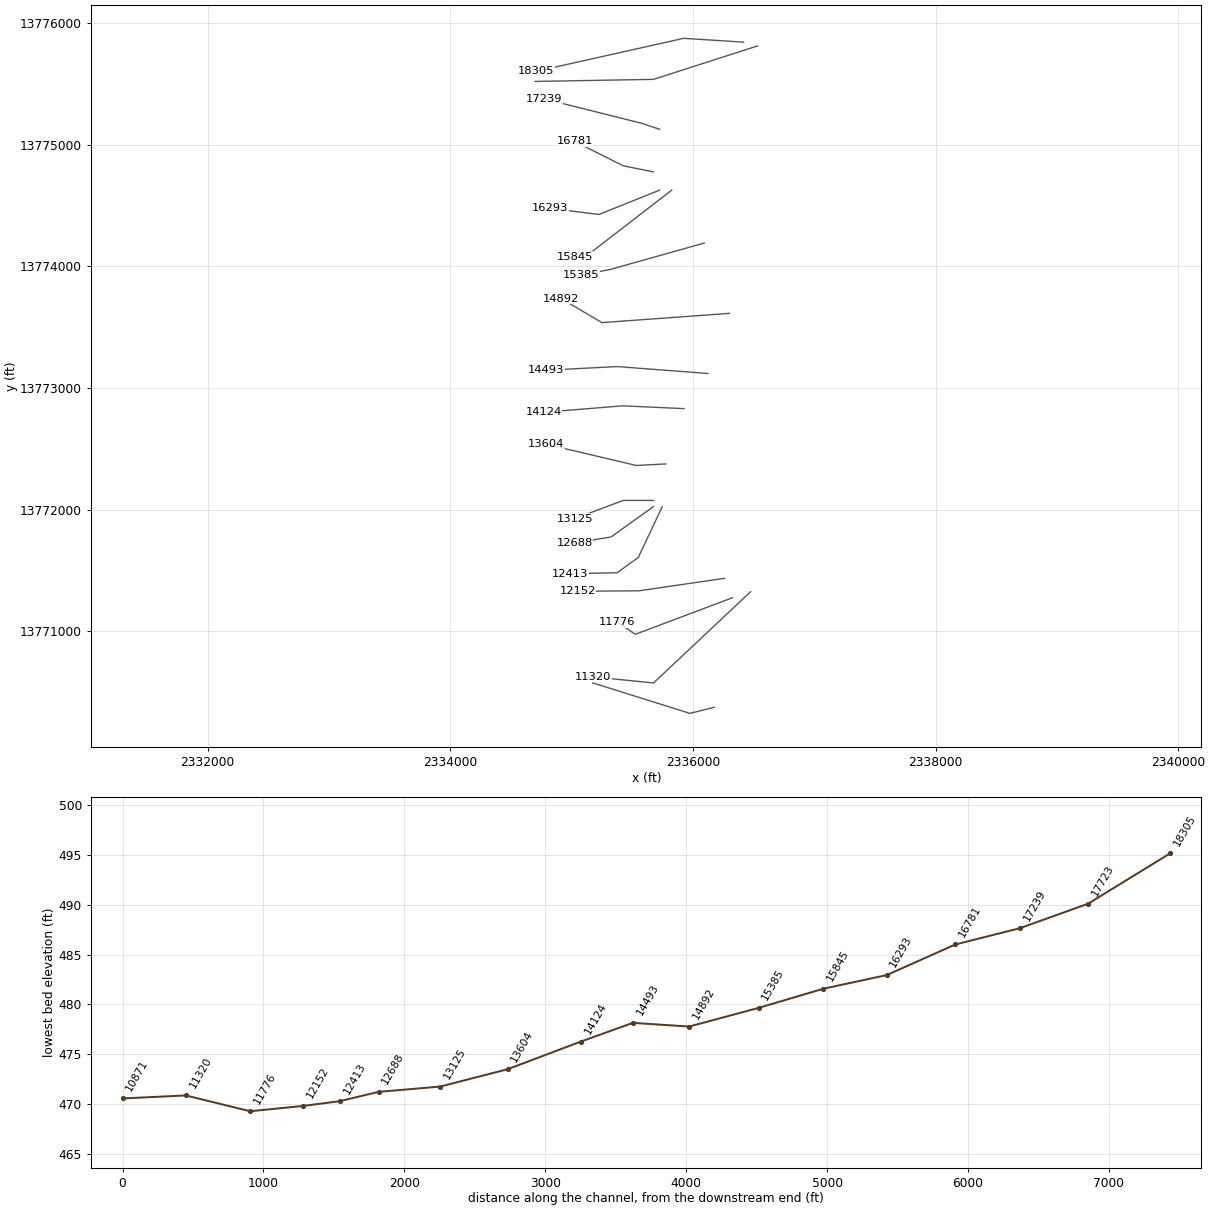
HEC-RAS study LONG BRANCH.prj: LONG BRANCH Base Level Engineering

--- LONG BRANCH.g01 (geometry) --- (continued)

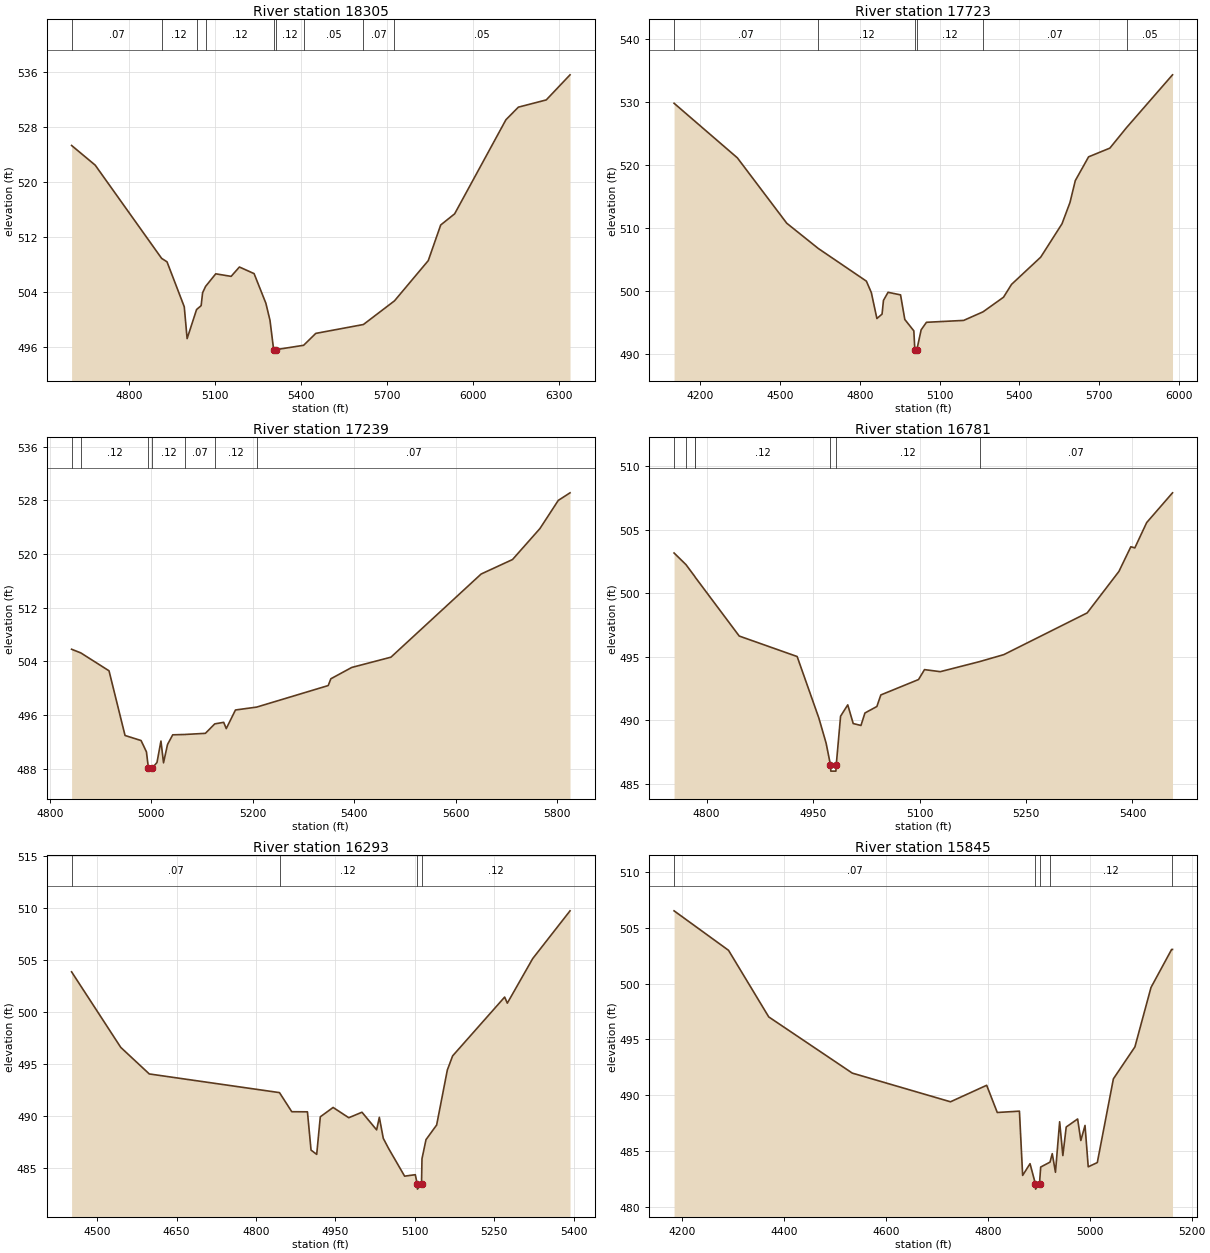
Type RM Length L Ch R = 1 ,18305   ,582,582,582
BEGIN DESCRIPTION:
LONG BRANCH 37.0
END DESCRIPTION:
XS GIS Cut Line= 3
      2336417.22     13775841.27      2335922.43     13775872.52
      2334709.45     13775601.81
#Sta/Elev= 30
  4598.8  525.32  4681.2  522.46  4912.8  508.91  4931.7   508.4  4991.8  501.87
  5001.8  497.24  5034.8  501.47  5050.7  502.03  5055.8  503.91  5066.2  504.83
  5101.6  506.66  5155.3  506.29  5184.2  507.65  5235.4  506.69  5276.4  502.39
  5290.8  499.91  5303.6  495.63  5304.1  495.13  5310.7  495.63  5408.2  496.27
  5450.6     498  5616.7  499.29  5725.1  502.73  5842.9  508.58  5886.3  513.76
  5934.9  515.38  6113.8  529.06  6157.2  530.89  6254.4  531.94  6337.4  535.59
#Mann= 9 ,-1 , 0
  4598.8     .07       0  4912.8     .12       0  5034.8     .07       0
  5066.2     .12       0  5303.6     .05       0  5310.7     .12       0
  5408.2     .05       0  5616.7     .07       0  5725.1     .05       0
Bank Sta=5303.6,5310.7
XS Rating Curve= 0 ,0
Exp/Cntr=0.3,0.1

Type RM Length L Ch R = 1 ,17723   ,484,484,484
BEGIN DESCRIPTION:
LONG BRANCH 36.0
END DESCRIPTION:
XS GIS Cut Line= 3
      2336531.84     13775810.03        2335675.     13775535.42
      2334699.22     13775518.37
#Sta/Elev= 30
    4101  529.73  4339.2  521.07    4525   510.7  4643.8  506.69  4824.7  501.51
  4843.3   499.7  4864.3  495.58  4883.7  496.28    4889  498.46  4906.3  499.74
  4953.3  499.33  4969.3  495.43  5003.3  493.62  5007.1  490.59  5007.6  490.09
  5014.4  490.59  5030.8  493.79  5050.8  494.98  5190.8  495.28  5263.7  496.64
  5340.8  498.96  5370.8  500.99  5480.8  505.32  5560.9  510.61  5590.9  513.99
  5610.9  517.46  5660.9  521.23  5740.9  522.61  5803.6  525.86  5976.7  534.24
#Mann= 6 ,-1 , 0
    4101     .07       0  4643.8     .12       0  5007.1     .05       0
  5014.4     .12       0  5263.7     .07       0  5803.6     .05       0
Bank Sta=5007.1,5014.4
XS Rating Curve= 0 ,0
Exp/Cntr=0.3,0.1

Type RM Length L Ch R = 1 ,17239   ,458,458,458
BEGIN DESCRIPTION:
LONG BRANCH 35.0
END DESCRIPTION:
XS GIS Cut Line= 3
      2335725.02     13775124.99        2335575.       13775175.
      2334774.95     13775375.01
#Sta/Elev= 30
  4842.7   505.8  4860.8  505.26  4916.5  502.59  4948.1  492.95  4979.7   492.2
  4990.3  490.51  4994.1  488.14  4994.6  487.64  5002.2  488.14  5011.1  488.93
  5018.9  492.12    5024  488.88  5031.8   491.6  5042.1  493.05  5065.6   493.1
  5106.5  493.27    5125  494.68  5142.6  494.91  5147.7  493.98  5165.8  496.75
  5207.6  497.18  5348.7  500.39  5353.9   501.4  5395.1  503.09  5472.4  504.62
  5650.2  517.01  5712.1  519.17  5766.2  523.79  5802.3  527.98  5825.5  529.11
#Mann= 7 ,-1 , 0
  4842.7     .07       0  4860.8     .12       0  4994.1     .05       0
  5002.2     .12       0  5065.6     .07       0    5125     .12       0
  5207.6     .07       0
Bank Sta=4994.1,5002.2
XS Rating Curve= 0 ,0
Exp/Cntr=0.3,0.1

Type RM Length L Ch R = 1 ,16781   ,488,488,488
BEGIN DESCRIPTION:
LONG BRANCH 34.0
END DESCRIPTION:
XS GIS Cut Line= 3
        2335675.       13774775.        2335425.       13774825.
      2335024.96     13775025.02
#Sta/Elev= 30
  4754.2  503.16  4770.9  502.25  4783.3  501.32  4784.2  501.24    4846  496.63
  4927.6  495.02  4958.2  490.18  4968.4  488.21  4974.5  486.51    4975  486.01
  4982.2  486.01  4982.7  486.51  4988.8  490.33  4998.9  491.22  5006.6  489.75
  5017.5   489.6  5023.1  490.58  5039.9  491.09  5045.5     492  5098.6  493.21
    5107  493.99  5129.3  493.83  5184.6  494.62  5218.8  495.17  5336.2  498.45
  5380.9  501.71  5397.7  503.65  5403.3  503.56    5420  505.55  5456.4  507.89
#Mann= 7 ,-1 , 0
  4754.2     .07       0  4770.9     .12       0  4783.3     .07       0
  4784.2     .12       0  4974.5     .05       0  4982.7     .12       0
  5184.6     .07       0
Bank Sta=4974.5,4982.7
XS Rating Curve= 0 ,0
Exp/Cntr=0.3,0.1

Type RM Length L Ch R = 1 ,16293   ,448,448,448
BEGIN DESCRIPTION:
LONG BRANCH 33.0
END DESCRIPTION:
XS GIS Cut Line= 3
      2335725.02     13774625.01        2335225.       13774425.
      2334824.95     13774475.01
#Sta/Elev= 30
  4451.6  503.88  4544.5   496.6  4598.4  494.04  4844.4  492.24  4867.6   490.4
  4897.2  490.39    4904   486.7  4914.7  486.29  4921.5  489.91  4945.7  490.81
  4975.3  489.82  5000.2  490.35  5027.9  488.65    5033  489.86  5040.5  487.83
  5050.6  486.85  5080.8  484.19    5101  484.33  5104.5  483.44    5105  482.94
  5112.7  483.44  5113.6  485.87  5121.2  487.71  5141.3  489.12  5161.5  494.42
  5171.5  495.78  5269.8  501.45  5274.8  500.86  5322.7  505.15  5393.3  509.76
#Mann= 4 ,-1 , 0
  4451.6     .07       0  4844.4     .12       0  5104.5     .05       0
  5112.7     .12       0
Bank Sta=5104.5,5112.7
XS Rating Curve= 0 ,0
Exp/Cntr=0.3,0.1

Type RM Length L Ch R = 1 ,15845   ,460,460,460
BEGIN DESCRIPTION:
LONG BRANCH 32.0
END DESCRIPTION:
XS GIS Cut Line= 3
      2335825.01     13774625.01        2335175.       13774125.
      2335024.99       13774075.
#Sta/Elev= 30
  4184.1  506.53    4291  502.99  4369.9  497.02  4533.9  491.98  4726.6  489.41
  4797.6  490.89  4818.4  488.45  4861.9  488.57  4868.2  482.81  4882.7  483.86
  4893.1  482.08  4893.6  481.58  4901.3  482.08  4903.6  483.56  4921.9     484
  4926.3  484.76  4932.6  483.09  4940.8  487.62  4947.1  484.59  4953.7  487.15
  4976.1  487.87  4982.4  485.94  4990.6  487.29  4996.9  483.58  5014.7  483.96
  5046.3  491.47  5088.5  494.33  5120.1  499.66  5160.6  503.07  5162.3  503.07
#Mann= 5 ,-1 , 0
  4184.1     .07       0  4893.1     .05       0  4901.3     .07       0
  4921.9     .12       0  5160.6     .07       0
Bank Sta=4893.1,4901.3
XS Rating Curve= 0 ,0
Exp/Cntr=0.3,0.1

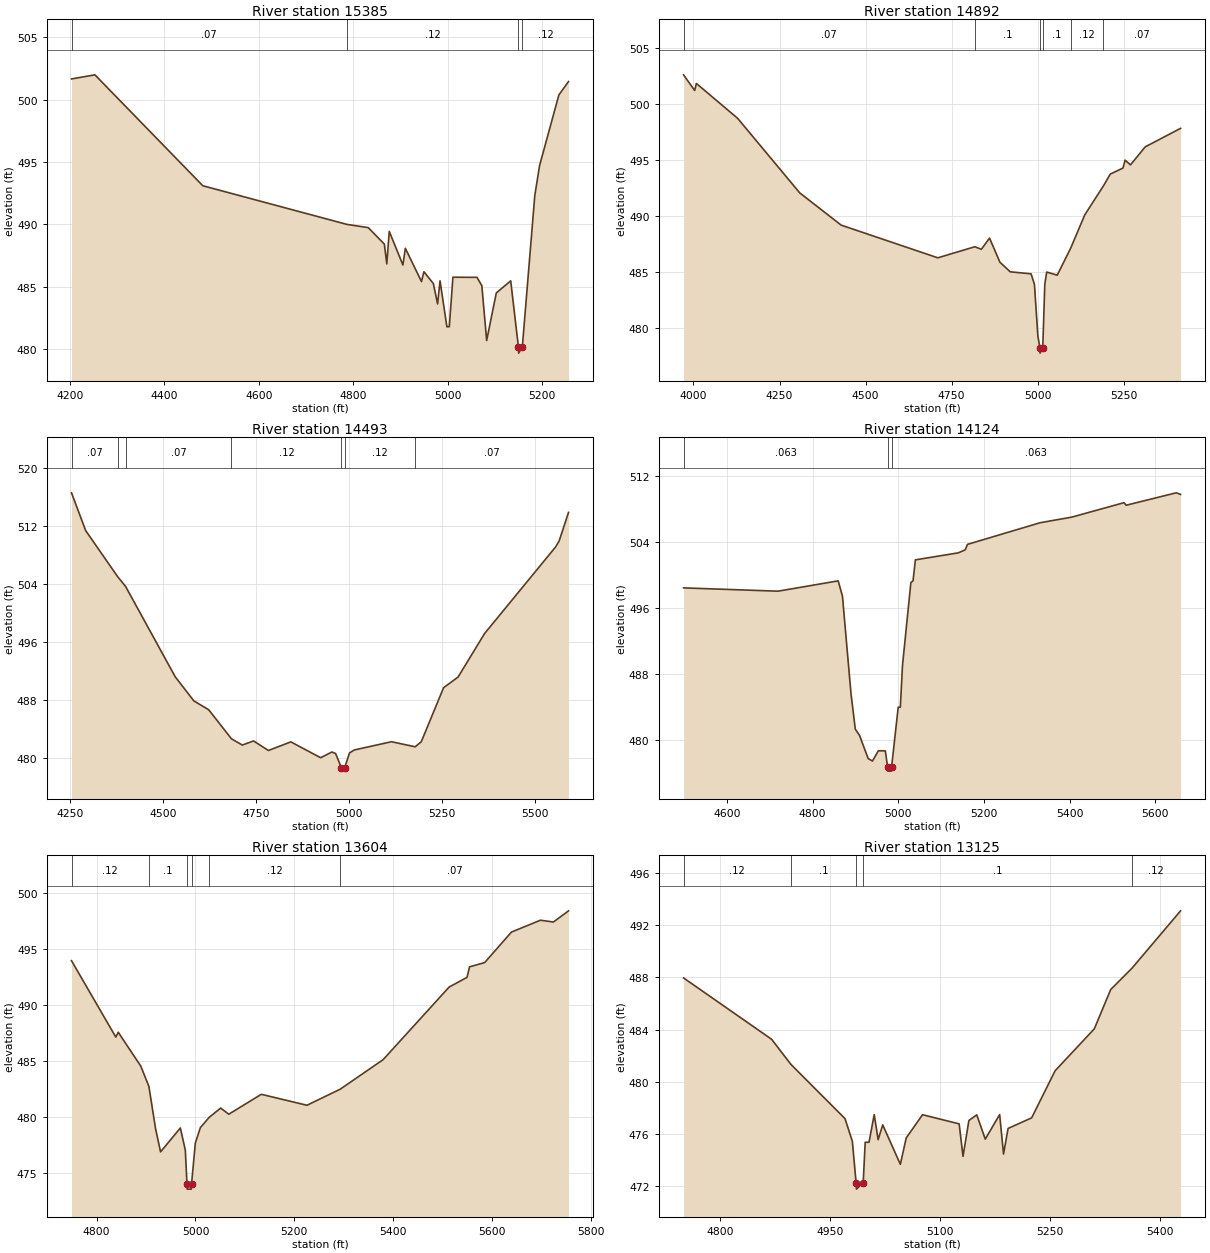
Type RM Length L Ch R = 1 ,15385   ,493,493,493
BEGIN DESCRIPTION:
LONG BRANCH 31.0
END DESCRIPTION:
XS GIS Cut Line= 3
      2336092.64     13774189.97        2335325.       13773975.
      2335075.02       13773925.
#Sta/Elev= 30
  4203.3  501.66  4252.8  501.99  4481.2  493.09  4786.2  489.99  4831.4  489.73
  4865.5  488.41  4870.7  486.82  4875.9  489.43  4904.8  486.73    4910  488.07
  4944.1   485.4  4949.3  486.19  4969.3  485.24  4978.2  483.61  4983.4  485.46
  4997.9  481.78    5003  481.78  5010.7  485.75  5061.7  485.74  5071.9  485.07
  5082.1  480.67  5102.5  484.49    5133  485.46  5149.3  480.16  5149.8  479.66
  5157.6  480.16    5184  492.31  5194.2  494.72    5235  500.38  5255.4  501.45
#Mann= 4 ,-1 , 0
  4203.3     .07       0  4786.2     .12       0  5149.3     .05       0
  5157.6     .12       0
Bank Sta=5149.3,5157.6
XS Rating Curve= 0 ,0
Exp/Cntr=0.3,0.1

Type RM Length L Ch R = 1 ,14892   ,399,399,399
BEGIN DESCRIPTION:
LONG BRANCH 30.0
END DESCRIPTION:
XS GIS Cut Line= 3
      2336301.64     13773612.37      2335249.01     13773536.36
       2334914.6     13773733.97
#Sta/Elev= 30
  3971.2  502.64  4003.5  501.24  4008.5  501.87  4128.2  498.76  4308.7   492.1
    4429  489.22  4709.8   486.3  4817.6  487.29  4836.2  487.06  4860.1  488.06
  4890.2  485.91  4920.3  485.05  4980.8  484.87  4990.5  483.93  5000.5  479.31
  5006.3  478.29  5006.8  477.79  5014.7  478.29  5020.6  483.92  5026.1  485.03
  5056.8  484.75  5095.9  487.17  5136.8  490.14  5190.7  492.71  5210.9  493.78
    5248  494.32  5253.8  495.02  5269.5   494.6  5312.4  496.21    5415  497.86
#Mann= 6 ,-1 , 0
  3971.2     .07       0  4817.6      .1       0  5006.3     .05       0
  5014.7      .1       0  5095.9     .12       0  5190.7     .07       0
Bank Sta=5006.3,5014.7
XS Rating Curve= 0 ,0
Exp/Cntr=0.3,0.1

Type RM Length L Ch R = 1 ,14493   ,369,369,369
BEGIN DESCRIPTION:
LONG BRANCH 29.0
END DESCRIPTION:
XS GIS Cut Line= 3
      2336122.97     13773118.37        2335375.       13773175.
      2334789.58     13773144.98
#Sta/Elev= 30
  4254.7  516.59  4292.8  511.37  4378.8  505.01    4400  503.67  4533.5  491.19
  4583.6  487.86  4623.7  486.63  4684.8  482.62    4714  481.76  4744.1  482.33
  4784.2  481.01  4844.4   482.2  4924.6  480.01  4954.7   480.8  4964.7  480.59
  4980.2  478.66  4980.7  478.16  4988.8  478.16  4989.3  478.66  5002.3  480.68
  5014.8  481.08    5115  482.22  5178.8  481.52  5195.1  482.22  5255.1  489.68
    5294  491.15  5365.3  497.16  5555.5  509.07  5565.5   509.9    5591  513.89
#Mann= 7 ,-1 , 0
  4254.7     .07       0  4378.8     .12       0    4400     .07       0
  4684.8     .12       0  4980.2     .05       0  4989.3     .12       0
  5178.8     .07       0
Bank Sta=4980.2,4989.3
XS Rating Curve= 0 ,0
Exp/Cntr=0.3,0.1

Type RM Length L Ch R = 1 ,14124   ,520,520,520
BEGIN DESCRIPTION:
LONG BRANCH 28.0
END DESCRIPTION:
XS GIS Cut Line= 3
      2335925.38     13772829.57      2335420.01     13772852.37
      2334768.25     13772799.32
#Sta/Elev= 30
    4499  498.46  4719.6  498.06  4859.8  499.31  4869.8  497.47  4889.8  485.63
  4899.8  481.37  4909.8   480.6  4929.8  477.81  4939.8  477.51  4953.6  478.75
  4969.9  478.74  4975.2  476.79  4975.7  476.29    4984  476.29  4984.5  476.79
  4999.9  484.02  5004.9  484.02  5009.9  489.07  5029.5  499.11  5034.5  499.31
    5040  501.85  5140.3   502.7  5156.4  503.07  5161.4  503.72    5331  506.34
    5405  507.02  5526.9  508.77  5531.9  508.46  5648.7  509.96  5658.8  509.77
#Mann= 3 ,-1 , 0
    4499    .063       0  4975.2    .063       0  4984.5    .063       0
Bank Sta=4975.2,4984.5
XS Rating Curve= 0 ,0
Exp/Cntr=0.3,0.1

Type RM Length L Ch R = 1 ,13604   ,479,479,479
BEGIN DESCRIPTION:
LONG BRANCH 27.0
END DESCRIPTION:
XS GIS Cut Line= 3
      2335774.98       13772375.      2335534.01     13772362.17
      2334789.65     13772536.87
#Sta/Elev= 30
  4749.1  493.95  4838.7  487.12  4843.7  487.55  4889.3  484.52  4905.7  482.71
  4919.3  478.91  4929.3  476.85  4969.4  478.99  4979.4  477.01  4982.8  474.02
  4983.3  473.52  4991.6  473.52  4992.1  474.02  4999.7  477.64  5009.9  479.02
  5027.7  479.94    5051  480.77  5067.4  480.22  5133.2     482  5225.6  481.02
    5293  482.46  5379.8   485.1  5513.3  491.59  5549.5  492.46  5554.7   493.4
  5585.2  493.78  5639.5  496.51  5698.1  497.57  5724.4  497.41    5755  498.41
#Mann= 6 ,-1 , 0
  4749.1     .12       0  4905.7      .1       0  4982.8     .05       0
  4992.1      .1       0  5027.7     .12       0    5293     .07       0
Bank Sta=4982.8,4992.1
XS Rating Curve= 0 ,0
Exp/Cntr=0.3,0.1

Type RM Length L Ch R = 1 ,13125   ,437,437,437
BEGIN DESCRIPTION:
LONG BRANCH 26.0
END DESCRIPTION:
XS GIS Cut Line= 3
      2335674.99       13772075.        2335425.       13772075.
      2335024.99       13771925.
#Sta/Elev= 30
  4750.3  487.96  4870.3  483.26  4896.7  481.33  4970.3  477.18  4980.3  475.44
  4985.4  472.28  4985.9  471.78  4995.1  472.28  4997.8  475.37    5003  475.37
  5010.1  477.49  5015.4  475.57  5021.7   476.7  5045.7  473.68  5053.7   475.7
  5075.9  477.48  5125.8  476.78  5131.1  474.29  5139.1  477.04  5149.8  477.47
  5161.4  475.61    5181  477.49  5186.3  474.47  5192.5  476.43  5224.6  477.24
  5256.6  480.85    5310  484.06  5332.3  487.07  5361.4  488.71  5427.5   493.1
#Mann= 5 ,-1 , 0
  4750.3     .12       0  4896.7      .1       0  4985.4     .05       0
  4995.1      .1       0  5361.4     .12       0
Bank Sta=4985.4,4995.1
XS Rating Curve= 0 ,0
Exp/Cntr=0.3,0.1

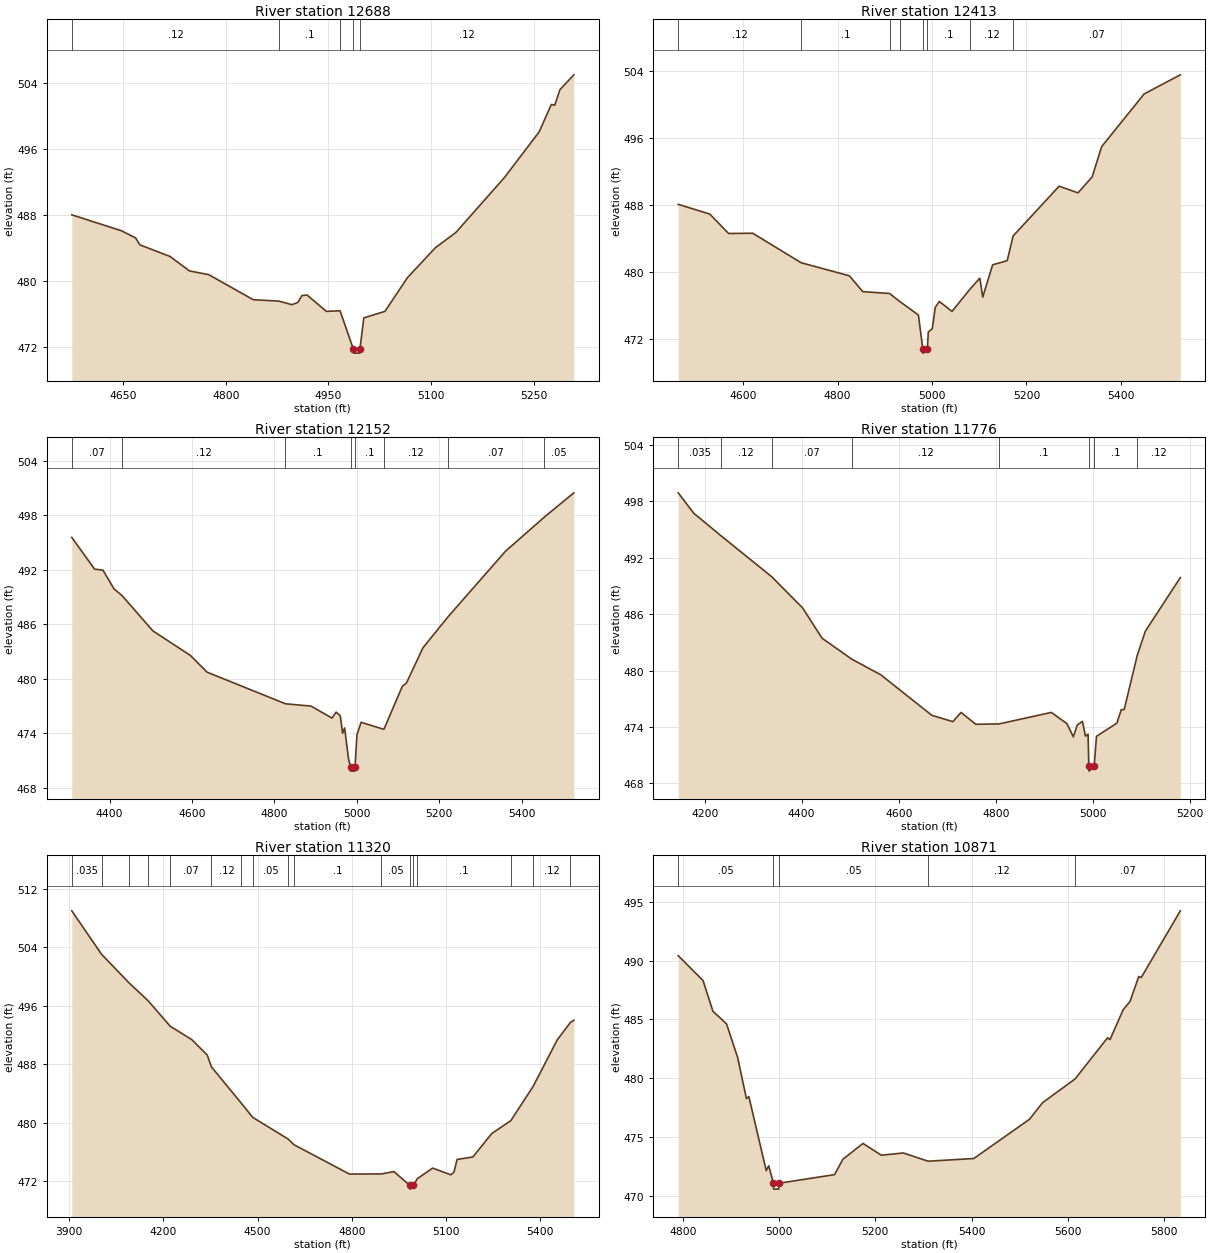
Type RM Length L Ch R = 1 ,12688   ,275,275,275
BEGIN DESCRIPTION:
LONG BRANCH 25.0
END DESCRIPTION:
XS GIS Cut Line= 3
      2335675.01     13772025.01        2335325.       13771775.
      2335024.97     13771724.99
#Sta/Elev= 30
  4574.6  488.01  4647.1  486.08    4668  485.21  4674.2  484.37  4718.4  482.96
  4746.7  481.21  4774.9  480.76  4840.1  477.72  4877.7  477.55  4896.6  477.12
  4905.2  477.39  4911.3  478.23  4918.7  478.29    4947  476.31    4967  476.38
  4986.4  471.75  4986.9  471.25  4995.6  471.25  4996.1  471.75  5001.7  475.52
  5032.6  476.31  5065.6   480.4  5106.1     484  5136.5  485.88  5207.5  492.54
  5258.2  498.06  5275.9  501.37    5281  501.29  5288.6  503.18  5308.9  504.97
#Mann= 5 ,-1 , 0
  4574.6     .12       0  4877.7      .1       0    4967     .12       0
  4986.4     .05       0  4996.1     .12       0
Bank Sta=4986.4,4996.1
XS Rating Curve= 0 ,0
Exp/Cntr=0.3,0.1

Type RM Length L Ch R = 1 ,12413   ,261,261,261
BEGIN DESCRIPTION:
A19714
END DESCRIPTION:
XS GIS Cut Line= 4
      2335746.82     13772023.98      2335549.21     13771605.97
      2335374.41     13771480.57      2334988.38       13771473.
#Sta/Elev= 30
  4462.3  488.08  4529.1  486.92    4569   484.6  4620.1  484.63  4722.7  481.11
  4824.9  479.55  4853.2  477.66    4910  477.44  4932.9  476.43  4971.1  474.87
  4980.4  470.82  4980.9  470.32  4990.1  470.82    4992  472.84  5000.5  473.24
  5006.7  475.76  5015.3  476.49  5042.3   475.3  5079.8  477.92  5101.2  479.27
  5107.4  477.01  5128.3  480.86  5159.2  481.36  5171.8  484.31  5269.2  490.25
  5309.2  489.45  5339.2  491.36  5359.2  494.96  5449.3  501.26  5525.9  503.54
#Mann= 8 ,-1 , 0
  4462.3     .12       0  4722.7      .1       0    4910     .12       0
  4932.9      .1       0  4980.4     .05       0  4990.1      .1       0
  5079.8     .12       0  5171.8     .07       0
Bank Sta=4980.4,4990.1
XS Rating Curve= 0 ,0
Exp/Cntr=0.3,0.1

Type RM Length L Ch R = 1 ,12152   ,376,376,376
BEGIN DESCRIPTION:
A19713
END DESCRIPTION:
XS GIS Cut Line= 3
      2336259.84     13771434.98      2335556.81     13771332.37
       2335048.8     13771328.58
#Sta/Elev= 30
    4308  495.56  4363.4  492.06  4383.6  491.96  4410.3  489.91  4430.3  489.14
  4504.9  485.27  4595.9  482.57  4636.3  480.73  4826.7  477.25  4888.9  476.99
  4939.5  475.68  4949.6  476.33  4959.7  475.93  4965.2  474.01  4970.2  474.59
  4979.9  471.13  4984.5  470.34    4985  469.84    4995  469.84  4995.5  470.34
  5000.1  473.84  5010.2  475.21  5065.5  474.44  5110.3  479.18  5120.3  479.54
  5160.3  483.41  5220.6  486.79  5360.3  494.02  5454.4  497.77  5526.5  500.46
#Mann= 8 ,-1 , 0
    4308     .07       0  4430.3     .12       0  4826.7      .1       0
  4984.5     .05       0  4995.5      .1       0  5065.5     .12       0
  5220.6     .07       0  5454.4     .05       0
Bank Sta=4984.5,4995.5
XS Rating Curve= 0 ,0
Exp/Cntr=0.3,0.1

Type RM Length L Ch R = 1 ,11776   ,456,456,456
BEGIN DESCRIPTION:
LONG BRANCH 24.0
END DESCRIPTION:
XS GIS Cut Line= 3
      2336324.99       13771275.        2335525.       13770975.
      2335374.97     13771075.02
#Sta/Elev= 30
  4145.6  498.89  4177.6  496.72  4233.9  494.32  4337.9  489.99  4401.9  486.66
    4442  483.44    4503  481.22    4563  479.55    4668  475.25  4711.6  474.57
  4728.5  475.55  4758.8  474.29    4807  474.33  4914.5  475.55  4946.6  474.36
  4959.9  472.96  4967.9  474.21  4978.6   474.6  4984.9  473.03  4990.2  473.24
  4991.8  469.81  4992.3  469.31  5002.8  469.81  5007.5  473.01  5049.6  474.41
  5058.6  475.84  5064.6  475.85  5091.6  481.62  5108.2  484.18  5180.3  489.88
#Mann= 8 ,-1 , 0
  4145.6    .035       0  4233.9     .12       0  4337.9     .07       0
    4503     .12       0    4807      .1       0  4991.8     .05       0
  5002.8      .1       0  5091.6     .12       0
Bank Sta=4991.8,5002.8
XS Rating Curve= 0 ,0
Exp/Cntr=0.3,0.1

Type RM Length L Ch R = 1 ,11320   ,449,449,449
BEGIN DESCRIPTION:
LONG BRANCH 23.0
END DESCRIPTION:
XS GIS Cut Line= 3
      2336474.97     13771324.97        2335675.       13770575.
      2335175.04       13770625.
#Sta/Elev= 30
  3908.3  508.97  4003.1  503.03  4090.4  499.13  4151.7  496.66  4221.8  493.18
  4290.5  491.35  4339.8  489.23  4353.2  487.61  4448.8  482.62  4484.6  480.71
  4597.4  477.74  4615.9  476.97  4792.6  472.95  4894.5  472.97  4934.2  473.29
  4985.3  471.39  4985.8  470.89  4996.5  471.39  5008.8  472.32  5057.6  473.77
  5115.4  472.85  5125.4   473.2  5135.5  474.95  5185.7  475.29    5246   478.5
  5306.6  480.26  5377.4  484.93  5454.6  491.32  5496.2  493.69  5507.3     494
#Mann= 17 ,-1 , 0
  3908.3    .035       0  4003.1     .12       0  4090.4    .035       0
  4151.7     .12       0  4221.8     .07       0  4353.2     .12       0
  4448.8     .07       0  4484.6     .05       0  4597.4     .12       0
  4615.9      .1       0  4894.5     .05       0  4985.3     .05       0
  4996.5     .05       0  5008.8      .1       0  5306.6     .07       0
  5377.4     .12       0  5496.2     .07       0
Bank Sta=4985.3,4996.5
XS Rating Curve= 0 ,0
Exp/Cntr=0.3,0.1

Type RM Length L Ch R = 1 ,10871   ,468,468,468
BEGIN DESCRIPTION:
LONG BRANCH 22.0
END DESCRIPTION:
XS GIS Cut Line= 3
      2336175.04     13770375.01        2335975.       13770325.
      2335175.04     13770574.99
#Sta/Elev= 30
    4790  490.41  4841.6   488.3  4862.2  485.69  4890.5  484.62  4913.7  481.75
  4931.8  478.28  4936.9  478.45    4973  472.16  4978.2  472.57    4988  471.09
  4988.5  470.59  4998.8  470.59  4999.3  471.09  5115.1  471.82  5132.4  473.12
  5174.3  474.47  5212.5  473.47  5258.1  473.66  5309.8  472.96  5404.8  473.19
  5520.6  476.52  5547.8  477.93  5615.5  479.95    5683  483.44  5688.2  483.29
  5715.4  485.82  5729.6  486.52  5747.9  488.64  5753.1  488.56  5834.3  494.22
#Mann= 5 ,-1 , 0
    4790     .05       0    4988     .05       0  4999.3     .05       0
  5309.8     .12       0  5615.5     .07       0
Bank Sta=4988,4999.3
XS Rating Curve= 0 ,0
Exp/Cntr=0.3,0.1