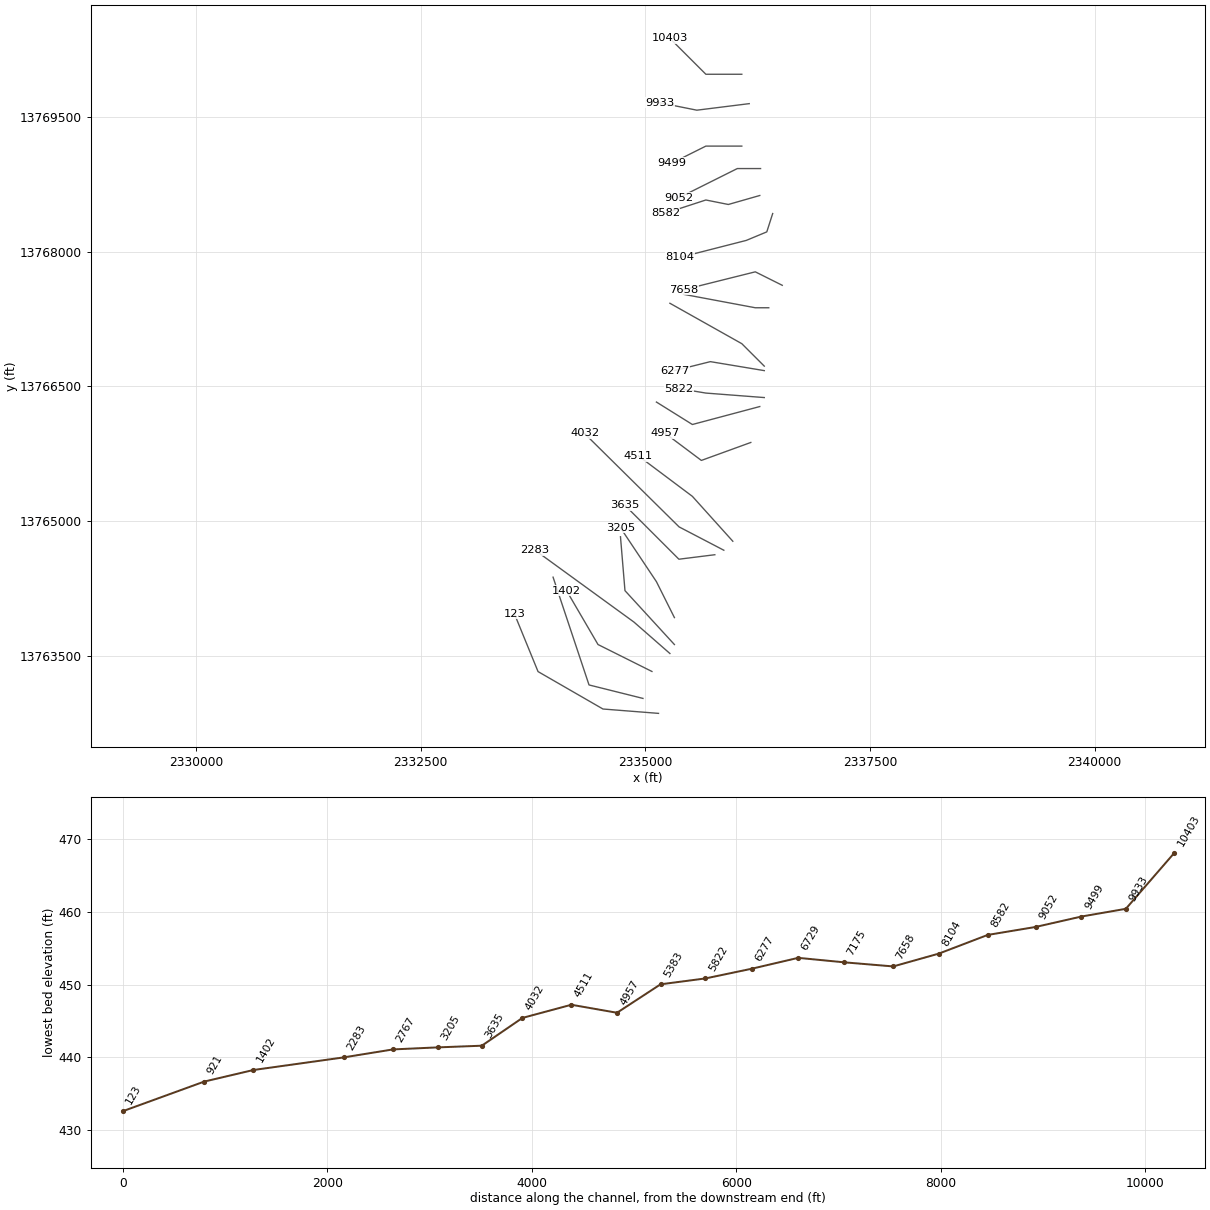
HEC-RAS study LONG BRANCH.prj: LONG BRANCH Base Level Engineering

--- LONG BRANCH.g01 (geometry) --- (continued)

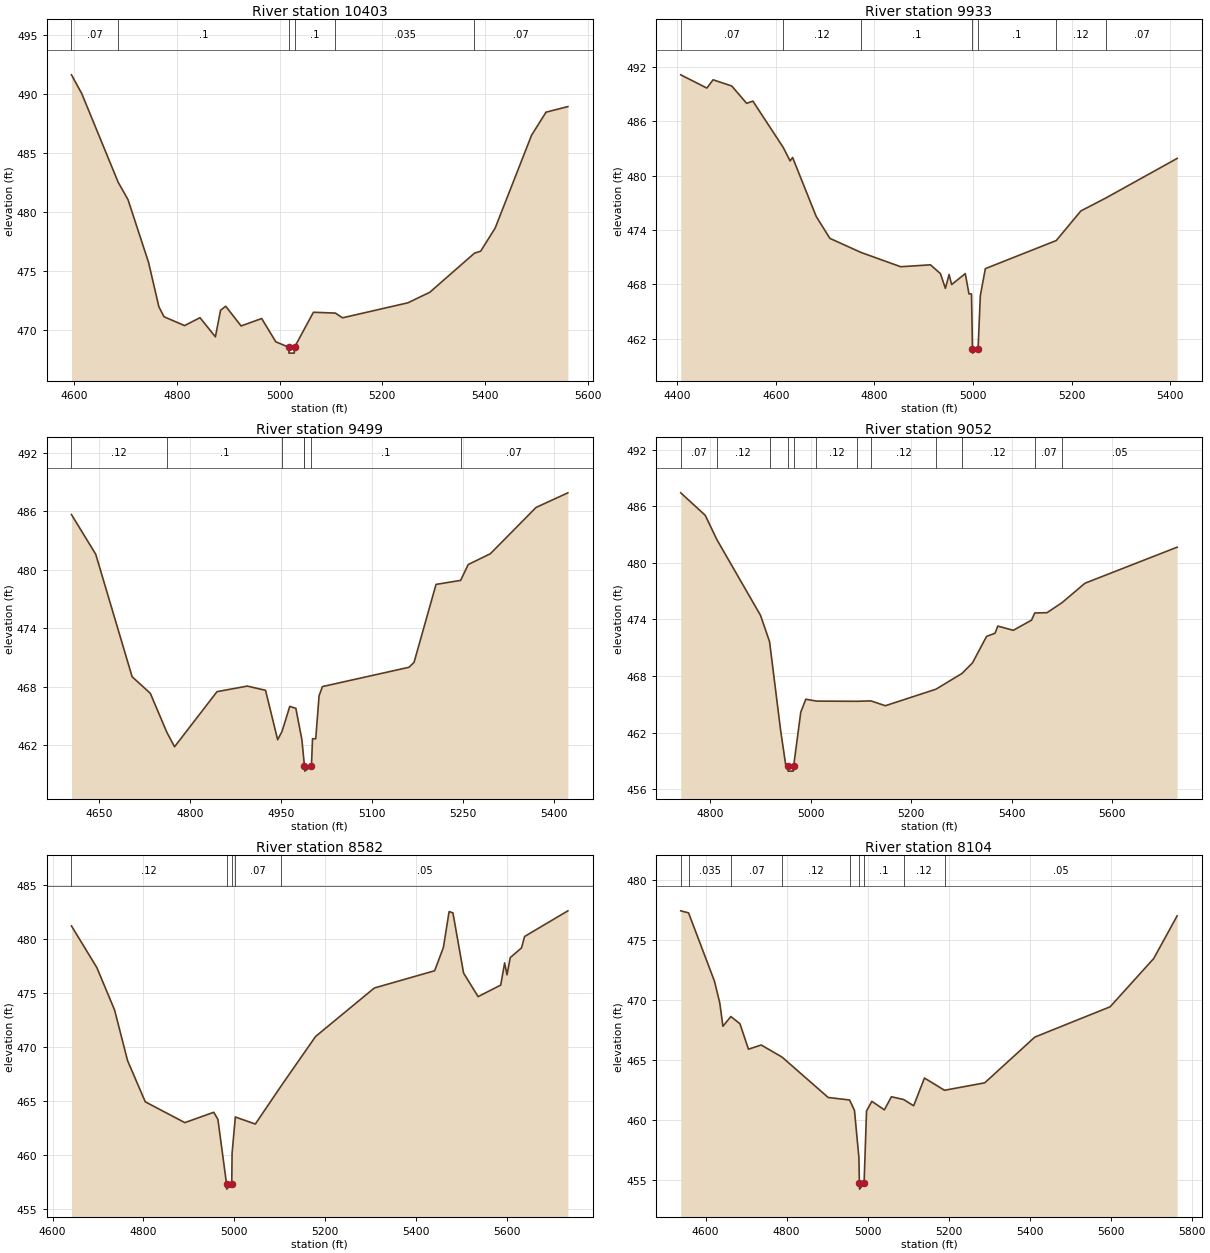
Type RM Length L Ch R = 1 ,10403   ,470,470,470
BEGIN DESCRIPTION:
LONG BRANCH 21.0
END DESCRIPTION:
XS GIS Cut Line= 3
      2336074.98       13769975.        2335675.       13769975.
      2335274.97     13770375.03
#Sta/Elev= 30
  4595.2   491.6  4615.2  490.01  4686.1   482.5  4705.2  481.03  4745.2  475.71
  4765.2  471.97  4775.2  471.12  4815.2  470.37  4845.2  471.04  4875.2  469.42
  4885.2  471.67  4895.2  472.01  4925.2  470.34  4965.2  470.97  4992.7     469
  5017.8  468.54  5018.3  468.04  5028.6  468.04  5029.1  468.54  5065.9   471.5
  5108.6  471.43  5122.5  471.03  5249.7   472.3  5292.2  473.19  5379.1   476.5
  5391.2  476.67  5419.4  478.62  5490.2  486.48  5518.4  488.44  5560.9  488.91
#Mann= 6 ,-1 , 0
  4595.2     .07       0  4686.1      .1       0  5017.8     .05       0
  5029.1      .1       0  5108.6    .035       0  5379.1     .07       0
Bank Sta=5017.8,5029.1
XS Rating Curve= 0 ,0
Exp/Cntr=0.3,0.1

Type RM Length L Ch R = 1 ,9933    ,434,434,434
BEGIN DESCRIPTION:
LONG BRANCH 20.0
END DESCRIPTION:
XS GIS Cut Line= 5
      2336157.63     13769647.83        2335975.       13769625.
        2335575.       13769575.        2335325.       13769625.
      2335163.51      13769657.3
#Sta/Elev= 30
  4407.1  491.15  4460.1  489.69  4472.7   490.6  4510.5  489.92  4540.8     488
  4553.4  488.25    4615  483.13  4628.9  481.64    4634  482.02  4681.8  475.52
  4709.6  473.09  4773.1  471.53  4853.2  469.96  4913.6  470.17  4933.8   469.2
  4943.9  467.57  4951.4   469.1  4956.5  467.99  4984.2   469.2  4991.7  466.96
  4996.8  466.96  4998.8  460.92  4999.3  460.42  5010.2  460.92  5014.7  466.74
  5024.9  469.75  5168.7  472.85  5218.6  476.12  5269.7  477.56  5413.9  481.92
#Mann= 7 ,-1 , 0
  4407.1     .07       0    4615     .12       0  4773.1      .1       0
  4998.8     .05       0  5010.2      .1       0  5168.7     .12       0
  5269.7     .07       0
Bank Sta=4998.8,5010.2
XS Rating Curve= 0 ,0
Exp/Cntr=0.3,0.1

Type RM Length L Ch R = 1 ,9499    ,447,447,447
BEGIN DESCRIPTION:
LONG BRANCH 19.0
END DESCRIPTION:
XS GIS Cut Line= 4
      2336074.96       13769175.        2335675.       13769175.
        2335475.       13769075.      2335300.56     13768987.78
#Sta/Elev= 30
  4604.3  485.67  4644.3   481.6  4704.3  469.04  4734.3  467.34  4761.8  463.31
  4774.3  461.86  4844.3  467.51  4894.3  468.08  4924.3  467.65  4944.3  462.58
  4951.5  463.43  4964.3     466  4974.3   465.8  4984.3  462.57  4987.4  460.57
  4988.5  459.86    4989  459.36    5000  459.86  5001.8  462.68  5007.1  462.68
  5012.6  467.09  5018.2  468.03  5160.8  470.01  5169.2  470.51  5205.5  478.51
    5246  478.92  5258.6  480.55    5295  481.65  5370.4   486.4  5422.9   487.9
#Mann= 7 ,-1 , 0
  4604.3     .12       0  4761.8      .1       0  4951.5     .12       0
  4987.4      .1       0  4988.5     .05       0    5000      .1       0
    5246     .07       0
Bank Sta=4988.5,5000
XS Rating Curve= 0 ,0
Exp/Cntr=0.3,0.1

Type RM Length L Ch R = 1 ,9052    ,470,470,470
BEGIN DESCRIPTION:
LONG BRANCH 18.0
END DESCRIPTION:
XS GIS Cut Line= 5
       2336283.7       13768925.        2336175.       13768925.
        2336025.       13768925.        2335625.       13768725.
      2335373.59     13768599.29
#Sta/Elev= 30
  4741.7  487.42  4790.4  485.04  4813.6  482.46  4900.4  474.43  4918.3  471.65
  4940.4  462.21  4950.4  458.59  4954.6  458.43  4955.1  457.93  4965.6  457.93
  4966.1  458.43  4980.4  464.19  4990.4  465.55  5011.6  465.35  5091.6  465.33
  5120.1  465.37  5148.5  464.86  5249.1  466.61  5300.9  468.28  5321.8   469.4
  5349.8  472.21  5366.6  472.54  5372.1   473.3  5402.9  472.85  5439.2  473.93
  5445.6  474.69    5470  474.72    5500  475.79  5545.4  477.84  5728.7  481.66
#Mann= 12 ,-1 , 0
  4741.7     .07       0  4813.6     .12       0  4918.3      .1       0
  4954.6     .05       0  4966.1      .1       0  5011.6     .12       0
  5091.6     .07       0  5120.1     .12       0  5249.1      .1       0
  5300.9     .12       0  5445.6     .07       0    5500     .05       0
Bank Sta=4954.6,4966.1
XS Rating Curve= 0 ,0
Exp/Cntr=0.3,0.1

Type RM Length L Ch R = 1 ,8582    ,478,478,478
BEGIN DESCRIPTION:
LONG BRANCH 17.0
END DESCRIPTION:
XS GIS Cut Line= 4
      2336275.03     13768625.01        2335925.       13768525.
        2335675.       13768575.      2335224.42     13768427.84
#Sta/Elev= 30
  4641.5  481.25  4697.4  477.38  4736.4  473.45    4765  468.75    4804  464.93
  4891.1     463  4954.8  463.96  4963.9   463.3  4982.9  457.33  4983.4  456.83
  4994.4  457.33  4995.1  460.15  5002.3  463.52  5046.3  462.87  5103.4  466.42
  5178.9  470.99  5308.3  475.49  5441.1  477.09  5460.4  479.25    5473  482.58
  5481.4  482.46  5504.9  476.87  5536.8  474.69  5586.6  475.76  5595.3  477.82
  5600.5  476.71  5607.6  478.31  5632.4  479.21  5639.2  480.27  5734.5  482.65
#Mann= 5 ,-1 , 0
  4641.5     .12       0  4982.9     .05       0  4994.4     .12       0
  5002.3     .07       0  5103.4     .05       0
Bank Sta=4982.9,4994.4
XS Rating Curve= 0 ,0
Exp/Cntr=0.3,0.1

Type RM Length L Ch R = 1 ,8104    ,446,446,446
BEGIN DESCRIPTION:
LONG BRANCH 16.0
END DESCRIPTION:
XS GIS Cut Line= 4
      2336418.67      13768424.2      2336353.04     13768219.95
        2336125.       13768125.      2335384.71      13767935.5
#Sta/Elev= 30
  4538.5  477.43  4557.8  477.26  4621.7  471.58  4634.8  469.78  4642.7  467.82
  4662.2  468.63  4684.7  468.03  4705.7  465.91  4737.2  466.26  4788.8  465.25
  4902.6  461.89  4955.5  461.68  4967.5  460.81  4978.4   456.9  4979.6  454.76
  4980.1  454.26  4991.2  454.76  4997.3  460.77  5010.4  461.57  5041.3  460.86
  5058.7  461.95  5088.9  461.72  5113.6   461.2  5140.3  463.51  5189.8  462.49
  5289.1  463.11  5412.9  466.92  5598.7  469.44  5706.4  473.46  5764.2  477.01
#Mann= 9 ,-1 , 0
  4538.5     .12       0  4557.8    .035       0  4662.2     .07       0
  4788.8     .12       0  4955.5      .1       0  4979.6     .05       0
  4991.2      .1       0  5088.9     .12       0  5189.8     .05       0
Bank Sta=4979.6,4991.2
XS Rating Curve= 0 ,0
Exp/Cntr=0.3,0.1

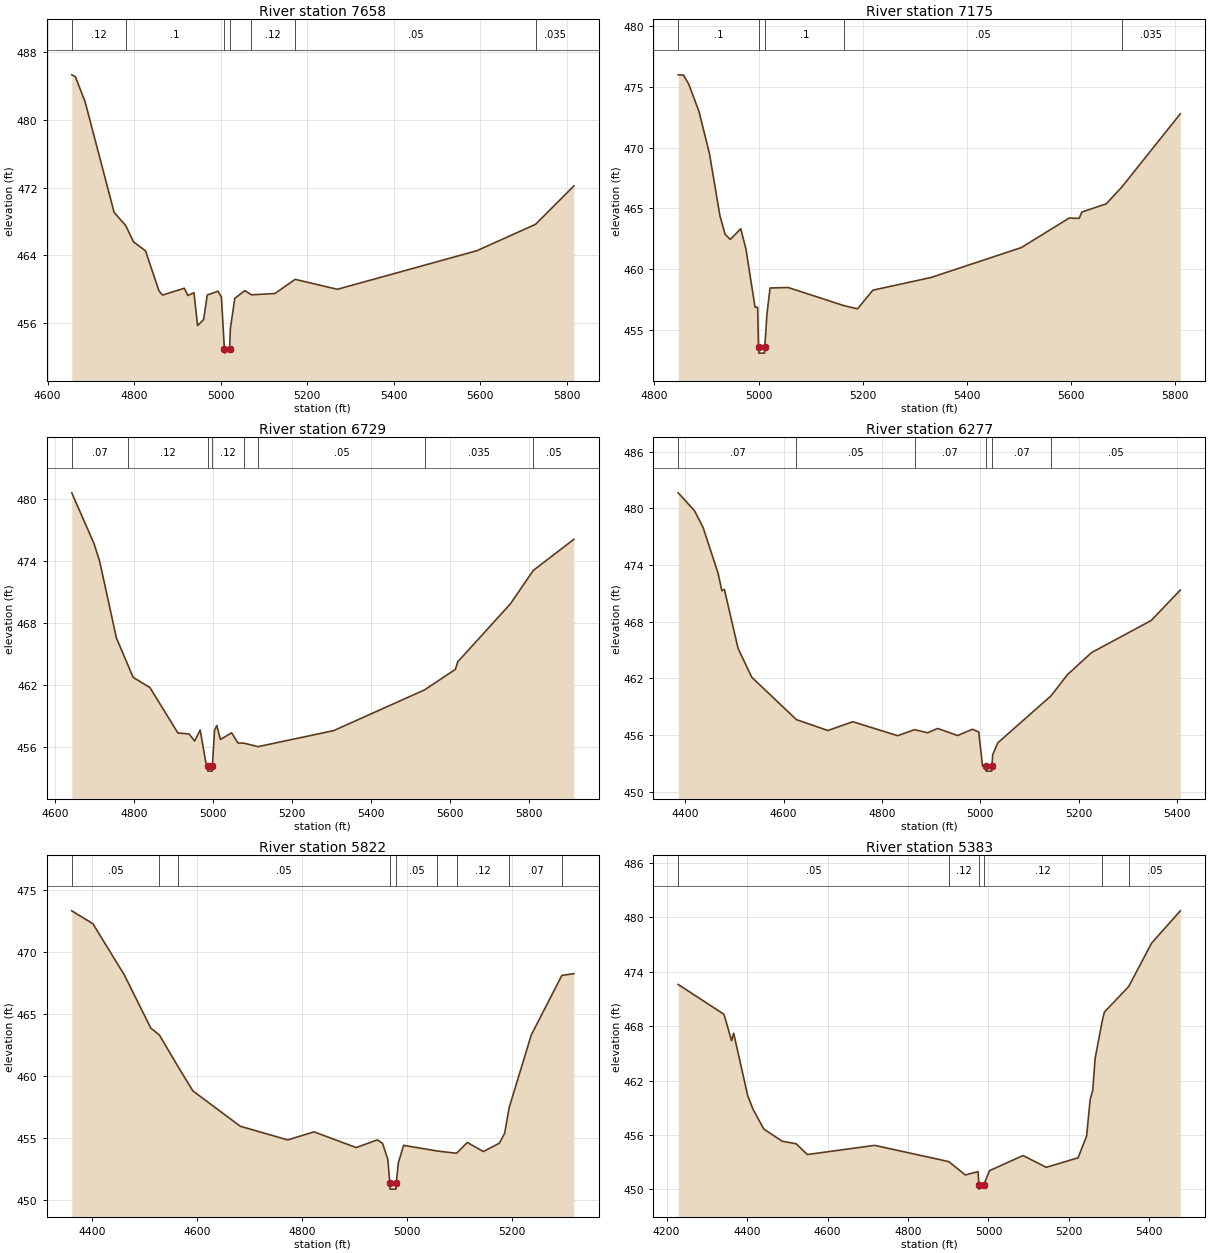
Type RM Length L Ch R = 1 ,7658    ,483,483,483
BEGIN DESCRIPTION:
LONG BRANCH 15.0
END DESCRIPTION:
XS GIS Cut Line= 3
      2336525.03     13767624.98        2336225.       13767775.
      2335424.97     13767574.99
#Sta/Elev= 30
    4656  485.28  4664.4  485.06  4686.8  482.11  4753.9  469.07  4780.5  467.54
  4798.6  465.61  4826.5  464.54  4857.3  459.86  4865.7  459.34    4916  460.14
  4924.4  459.29  4938.3  459.62  4946.7  455.74  4960.7  456.46  4969.1  459.35
    4994  459.79  5001.8  459.08  5008.6     453  5009.1   452.5  5020.7     453
  5022.4  455.38  5032.7  458.96  5055.9  459.86  5071.2  459.37  5125.4  459.52
    5172  461.19  5269.8  460.02  5591.9  464.56  5727.6  467.67  5816.1  472.19
#Mann= 7 ,-1 , 0
    4656     .12       0  4780.5      .1       0  5008.6     .05       0
  5020.7      .1       0  5071.2     .12       0    5172     .05       0
  5727.6    .035       0
Bank Sta=5008.6,5020.7
XS Rating Curve= 0 ,0
Exp/Cntr=0.3,0.1

Type RM Length L Ch R = 1 ,7175    ,446,446,446
BEGIN DESCRIPTION:
LONG BRANCH 14.0
END DESCRIPTION:
XS GIS Cut Line= 3
        2336375.       13767375.        2336225.       13767375.
      2335425.04     13767524.99
#Sta/Elev= 30
  4845.7  476.01  4855.7  475.99  4865.7  475.26  4885.7  472.97  4905.7  469.51
  4925.7   464.4  4935.7  462.86  4945.7  462.44  4965.7  463.32  4975.7  461.65
  4993.2  456.85  4998.2  456.85  4999.8  453.57  5000.3  453.07  5011.4  453.07
  5011.9  453.57  5016.1  456.32    5022  458.44  5056.7  458.48  5164.2  456.98
  5189.9  456.72  5219.5  458.26  5331.5  459.31  5504.4  461.77    5596   464.2
  5615.5  464.18  5620.6   464.7  5667.2  465.37  5697.7  466.78  5809.6   472.8
#Mann= 5 ,-1 , 0
  4845.7      .1       0  4999.8     .05       0  5011.9      .1       0
  5164.2     .05       0  5697.7    .035       0
Bank Sta=4999.8,5011.9
XS Rating Curve= 0 ,0
Exp/Cntr=0.3,0.1

Type RM Length L Ch R = 1 ,6729    ,452,452,452
BEGIN DESCRIPTION:
LONG BRANCH 13.0
END DESCRIPTION:
XS GIS Cut Line= 3
      2336324.97     13766725.03        2336075.       13766975.
      2335274.99       13767425.
#Sta/Elev= 30
  4642.3  480.61  4698.8  475.68    4713  473.97  4755.4  466.56  4784.2  463.97
  4797.8  462.75  4840.2  461.77    4911  457.37  4939.2  457.28  4953.4  456.59
  4967.5  457.66  4981.7  454.54  4986.2  454.18  4986.7  453.68  4997.9  453.68
  4998.4  454.18  5003.8  457.63  5009.5  458.09  5018.8  456.74  5047.1  457.39
  5063.1   456.4  5078.9  456.38  5114.2  456.05  5305.6   457.6  5535.6  461.54
  5613.8  463.53  5619.5  464.25  5753.1  469.87    5811   473.1  5913.7  476.11
#Mann= 8 ,-1 , 0
  4642.3     .07       0  4784.2     .12       0  4986.2     .05       0
  4998.4     .12       0  5078.9     .07       0  5114.2     .05       0
  5535.6    .035       0    5811     .05       0
Bank Sta=4986.2,4998.4
XS Rating Curve= 0 ,0
Exp/Cntr=0.3,0.1

Type RM Length L Ch R = 1 ,6277    ,455,455,455
BEGIN DESCRIPTION:
LONG BRANCH 12.0
END DESCRIPTION:
XS GIS Cut Line= 3
      2336325.03       13766675.        2335725.       13766775.
      2335325.01       13766675.
#Sta/Elev= 30
  4385.7  481.65  4418.7  479.76  4436.4  477.96  4466.8  473.12  4474.4  471.28
  4479.5  471.43  4507.4  465.17  4535.3  462.12    4626  457.64  4689.9  456.49
  4740.6  457.42  4831.8  455.94  4866.1  456.58  4892.6  456.25  4912.9  456.71
  4953.5  455.96  4983.9  456.62  4996.6  456.33  5004.3   452.7    5011  452.69
  5011.5  452.19  5022.8  452.19  5023.3  452.69  5024.9  453.91  5035.2  455.18
  5143.7  460.17    5177  462.41  5225.9  464.74    5347  468.13  5406.3  471.36
#Mann= 6 ,-1 , 0
  4385.7     .07       0    4626     .05       0  4866.1     .07       0
    5011     .05       0  5023.3     .07       0  5143.7     .05       0
Bank Sta=5011,5023.3
XS Rating Curve= 0 ,0
Exp/Cntr=0.3,0.1

Type RM Length L Ch R = 1 ,5822    ,439,439,439
BEGIN DESCRIPTION:
LONG BRANCH 11.0
END DESCRIPTION:
XS GIS Cut Line= 3
      2336325.04       13766375.        2335675.       13766425.
        2335375.       13766475.
#Sta/Elev= 30
  4361.8  473.35    4402  472.31  4462.1  468.15  4512.3  463.87  4528.7  463.31
  4564.5  460.73  4592.5  458.79  4682.8  455.93    4773  454.83  4823.2  455.48
  4903.4  454.21  4943.6  454.83  4953.6  454.55  4963.6  453.26  4967.5  451.35
    4968  450.85  4979.3  450.85  4979.8  451.35  4983.7  452.98  4993.7  454.39
  5058.1  453.93  5094.5  453.75  5115.1  454.62  5145.6  453.89    5176  454.56
  5186.1  455.36  5194.8  457.45  5236.8  463.31  5295.1  468.13  5317.9  468.27
#Mann= 9 ,-1 , 0
  4361.8     .05       0  4528.7     .07       0  4564.5     .05       0
  4967.5     .05       0  4979.8     .05       0  5058.1     .07       0
  5094.5     .12       0  5194.8     .07       0  5295.1     .05       0
Bank Sta=4967.5,4979.8
XS Rating Curve= 0 ,0
Exp/Cntr=0.3,0.1

Type RM Length L Ch R = 1 ,5383    ,426,426,426
BEGIN DESCRIPTION:
LONG BRANCH 10.0
END DESCRIPTION:
XS GIS Cut Line= 3
      2336274.99       13766275.        2335525.       13766075.
      2335124.99       13766325.
#Sta/Elev= 30
  4228.9  472.58  4342.7  469.29  4361.5  466.38  4366.7  467.21  4401.6  460.33
  4415.2   458.8  4441.7  456.65  4487.6  455.31  4521.9  455.04  4549.7  453.85
  4717.3  454.86  4901.4  453.07  4942.4   451.6    4974  451.97  4976.3  450.54
  4976.8  450.04  4988.6  450.54  5002.5  452.07  5085.9  453.74  5143.7  452.44
  5222.7  453.49  5243.9  455.89  5252.7   459.9  5259.2  460.94  5265.1  464.43
  5282.9  468.59  5288.1  469.54  5348.5  472.35  5405.4  477.13  5476.8  480.69
#Mann= 6 ,-1 , 0
  4228.9     .05       0  4901.4     .12       0  4976.3     .05       0
  4988.6     .12       0  5282.9     .07       0  5348.5     .05       0
Bank Sta=4976.3,4988.6
XS Rating Curve= 0 ,0
Exp/Cntr=0.3,0.1

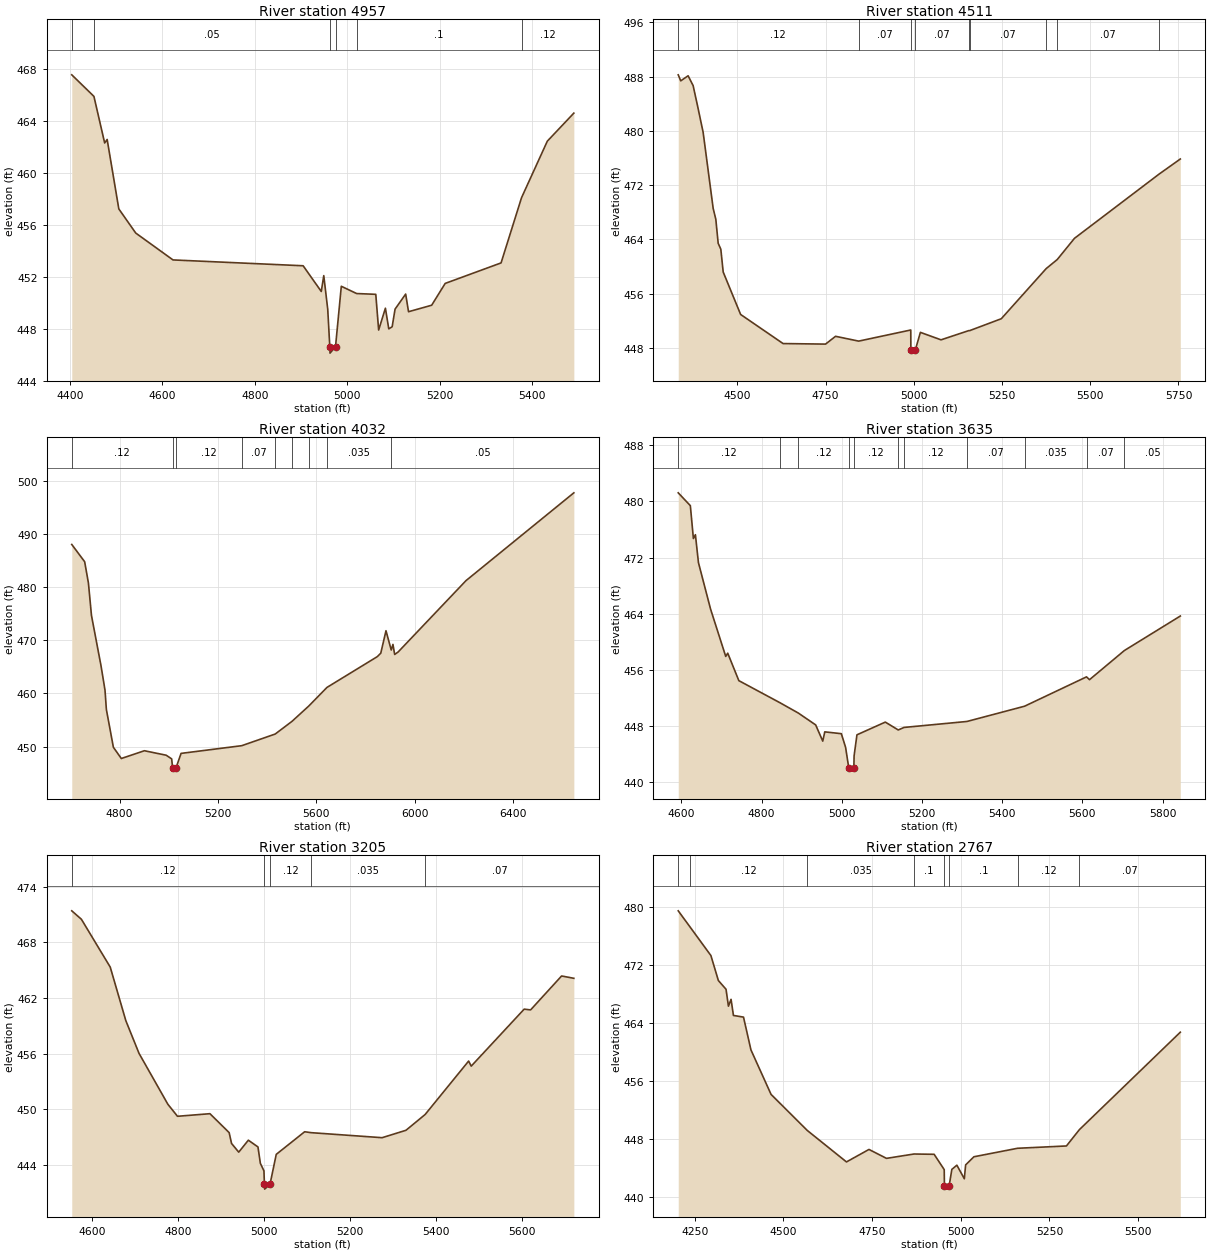
Type RM Length L Ch R = 1 ,4957    ,446,446,446
BEGIN DESCRIPTION:
LONG BRANCH 9.0
END DESCRIPTION:
XS GIS Cut Line= 3
      2336174.99       13765875.        2335625.       13765675.
      2335225.02     13765974.99
#Sta/Elev= 30
  4404.5  467.57  4452.4  465.91  4475.6  462.32    4481  462.59  4506.2  457.24
  4542.8  455.38  4623.3  453.31  4904.6  452.86  4943.8  450.88  4949.2   452.1
  4957.8  449.49  4962.2  446.63  4962.7  446.13  4974.6  446.63  4987.1  451.28
  5020.2  450.72  5061.6  450.66  5067.8  447.91  5082.4  449.59  5089.7     448
    5097  448.16  5103.3  449.52  5126.2  450.68  5132.4  449.32  5182.4  449.82
  5211.6   451.5  5332.4  453.08  5376.6   458.1  5432.4  462.46  5489.7  464.62
#Mann= 6 ,-1 , 0
  4404.5     .07       0  4452.4     .05       0  4962.2     .05       0
  4974.6     .05       0  5020.2      .1       0  5376.6     .12       0
Bank Sta=4962.2,4974.6
XS Rating Curve= 0 ,0
Exp/Cntr=0.3,0.1

Type RM Length L Ch R = 1 ,4511    ,479,479,479
BEGIN DESCRIPTION:
LONG BRANCH 8.0
END DESCRIPTION:
XS GIS Cut Line= 3
        2335975.       13764775.        2335525.       13765275.
      2334924.99     13765725.01
#Sta/Elev= 30
  4332.5  488.26  4339.6  487.37  4360.5  488.12  4374.7  486.67  4387.3  483.67
  4403.1  479.77  4431.5  468.56    4439  466.97  4445.7  463.42  4453.2  462.55
  4459.9  459.19  4509.3  452.93  4629.6  448.64  4749.9  448.56  4778.3  449.71
  4843.8     449  4991.4  450.64  4991.7  447.73  4992.2  447.23  5004.5  447.73
  5018.7  450.29  5077.1  449.19  5155.8  450.55  5158.5  450.55  5247.9   452.3
  5375.1  459.69  5406.5  461.03  5455.2  464.15  5694.7  473.61  5755.2  475.85
#Mann= 10 ,-1 , 0
  4332.5     .07       0  4387.3     .12       0  4843.8     .07       0
  4991.7     .05       0  5004.5     .07       0  5155.8     .12       0
  5158.5     .07       0  5375.1     .12       0  5406.5     .07       0
  5694.7     .05       0
Bank Sta=4991.7,5004.5
XS Rating Curve= 0 ,0
Exp/Cntr=0.3,0.1

Type RM Length L Ch R = 1 ,4032    ,397,397,397
BEGIN DESCRIPTION:
LONG BRANCH 7.0
END DESCRIPTION:
XS GIS Cut Line= 3
        2335875.       13764675.      2335377.24     13764934.79
      2334324.99     13765975.01
#Sta/Elev= 30
  4605.4  487.99  4657.8  484.75  4673.1  480.76  4685.5  474.66  4724.1  465.26
  4740.5  460.64  4746.1  456.99  4774.6   449.9  4806.8  447.79  4900.7  449.25
  4989.1  448.41  5011.5  447.72  5015.6  445.92  5016.1  445.42  5028.4  445.92
  5049.7  448.75  5296.6   450.2  5432.6  452.39  5500.2  454.75  5568.6  457.63
  5642.8  461.14  5847.4  466.92  5861.6  467.57  5882.8  471.79  5904.1  468.17
  5911.1  469.22  5918.1  467.33  5932.3   467.8  6208.1   481.2  6646.5  497.69
#Mann= 9 ,-1 , 0
  4605.4     .12       0  5015.6     .05       0  5028.4     .12       0
  5296.6     .07       0  5432.6     .12       0  5500.2     .07       0
  5568.6     .12       0  5642.8    .035       0  5904.1     .05       0
Bank Sta=5015.6,5028.4
XS Rating Curve= 0 ,0
Exp/Cntr=0.3,0.1

Type RM Length L Ch R = 1 ,3635    ,430,430,430
BEGIN DESCRIPTION:
LONG BRANCH 6.0
END DESCRIPTION:
XS GIS Cut Line= 3
      2335774.97       13764625.        2335375.       13764575.
      2334775.01     13765174.99
#Sta/Elev= 30
  4592.4  481.22  4622.6  479.39  4630.2  474.71  4635.2  475.26  4642.8  471.28
    4673  464.67  4710.8  457.93  4715.8  458.39  4743.5  454.48  4845.6  451.35
  4891.7  449.87    4935  448.18  4952.7  445.87  4957.7  447.19    4999  446.93
  5009.6  444.99  5017.4   442.1  5017.9   441.6  5030.2   442.1  5030.8  443.77
  5037.9  446.77  5108.6  448.58  5140.9  447.46  5155.3  447.82  5312.2  448.67
  5455.7  450.84  5610.2  455.02  5617.7  454.62  5704.6  458.77    5844  463.68
#Mann= 11 ,-1 , 0
  4592.4     .12       0  4845.6     .07       0  4891.7     .12       0
  5017.4     .05       0  5030.2     .12       0  5140.9     .07       0
  5155.3     .12       0  5312.2     .07       0  5455.7    .035       0
  5610.2     .07       0  5704.6     .05       0
Bank Sta=5017.4,5030.2
XS Rating Curve= 0 ,0
Exp/Cntr=0.3,0.1

Type RM Length L Ch R = 1 ,3205    ,438,438,438
BEGIN DESCRIPTION:
LONG BRANCH 5.0
END DESCRIPTION:
XS GIS Cut Line= 3
      2335325.01     13763924.98        2335125.       13764325.
      2334725.02     13764924.96
#Sta/Elev= 30
  4553.5   471.4  4575.9  470.49    4643  465.33  4679.3  459.55    4710  456.02
  4777.1  450.53  4799.5  449.23    4875  449.51  4919.7  447.47  4925.3   446.3
    4942  445.36  4964.4  446.65  4986.8  445.92  4992.3  444.16  5000.7  443.34
  5001.8  441.87  5002.3  441.37  5014.7  441.87  5029.3  445.12  5095.4  447.56
  5111.1  447.46  5275.7  446.92  5331.2  447.72  5375.7  449.42    5477  455.19
    5483  454.64  5606.2  460.79  5621.2  460.71  5693.3  464.37  5721.8  464.12
#Mann= 5 ,-1 , 0
  4553.5     .12       0  5001.8     .05       0  5014.7     .12       0
  5111.1    .035       0  5375.7     .07       0
Bank Sta=5001.8,5014.7
XS Rating Curve= 0 ,0
Exp/Cntr=0.3,0.1

Type RM Length L Ch R = 1 ,2767    ,484,484,484
BEGIN DESCRIPTION:
LONG BRANCH 4.0
END DESCRIPTION:
XS GIS Cut Line= 3
      2335325.03     13763624.97        2334775.       13764225.
        2334725.     13764825.04
#Sta/Elev= 30
  4203.2  479.45  4235.1  477.32  4295.4  473.28  4316.4  469.84    4338  468.64
  4344.8  466.31  4352.2  467.25  4358.9  465.03  4387.3   464.8  4408.3  460.28
    4465  454.15  4567.1  449.18  4677.7  444.84  4741.2  446.56  4790.6  445.33
  4868.2  445.93    4925  445.89  4953.4  443.78    4954  441.59  4954.5  441.09
  4967.5  441.59  4974.9  443.81  4989.1  444.39  5010.1  442.52  5013.8  444.43
  5037.2  445.55  5160.2  446.72  5298.1  447.04  5334.5  449.28  5619.3  462.72
#Mann= 8 ,-1 , 0
  4203.2     .07       0  4235.1     .12       0  4567.1    .035       0
  4868.2      .1       0    4954     .05       0  4967.5      .1       0
  5160.2     .12       0  5334.5     .07       0
Bank Sta=4954,4967.5
XS Rating Curve= 0 ,0
Exp/Cntr=0.3,0.1

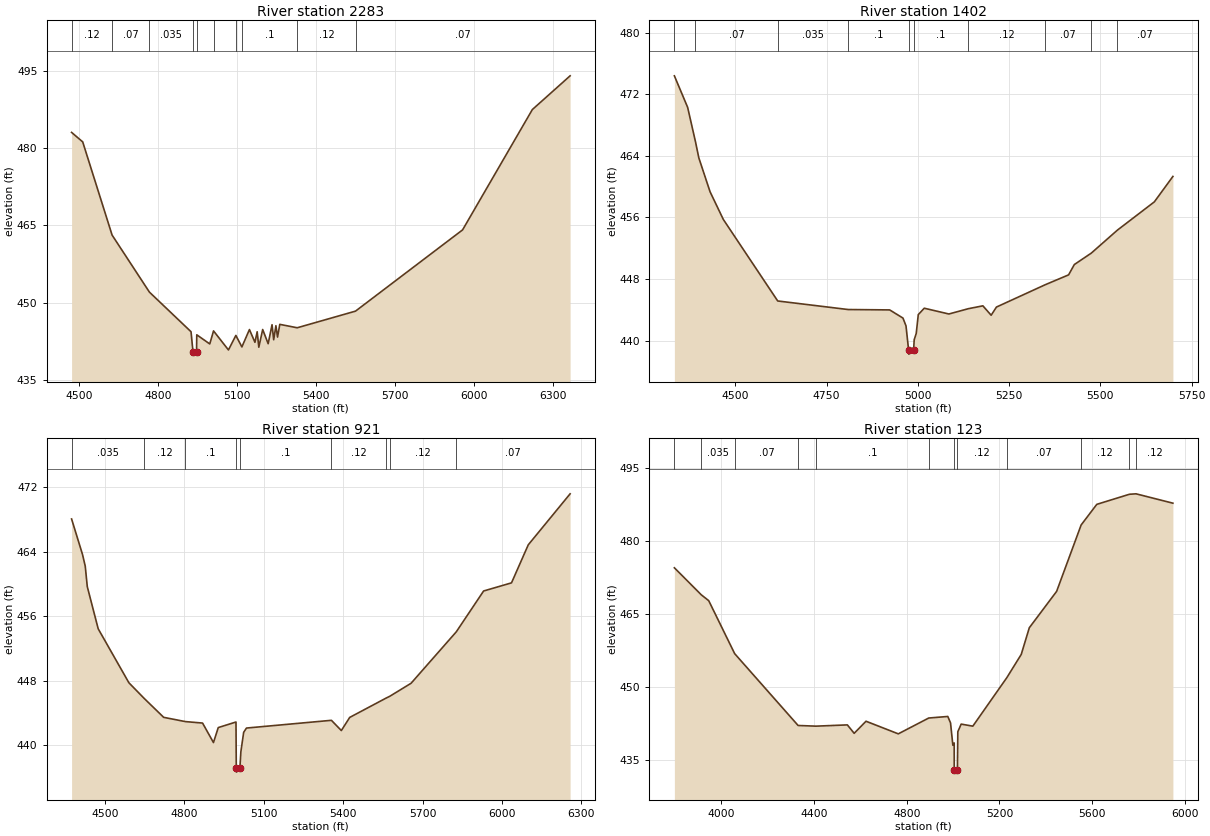
Type RM Length L Ch R = 1 ,2283    ,881,881,881
BEGIN DESCRIPTION:
LONG BRANCH 3.0
END DESCRIPTION:
XS GIS Cut Line= 3
      2335274.97     13763525.03        2334875.       13763875.
      2333775.01     13764674.99
#Sta/Elev= 30
  4472.9  483.05  4515.1  481.21  4626.6  463.11  4768.1  452.04  4926.1  444.34
  4933.5  440.49    4934  439.99    4947  440.49  4947.9  443.74  4997.2  441.97
  5011.5   444.5  5068.1   440.8  5096.2  443.62  5119.1  441.39  5147.7  444.76
  5168.6  442.29  5177.1  444.33  5183.3  441.33    5198  444.77  5218.8  442.01
  5233.5   445.7  5239.7  442.78  5248.2  445.51  5254.4   443.3  5262.9  445.77
  5329.1  445.11  5550.2  448.34  5956.5  464.12  6221.2  487.49  6364.5  494.04
#Mann= 10 ,-1 , 0
  4472.9     .12       0  4626.6     .07       0  4768.1    .035       0
  4933.5    .035       0    4947    .035       0  5011.5      .1       0
  5096.2     .12       0  5119.1      .1       0  5329.1     .12       0
  5550.2     .07       0
Bank Sta=4933.5,4947
XS Rating Curve= 0 ,0
Exp/Cntr=0.3,0.1

Type RM Length L Ch R = 1 ,1402    ,481,481,481
BEGIN DESCRIPTION:
LONG BRANCH 2.0
END DESCRIPTION:
XS GIS Cut Line= 3
      2335074.97     13763325.02        2334475.       13763625.
        2334125.     13764224.99
#Sta/Elev= 30
  4333.3  474.39  4369.6   470.3  4391.1  465.83  4400.3  463.73  4431.1  459.33
  4467.4  455.74  4616.3  445.16    4809  444.05    4923     444  4959.4  442.94
  4967.7  441.92  4974.9  438.76  4975.4  438.26  4988.5  438.76  4990.1  440.12
  4995.7  440.95  5001.3  443.39  5017.7  444.22  5085.1  443.47  5138.7  444.16
  5178.2  444.53  5200.9  443.31  5215.4  444.37  5348.1  447.25    5413  448.55
  5428.7  449.89  5475.1  451.37  5546.5  454.35  5647.9  458.03  5698.7  461.33
#Mann= 10 ,-1 , 0
  4333.3     .12       0  4391.1     .07       0  4616.3    .035       0
    4809      .1       0  4974.9     .05       0  4988.5      .1       0
  5138.7     .12       0  5348.1     .07       0  5475.1     .12       0
  5546.5     .07       0
Bank Sta=4974.9,4988.5
XS Rating Curve= 0 ,0
Exp/Cntr=0.3,0.1

Type RM Length L Ch R = 1 ,921     ,798,798,798
BEGIN DESCRIPTION:
LONG BRANCH 1.0
END DESCRIPTION:
XS GIS Cut Line= 3
      2334975.03     13763024.99        2334375.       13763175.
        2333975.     13764374.99
#Sta/Elev= 30
  4373.7  468.09    4415  463.68  4425.3  462.23    4433  459.69  4474.2  454.46
  4590.2  447.76  4648.2  445.81  4721.6  443.47  4803.9  442.94  4868.5  442.76
  4909.7  440.34  4927.8   442.2  4994.8  442.89  4995.9  437.17  4996.4  436.67
  5009.5  437.17  5013.3  439.22  5023.8  441.61  5034.4  442.14  5355.3   443.1
  5392.8  441.83  5424.4  443.46  5560.8  445.84  5576.2  446.09  5656.3   447.7
    5827  454.08  5930.3  459.15  6035.7  460.16    6099  464.88  6257.1  471.21
#Mann= 9 ,-1 , 0
  4373.7    .035       0  4648.2     .12       0  4803.9      .1       0
  4995.9     .05       0  5009.5      .1       0  5355.3     .12       0
  5560.8     .07       0  5576.2     .12       0    5827     .07       0
Bank Sta=4995.9,5009.5
XS Rating Curve= 0 ,0
Exp/Cntr=0.3,0.1

Type RM Length L Ch R = 1 ,123     ,0,0,0
BEGIN DESCRIPTION:
A19712
END DESCRIPTION:
XS GIS Cut Line= 4
      2335148.12      13762858.4      2334530.02     13762907.02
      2333807.79     13763323.68      2333543.89     13763969.54
#Sta/Elev= 30
  3796.9  474.55  3913.1     469  3945.1   467.8  4057.1  456.92  4330.8  442.17
  4407.6  442.03  4543.4  442.29  4572.8  440.56  4623.9  443.04  4763.2  440.45
  4894.6   443.7  4976.9  444.02  4988.7   442.7  4998.7  438.12  5004.5  438.58
  5004.7  433.09  5005.2  432.59  5018.3  433.09  5020.2  440.89  5034.6  442.45
  5084.9  442.03  5231.8     452  5293.8  456.76  5328.7  462.24  5446.6  469.71
  5552.3  483.34  5619.9  487.58  5760.8  489.65  5789.3  489.74  5948.4  487.82
#Mann= 12 ,-1 , 0
  3796.9     .12       0  3913.1    .035       0  4057.1     .07       0
  4330.8     .12       0  4407.6      .1       0  4894.6     .12       0
  5004.7     .05       0  5018.3     .12       0  5231.8     .07       0
  5552.3     .12       0  5760.8     .07       0  5789.3     .12       0
Bank Sta=5004.7,5018.3
XS Rating Curve= 0 ,0
Exp/Cntr=0.3,0.1

Chan Stop Cuts=-1
Use User Specified Reach Order=0
Composite Channel Slope=5