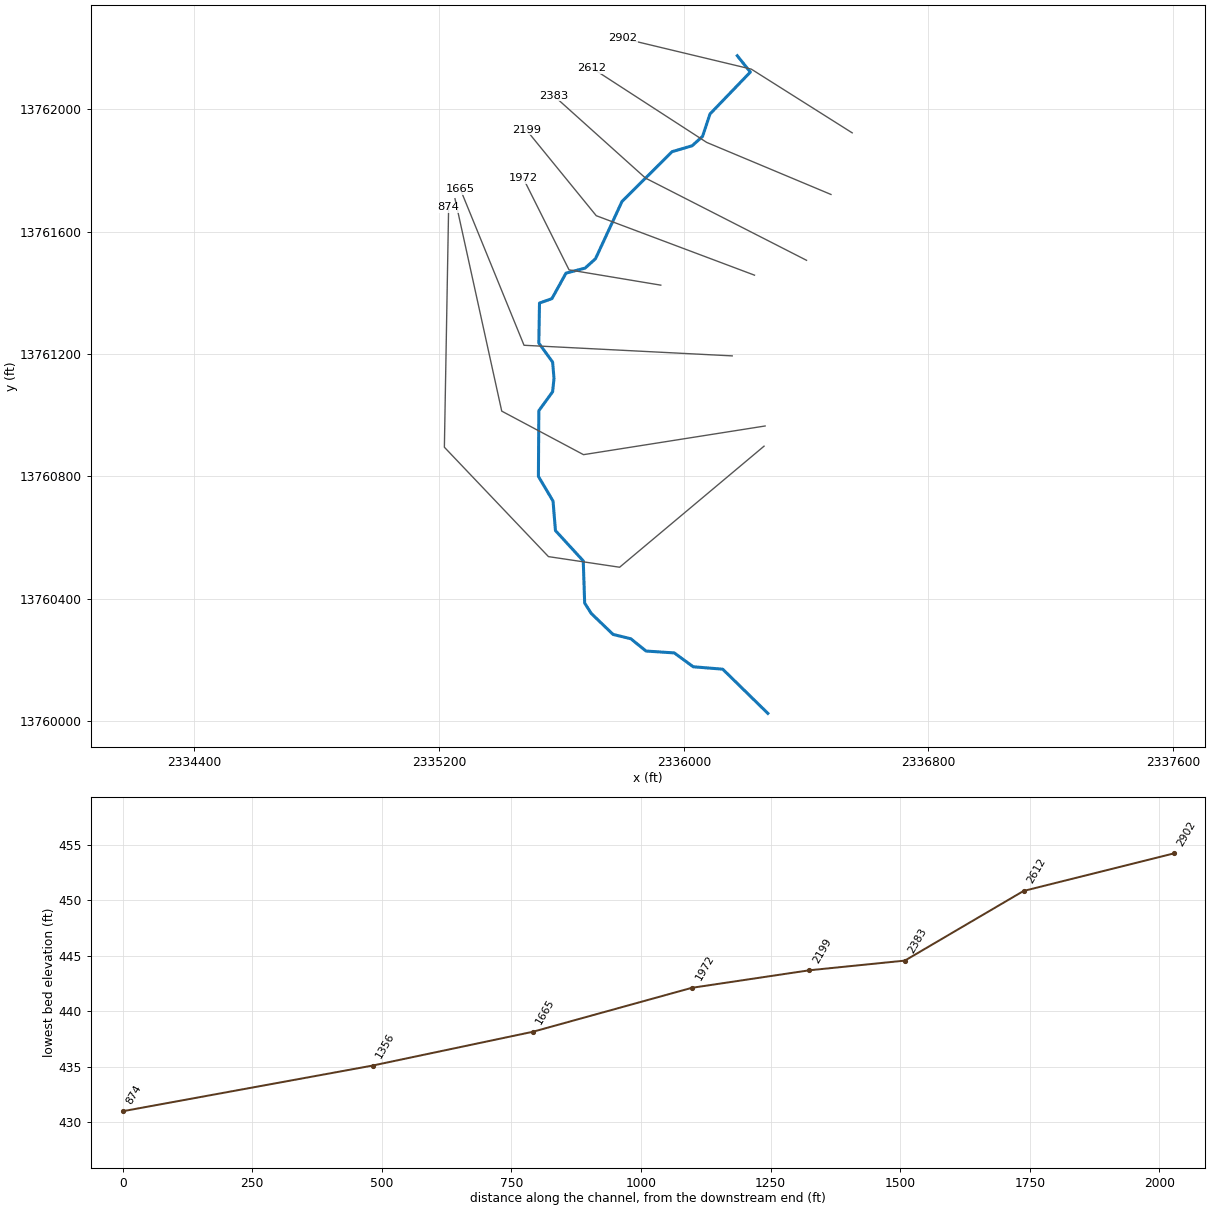
--- MILL CREEK TRIBUTARY D.prj (project) ---

Proj Title=MILL CREEK TRIBUTARY D Base Level Engineering
Current Plan=p01
Default Exp/Contr=0.3,0.1
English Units
Geom File=g01
Flow File=f01
Plan File=p01
Y Axis Title=Elevation
X Axis Title(PF)=Main Channel Distance
X Axis Title(XS)=Station
BEGIN DESCRIPTION:
MILL CREEK TRIBUTARY D
END DESCRIPTION:
DSS Export Rating Curves= 0
DSS Export Rating Curve Sorted= 0
DSS Export Volume Flow Curves= 0
DXF OffsetX= 0
DXF OffsetY= 0
DXF ScaleX= 1
DXF ScaleY= 10

--- MILL CREEK TRIBUTARY D.p01 (plan) ---

Plan Title=Multiple Run
Short Identifier=Multiple
Geom File=g01
Flow File=f01
Subcritical Flow
K Sum by GR= 0
Std Step Tol= 0.01
Critical Tol= 0.01
Num of Std Step Trials= 20
Max Error Tol= 0.3
Flow Tol Ratio= 0.001
Split Flow NTrial= 30
Split Flow Tol= 0.02
Split Flow Ratio= 0.02
Log Output Level= 0
Friction Slope Method= 1
Unsteady Friction Slope Method= 2
Unsteady Bridges Friction Slope Method= 1
Parabolic Critical Depth
Global Vel Dist=  1 , 1 , 1
Global Log Level= 0
CheckData=True
Encroach Param= -1, 0, 0, 0
BEGIN DESCRIPTION:
Multiple Run
END DESCRIPTION:

--- MILL CREEK TRIBUTARY D.f01 (steady flow) ---

Flow Title=Multiple
Number of Profiles=7
Profile Names=10-year,25-year,50-year,1pct_min,100-year,1pct_plu,500-year
River Rch & RM= MILL CREEK TRIBU,Reach-1,2902
     303     471     617     393     784    1565    1253
Boundary for River Rch & Prof#=MILL CREEK TRIBU,Reach-1,1
Up Type=0
Dn Type=3
Dn Slope=0.005
Boundary for River Rch & Prof#=MILL CREEK TRIBU,Reach-1,2
Up Type=0
Dn Type=3
Dn Slope=0.005
Boundary for River Rch & Prof#=MILL CREEK TRIBU,Reach-1,3
Up Type=0
Dn Type=3
Dn Slope=0.005
Boundary for River Rch & Prof#=MILL CREEK TRIBU,Reach-1,4
Up Type=0
Dn Type=3
Dn Slope=0.005
Boundary for River Rch & Prof#=MILL CREEK TRIBU,Reach-1,5
Up Type=0
Dn Type=3
Dn Slope=0.005
Boundary for River Rch & Prof#=MILL CREEK TRIBU,Reach-1,6
Up Type=0
Dn Type=3
Dn Slope=0.005
Boundary for River Rch & Prof#=MILL CREEK TRIBU,Reach-1,7
Up Type=0
Dn Type=3
Dn Slope=0.005

--- MILL CREEK TRIBUTARY D.g01 (geometry) ---

Geom Title=Existing Conditions
Program Version=4.10

River Reach=MILL CREEK TRIBU,Reach-1
Reach XY= 30
        2336175.       13762175.      2336217.75     13762121.67
      2336085.79     13761984.66      2336061.51     13761911.44
      2336027.54     13761880.75       2335961.8     13761861.36
      2335798.01     13761698.47      2335711.52     13761511.44
      2335677.51     13761480.76      2335615.04     13761464.29
      2335568.93     13761380.83      2335528.39     13761366.56
       2335526.2     13761235.52      2335571.29      13761173.4
      2335575.81     13761119.97       2335571.3      13761076.6
      2335526.22      13761014.5       2335524.8     13760799.92
      2335572.64     13760719.02      2335580.54     13760622.58
      2335671.44     13760523.53      2335676.06     13760385.43
      2335697.84     13760351.42      2335768.92     13760283.13
      2335827.17     13760268.86      2335876.58     13760228.82
      2335969.03     13760222.65      2336030.98     13760177.36
      2336127.43     13760169.48        2336275.       13760025.

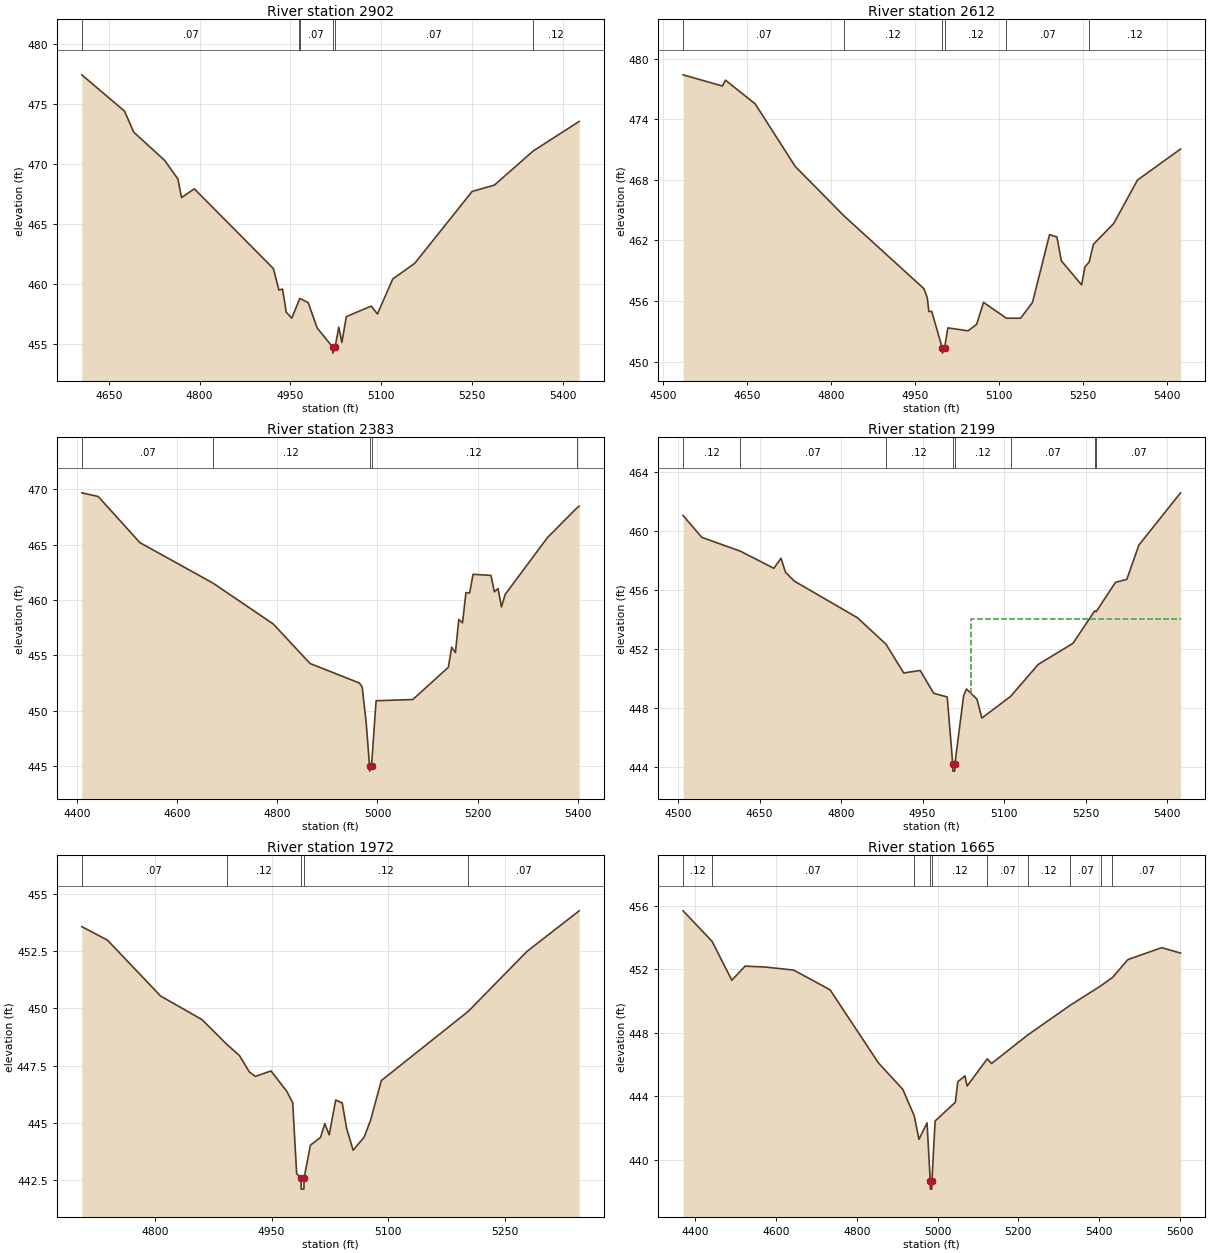
Type RM Length L Ch R = 1 ,2902    ,290,290,290
BEGIN DESCRIPTION:
MILL CREEK TRIBUTARY D 4.0
END DESCRIPTION:
XS GIS Cut Line= 3
      2336550.73     13761922.92      2336220.87     13762131.25
      2335800.71     13762231.95
#Sta/Elev= 30
  4605.3  477.45  4675.9  474.42  4691.2  472.66  4742.2  470.31  4764.2  468.75
  4770.1   467.2  4791.3  467.93  4921.9  461.28  4931.2  459.48  4937.1  459.56
  4943.3  457.63  4952.4  457.13  4964.2  458.59  4965.7  458.78  4979.5  458.43
  4994.3  456.32    5020  454.71  5020.3  454.21    5024  454.71  5030.1  456.38
  5035.2  455.11  5042.6  457.26  5083.7  458.14    5094  457.48  5119.3   460.4
  5155.7  461.71  5250.5  467.71  5287.3  468.24  5351.4  471.09  5427.5  473.56
#Mann= 6 ,-1 , 0
  4605.3     .07       0  4964.2     .12       0  4965.7     .07       0
    5020     .05       0    5024     .07       0  5351.4     .12       0
Bank Sta=5020,5024
XS Rating Curve= 0 ,0
Exp/Cntr=0.3,0.1

Type RM Length L Ch R = 1 ,2612    ,229,229,229
BEGIN DESCRIPTION:
B19461
END DESCRIPTION:
XS GIS Cut Line= 3
      2336481.33     13761721.51      2336075.04     13761891.67
      2335700.01     13762134.75
#Sta/Elev= 30
    4536   478.4  4606.1  477.29  4611.5  477.87  4664.5  475.53  4735.9  469.33
  4823.3  464.41  4965.7  457.21  4971.6   456.3  4974.3  454.96  4979.5  454.96
  4998.4  451.33  4998.6  450.83  5002.4  451.33  5008.3  453.33  5044.5  453.04
  5059.7  453.69  5071.9  455.86  5112.6  454.29  5138.1  454.29  5159.3  455.85
  5189.6  462.56  5202.9  462.34  5210.7  459.98  5246.9  457.59  5252.9  459.38
  5260.4  459.85    5268  461.61  5304.3  463.68  5346.5  467.97  5423.4  471.05
#Mann= 6 ,-1 , 0
    4536     .07       0  4823.3     .12       0  4998.4     .05       0
  5002.4     .12       0  5112.6     .07       0  5260.4     .12       0
Bank Sta=4998.4,5002.4
XS Rating Curve= 0 ,0
Exp/Cntr=0.3,0.1

Type RM Length L Ch R = 1 ,2383    ,184,184,184
BEGIN DESCRIPTION:
MILL CREEK TRIBUTARY D 3.0
END DESCRIPTION:
XS GIS Cut Line= 3
      2336401.44     13761506.25        2335875.       13761775.
      2335575.02     13762044.46
#Sta/Elev= 30
  4408.9  469.67  4441.7  469.34    4525  465.18  4671.3  461.52  4791.6  457.84
  4865.2  454.27  4963.8  452.51  4969.4  452.15  4977.5  448.88  4984.1  445.06
  4984.3  444.56  4988.1  445.06  4997.2  450.91  5070.6  451.02  5141.6  453.93
  5148.3  455.74  5155.8  455.26  5162.5  458.24    5170  457.94  5176.8  460.67
  5184.2  460.63    5191  462.32  5226.8  462.22  5233.6  460.74    5241  461.03
  5247.8  459.37  5255.2   460.5  5339.7  465.63  5398.2  468.29  5403.2  468.46
#Mann= 5 ,-1 , 0
  4408.9     .07       0  4671.3     .12       0  4984.1     .05       0
  4988.1     .12       0  5398.2     .07       0
Bank Sta=4984.1,4988.1
XS Rating Curve= 0 ,0
Exp/Cntr=0.3,0.1

Type RM Length L Ch R = 1 ,2199    ,227,227,227
BEGIN DESCRIPTION:
B19460
END DESCRIPTION:
XS GIS Cut Line= 3
      2336231.32     13761457.63      2335713.93     13761652.08
      2335484.78     13761933.32
#Sta/Elev= 30
  4509.3  461.03  4543.6  459.55  4614.8  458.61  4676.3  457.45  4689.5  458.13
  4697.7  457.18  4714.4  456.57    4830   454.1  4882.7   452.3  4915.3  450.35
  4945.6  450.52  4970.5  448.97  4995.4  448.72  5005.5  444.19  5005.7  443.69
  5009.2  443.69  5009.5  444.19  5025.6  448.82  5030.9  449.26  5050.2  448.57
  5059.1  447.29    5112  448.76  5162.9  450.93  5226.8  452.36    5267  454.57
  5269.6  454.51  5305.1   456.5  5325.9   456.7  5348.2  459.03  5424.8  462.57
#Mann= 8 ,-1 , 0
  4509.3     .12       0  4614.8     .07       0  4882.7     .12       0
  5005.5     .05       0  5009.5     .12       0    5112     .07       0
    5267     .12       0  5269.6     .07       0
#XS Ineff= 2 , 0
       0                    5040       0     454
Permanent Ineff=
       F       F
Bank Sta=5005.5,5009.5
XS Rating Curve= 0 ,0
Exp/Cntr=0.3,0.1

Type RM Length L Ch R = 1 ,1972    ,307,307,307
BEGIN DESCRIPTION:
MILL CREEK TRIBUTARY D 2.0
END DESCRIPTION:
XS GIS Cut Line= 3
      2335925.02       13761425.        2335625.       13761475.
      2335474.98     13761775.03
#Sta/Elev= 30
  4705.9  453.57  4738.9  452.98  4807.3  450.54  4860.5  449.51  4892.1  448.44
  4908.7  447.94  4921.3  447.23    4929  447.03  4949.2  447.27  4969.5  446.38
  4977.1  445.88  4982.2  442.78  4987.8  442.61    4988  442.11  4991.5  442.11
  4991.8  442.61  4999.9  444.03  5012.9  444.37  5018.4  444.97    5024  444.48
  5032.4     446  5040.8  445.87  5046.4  444.77  5054.8  443.81  5068.8  444.37
  5077.1   445.1  5091.1  446.85  5202.8  449.87  5278.4  452.49  5345.5  454.26
#Mann= 5 ,-1 , 0
  4705.9     .07       0  4892.1     .12       0  4987.8     .05       0
  4991.8     .12       0  5202.8     .07       0
Bank Sta=4987.8,4991.8
XS Rating Curve= 0 ,0
Exp/Cntr=0.3,0.1

Type RM Length L Ch R = 1 ,1665    ,309,309,309
BEGIN DESCRIPTION:
B19459
END DESCRIPTION:
XS GIS Cut Line= 3
      2336158.42     13761193.75      2335477.82     13761228.47
      2335269.74     13761738.26
#Sta/Elev= 30
  4369.9  455.67  4441.6  453.75  4490.5   451.3  4523.5  452.19  4573.6  452.13
  4643.7  451.94  4733.8   450.7  4853.9  446.09    4914  444.43  4942.3  442.77
  4954.1  441.29  4974.1  442.32  4982.1  438.65  4982.4  438.15  4985.9  438.15
  4986.1  438.65  4994.1  442.44  5044.2  443.62  5050.3  444.91    5068  445.28
  5073.4  444.64  5123.2  446.35    5134  446.06  5223.3  447.85  5328.4  449.72
    5404  450.94  5433.4  451.47  5471.6   452.6  5555.3  453.35    5602  453.01
#Mann= 10 ,-1 , 0
  4369.9     .12       0  4441.6     .07       0  4942.3     .12       0
  4982.1     .05       0  4986.1     .12       0  5123.2     .07       0
  5223.3     .12       0  5328.4     .07       0    5404     .12       0
  5433.4     .07       0
Bank Sta=4982.1,4986.1
XS Rating Curve= 0 ,0
Exp/Cntr=0.3,0.1

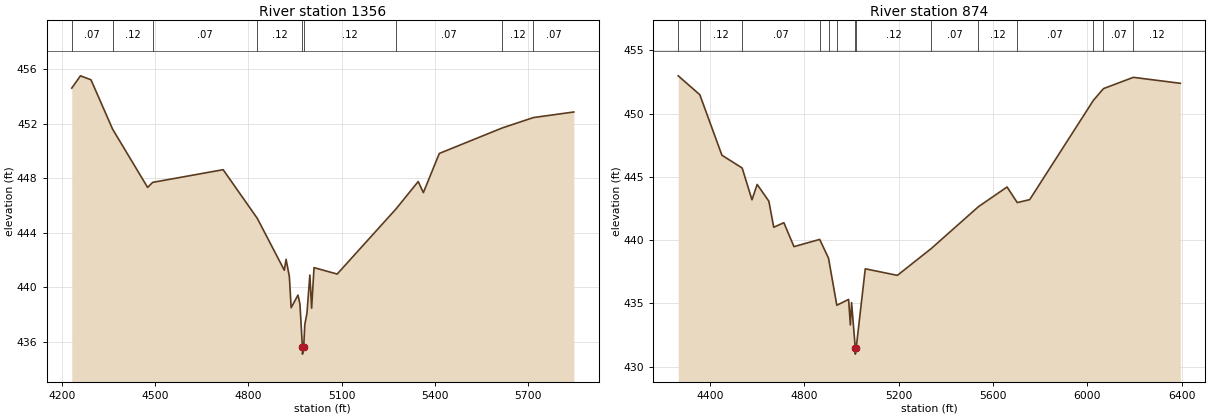
Type RM Length L Ch R = 1 ,1356    ,482,482,482
BEGIN DESCRIPTION:
B19458
END DESCRIPTION:
XS GIS Cut Line= 4
      2336266.03     13760964.59      2335672.26     13760870.83
       2335404.9     13761013.19      2335252.12     13761707.66
#Sta/Elev= 30
  4231.8  454.61  4259.7  455.51  4293.6  455.22  4363.2   451.6  4475.8  447.33
  4492.1   447.7  4718.8  448.63  4828.7  445.06  4915.5  441.26  4921.2  442.06
  4931.8  440.79  4937.5  438.51  4959.5  439.44  4965.8  438.78  4973.8  435.61
    4974  435.11  4977.8  435.61  4981.4  437.27  4988.4  438.11  4997.7  440.91
  5003.4  438.48  5011.1  441.45  5085.6  440.98  5275.1  445.76  5346.2  447.76
  5362.9  446.95  5414.1  449.82  5616.7  451.69  5716.8  452.45  5846.9  452.86
#Mann= 9 ,-1 , 0
  4231.8     .07       0  4363.2     .12       0  4492.1     .07       0
  4828.7     .12       0  4973.8     .05       0  4977.8     .12       0
  5275.1     .07       0  5616.7     .12       0  5716.8     .07       0
Bank Sta=4973.8,4977.8
XS Rating Curve= 0 ,0
Exp/Cntr=0.3,0.1

Type RM Length L Ch R = 1 ,874     ,0,0,0
BEGIN DESCRIPTION:
B19457
END DESCRIPTION:
XS GIS Cut Line= 5
      2336262.55     13760898.62      2335790.32     13760502.78
      2335557.68      13760537.5       2335217.4     13760895.14
      2335231.29     13761679.86
#Sta/Elev= 30
  4264.7  452.98  4356.2  451.49    4450  446.71  4535.9   445.7  4577.5  443.19
  4599.6   444.4  4649.1  443.08  4669.9  441.02  4712.8  441.38  4755.7  439.49
  4864.8  440.06  4902.2  438.58  4937.4  434.86  4987.4  435.32    4995   433.3
    5000  435.07  5015.7   431.5    5016     431  5019.7   431.5  5058.1  437.74
  5194.2  437.22  5338.1  439.34  5537.9  442.64  5659.6   444.2  5702.9  442.97
  5755.6   443.2  6025.7  451.04  6068.7  451.97  6195.4  452.86  6394.6  452.39
#Mann= 14 ,-1 , 0
  4264.7     .07       0  4356.2     .12       0  4535.9     .07       0
  4864.8     .12       0  4902.2      .1       0  4937.4     .12       0
  5015.7     .05       0  5019.7     .12       0  5338.1     .07       0
  5537.9     .12       0  5702.9     .07       0  6025.7     .12       0
  6068.7     .07       0  6195.4     .12       0
Bank Sta=5015.7,5019.7
XS Rating Curve= 0 ,0
Exp/Cntr=0.3,0.1

Chan Stop Cuts=-1
Use User Specified Reach Order=0
Composite Channel Slope=5