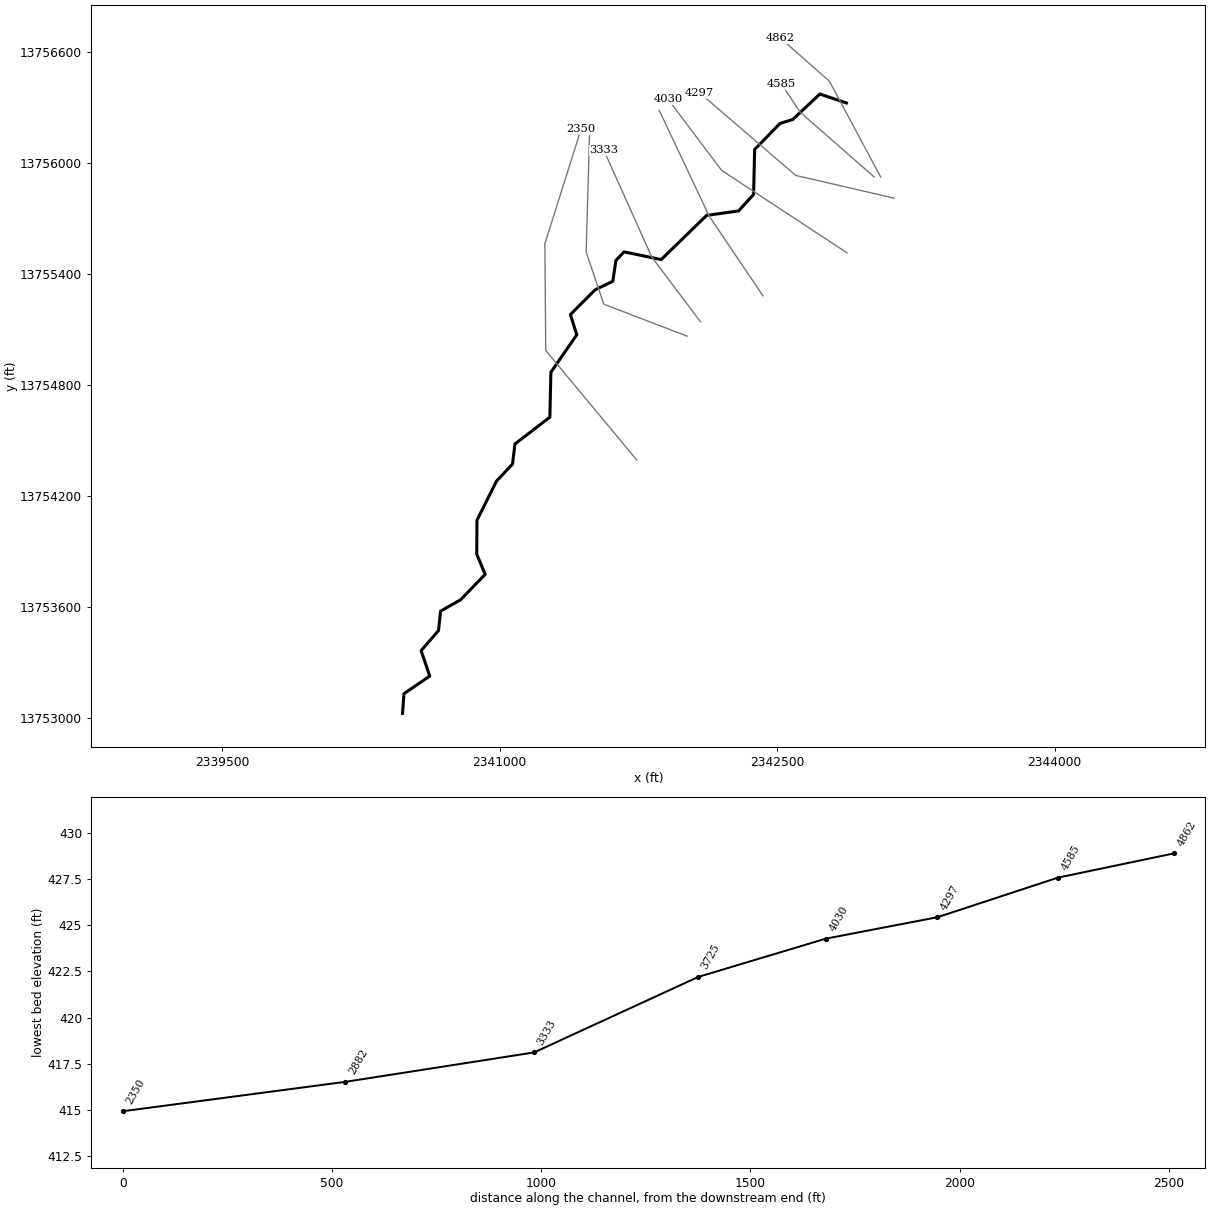
--- MILL TRIBUTARY 1.prj (project) ---

Proj Title=MILL TRIBUTARY 1 Base Level Engineering
Current Plan=p01
Default Exp/Contr=0.3,0.1
English Units
Geom File=g01
Flow File=f01
Plan File=p01
BEGIN DESCRIPTION:
MILL TRIBUTARY 1
END DESCRIPTION:

--- MILL TRIBUTARY 1.p01 (plan) ---

Plan Title=Multiple Run
Short Identifier=Multiple
Geom File=g01
Flow File=f01
Subcritical Flow
K Sum by GR= 0
Std Step Tol= 0.01
Critical Tol= 0.01
Num of Std Step Trials= 20
Max Error Tol= 0.3
Flow Tol Ratio= 0.001
Split Flow NTrial= 30
Split Flow Tol= 0.02
Split Flow Ratio= 0.02
Log Output Level= 0
Friction Slope Method= 1
Unsteady Friction Slope Method= 2
Unsteady Bridges Friction Slope Method= 1
Parabolic Critical Depth
Global Vel Dist=  1 , 1 , 1
Global Log Level= 0
CheckData=True
Encroach Param= -1, 0, 0, 0
BEGIN DESCRIPTION:
Multiple Run
END DESCRIPTION:

--- MILL TRIBUTARY 1.f01 (steady flow) ---

Flow Title=Multiple
Number of Profiles=7
Profile Names=10-year,25-year,50-year,1pct_min,100-year,1pct_plu,500-year
River Rch & RM= MILL TRIBUTARY 1,Reach-1,4862
     753    1230    1666    1092    2179    4347    3694
Boundary for River Rch & Prof#=MILL TRIBUTARY 1,Reach-1,1
Up Type=0
Dn Type=3
Dn Slope=0.005
Boundary for River Rch & Prof#=MILL TRIBUTARY 1,Reach-1,2
Up Type=0
Dn Type=3
Dn Slope=0.005
Boundary for River Rch & Prof#=MILL TRIBUTARY 1,Reach-1,3
Up Type=0
Dn Type=3
Dn Slope=0.005
Boundary for River Rch & Prof#=MILL TRIBUTARY 1,Reach-1,4
Up Type=0
Dn Type=3
Dn Slope=0.005
Boundary for River Rch & Prof#=MILL TRIBUTARY 1,Reach-1,5
Up Type=0
Dn Type=3
Dn Slope=0.005
Boundary for River Rch & Prof#=MILL TRIBUTARY 1,Reach-1,6
Up Type=0
Dn Type=3
Dn Slope=0.005
Boundary for River Rch & Prof#=MILL TRIBUTARY 1,Reach-1,7
Up Type=0
Dn Type=3
Dn Slope=0.005

--- MILL TRIBUTARY 1.g01 (geometry) ---

Geom Title=Existing Conditions

River Reach=MILL TRIBUTARY 1,Reach-1
Reach XY= 30
      2342875.00     13756325.00      2342731.02     13756373.41
      2342584.68     13756235.78      2342515.32     13756214.22
      2342378.54     13756073.54      2342372.95     13755830.84
      2342291.80     13755741.42      2342118.81     13755717.18
      2341873.50     13755478.46      2341672.42     13755520.03
      2341628.53     13755473.78      2341611.74     13755361.35
      2341515.34     13755314.21      2341382.50     13755181.05
      2341416.93     13755071.69      2341277.06     13754869.14
      2341271.47     13754626.45      2341082.75     13754481.45
      2341069.46     13754372.58      2340983.16     13754281.05
      2340877.24     13754069.07      2340876.24     13753885.50
      2340921.87     13753776.63      2340788.20     13753638.64
      2340680.42     13753577.67      2340669.46     13753472.58
      2340575.61     13753364.37      2340621.96     13753226.42
      2340482.60     13753131.55      2340475.00     13753025.00

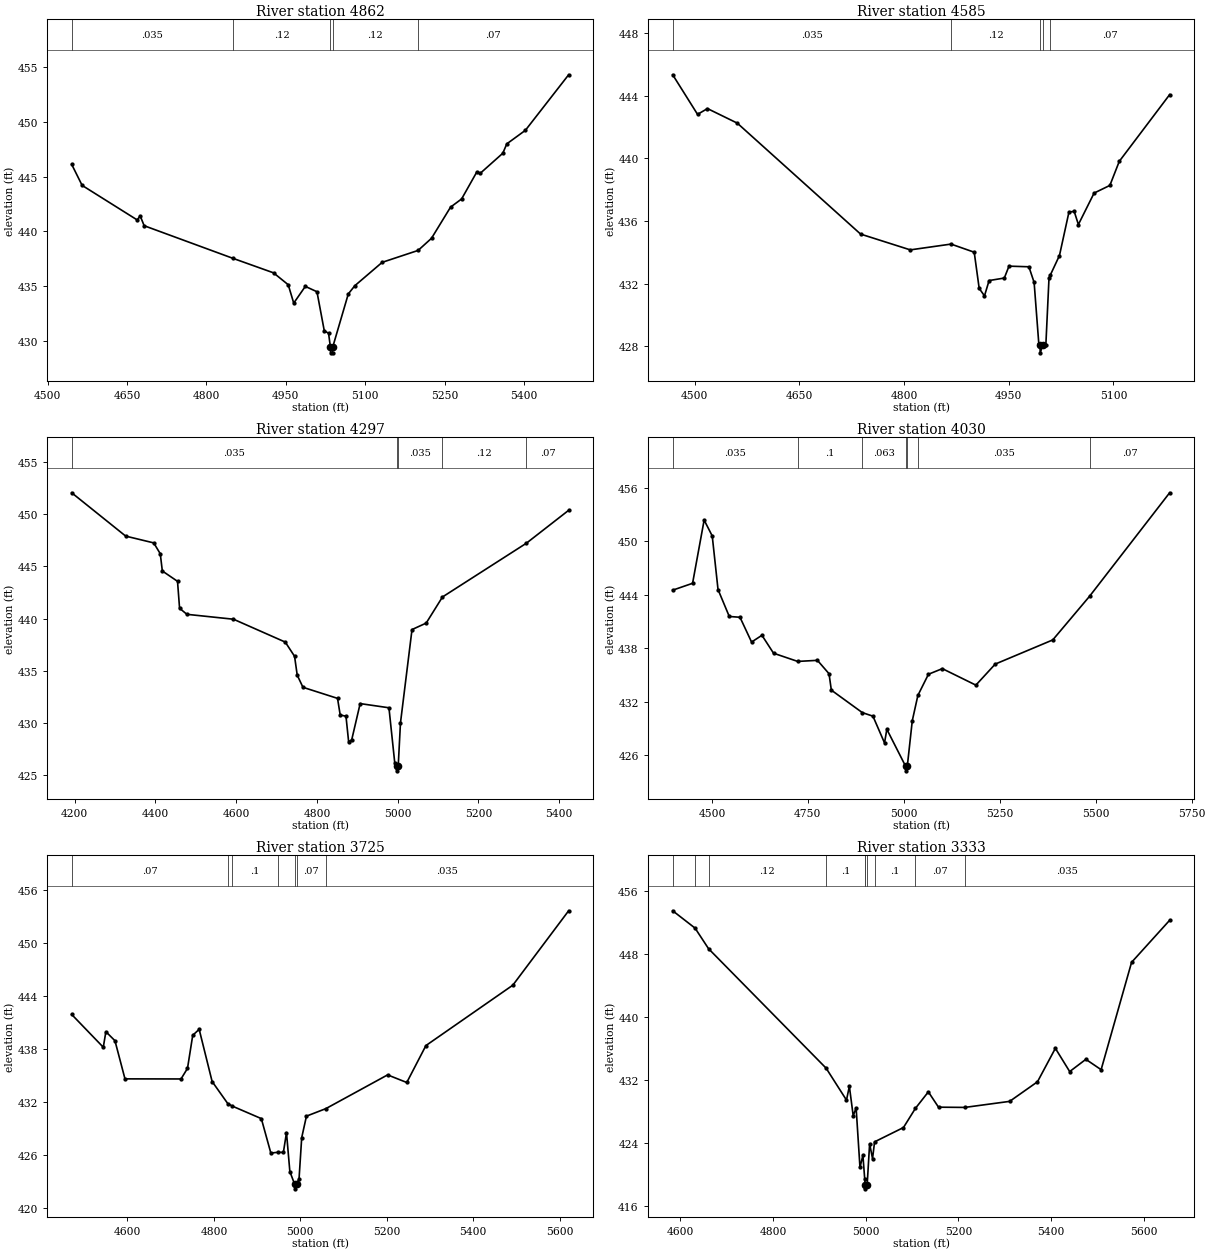
Type RM Length L Ch R = 1,4862,277,277,277
BEGIN DESCRIPTION:
B19465
END DESCRIPTION:
XS GIS Cut Line= 3
      2343060.13     13755924.25      2342782.55     13756443.00
      2342519.29     13756674.48
#Sta/Elev= 30
  4545.5  446.12  4565.2  444.20  4669.2  441.04  4674.9  441.41  4682.4  440.51
  4850.5  437.52  4926.8  436.20  4954.6  435.11  4965.0  433.43  4986.9  434.96
  5008.9  434.47  5022.7  430.90  5030.8  430.67  5034.4  429.38  5034.7  428.88
  5038.3  428.88  5038.5  429.38  5068.1  434.27  5080.4  435.02  5132.1  437.16
  5200.0  438.25  5225.3  439.36  5261.3  442.21  5282.2  442.96  5310.7  445.41
  5317.3  445.30  5360.0  447.14  5367.6  448.00  5402.7  449.24  5484.4  454.32
#Mann=5,-1,0
  4545.5   0.035       0  4850.5    0.12       0  5034.4    0.05       0
  5038.5    0.12       0  5200.0    0.07       0
Bank Sta=5034.4,5038.5
Exp/Cntr=0.3,0.1

Type RM Length L Ch R = 1,4585,288,288,288
BEGIN DESCRIPTION:
MILL TRIBUTARY 1 9.0
END DESCRIPTION:
XS GIS Cut Line= 3
      2343025.00     13755925.00      2342625.00     13756275.00
      2342524.99     13756425.01
#Sta/Elev= 30
  4468.7  445.34  4504.3  442.81  4518.5  443.18  4561.2  442.25  4737.8  435.16
  4809.0  434.15  4867.4  434.52  4900.6  434.00  4907.7  431.69  4915.3  431.21
  4921.9  432.19  4943.7  432.35  4950.4  433.11  4978.9  433.07  4986.4  432.07
  4993.1  428.15  4994.8  428.07  4995.1  427.57  4998.9  428.07  5003.2  428.07
  5007.7  432.34  5009.7  432.55  5022.7  433.79  5036.3  436.57  5043.8  436.61
  5049.8  435.77  5072.3  437.78  5094.9  438.27  5108.4  439.81  5180.5  444.07
#Mann=5,-1,0
  4468.7   0.035       0  4867.4    0.12       0  4994.8    0.05       0
  4998.9    0.12       0  5009.7    0.07       0
Bank Sta=4994.8,4998.9
Exp/Cntr=0.3,0.1

Type RM Length L Ch R = 1,4297,267,267,267
BEGIN DESCRIPTION:
MILL TRIBUTARY 1 8.0
END DESCRIPTION:
XS GIS Cut Line= 3
      2343132.90     13755810.53      2342600.55     13755933.38
      2342081.81     13756379.31
#Sta/Elev= 30
  4192.8  452.06  4326.5  447.91  4395.9  447.26  4412.1  446.22  4417.2  444.57
  4454.8  443.58  4459.9  441.00  4478.0  440.42  4593.4  439.95  4721.6  437.76
  4744.6  436.40  4751.2  434.59  4765.4  433.43  4851.0  432.37  4857.6  430.78
  4871.9  430.66  4878.5  428.21  4886.1  428.40  4907.0  431.87  4978.3  431.47
  4992.6  426.22  4997.1  425.93  4997.4  425.43  5001.3  425.93  5006.8  430.01
  5035.4  438.96  5070.5  439.58  5110.8  442.08  5318.6  447.23  5423.2  450.38
#Mann=5,-1,0
  4192.8   0.035       0  4997.1   0.035       0  5001.3   0.035       0
  5110.8    0.12       0  5318.6    0.07       0
Bank Sta=4997.1,5001.3
Exp/Cntr=0.3,0.1

Type RM Length L Ch R = 1,4030,305,305,305
BEGIN DESCRIPTION:
B19464
END DESCRIPTION:
XS GIS Cut Line= 3
      2342878.12     13755514.75      2342200.13     13755960.68
      2341909.48     13756346.70
#Sta/Elev= 30
  4397.9  444.53  4449.7  445.30  4479.8  452.39  4500.9  450.61  4516.0  444.60
  4545.3  441.58  4573.2  441.49  4603.4  438.71  4630.4  439.47  4660.6  437.46
  4723.5  436.54  4775.0  436.66  4805.2  435.16  4811.2  433.32  4891.9  430.80
  4919.6  430.40  4949.8  427.40  4955.8  428.93  5004.9  424.77  5005.2  424.27
  5009.1  424.77  5022.1  429.89  5036.7  432.73  5064.2  435.10  5100.4  435.73
  5187.8  433.88  5238.2  436.24  5388.1  438.95  5483.9  443.84  5692.6  455.45
#Mann=7,-1,0
  4397.9   0.035       0  4723.5     0.1       0  4891.9   0.063       0
  5004.9    0.05       0  5009.1   0.063       0  5036.7   0.035       0
  5483.9    0.07       0
Bank Sta=5004.9,5009.1
Exp/Cntr=0.3,0.1

Type RM Length L Ch R = 1,3725,392,392,392
BEGIN DESCRIPTION:
MILL TRIBUTARY 1 7.0
END DESCRIPTION:
XS GIS Cut Line= 3
      2342423.07     13755282.73      2342131.88     13755714.97
      2341863.43     13756283.73
#Sta/Elev= 30
  4470.9  441.94  4544.0  438.23  4550.0  439.99  4571.0  438.97  4594.2  434.65
  4723.9  434.64  4738.9  435.84  4751.0  439.58  4765.9  440.26  4795.9  434.35
  4832.0  431.86  4842.9  431.56  4909.8  430.15  4931.8  426.25  4948.4  426.34
  4960.8  426.32  4968.0  428.57  4975.8  424.16  4987.0  422.70  4987.2  422.20
  4991.2  422.70  4997.1  423.35  5003.2  427.99  5014.2  430.43  5059.1  431.28
  5202.0  435.10  5246.4  434.24  5290.7  438.42  5491.9  445.26  5621.0  453.68
#Mann=7,-1,0
  4470.9    0.07       0  4832.0   0.035       0  4842.9     0.1       0
  4948.4    0.07       0  4987.0    0.05       0  4991.2    0.07       0
  5059.1   0.035       0
Bank Sta=4987,4991.2
Exp/Cntr=0.3,0.1

Type RM Length L Ch R = 1,3333,451,451,451
BEGIN DESCRIPTION:
MILL TRIBUTARY 1 6.0
END DESCRIPTION:
XS GIS Cut Line= 3
      2342086.37     13755141.67      2341822.47     13755492.01
      2341563.12     13756069.87
#Sta/Elev= 30
  4583.7  453.50  4632.0  451.29  4661.1  448.67  4914.7  433.47  4958.6  429.41
  4964.8  431.17  4973.1  427.41  4979.4  428.42  4987.7  420.84  4994.0  422.39
  4997.9  419.39  4998.9  418.62  4999.2  418.12  5003.2  418.62  5008.5  423.86
  5014.8  421.97  5019.2  424.10  5081.5  425.92  5107.3  428.36  5135.2  430.46
  5157.1  428.51  5213.8  428.48  5310.6  429.25  5370.6  431.74  5409.2  436.00
  5440.1  433.04  5475.0  434.60  5507.9  433.28  5573.6  446.94  5655.7  452.29
#Mann=10,-1,0
  4583.7    0.12       0  4632.0    0.07       0  4661.1    0.12       0
  4914.7     0.1       0  4997.9    0.12       0  4998.9    0.05       0
  5003.2    0.12       0  5019.2     0.1       0  5107.3    0.07       0
  5213.8   0.035       0
Bank Sta=4998.9,5003.2
Exp/Cntr=0.3,0.1

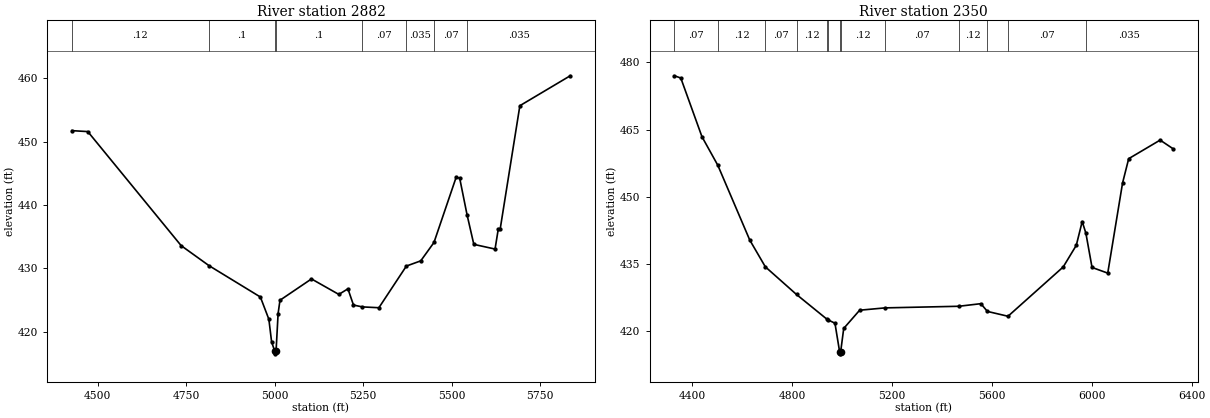
Type RM Length L Ch R = 1,2882,532,532,532
BEGIN DESCRIPTION:
B19463
END DESCRIPTION:
XS GIS Cut Line= 4
      2342013.60     13755064.29      2341563.11     13755237.20
      2341467.56     13755519.31      2341485.76     13756147.26
#Sta/Elev= 30
  4426.8  451.72  4472.1  451.57  4735.9  433.59  4814.5  430.44  4959.8  425.49
  4983.8  421.98  4991.5  418.42  4999.9  417.03  5000.2  416.53  5004.2  417.03
  5009.9  422.89  5015.2  424.98  5104.2  428.34  5181.5  425.90  5207.2  426.78
  5222.9  424.22  5248.1  423.93  5294.7  423.80  5372.4  430.37  5413.0  431.19
  5450.4  434.09  5513.0  444.36  5523.0  444.24  5543.8  438.47  5563.0  433.79
  5623.0  433.05  5632.3  436.27  5637.3  436.14  5693.1  455.65  5835.4  460.37
#Mann=8,-1,0
  4426.8    0.12       0  4814.5     0.1       0  4999.9    0.05       0
  5004.2     0.1       0  5248.1    0.07       0  5372.4   0.035       0
  5450.4    0.07       0  5543.8   0.035       0
Bank Sta=4999.9,5004.2
Exp/Cntr=0.3,0.1

Type RM Length L Ch R = 1,2350,0,0,0
BEGIN DESCRIPTION:
B19462
END DESCRIPTION:
XS GIS Cut Line= 4
      2341740.60     13754395.39      2341249.15     13754986.95
      2341244.60     13755564.82      2341440.27     13756183.67
#Sta/Elev= 30
  4328.5  477.02  4354.0  476.52  4438.7  463.42  4502.3  457.03  4630.1  440.35
  4692.5  434.37  4817.4  428.19  4939.3  422.67  4942.4  422.55  4971.3  421.78
  4989.9  415.44  4990.2  414.94  4994.3  415.44  5006.4  420.61  5070.2  424.68
  5172.2  425.20  5467.4  425.56  5555.6  426.14  5581.8  424.41  5664.3  423.33
  5885.4  434.34  5937.8  439.17  5961.4  444.48  5976.2  441.87  6000.8  434.23
  6063.7  432.96  6123.0  453.07  6147.6  458.51  6273.5  462.66  6324.5  460.76
#Mann=13,-1,0
  4328.5    0.07       0  4502.3    0.12       0  4692.5    0.07       0
  4817.4    0.12       0  4939.3     0.1       0  4942.4    0.12       0
  4989.9    0.05       0  4994.3    0.12       0  5172.2    0.07       0
  5467.4    0.12       0  5581.8     0.1       0  5664.3    0.07       0
  5976.2   0.035       0
Bank Sta=4989.9,4994.3
Exp/Cntr=0.3,0.1

Chan Stop Cuts=-1