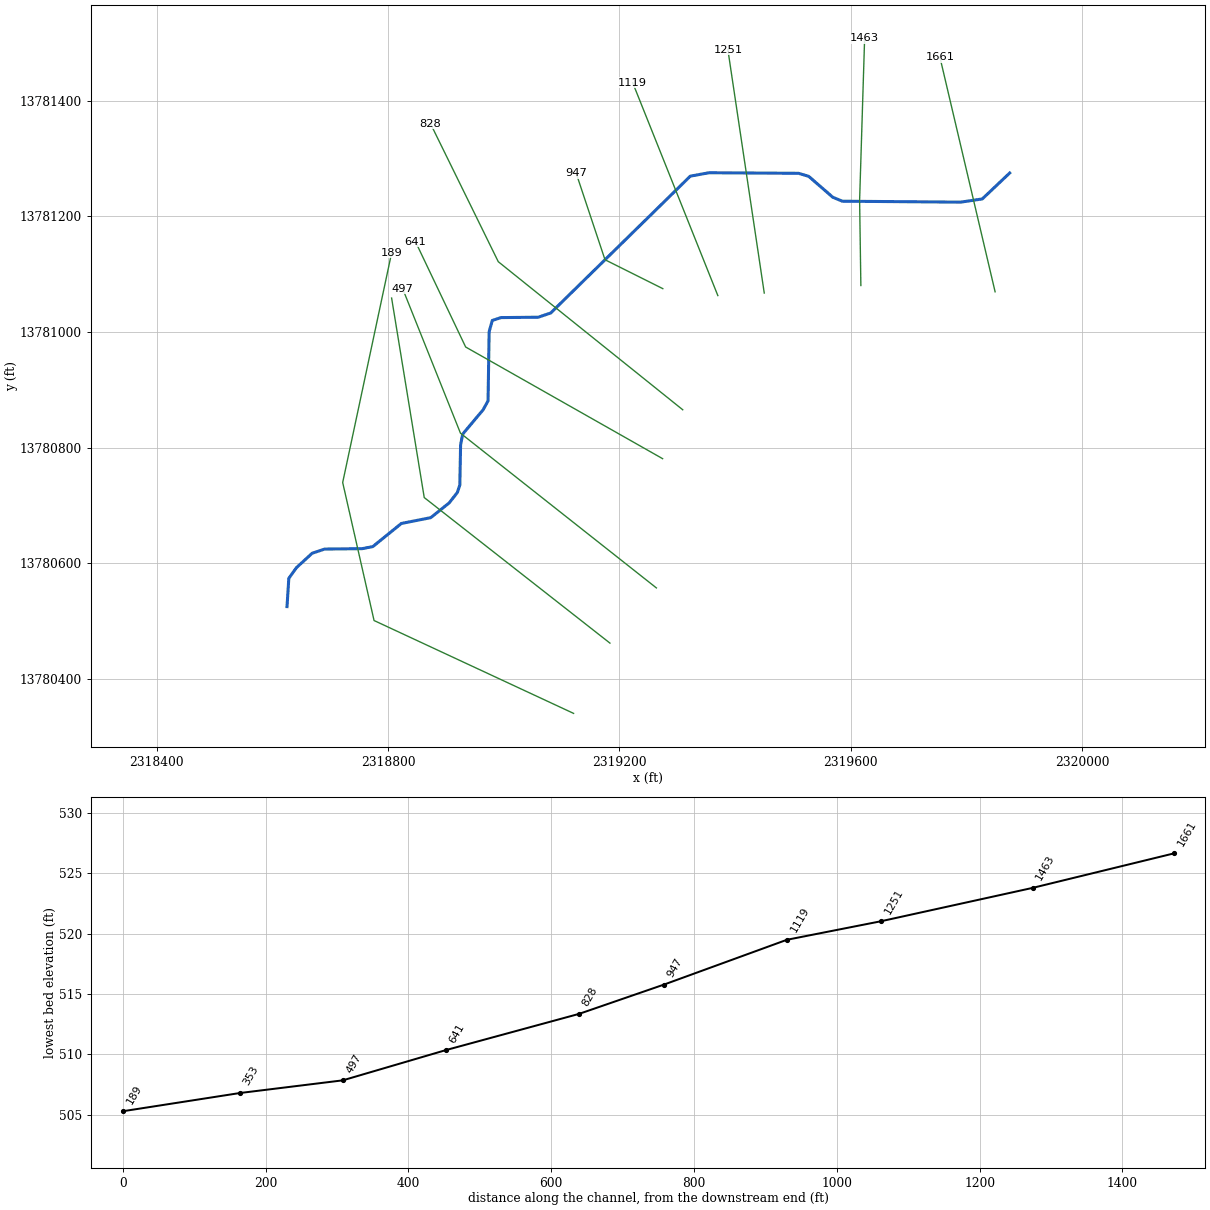
--- MILL TRIBUTARY 10.prj (project) ---

Proj Title=MILL TRIBUTARY 10 Base Level Engineering
Current Plan=p01
Default Exp/Contr=0.3,0.1
English Units
Geom File=g01
Flow File=f01
Plan File=p01
BEGIN DESCRIPTION:
MILL TRIBUTARY 10
END DESCRIPTION:

--- MILL TRIBUTARY 10.p01 (plan) ---

Plan Title=Multiple Run
Short Identifier=Multiple
Geom File=g01
Flow File=f01
Subcritical Flow
K Sum by GR= 0
Std Step Tol= 0.01
Critical Tol= 0.01
Num of Std Step Trials= 20
Max Error Tol= 0.3
Flow Tol Ratio= 0.001
Split Flow NTrial= 30
Split Flow Tol= 0.02
Split Flow Ratio= 0.02
Log Output Level= 0
Friction Slope Method= 1
Unsteady Friction Slope Method= 2
Unsteady Bridges Friction Slope Method= 1
Parabolic Critical Depth
Global Vel Dist=  1 , 1 , 1
Global Log Level= 0
CheckData=True
Encroach Param= -1, 0, 0, 0
BEGIN DESCRIPTION:
Multiple Run
END DESCRIPTION:

--- MILL TRIBUTARY 10.f01 (steady flow) ---

Flow Title=Multiple
Number of Profiles=7
Profile Names=10-year,25-year,50-year,1pct_min,100-year,1pct_plu,500-year
River Rch & RM= MILL TRIBUTARY 1,Reach-1,1661
     229     347     447     280     560    1116     864
Boundary for River Rch & Prof#=MILL TRIBUTARY 1,Reach-1,1
Up Type=0
Dn Type=3
Dn Slope=0.005
Boundary for River Rch & Prof#=MILL TRIBUTARY 1,Reach-1,2
Up Type=0
Dn Type=3
Dn Slope=0.005
Boundary for River Rch & Prof#=MILL TRIBUTARY 1,Reach-1,3
Up Type=0
Dn Type=3
Dn Slope=0.005
Boundary for River Rch & Prof#=MILL TRIBUTARY 1,Reach-1,4
Up Type=0
Dn Type=3
Dn Slope=0.005
Boundary for River Rch & Prof#=MILL TRIBUTARY 1,Reach-1,5
Up Type=0
Dn Type=3
Dn Slope=0.005
Boundary for River Rch & Prof#=MILL TRIBUTARY 1,Reach-1,6
Up Type=0
Dn Type=3
Dn Slope=0.005
Boundary for River Rch & Prof#=MILL TRIBUTARY 1,Reach-1,7
Up Type=0
Dn Type=3
Dn Slope=0.005

--- MILL TRIBUTARY 10.g01 (geometry) ---

Geom Title=Existing Conditions

River Reach=MILL TRIBUTARY 1,Reach-1
Reach XY= 30
      2319875.00     13781275.00      2319827.59     13781230.14
      2319790.17     13781224.59      2319585.50     13781226.22
      2319568.94     13781233.14      2319527.33     13781269.25
      2319509.78     13781274.48      2319354.82     13781275.44
      2319322.55     13781269.54      2319081.12     13781032.88
      2319059.64     13781025.59      2318995.02     13781024.88
      2318980.04     13781019.92      2318974.62     13781000.38
      2318972.73     13780880.95      2318964.15     13780865.36
      2318928.86     13780823.40      2318925.25     13780804.89
      2318923.90     13780735.33      2318919.58     13780722.32
      2318905.54     13780704.46      2318873.61     13780678.84
      2318822.85     13780668.85      2318773.41     13780628.82
      2318754.90     13780625.23      2318690.11     13780624.54
      2318668.55     13780617.36      2318641.31     13780592.34
      2318628.12     13780574.01      2318625.00     13780525.00

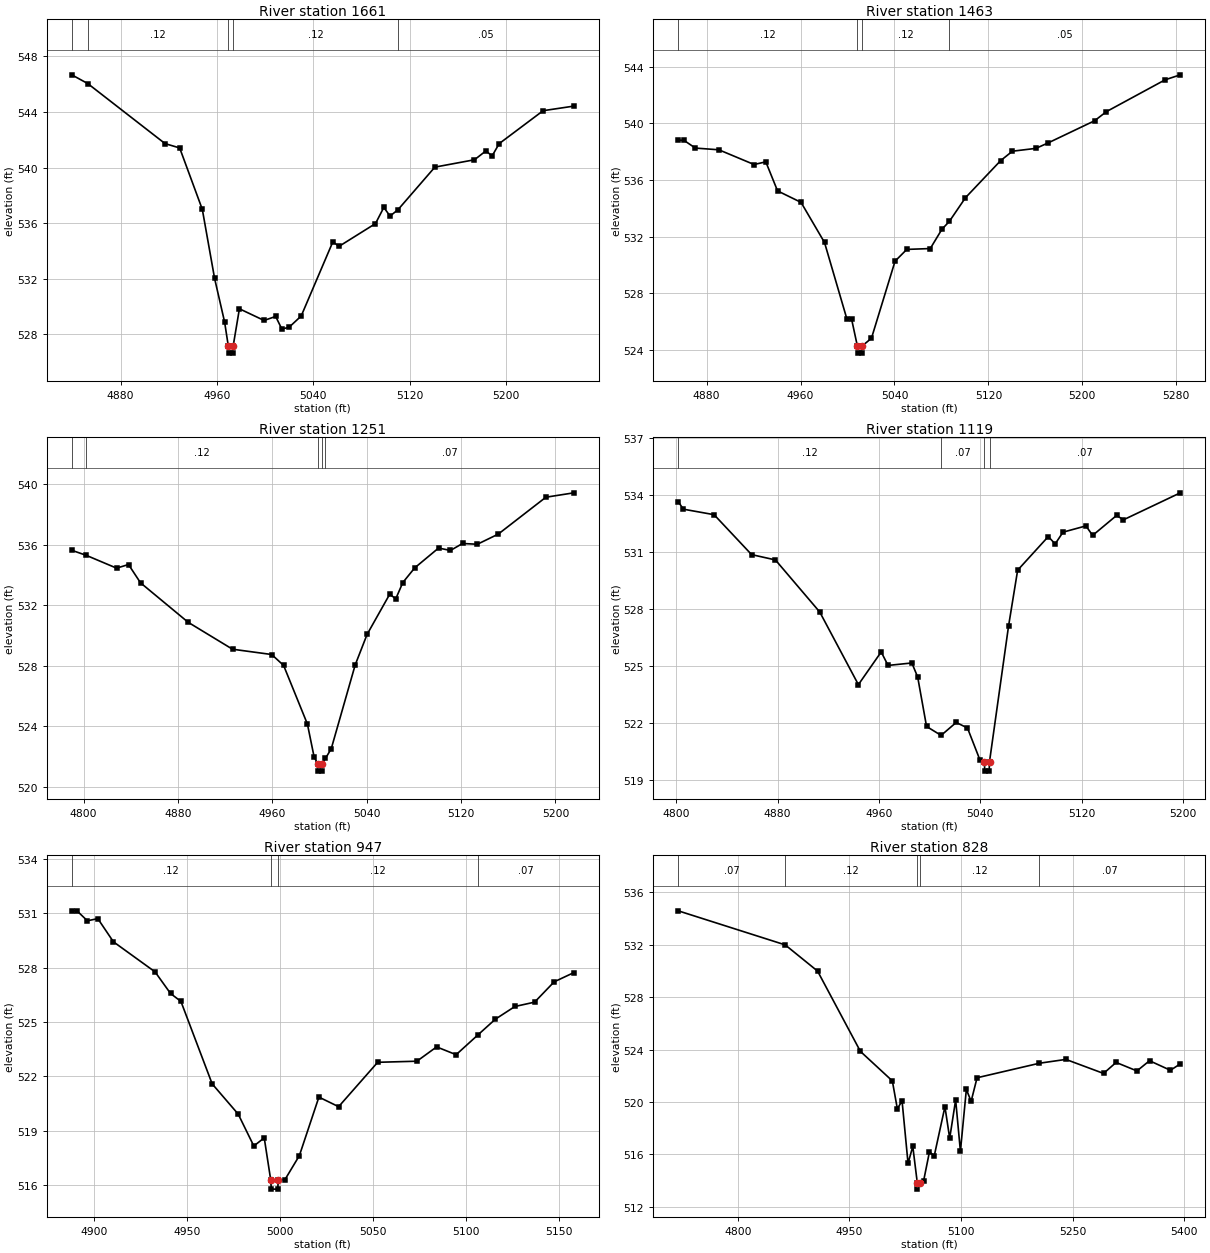
Type RM Length L Ch R = 1,1661,198,198,198
BEGIN DESCRIPTION:
B19472
END DESCRIPTION:
XS GIS Cut Line= 2
      2319849.77     13781069.53      2319754.29     13781475.34
#Sta/Elev= 30
  4839.5  546.67  4852.8  546.04  4917.0  541.72  4929.1  541.41  4947.9  536.99
  4958.1  532.02  4966.4  528.89  4969.5  527.15  4969.8  526.65  4973.3  526.65
  4973.5  527.15  4978.7  529.84  4999.2  529.00  5008.8  529.29  5013.9  528.39
  5019.8  528.50  5030.0  529.32  5056.3  534.66  5061.4  534.33  5091.7  535.97
  5098.6  537.13  5103.8  536.51  5110.4  536.97  5141.0  540.03  5173.9  540.56
  5183.4  541.20  5188.5  540.83  5194.4  541.72  5230.9  544.09  5256.4  544.42
#Mann=5,-1,0
  4839.5   0.035       0  4852.8    0.12       0  4969.5    0.05       0
  4973.5    0.12       0  5110.4    0.05       0
Bank Sta=4969.5,4973.5
Exp/Cntr=0.3,0.1

Type RM Length L Ch R = 1,1463,212,212,212
BEGIN DESCRIPTION:
MILL TRIBUTARY 10 3.0
END DESCRIPTION:
XS GIS Cut Line= 3
      2319617.57     13781080.38      2319615.40     13781227.94
      2319624.08     13781507.93
#Sta/Elev= 30
  4855.8  538.81  4860.6  538.81  4870.4  538.26  4890.4  538.14  4920.4  537.10
  4930.4  537.29  4940.4  535.24  4960.4  534.43  4980.4  531.60  4999.4  526.22
  5003.4  526.22  5008.4  524.29  5008.7  523.79  5012.2  523.79  5012.4  524.29
  5020.4  524.84  5040.5  530.28  5050.5  531.11  5070.5  531.17  5080.5  532.54
  5086.7  533.08  5100.5  534.76  5130.5  537.38  5140.5  538.04  5160.5  538.24
  5170.5  538.61  5210.5  540.19  5220.5  540.83  5270.6  543.08  5283.5  543.43
#Mann=4,-1,0
  4855.8    0.12       0  5008.4    0.05       0  5012.4    0.12       0
  5086.7    0.05       0
Bank Sta=5008.4,5012.4
Exp/Cntr=0.3,0.1

Type RM Length L Ch R = 1,1251,132,132,132
BEGIN DESCRIPTION:
B19471
END DESCRIPTION:
XS GIS Cut Line= 2
      2319450.47     13781067.38      2319387.53     13781488.40
#Sta/Elev= 30
  4789.9  535.63  4802.1  535.30  4827.9  534.45  4838.0  534.69  4848.2  533.48
  4888.6  530.87  4926.2  529.09  4959.4  528.74  4969.5  528.02  4989.7  524.14
  4995.4  521.96  4998.4  521.53  4998.7  521.03  5002.2  521.03  5002.4  521.53
  5005.0  521.87  5009.9  522.51  5030.2  528.05  5040.3  530.07  5059.5  532.73
  5064.6  532.42  5070.6  533.50  5080.7  534.47  5100.9  535.78  5111.0  535.62
  5121.2  536.08  5133.8  536.03  5151.5  536.70  5191.9  539.14  5215.6  539.43
#Mann=5,-1,0
  4789.9    0.07       0  4802.1    0.12       0  4998.4    0.05       0
  5002.4    0.12       0  5005.0    0.07       0
Bank Sta=4998.4,5002.4
Exp/Cntr=0.3,0.1

Type RM Length L Ch R = 1,1119,172,172,172
BEGIN DESCRIPTION:
B19470
END DESCRIPTION:
XS GIS Cut Line= 2
      2319370.19     13781062.98      2319223.00     13781430.94
#Sta/Elev= 30
  4801.6  533.67  4805.6  533.27  4829.9  532.98  4859.5  530.88  4878.3  530.60
  4913.3  527.86  4943.8  524.04  4961.8  525.76  4967.2  525.05  4986.0  525.18
  4990.6  524.44  4997.6  521.84  5009.1  521.37  5021.0  522.05  5029.9  521.76
  5039.9  520.05  5043.3  519.99  5043.5  519.49  5047.0  519.49  5047.3  519.99
  5062.3  527.11  5069.5  530.06  5093.7  531.83  5099.1  531.44  5105.3  532.06
  5123.4  532.39  5128.7  531.89  5147.6  532.94  5153.0  532.71  5197.9  534.13
#Mann=4,-1,0
  4801.6    0.12       0  5009.1    0.07       0  5043.3    0.05       0
  5047.3    0.07       0
Bank Sta=5043.3,5047.3
Exp/Cntr=0.3,0.1

Type RM Length L Ch R = 1,947,119,119,119
BEGIN DESCRIPTION:
MILL TRIBUTARY 10 2.0
END DESCRIPTION:
XS GIS Cut Line= 3
      2319275.04     13781074.98      2319175.00     13781125.00
      2319124.99     13781275.04
#Sta/Elev= 30
  4888.2  531.14  4891.0  531.14  4896.6  530.59  4902.2  530.71  4910.6  529.43
  4933.0  527.77  4941.3  526.58  4946.9  526.14  4963.7  521.59  4977.7  519.92
  4986.1  518.16  4991.7  518.61  4995.2  516.28  4995.5  515.78  4999.0  515.78
  4999.2  516.28  5002.7  516.28  5010.6  517.63  5021.1  520.86  5031.7  520.33
  5052.7  522.78  5073.8  522.84  5084.4  523.63  5094.9  523.20  5106.6  524.29
  5116.0  525.16  5126.5  525.86  5137.1  526.10  5147.6  527.22  5158.2  527.73
#Mann=4,-1,0
  4888.2    0.12       0  4995.2    0.05       0  4999.2    0.12       0
  5106.6    0.07       0
Bank Sta=4995.2,4999.2
Exp/Cntr=0.3,0.1

Type RM Length L Ch R = 1,828,187,187,187
BEGIN DESCRIPTION:
B19469
END DESCRIPTION:
XS GIS Cut Line= 3
      2319309.45     13780865.50      2318990.40     13781121.61
      2318873.28     13781360.19
#Sta/Elev= 30
  4719.9  534.59  4863.7  531.99  4907.2  529.99  4964.8  523.86  5007.7  521.61
  5014.4  519.49  5020.8  520.07  5028.8  515.32  5035.2  516.61  5041.2  513.85
  5041.4  513.35  5045.2  513.85  5049.6  513.94  5057.6  516.20  5064.0  515.88
  5078.4  519.64  5084.8  517.23  5092.8  520.16  5099.2  516.24  5107.2  520.96
  5113.6  520.05  5121.6  521.85  5205.5  522.96  5241.0  523.25  5291.6  522.18
  5308.5  523.02  5336.5  522.37  5353.4  523.15  5381.5  522.42  5394.8  522.91
#Mann=5,-1,0
  4719.9    0.07       0  4863.7    0.12       0  5041.2    0.05       0
  5045.2    0.12       0  5205.5    0.07       0
Bank Sta=5041.2,5045.2
Exp/Cntr=0.3,0.1

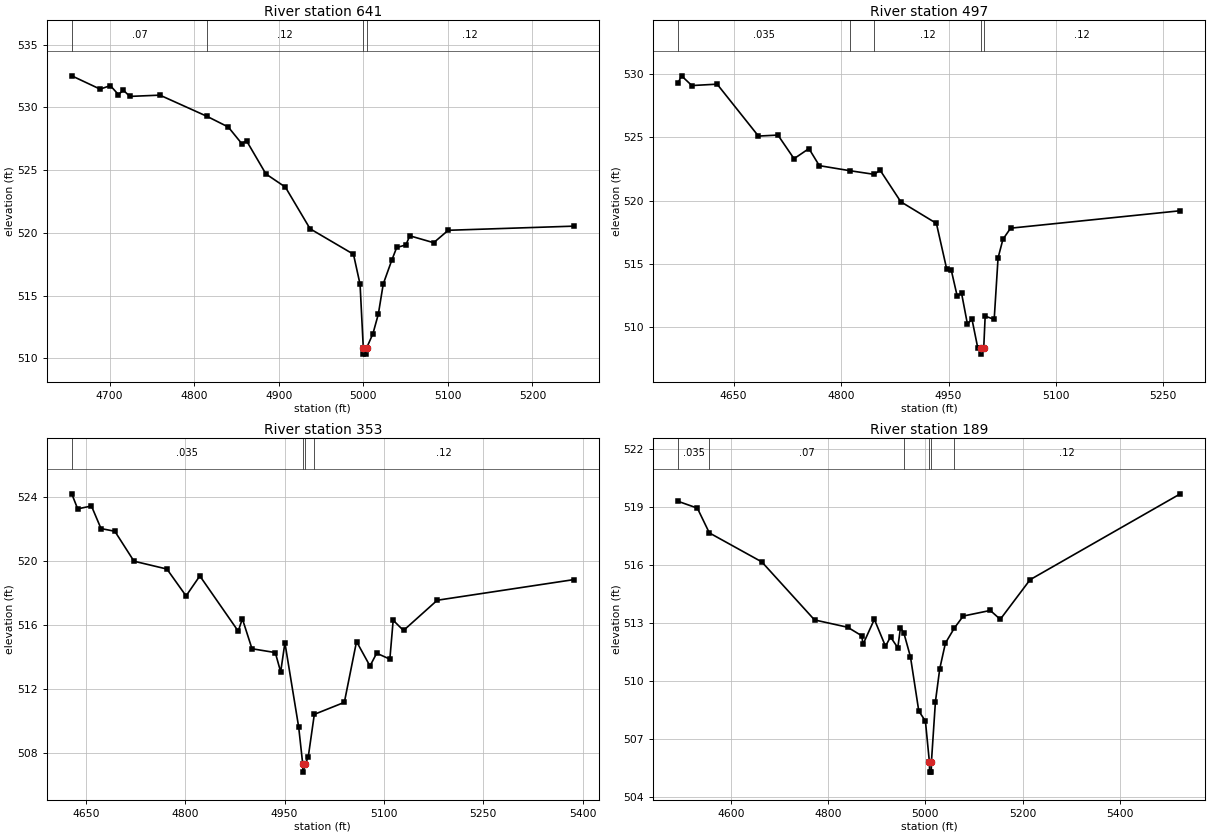
Type RM Length L Ch R = 1,641,144,144,144
BEGIN DESCRIPTION:
B19468
END DESCRIPTION:
XS GIS Cut Line= 3
      2319274.67     13780780.90      2318933.98     13780974.04
      2318847.19     13781156.30
#Sta/Elev= 30
  4655.4  532.52  4688.9  531.46  4701.0  531.74  4710.6  531.02  4716.3  531.38
  4724.0  530.88  4759.6  530.98  4815.6  529.28  4840.4  528.44  4856.3  527.12
  4862.0  527.34  4884.9  524.70  4907.9  523.65  4937.1  520.33  4988.4  518.30
  4996.2  515.90  5000.0  510.84  5000.2  510.34  5003.7  510.34  5004.0  510.84
  5011.4  511.97  5017.8  513.53  5023.6  515.93  5033.7  517.83  5039.5  518.84
  5050.3  519.04  5055.0  519.77  5083.2  519.22  5100.4  520.21  5248.9  520.54
#Mann=4,-1,0
  4655.4    0.07       0  4815.6    0.12       0  5000.0    0.05       0
  5004.0    0.12       0
Bank Sta=5000,5004
Exp/Cntr=0.3,0.1

Type RM Length L Ch R = 1,497,144,144,144
BEGIN DESCRIPTION:
MILL TRIBUTARY 10 1.0
END DESCRIPTION:
XS GIS Cut Line= 3
      2319263.87     13780557.35      2318925.00     13780825.00
      2318824.99     13781075.02
#Sta/Elev= 30
  4572.6  529.33  4577.2  529.87  4591.6  529.10  4626.9  529.21  4684.6  525.10
  4711.8  525.18  4734.3  523.31  4755.1  524.11  4769.6  522.76  4812.2  522.36
  4846.3  522.07  4854.5  522.40  4883.4  519.90  4933.1  518.19  4947.5  514.57
  4953.9  514.48  4962.0  512.47  4968.3  512.64  4976.4  510.23  4982.8  510.60
  4990.8  508.35  4995.2  508.34  4995.5  507.84  4999.2  508.34  5001.2  510.85
  5013.8  510.59  5019.2  515.45  5026.0  516.93  5036.7  517.81  5273.7  519.19
#Mann=5,-1,0
  4572.6   0.035       0  4812.2    0.07       0  4846.3    0.12       0
  4995.2    0.05       0  4999.2    0.12       0
Bank Sta=4995.2,4999.2
Exp/Cntr=0.3,0.1

Type RM Length L Ch R = 1,353,164,164,164
BEGIN DESCRIPTION:
B19467
END DESCRIPTION:
XS GIS Cut Line= 3
      2319183.58     13780461.86      2318862.36     13780713.62
      2318805.93     13781058.71
#Sta/Elev= 30
  4628.8  524.18  4637.7  523.24  4658.5  523.42  4672.9  522.01  4693.8  521.84
  4722.7  519.97  4772.4  519.48  4801.3  517.80  4822.1  519.05  4880.0  515.60
  4886.3  516.37  4900.8  514.50  4936.0  514.26  4944.1  513.05  4950.5  514.87
  4971.3  509.60  4977.4  507.29  4977.7  506.79  4981.4  507.29  4985.8  507.76
  4994.9  510.40  5040.2  511.15  5058.6  514.95  5078.9  513.42  5089.0  514.22
  5108.9  513.85  5113.9  516.28  5129.5  515.64  5180.4  517.53  5386.6  518.82
#Mann=4,-1,0
  4628.8   0.035       0  4977.4    0.05       0  4981.4   0.035       0
  4994.9    0.12       0
Bank Sta=4977.4,4981.4
Exp/Cntr=0.3,0.1

Type RM Length L Ch R = 1,189,0,0,0
BEGIN DESCRIPTION:
B19466
END DESCRIPTION:
XS GIS Cut Line= 4
      2319120.64     13780340.34      2318775.56     13780500.95
      2318721.30     13780739.66      2318805.94     13781136.81
#Sta/Elev= 30
  4492.2  519.28  4531.5  518.93  4556.1  517.65  4663.9  516.15  4772.2  513.15
  4840.4  512.77  4869.3  512.33  4871.7  511.88  4895.1  513.18  4918.0  511.79
  4928.3  512.27  4943.3  511.71  4948.8  512.75  4955.8  512.47  4969.3  511.24
  4986.4  508.44  5000.0  507.92  5008.3  505.78  5008.6  505.28  5012.1  505.28
  5012.3  505.78  5020.6  508.93  5029.5  510.63  5041.1  511.95  5059.5  512.73
  5077.7  513.35  5133.3  513.64  5153.8  513.18  5215.1  515.23  5523.7  519.67
#Mann=6,-1,0
  4492.2   0.035       0  4556.1    0.07       0  4955.8   0.035       0
  5008.3   0.035       0  5012.3   0.035       0  5059.5    0.12       0
Bank Sta=5008.3,5012.3
Exp/Cntr=0.3,0.1

Chan Stop Cuts=-1