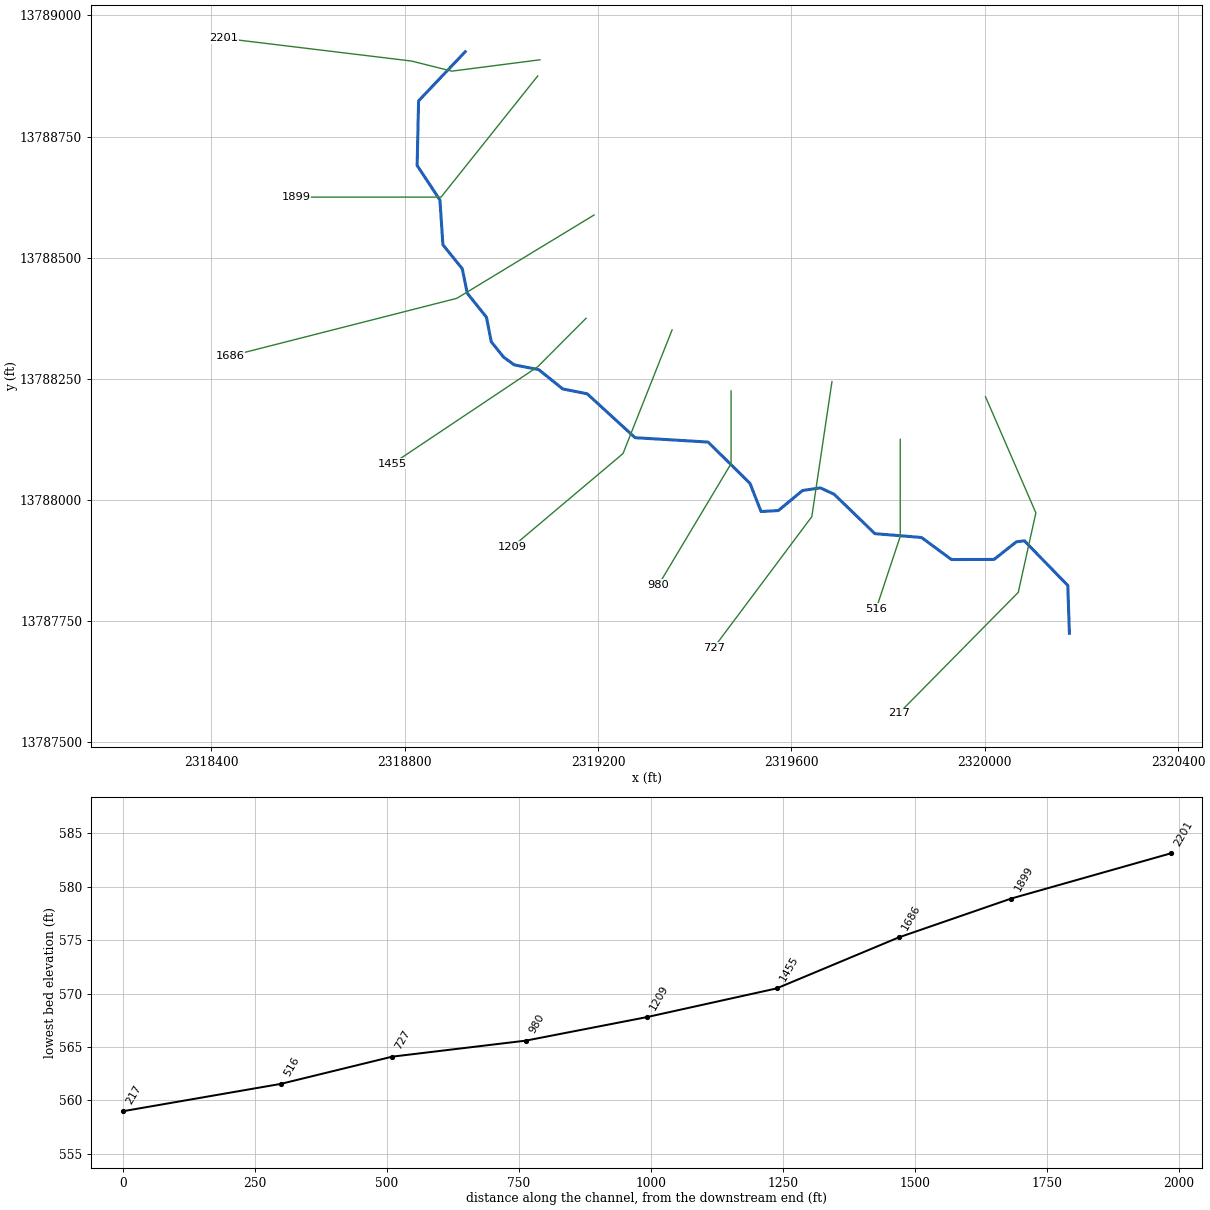
--- MILL TRIBUTARY 14.prj (project) ---

Proj Title=MILL TRIBUTARY 14 Base Level Engineering
Current Plan=p01
Default Exp/Contr=0.3,0.1
English Units
Geom File=g01
Flow File=f01
Plan File=p01
BEGIN DESCRIPTION:
MILL TRIBUTARY 14
END DESCRIPTION:

--- MILL TRIBUTARY 14.p01 (plan) ---

Plan Title=Multiple Run
Short Identifier=Multiple
Geom File=g01
Flow File=f01
Subcritical Flow
K Sum by GR= 0
Std Step Tol= 0.01
Critical Tol= 0.01
Num of Std Step Trials= 20
Max Error Tol= 0.3
Flow Tol Ratio= 0.001
Split Flow NTrial= 30
Split Flow Tol= 0.02
Split Flow Ratio= 0.02
Log Output Level= 0
Friction Slope Method= 1
Unsteady Friction Slope Method= 2
Unsteady Bridges Friction Slope Method= 1
Parabolic Critical Depth
Global Vel Dist=  1 , 1 , 1
Global Log Level= 0
CheckData=True
Encroach Param= -1, 0, 0, 0
BEGIN DESCRIPTION:
Multiple Run
END DESCRIPTION:

--- MILL TRIBUTARY 14.f01 (steady flow) ---

Flow Title=Multiple
Number of Profiles=7
Profile Names=10-year,25-year,50-year,1pct_min,100-year,1pct_plu,500-year
River Rch & RM= MILL TRIBUTARY 1,Reach-1,2201
     287     444     581     370     738    1473    1178
Boundary for River Rch & Prof#=MILL TRIBUTARY 1,Reach-1,1
Up Type=0
Dn Type=3
Dn Slope=0.005
Boundary for River Rch & Prof#=MILL TRIBUTARY 1,Reach-1,2
Up Type=0
Dn Type=3
Dn Slope=0.005
Boundary for River Rch & Prof#=MILL TRIBUTARY 1,Reach-1,3
Up Type=0
Dn Type=3
Dn Slope=0.005
Boundary for River Rch & Prof#=MILL TRIBUTARY 1,Reach-1,4
Up Type=0
Dn Type=3
Dn Slope=0.005
Boundary for River Rch & Prof#=MILL TRIBUTARY 1,Reach-1,5
Up Type=0
Dn Type=3
Dn Slope=0.005
Boundary for River Rch & Prof#=MILL TRIBUTARY 1,Reach-1,6
Up Type=0
Dn Type=3
Dn Slope=0.005
Boundary for River Rch & Prof#=MILL TRIBUTARY 1,Reach-1,7
Up Type=0
Dn Type=3
Dn Slope=0.005

--- MILL TRIBUTARY 14.g01 (geometry) ---

Geom Title=Existing Conditions

River Reach=MILL TRIBUTARY 1,Reach-1
Reach XY= 30
      2318925.00     13788925.00      2318828.48     13788823.55
      2318825.50     13788690.22      2318872.64     13788619.02
      2318878.83     13788526.58      2318918.88     13788477.18
      2318929.16     13788426.72      2318968.89     13788377.16
      2318978.86     13788326.42      2319004.52     13788294.62
      2319026.42     13788278.86      2319077.16     13788268.89
      2319126.73     13788229.19      2319177.29     13788219.15
      2319276.47     13788128.55      2319427.46     13788119.54
      2319514.12     13788034.36      2319537.01     13787976.18
      2319572.90     13787978.22      2319622.78     13788019.59
      2319659.65     13788025.03      2319688.20     13788011.85
      2319772.58     13787930.54      2319869.02     13787922.64
      2319930.98     13787877.17      2320019.11     13787877.37
      2320065.16     13787913.67      2320081.76     13787915.88
      2320171.62     13787823.63      2320175.00     13787725.00

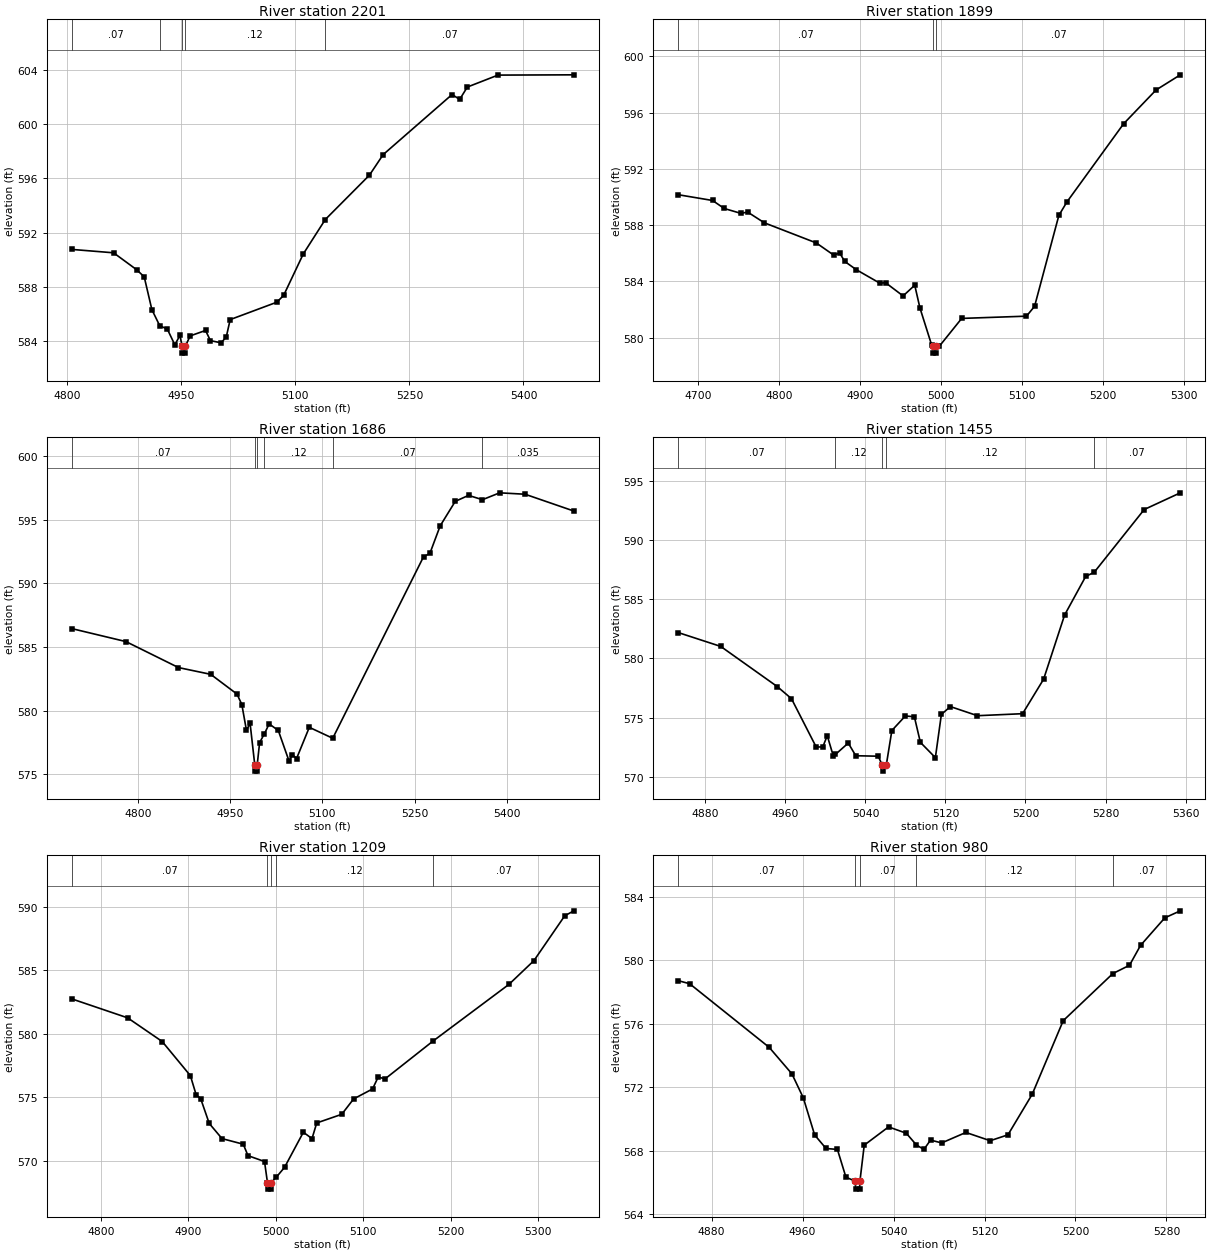
Type RM Length L Ch R = 1,2201,302,302,302
BEGIN DESCRIPTION:
B19474
END DESCRIPTION:
XS GIS Cut Line= 4
      2319079.54     13788908.33      2318897.26     13788884.90
      2318813.93     13788905.73      2318425.92     13788952.60
#Sta/Elev= 30
  4805.8  590.76  4860.8  590.51  4891.0  589.27  4901.1  588.74  4911.2  586.32
  4921.6  585.13  4931.4  584.90  4941.4  583.73  4948.0  584.42  4951.1  583.62
  4951.3  583.12  4954.8  583.12  4955.1  583.62  4961.6  584.39  4981.8  584.79
  4988.2  584.04  5002.2  583.88  5009.0  584.30  5014.2  585.59  5075.5  586.87
  5084.5  587.37  5110.4  590.43  5139.3  592.96  5197.4  596.23  5215.4  597.74
  5306.1  602.17  5316.1  601.81  5326.2  602.72  5366.5  603.60  5466.3  603.62
#Mann=5,-1,0
  4805.8    0.07       0  4921.6    0.12       0  4951.1    0.05       0
  4955.1    0.12       0  5139.3    0.07       0
Bank Sta=4951.1,4955.1
Exp/Cntr=0.3,0.1

Type RM Length L Ch R = 1,1899,213,213,213
BEGIN DESCRIPTION:
MILL TRIBUTARY 14 4.0
END DESCRIPTION:
XS GIS Cut Line= 3
      2319074.99     13788874.99      2318875.00     13788625.00
      2318575.04     13788625.00
#Sta/Elev= 30
  4675.2  590.16  4717.6  589.75  4732.0  589.18  4752.8  588.83  4760.8  588.93
  4781.6  588.16  4845.7  586.73  4867.3  585.86  4874.5  586.02  4880.9  585.41
  4895.3  584.82  4924.1  583.87  4931.3  583.90  4952.9  582.96  4967.3  583.72
  4973.7  582.11  4988.1  579.48  4990.1  579.39  4990.4  578.89  4993.9  578.89
  4994.1  579.39  4997.8  579.39  5025.3  581.36  5105.3  581.52  5115.3  582.22
  5145.3  588.69  5155.3  589.65  5225.3  595.21  5265.3  597.61  5295.3  598.69
#Mann=3,-1,0
  4675.2    0.07       0  4990.1    0.05       0  4994.1    0.07       0
Bank Sta=4990.1,4994.1
Exp/Cntr=0.3,0.1

Type RM Length L Ch R = 1,1686,231,231,231
BEGIN DESCRIPTION:
B19477
END DESCRIPTION:
XS GIS Cut Line= 3
      2319191.51     13788588.01      2318907.68     13788416.15
      2318438.12     13788296.81
#Sta/Elev= 30
  4692.5  586.44  4780.6  585.42  4866.0  583.38  4918.4  582.85  4961.1  581.30
  4969.0  580.48  4976.5  578.45  4982.4  579.01  4990.0  575.75  4990.3  575.25
  4993.8  575.25  4994.0  575.75  4997.9  577.49  5005.8  578.19  5013.4  578.96
  5028.3  578.44  5045.9  576.02  5051.1  576.54  5058.0  576.24  5078.7  578.69
  5116.8  577.83  5264.4  592.08  5274.7  592.34  5291.5  594.51  5316.0  596.43
  5337.6  596.90  5360.2  596.56  5388.2  597.10  5429.5  596.99  5508.8  595.67
#Mann=6,-1,0
  4692.5    0.07       0  4990.0    0.05       0  4994.0    0.07       0
  5005.8    0.12       0  5116.8    0.07       0  5360.2   0.035       0
Bank Sta=4990,4994
Exp/Cntr=0.3,0.1

Type RM Length L Ch R = 1,1455,246,246,246
BEGIN DESCRIPTION:
MILL TRIBUTARY 14 3.0
END DESCRIPTION:
XS GIS Cut Line= 3
      2319175.02     13788375.02      2319075.00     13788275.00
      2318775.00     13788075.00
#Sta/Elev= 30
  4852.8  582.18  4895.3  581.01  4951.8  577.62  4966.0  576.60  4990.7  572.52
  4997.3  572.52  5001.8  573.47  5007.8  571.77  5010.0  571.89  5022.8  572.85
  5030.3  571.78  5052.8  571.74  5056.8  570.98  5057.1  570.48  5060.8  570.98
  5066.4  573.91  5079.9  575.14  5088.9  575.07  5094.9  572.91  5109.9  571.62
  5115.9  575.27  5124.9  575.93  5152.0  575.16  5197.1  575.33  5218.1  578.24
  5239.1  583.66  5260.2  586.92  5268.7  587.27  5318.7  592.57  5354.8  593.98
#Mann=5,-1,0
  4852.8    0.07       0  5010.0    0.12       0  5056.8    0.05       0
  5060.8    0.12       0  5268.7    0.07       0
Bank Sta=5056.8,5060.8
Exp/Cntr=0.3,0.1

Type RM Length L Ch R = 1,1209,229,229,229
BEGIN DESCRIPTION:
B19476
END DESCRIPTION:
XS GIS Cut Line= 3
      2319352.98     13788351.03      2319251.43     13788095.83
      2319022.25     13787903.11
#Sta/Elev= 30
  4766.8  582.74  4830.7  581.25  4870.2  579.39  4902.4  576.71  4909.0  575.21
  4914.3  574.88  4924.0  572.95  4938.6  571.76  4962.9  571.32  4968.3  570.42
  4987.2  569.96  4990.6  568.29  4990.8  567.79  4994.3  567.79  4994.6  568.29
  5000.7  568.73  5010.1  569.50  5031.6  572.26  5041.5  571.76  5046.9  572.99
  5075.5  573.67  5089.1  574.88  5110.7  575.66  5117.2  576.60  5125.0  576.45
  5179.6  579.41  5266.7  583.88  5295.3  585.75  5330.5  589.27  5340.9  589.66
#Mann=5,-1,0
  4766.8    0.07       0  4990.6    0.05       0  4994.6    0.07       0
  5000.7    0.12       0  5179.6    0.07       0
Bank Sta=4990.6,4994.6
Exp/Cntr=0.3,0.1

Type RM Length L Ch R = 1,980,253,253,253
BEGIN DESCRIPTION:
MILL TRIBUTARY 14 2.0
END DESCRIPTION:
XS GIS Cut Line= 3
      2319475.00     13788225.02      2319475.00     13788075.00
      2319324.99     13787824.98
#Sta/Elev= 30
  4850.6  578.72  4860.6  578.53  4930.6  574.52  4950.6  572.85  4960.6  571.34
  4970.6  569.00  4980.6  568.15  4990.6  568.09  4998.1  566.34  5006.4  566.09
  5006.6  565.59  5010.1  565.59  5010.4  566.09  5014.2  568.36  5035.6  569.51
  5051.2  569.11  5060.1  568.37  5066.7  568.09  5072.5  568.68  5082.3  568.50
  5103.6  569.16  5125.0  568.64  5140.6  569.01  5161.9  571.56  5189.2  576.20
  5232.9  579.17  5247.5  579.69  5257.2  580.94  5278.6  582.68  5292.2  583.12
#Mann=5,-1,0
  4850.6    0.07       0  5006.4    0.05       0  5010.4    0.07       0
  5060.1    0.12       0  5232.9    0.07       0
Bank Sta=5006.4,5010.4
Exp/Cntr=0.3,0.1

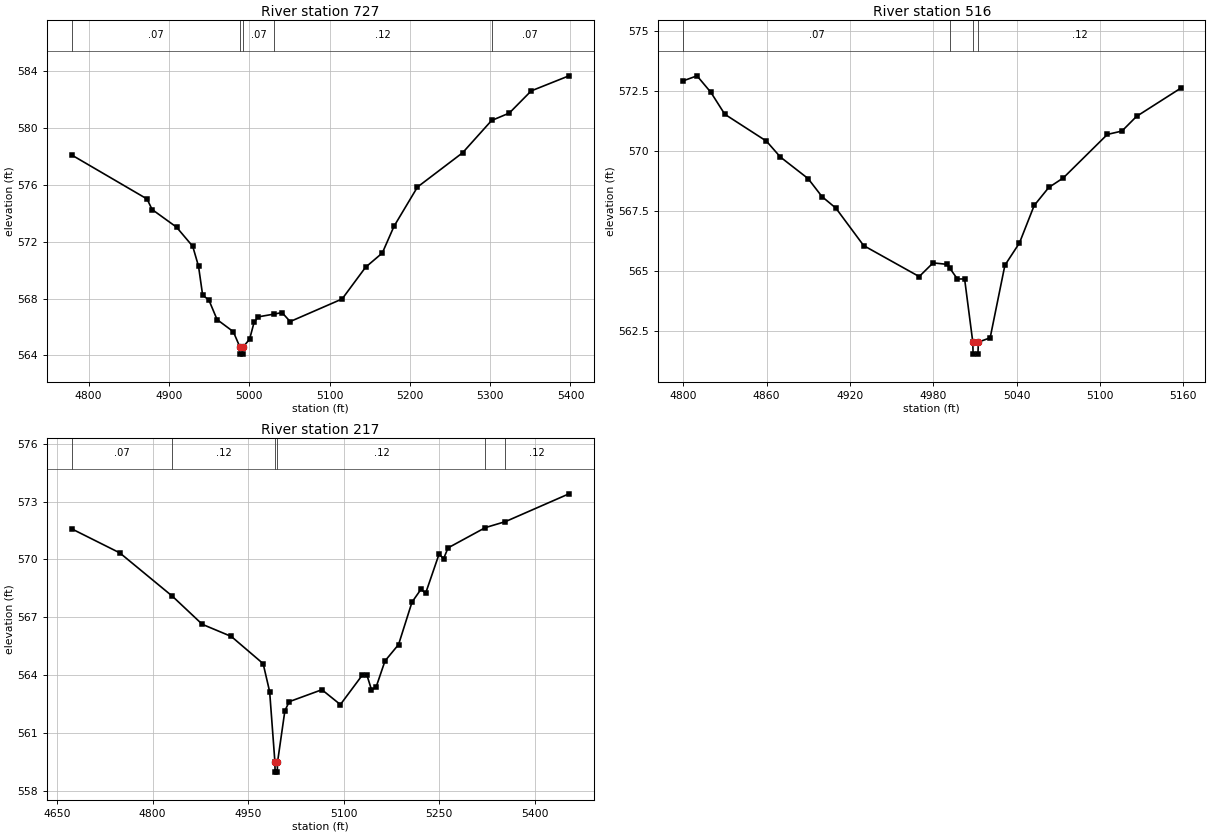
Type RM Length L Ch R = 1,727,211,211,211
BEGIN DESCRIPTION:
B19475
END DESCRIPTION:
XS GIS Cut Line= 3
      2319683.71     13788244.23      2319642.05     13787965.63
      2319439.49     13787695.55
#Sta/Elev= 30
  4778.8  578.10  4872.8  575.00  4879.1  574.26  4909.5  573.02  4929.7  571.67
  4936.9  570.27  4942.0  568.25  4949.9  567.88  4960.0  566.52  4980.2  565.67
  4988.4  564.59  4988.6  564.09  4992.1  564.09  4992.4  564.59  5000.5  565.14
  5006.1  566.33  5011.2  566.71  5031.3  566.91  5040.9  567.01  5051.0  566.38
  5115.7  567.97  5144.9  570.20  5165.7  571.20  5180.3  573.08  5209.5  575.84
  5265.7  578.25  5301.8  580.52  5323.8  581.04  5351.1  582.60  5398.1  583.66
#Mann=5,-1,0
  4778.8    0.07       0  4988.4    0.05       0  4992.4    0.07       0
  5031.3    0.12       0  5301.8    0.07       0
Bank Sta=4988.4,4992.4
Exp/Cntr=0.3,0.1

Type RM Length L Ch R = 1,516,299,299,299
BEGIN DESCRIPTION:
MILL TRIBUTARY 14 1.0
END DESCRIPTION:
XS GIS Cut Line= 3
      2319825.00     13788125.05      2319825.00     13787925.00
      2319774.99     13787774.96
#Sta/Elev= 30
  4799.9  572.92  4809.9  573.13  4819.9  572.44  4829.9  571.53  4859.9  570.41
  4869.9  569.75  4889.9  568.85  4899.9  568.10  4909.9  567.62  4929.9  566.06
  4969.9  564.77  4979.9  565.34  4989.9  565.28  4991.8  565.13  4997.4  564.67
  5002.6  564.67  5008.5  562.04  5008.7  561.54  5012.2  561.54  5012.5  562.04
  5021.0  562.22  5031.6  565.24  5042.1  566.17  5052.7  567.73  5063.2  568.48
  5073.7  568.88  5105.4  570.69  5115.9  570.83  5126.4  571.44  5158.1  572.61
#Mann=4,-1,0
  4799.9    0.07       0  4991.8    0.12       0  5008.5    0.05       0
  5012.5    0.12       0
Bank Sta=5008.5,5012.5
Exp/Cntr=0.3,0.1

Type RM Length L Ch R = 1,217,0,0,0
BEGIN DESCRIPTION:
B19473
END DESCRIPTION:
XS GIS Cut Line= 4
      2320001.41     13788213.06      2320105.59     13787973.44
      2320069.13     13787809.38      2319822.07     13787559.71
#Sta/Elev= 30
  4672.8  571.59  4748.5  570.34  4831.2  568.09  4877.9  566.64  4923.5  566.01
  4973.5  564.60  4983.7  563.15  4992.0  559.48  4992.2  558.98  4995.7  558.98
  4996.0  559.48  5007.6  562.16  5014.4  562.63  5065.7  563.25  5094.7  562.48
  5129.4  564.02  5136.4  564.00  5143.5  563.25  5150.6  563.37  5164.7  564.74
  5186.0  565.59  5207.1  567.79  5221.3  568.46  5228.4  568.24  5249.6  570.28
  5256.7  570.04  5263.7  570.60  5322.2  571.65  5353.7  571.96  5453.4  573.40
#Mann=6,-1,0
  4672.8    0.07       0  4831.2    0.12       0  4992.0    0.05       0
  4996.0    0.12       0  5322.2    0.07       0  5353.7    0.12       0
Bank Sta=4992,4996
Exp/Cntr=0.3,0.1

Chan Stop Cuts=-1