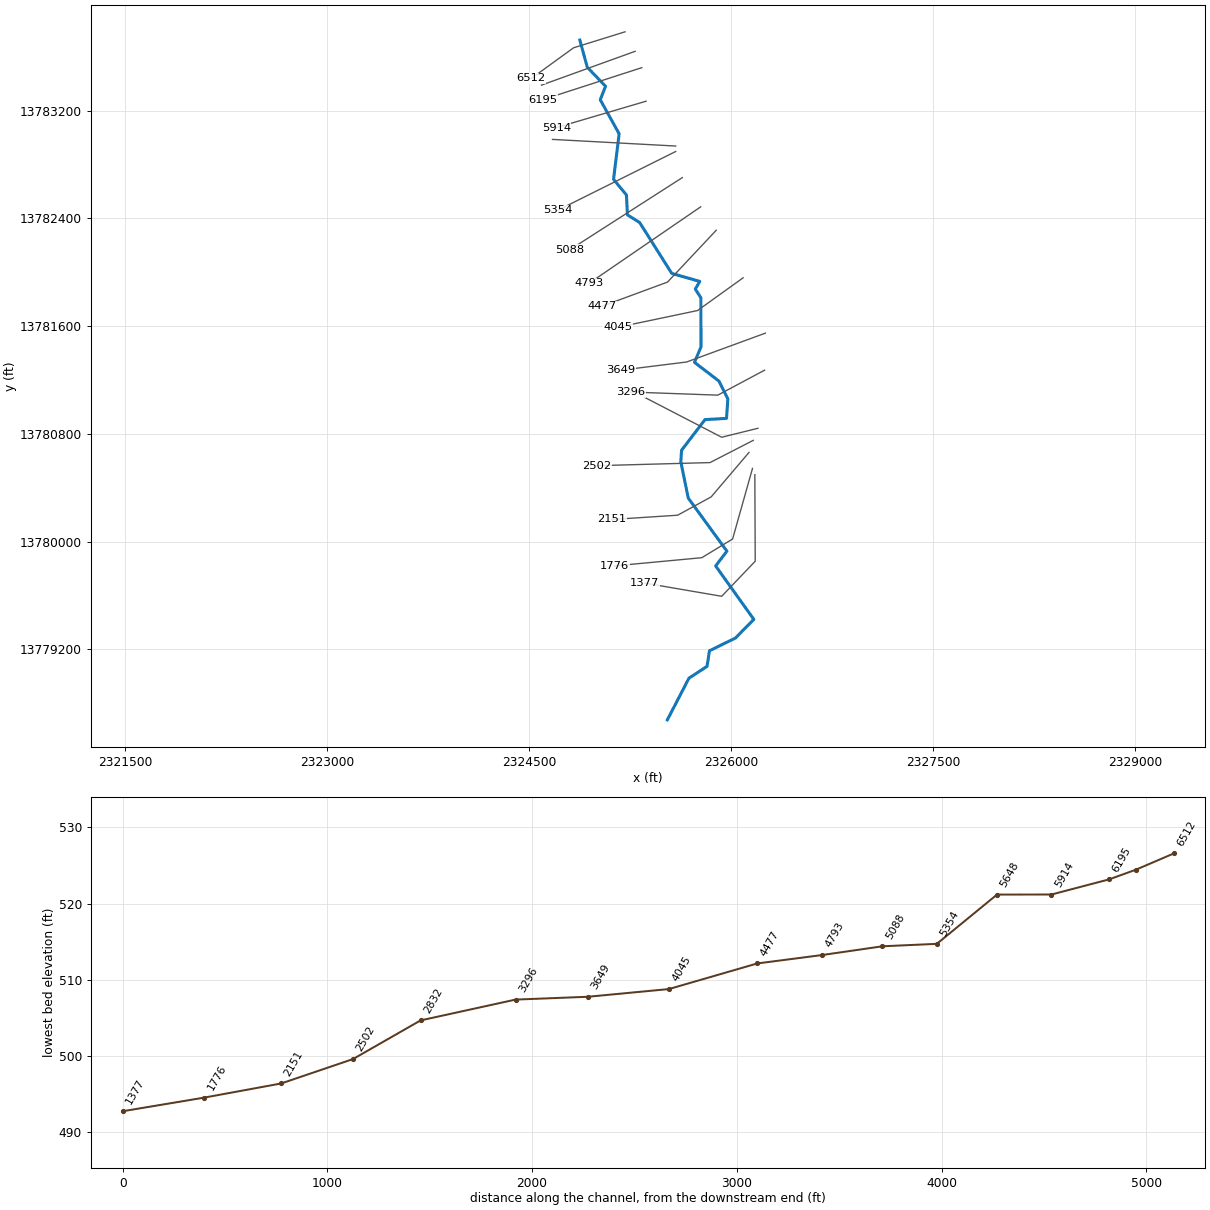
--- MILL TRIBUTARY 15.prj (project) ---

Proj Title=MILL TRIBUTARY 15 Base Level Engineering
Current Plan=p01
Default Exp/Contr=0.3,0.1
English Units
Geom File=g01
Flow File=f01
Plan File=p01
BEGIN DESCRIPTION:
MILL TRIBUTARY 15
END DESCRIPTION:

--- MILL TRIBUTARY 15.p01 (plan) ---

Plan Title=Multiple Run
Short Identifier=Multiple
Geom File=g01
Flow File=f01
Subcritical Flow
K Sum by GR= 0
Std Step Tol= 0.01
Critical Tol= 0.01
Num of Std Step Trials= 20
Max Error Tol= 0.3
Flow Tol Ratio= 0.001
Split Flow NTrial= 30
Split Flow Tol= 0.02
Split Flow Ratio= 0.02
Log Output Level= 0
Friction Slope Method= 1
Unsteady Friction Slope Method= 2
Unsteady Bridges Friction Slope Method= 1
Parabolic Critical Depth
Global Vel Dist=  1 , 1 , 1
Global Log Level= 0
CheckData=True
Encroach Param= -1, 0, 0, 0
BEGIN DESCRIPTION:
Multiple Run
END DESCRIPTION:

--- MILL TRIBUTARY 15.f01 (steady flow) ---

Flow Title=Multiple
Number of Profiles=7
Profile Names=10-year,25-year,50-year,1pct_min,100-year,1pct_plu,500-year
River Rch & RM= MILL TRIBUTARY 1,Reach-1,6512
     526     850    1143     747    1490    2973    2504
River Rch & RM= MILL TRIBUTARY 1,Reach-1,5354
     749    1231    1676    1105    2205    4399    3781
Boundary for River Rch & Prof#=MILL TRIBUTARY 1,Reach-1,1
Up Type=0
Dn Type=3
Dn Slope=0.005
Boundary for River Rch & Prof#=MILL TRIBUTARY 1,Reach-1,2
Up Type=0
Dn Type=3
Dn Slope=0.005
Boundary for River Rch & Prof#=MILL TRIBUTARY 1,Reach-1,3
Up Type=0
Dn Type=3
Dn Slope=0.005
Boundary for River Rch & Prof#=MILL TRIBUTARY 1,Reach-1,4
Up Type=0
Dn Type=3
Dn Slope=0.005
Boundary for River Rch & Prof#=MILL TRIBUTARY 1,Reach-1,5
Up Type=0
Dn Type=3
Dn Slope=0.005
Boundary for River Rch & Prof#=MILL TRIBUTARY 1,Reach-1,6
Up Type=0
Dn Type=3
Dn Slope=0.005
Boundary for River Rch & Prof#=MILL TRIBUTARY 1,Reach-1,7
Up Type=0
Dn Type=3
Dn Slope=0.005

--- MILL TRIBUTARY 15.g01 (geometry) ---

Geom Title=Existing Conditions

River Reach=MILL TRIBUTARY 1,Reach-1
Reach XY= 30
      2324875.00     13783725.00      2324930.46     13783522.55
      2325065.85     13783381.73      2325026.84     13783281.13
      2325166.96     13783028.32      2325125.39     13782690.16
      2325221.44     13782573.53      2325228.48     13782426.27
      2325319.37     13782369.38      2325557.86     13781991.28
      2325765.84     13781932.00      2325732.81     13781875.11
      2325774.35     13781809.84      2325774.91     13781445.02
      2325726.54     13781330.85      2325908.37     13781191.71
      2325974.51     13781059.78      2325964.54     13780914.47
      2325804.87     13780905.58      2325630.41     13780677.42
      2325625.38     13780590.28      2325680.46     13780322.55
      2325967.39     13779928.33      2325883.99     13779818.34
      2326167.40     13779421.66      2326031.06     13779283.14
      2325838.26     13779188.66      2325819.58     13779072.33
      2325685.65     13778984.99      2325525.00     13778675.00

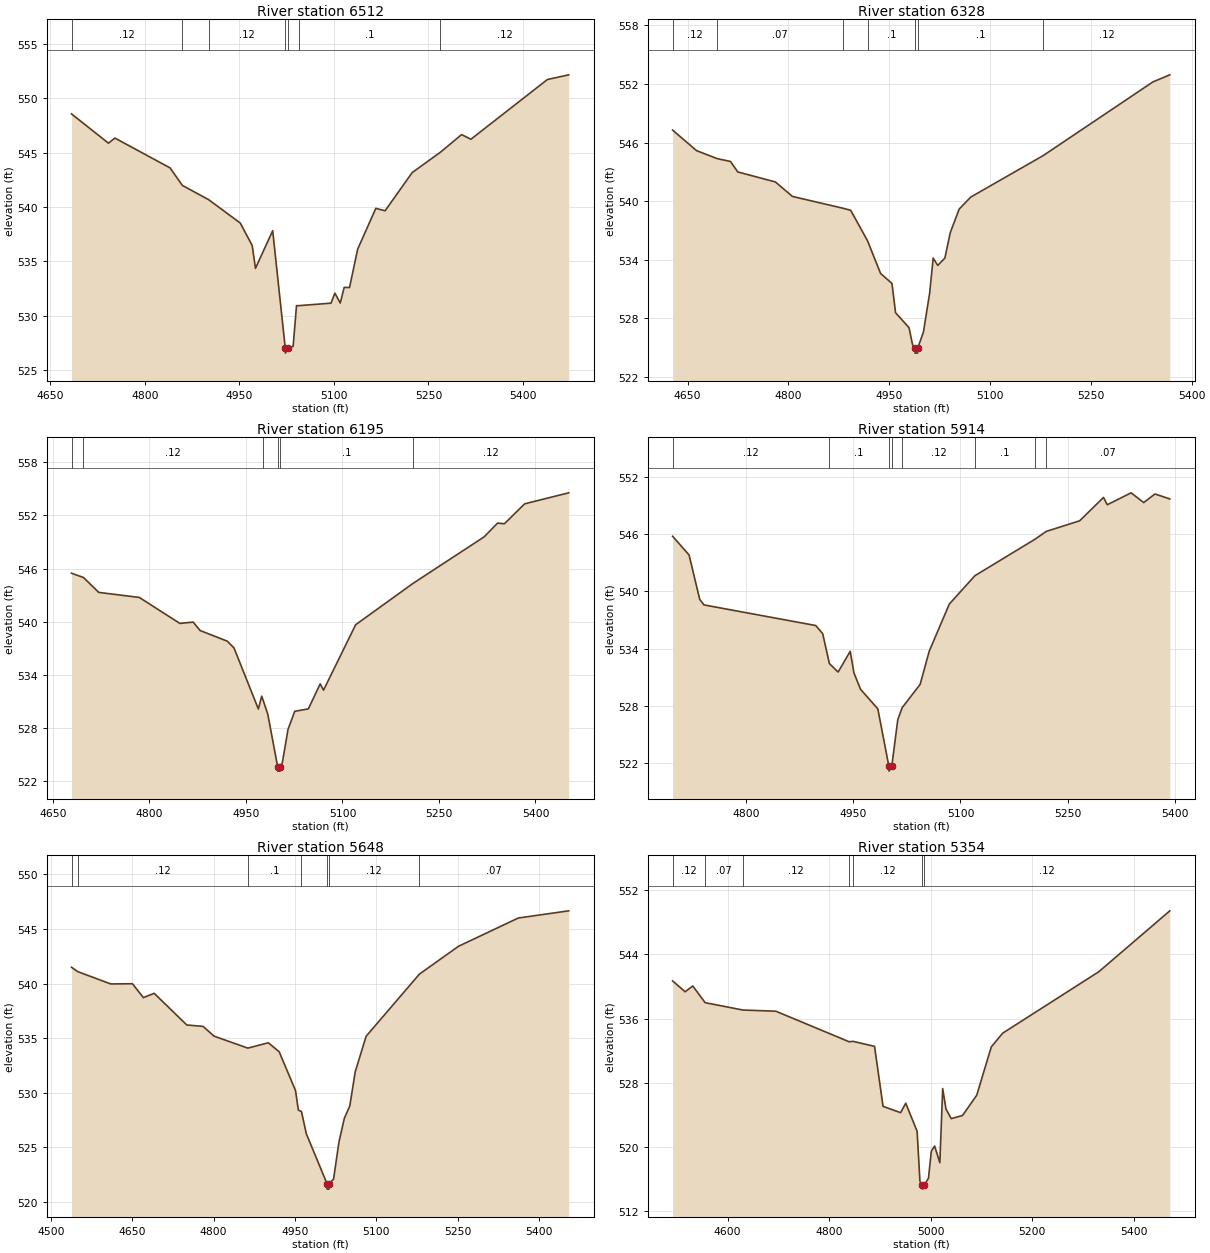
Type RM Length L Ch R = 1,6512,184,184,184
BEGIN DESCRIPTION:
B19493
END DESCRIPTION:
XS GIS Cut Line= 3
      2325210.69     13783785.93      2324828.49     13783667.21
      2324513.93     13783439.23
#Sta/Elev= 30
  4683.9  548.55  4742.5  545.86  4752.7  546.33  4840.2  543.59  4859.7  541.98
  4901.4  540.67  4951.6  538.52  4970.5  536.46  4975.7  534.36  5003.0  537.82
  5022.9  527.07  5023.2  526.57  5026.9  527.07  5035.4  527.19  5040.8  530.93
  5044.0  530.93  5095.5  531.16  5101.7  532.08  5110.2  531.17  5116.4  532.61
  5124.9  532.60  5137.8  536.12  5166.6  539.87  5181.3  539.65  5224.3  543.16
  5269.1  545.03  5302.7  546.65  5317.4  546.22  5438.8  551.71  5472.6  552.14
#Mann=7,-1,0
  4683.9    0.12       0  4859.7    0.07       0  4901.4    0.12       0
  5022.9    0.05       0  5026.9    0.12       0  5044.0     0.1       0
  5269.1    0.12       0
Bank Sta=5022.9,5026.9
Exp/Cntr=0.3,0.1

Type RM Length L Ch R = 1,6328,133,133,133
BEGIN DESCRIPTION:
B19494
END DESCRIPTION:
XS GIS Cut Line= 2
      2325286.03     13783641.16      2324590.18     13783389.96
#Sta/Elev= 30
  4627.7  547.28  4663.3  545.18  4694.1  544.36  4713.8  544.07  4724.6  543.00
  4780.7  541.97  4806.0  540.49  4880.7  539.29  4892.7  539.07  4917.8  535.94
  4937.1  532.61  4954.1  531.58  4959.4  528.59  4979.4  527.06  4984.7  525.32
  4988.3  524.95  4988.5  524.45  4992.0  524.45  4992.3  524.95  5000.9  526.61
  5010.1  530.57  5015.4  534.18  5022.2  533.43  5032.8  534.18  5040.8  536.78
  5054.1  539.20  5071.4  540.43  5179.3  544.68  5342.2  552.21  5367.5  552.94
#Mann=7,-1,0
  4627.7    0.12       0  4694.1    0.07       0  4880.7    0.12       0
  4917.8     0.1       0  4988.3    0.05       0  4992.3     0.1       0
  5179.3    0.12       0
Bank Sta=4988.3,4992.3
Exp/Cntr=0.3,0.1

Type RM Length L Ch R = 1,6195,281,281,281
BEGIN DESCRIPTION:
B19492
END DESCRIPTION:
XS GIS Cut Line= 2
      2325335.26     13783519.55      2324599.84     13783282.13
#Sta/Elev= 30
  4678.9  545.48  4697.5  545.00  4721.2  543.32  4784.3  542.75  4847.3  539.82
  4867.9  539.97  4878.8  539.02  4920.9  537.82  4931.4  537.06  4969.3  530.17
  4974.5  531.62  4976.8  531.13  4983.9  529.60  4999.3  523.66  4999.6  523.16
  5003.1  523.16  5003.3  523.66  5006.6  524.12  5015.4  527.87  5025.9  529.91
  5047.0  530.18  5065.4  533.00  5070.6  532.29  5120.5  539.67  5209.6  544.33
  5320.2  549.58  5341.2  551.14  5351.7  551.06  5383.2  553.31  5451.7  554.55
#Mann=6,-1,0
  4678.9    0.07       0  4697.5    0.12       0  4976.8     0.1       0
  4999.3    0.05       0  5003.3     0.1       0  5209.6    0.12       0
Bank Sta=4999.3,5003.3
Exp/Cntr=0.3,0.1

Type RM Length L Ch R = 1,5914,266,266,266
BEGIN DESCRIPTION:
B19491
END DESCRIPTION:
XS GIS Cut Line= 2
      2325367.07     13783270.51      2324699.97     13783074.14
#Sta/Elev= 30
  4697.4  545.78  4720.4  543.82  4735.3  539.17  4741.3  538.59  4897.6  536.43
  4907.3  535.58  4916.7  532.44  4928.9  531.56  4945.8  533.73  4951.0  531.47
  4960.2  529.76  4984.4  527.70  4999.9  521.68  5000.1  521.18  5003.9  521.68
  5012.3  526.56  5018.5  527.83  5043.6  530.27  5056.3  533.74  5084.4  538.68
  5120.2  541.65  5204.7  545.49  5220.0  546.29  5266.7  547.40  5300.1  549.85
  5305.3  549.08  5338.6  550.33  5356.3  549.31  5372.0  550.21  5392.8  549.69
#Mann=8,-1,0
  4697.4    0.12       0  4916.7     0.1       0  4999.9    0.05       0
  5003.9     0.1       0  5018.5    0.12       0  5120.2     0.1       0
  5204.7    0.12       0  5220.0    0.07       0
Bank Sta=4999.9,5003.9
Exp/Cntr=0.3,0.1

Type RM Length L Ch R = 1,5648,294,294,294
BEGIN DESCRIPTION:
B19490
END DESCRIPTION:
XS GIS Cut Line= 2
      2325587.17     13782937.52      2324672.10     13782986.75
#Sta/Elev= 30
  4538.2  541.50  4549.6  541.10  4610.5  539.97  4650.5  539.99  4670.6  538.72
  4690.6  539.11  4750.7  536.21  4780.7  536.08  4800.8  535.19  4863.2  534.09
  4900.9  534.58  4920.9  533.76  4951.0  530.21  4956.3  528.41  4962.0  528.28
  4971.0  526.24  5009.1  521.67  5009.3  521.17  5012.8  521.17  5013.1  521.67
  5021.1  522.08  5031.1  525.48  5041.1  527.67  5051.1  528.79  5061.1  531.92
  5081.2  535.18  5179.4  540.87  5251.4  543.42  5361.6  546.01  5454.6  546.67
#Mann=7,-1,0
  4538.2    0.07       0  4549.6    0.12       0  4863.2     0.1       0
  4962.0    0.12       0  5009.1    0.05       0  5013.1    0.12       0
  5179.4    0.07       0
Bank Sta=5009.1,5013.1
Exp/Cntr=0.3,0.1

Type RM Length L Ch R = 1,5354,266,266,266
BEGIN DESCRIPTION:
B19489
END DESCRIPTION:
XS GIS Cut Line= 2
      2325587.10     13782896.96      2324710.17     13782459.94
#Sta/Elev= 30
  4491.5  540.69  4516.2  539.34  4531.2  540.06  4555.6  537.98  4630.0  537.06
  4695.0  536.91  4839.4  533.10  4846.9  533.15  4889.4  532.53  4906.2  525.04
  4940.8  524.25  4950.9  525.43  4973.3  521.93  4978.9  515.67  4983.5  515.21
  4983.7  514.71  4987.5  515.21  4995.7  516.07  5001.3  519.44  5007.8  520.09
  5018.1  518.01  5023.7  527.26  5030.2  524.71  5040.5  523.51  5062.8  523.90
  5090.8  526.43  5119.5  532.46  5141.9  534.17  5331.4  541.84  5471.3  549.44
#Mann=7,-1,0
  4491.5    0.12       0  4555.6    0.07       0  4630.0    0.12       0
  4839.4   0.035       0  4846.9    0.12       0  4983.5    0.05       0
  4987.5    0.12       0
Bank Sta=4983.5,4987.5
Exp/Cntr=0.3,0.1

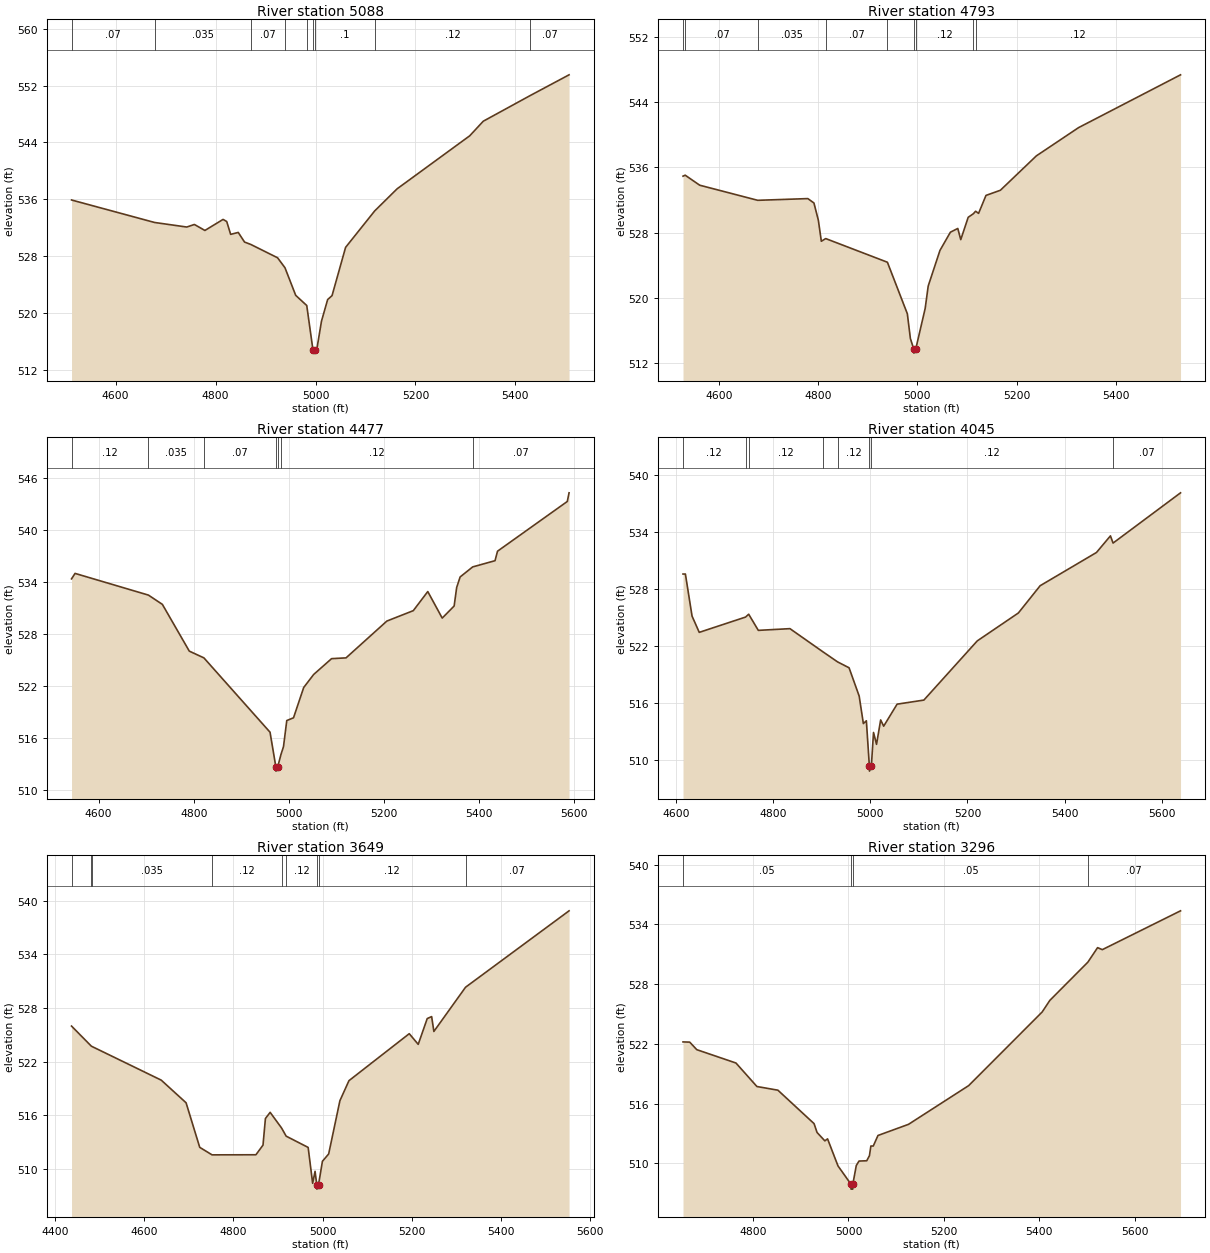
Type RM Length L Ch R = 1,5088,295,295,295
BEGIN DESCRIPTION:
B19488
END DESCRIPTION:
XS GIS Cut Line= 2
      2325636.39     13782702.99      2324798.35     13782165.48
#Sta/Elev= 30
  4511.8  535.91  4678.0  532.75  4742.4  532.11  4757.6  532.47  4778.7  531.63
  4815.0  533.18  4822.3  532.89  4830.2  531.08  4845.4  531.35  4858.0  530.00
  4870.3  529.67  4924.1  527.79  4938.9  526.39  4960.4  522.51  4982.5  521.08
  4994.8  514.89  4995.0  514.39  4998.5  514.39  4998.8  514.89  5002.7  514.96
  5012.0  518.89  5024.3  521.92  5033.1  522.47  5060.2  529.25  5118.4  534.37
  5163.3  537.48  5308.6  544.93  5335.7  546.98  5430.0  550.60  5507.4  553.50
#Mann=9,-1,0
  4511.8    0.07       0  4678.0   0.035       0  4870.3    0.07       0
  4938.9    0.12       0  4982.5     0.1       0  4994.8    0.05       0
  4998.8     0.1       0  5118.4    0.12       0  5430.0    0.07       0
Bank Sta=4994.8,4998.8
Exp/Cntr=0.3,0.1

Type RM Length L Ch R = 1,4793,316,316,316
BEGIN DESCRIPTION:
B19487
END DESCRIPTION:
XS GIS Cut Line= 2
      2325772.47     13782485.81      2324945.60     13781919.14
#Sta/Elev= 30
  4528.0  534.93  4532.3  535.05  4561.7  533.82  4678.5  531.97  4779.5  532.18
  4791.8  531.64  4800.7  529.52  4806.7  526.95  4815.5  527.28  4939.8  524.38
  4980.0  518.06  4986.1  515.03  4992.9  513.74  4993.2  513.24  4996.9  513.74
  5015.9  518.72  5022.0  521.46  5045.7  525.83  5066.7  528.06  5081.6  528.52
  5087.6  527.15  5102.6  529.89  5113.1  530.33  5117.5  530.63  5123.5  530.37
  5138.4  532.57  5167.4  533.20  5240.0  537.42  5325.0  540.88  5530.4  547.35
#Mann=9,-1,0
  4528.0    0.12       0  4532.3    0.07       0  4678.5   0.035       0
  4815.5    0.07       0  4939.8    0.12       0  4992.9    0.05       0
  4996.9    0.12       0  5113.1     0.1       0  5117.5    0.12       0
Bank Sta=4992.9,4996.9
Exp/Cntr=0.3,0.1

Type RM Length L Ch R = 1,4477,432,432,432
BEGIN DESCRIPTION:
B19486
END DESCRIPTION:
XS GIS Cut Line= 3
      2325888.26     13782312.04      2325526.34     13781926.95
      2325039.97     13781747.46
#Sta/Elev= 30
  4542.9  534.38  4550.3  535.01  4704.7  532.50  4734.0  531.43  4790.7  526.02
  4821.4  525.24  4960.6  516.64  4972.8  512.64  4973.0  512.14  4976.8  512.64
  4983.6  514.07  4988.9  514.97  4995.8  517.99  5010.0  518.31  5031.4  521.81
  5052.4  523.32  5090.1  525.15  5120.5  525.24  5206.5  529.50  5262.0  530.70
  5292.5  532.91  5322.9  529.84  5348.0  531.24  5353.3  533.38  5360.6  534.60
  5387.0  535.76  5434.0  536.48  5439.3  537.58  5586.1  543.33  5589.8  544.33
#Mann=7,-1,0
  4542.9    0.12       0  4704.7   0.035       0  4821.4    0.07       0
  4972.8    0.05       0  4976.8    0.07       0  4983.6    0.12       0
  5387.0    0.07       0
Bank Sta=4972.8,4976.8
Exp/Cntr=0.3,0.1

Type RM Length L Ch R = 1,4045,396,396,396
BEGIN DESCRIPTION:
B19485
END DESCRIPTION:
XS GIS Cut Line= 3
      2326088.05     13781958.78      2325749.30     13781715.57
      2325155.73     13781591.07
#Sta/Elev= 30
  4614.8  529.53  4619.7  529.53  4633.4  525.10  4648.2  523.39  4743.5  525.00
  4749.9  525.30  4769.7  523.60  4834.8  523.78  4902.4  521.35  4932.8  520.28
  4956.4  519.66  4977.2  516.68  4985.8  513.79  4992.0  514.08  4998.2  509.28
  4998.4  508.78  5002.2  509.28  5006.7  512.85  5012.9  511.60  5021.4  514.17
  5027.6  513.51  5055.2  515.83  5110.3  516.26  5220.1  522.49  5304.7  525.43
  5349.5  528.30  5465.4  531.80  5494.1  533.55  5499.5  532.79  5638.3  538.08
#Mann=8,-1,0
  4614.8    0.12       0  4743.5   0.035       0  4749.9    0.12       0
  4902.4    0.07       0  4932.8    0.12       0  4998.2    0.05       0
  5002.2    0.12       0  5499.5    0.07       0
Bank Sta=4998.2,5002.2
Exp/Cntr=0.3,0.1

Type RM Length L Ch R = 1,3649,353,353,353
BEGIN DESCRIPTION:
B19484
END DESCRIPTION:
XS GIS Cut Line= 3
      2326253.14     13781547.63      2325668.22     13781333.35
      2325179.41     13781272.61
#Sta/Elev= 30
  4437.1  525.99  4481.4  523.75  4482.1  523.73  4638.2  519.95  4693.9  517.42
  4724.5  512.44  4752.1  511.60  4850.5  511.61  4866.4  512.69  4871.8  515.66
  4882.4  516.35  4908.0  514.60  4918.3  513.69  4967.6  512.43  4977.7  508.42
  4983.1  509.76  4986.9  508.27  4987.2  507.77  4990.9  508.27  4999.6  510.88
  5013.6  511.70  5038.8  517.65  5059.1  519.89  5194.3  525.14  5214.4  523.95
  5234.6  526.83  5244.5  527.05  5249.5  525.39  5320.5  530.33  5552.6  538.87
#Mann=9,-1,0
  4437.1   0.035       0  4481.4    0.05       0  4482.1   0.035       0
  4752.1    0.12       0  4908.0   0.035       0  4918.3    0.12       0
  4986.9    0.05       0  4990.9    0.12       0  5320.5    0.07       0
Bank Sta=4986.9,4990.9
Exp/Cntr=0.3,0.1

Type RM Length L Ch R = 1,3296,464,464,464
BEGIN DESCRIPTION:
B19483
END DESCRIPTION:
XS GIS Cut Line= 3
      2326247.37     13781272.56      2325899.87     13781087.22
      2325251.22     13781110.39
#Sta/Elev= 30
  4653.2  522.19  4667.2  522.17  4682.1  521.41  4764.2  520.07  4808.1  517.71
  4852.1  517.34  4927.9  513.98  4934.2  513.09  4950.5  512.25  4956.2  512.45
  4978.1  509.73  5005.2  507.90  5005.5  507.40  5009.0  507.40  5009.2  507.90
  5016.4  509.77  5022.1  510.22  5038.3  510.25  5044.0  510.76  5047.0  511.73
  5052.0  511.73  5061.9  512.79  5125.9  513.91  5252.0  517.80  5406.1  525.20
  5422.1  526.36  5501.8  530.20  5522.2  531.66  5532.2  531.46  5696.1  535.36
#Mann=4,-1,0
  4653.2    0.05       0  5005.2    0.05       0  5009.2    0.05       0
  5501.8    0.07       0
Bank Sta=5005.2,5009.2
Exp/Cntr=0.3,0.1

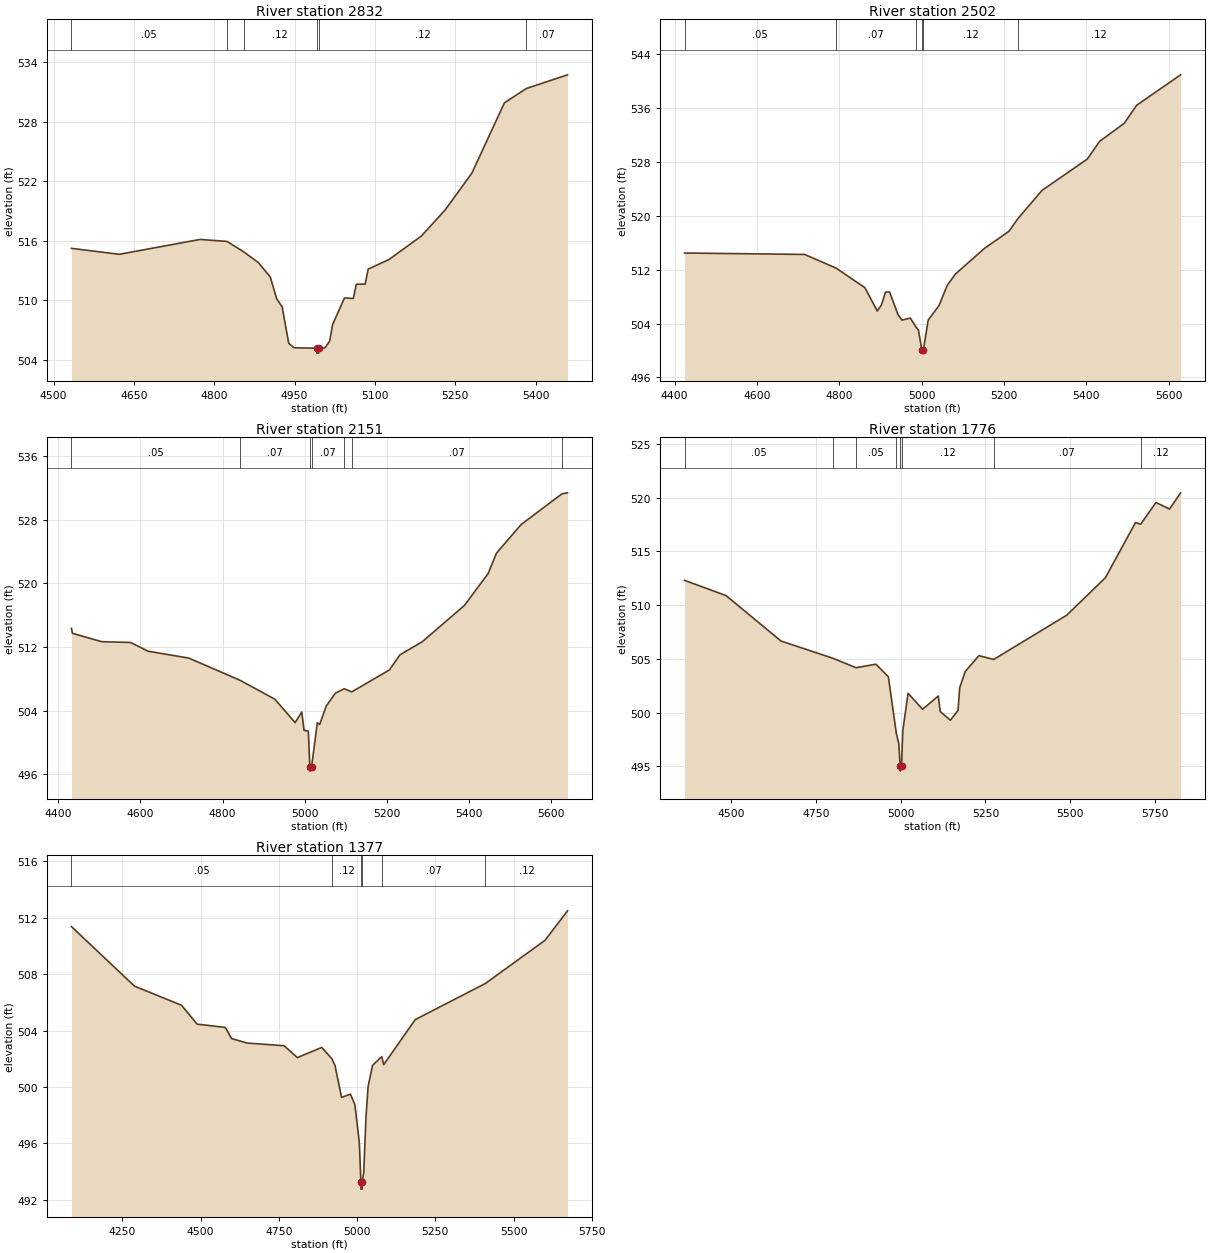
Type RM Length L Ch R = 1,2832,330,330,330
BEGIN DESCRIPTION:
B19482
END DESCRIPTION:
XS GIS Cut Line= 3
      2326198.11     13780841.10      2325928.83     13780774.50
      2325352.63     13781072.73
#Sta/Elev= 30
  4533.4  515.23  4622.7  514.63  4773.5  516.13  4823.6  515.93  4854.7  514.89
  4882.5  513.79  4904.7  512.34  4916.5  510.15  4926.8  509.32  4939.0  505.67
  4949.0  505.21  4991.2  505.17  4991.5  504.67  4995.0  504.67  4995.2  505.17
  5006.5  505.20  5015.4  505.87  5021.0  507.55  5043.1  510.23  5059.6  510.18
  5065.3  511.61  5081.8  511.63  5087.4  513.14  5126.1  514.10  5186.7  516.47
  5231.1  519.10  5281.0  522.81  5341.8  529.90  5382.7  531.34  5459.6  532.72
#Mann=6,-1,0
  4533.4    0.05       0  4823.6    0.07       0  4854.7    0.12       0
  4991.2    0.05       0  4995.2    0.12       0  5382.7    0.07       0
Bank Sta=4991.2,4995.2
Exp/Cntr=0.3,0.1

Type RM Length L Ch R = 1,2502,351,351,351
BEGIN DESCRIPTION:
B19481
END DESCRIPTION:
XS GIS Cut Line= 3
      2326163.38     13780751.34      2325841.96     13780586.28
      2324998.20     13780563.17
#Sta/Elev= 30
  4424.0  514.47  4715.8  514.26  4792.1  512.23  4862.3  509.32  4892.3  505.85
  4902.3  506.75  4912.3  508.67  4922.3  508.68  4942.3  505.37  4952.3  504.50
  4972.4  504.81  4986.4  503.48  4992.4  503.02  5000.4  500.10  5000.6  499.60
  5004.1  499.60  5004.4  500.10  5016.1  504.52  5042.4  506.67  5062.4  509.68
  5082.4  511.36  5152.4  515.14  5212.4  517.71  5233.3  519.52  5292.5  523.77
  5402.5  528.42  5432.5  531.05  5492.6  533.75  5522.6  536.42  5629.4  540.94
#Mann=6,-1,0
  4424.0    0.05       0  4792.1    0.07       0  4986.4    0.12       0
  5000.4    0.05       0  5004.4    0.12       0  5233.3    0.12       0
Bank Sta=5000.4,5004.4
Exp/Cntr=0.3,0.1

Type RM Length L Ch R = 1,2151,375,375,375
BEGIN DESCRIPTION:
B19480
END DESCRIPTION:
XS GIS Cut Line= 4
      2326131.54     13780661.59      2325850.64     13780331.47
      2325601.62     13780195.38      2325112.30     13780163.53
#Sta/Elev= 30
  4432.2  514.35  4434.4  513.73  4505.8  512.67  4576.1  512.57  4618.9  511.47
  4717.7  510.61  4843.0  507.81  4927.3  505.44  4976.7  502.50  4992.8  503.83
  4998.5  501.52  5008.8  501.44  5012.6  496.90  5012.9  496.40  5016.6  496.90
  5030.7  502.48  5036.4  502.26  5052.6  504.60  5074.4  506.19  5096.2  506.75
  5114.6  506.36  5206.2  509.12  5231.7  511.01  5286.3  512.67  5388.9  517.23
  5446.7  521.25  5466.7  523.79  5526.9  527.40  5626.4  531.26  5639.8  531.38
#Mann=7,-1,0
  4432.2    0.05       0  4843.0    0.07       0  5012.6    0.05       0
  5016.6    0.07       0  5096.2    0.12       0  5114.6    0.07       0
  5626.4    0.12       0
Bank Sta=5012.6,5016.6
Exp/Cntr=0.3,0.1

Type RM Length L Ch R = 1,1776,399,399,399
BEGIN DESCRIPTION:
B19479
END DESCRIPTION:
XS GIS Cut Line= 4
      2326157.58     13780542.85      2326009.90     13780018.74
      2325781.15     13779879.75      2325132.58     13779818.95
#Sta/Elev= 30
  4362.3  512.30  4484.7  510.88  4647.1  506.65  4799.1  505.06  4868.3  504.17
  4926.9  504.50  4963.7  503.32  4987.4  498.01  4994.5  497.11  4998.5  495.05
  4998.7  494.55  5002.5  495.05  5006.3  498.32  5021.8  501.79  5064.7  500.30
  5110.9  501.54  5116.8  500.09  5146.6  499.29  5169.1  500.19  5174.2  502.33
  5190.7  503.83  5230.9  505.29  5274.5  504.94  5490.1  509.06  5604.0  512.54
  5692.9  517.68  5708.0  517.52  5753.2  519.54  5793.3  518.93  5825.9  520.44
#Mann=8,-1,0
  4362.3    0.05       0  4799.1    0.07       0  4868.3    0.05       0
  4987.4    0.12       0  4998.5    0.05       0  5002.5    0.12       0
  5274.5    0.07       0  5708.0    0.12       0
Bank Sta=4998.5,5002.5
Exp/Cntr=0.3,0.1

Type RM Length L Ch R = 1,1377,0,0,0
BEGIN DESCRIPTION:
B19478
END DESCRIPTION:
XS GIS Cut Line= 4
      2326174.95     13780496.57      2326177.85     13779853.69
      2325928.83     13779593.09      2325355.45     13779691.55
#Sta/Elev= 30
  4087.3  511.36  4288.9  507.14  4438.9  505.79  4488.9  504.45  4578.9  504.22
  4598.9  503.43  4648.9  503.11  4766.7  502.92  4809.2  502.08  4886.9  502.80
  4919.3  502.00  4929.3  501.53  4950.4  499.26  4978.7  499.49  4992.9  498.75
  5007.0  496.09  5012.2  493.26  5012.5  492.76  5016.0  492.76  5016.2  493.26
  5021.2  493.93  5028.4  497.87  5035.3  500.05  5049.5  501.53  5078.8  502.15
  5085.0  501.58  5185.7  504.77  5409.8  507.33  5600.5  510.39  5672.4  512.48
#Mann=6,-1,0
  4087.3    0.05       0  4919.3    0.12       0  5012.2    0.05       0
  5016.2    0.12       0  5078.8    0.07       0  5409.8    0.12       0
Bank Sta=5012.2,5016.2
Exp/Cntr=0.3,0.1

Chan Stop Cuts=-1