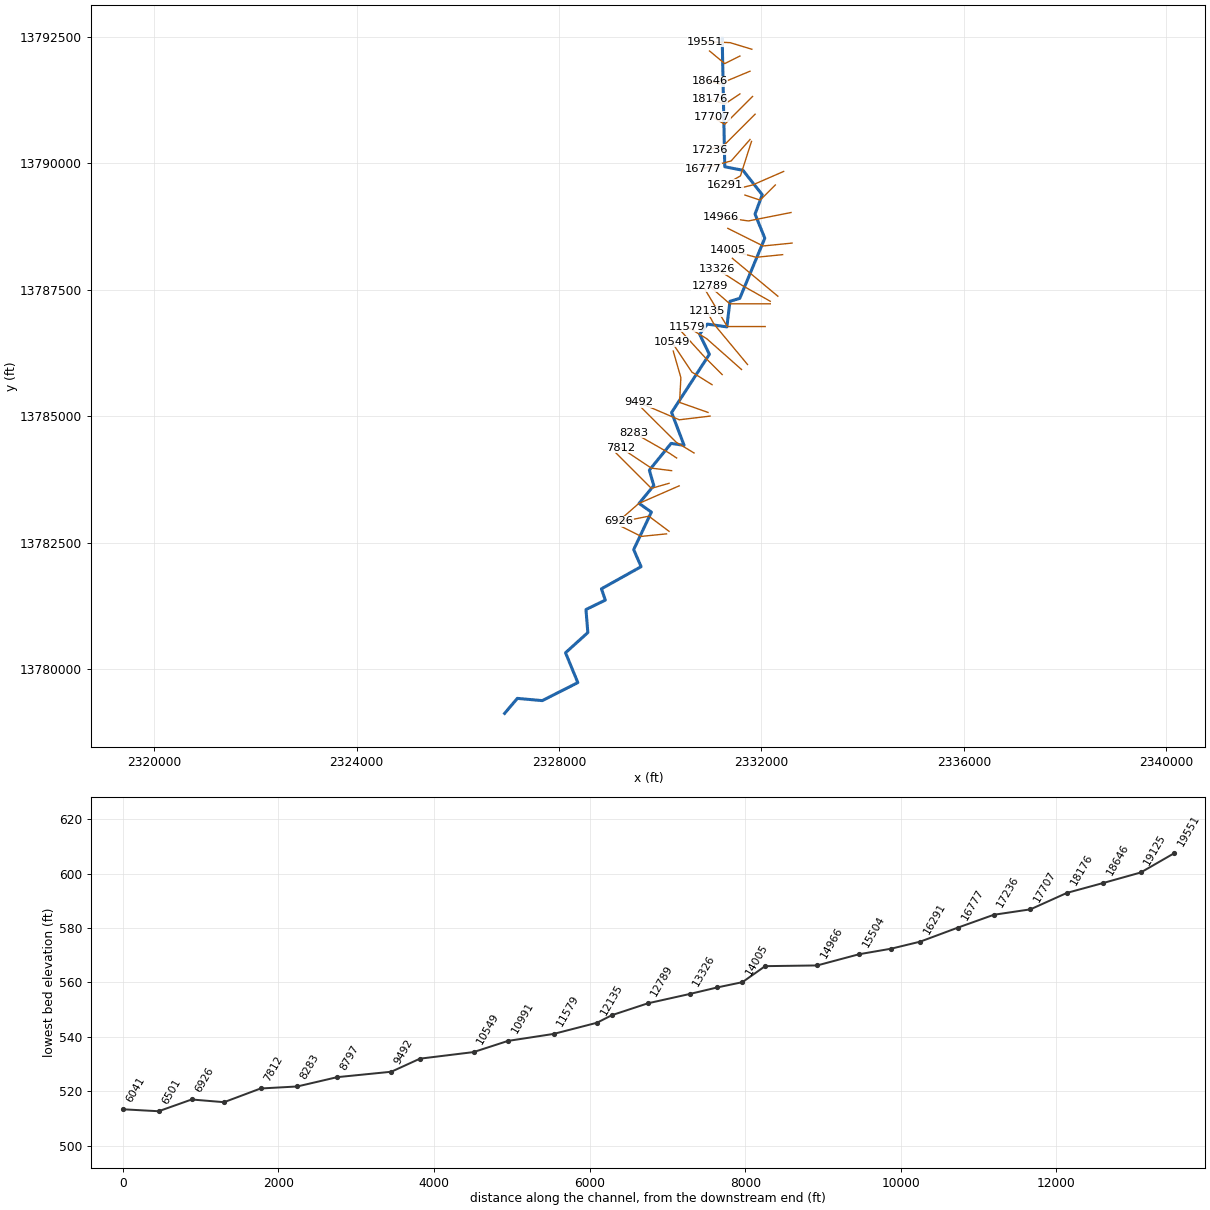
--- MILL TRIBUTARY 16.prj (project) ---

Proj Title=MILL TRIBUTARY 16 Base Level Engineering
Current Plan=p01
Default Exp/Contr=0.3,0.1
English Units
Geom File=g01
Flow File=f01
Plan File=p01
Y Axis Title=Elevation
X Axis Title(PF)=Main Channel Distance
X Axis Title(XS)=Station
BEGIN DESCRIPTION:
MILL TRIBUTARY 16
END DESCRIPTION:
DSS Export Rating Curves= 0
DSS Export Rating Curve Sorted= 0
DSS Export Volume Flow Curves= 0
DXF OffsetX= 0
DXF OffsetY= 0
DXF ScaleX= 1
DXF ScaleY= 10

--- MILL TRIBUTARY 16.p01 (plan) ---

Plan Title=Multiple Run
Short Identifier=Multiple
Geom File=g01
Flow File=f01
Subcritical Flow
K Sum by GR= 0
Std Step Tol= 0.01
Critical Tol= 0.01
Num of Std Step Trials= 20
Max Error Tol= 0.3
Flow Tol Ratio= 0.001
Split Flow NTrial= 30
Split Flow Tol= 0.02
Split Flow Ratio= 0.02
Log Output Level= 0
Friction Slope Method= 1
Unsteady Friction Slope Method= 2
Unsteady Bridges Friction Slope Method= 1
Parabolic Critical Depth
Global Vel Dist=  1 , 1 , 1
Global Log Level= 0
CheckData=True
Encroach Param= -1, 0, 0, 0
BEGIN DESCRIPTION:
Multiple Run
END DESCRIPTION:

--- MILL TRIBUTARY 16.f01 (steady flow) ---

Flow Title=Multiple
Number of Profiles=7
Profile Names=10-year,25-year,50-year,1pct_min,100-year,1pct_plu,500-year
River Rch & RM= MILL TRIBUTARY 1,Reach-1,19551
     438     696     927     599    1195    2384    1964
River Rch & RM= MILL TRIBUTARY 1,Reach-1,15918
     824    1357    1849    1219    2433    4854    4175
River Rch & RM= MILL TRIBUTARY 1,Reach-1,9492
    1095    1831    2519    1677    3345    6675    5848
River Rch & RM= MILL TRIBUTARY 1,Reach-1,6501
    1405    2371    3283    2196    4381    8742    7738
River Rch & RM= MILL TRIBUTARY 1,Reach-1,711
    1423    2403    3328    2226    4441    8860    7844
Boundary for River Rch & Prof#=MILL TRIBUTARY 1,Reach-1,1
Up Type=0
Dn Type=3
Dn Slope=0.005
Boundary for River Rch & Prof#=MILL TRIBUTARY 1,Reach-1,2
Up Type=0
Dn Type=3
Dn Slope=0.005
Boundary for River Rch & Prof#=MILL TRIBUTARY 1,Reach-1,3
Up Type=0
Dn Type=3
Dn Slope=0.005
Boundary for River Rch & Prof#=MILL TRIBUTARY 1,Reach-1,4
Up Type=0
Dn Type=3
Dn Slope=0.005
Boundary for River Rch & Prof#=MILL TRIBUTARY 1,Reach-1,5
Up Type=0
Dn Type=3
Dn Slope=0.005
Boundary for River Rch & Prof#=MILL TRIBUTARY 1,Reach-1,6
Up Type=0
Dn Type=3
Dn Slope=0.005
Boundary for River Rch & Prof#=MILL TRIBUTARY 1,Reach-1,7
Up Type=0
Dn Type=3
Dn Slope=0.005

--- MILL TRIBUTARY 16.g01 (geometry) ---

Geom Title=Existing Conditions
Program Version=4.10

River Reach=MILL TRIBUTARY 1,Reach-1
Reach XY= 30
        2331225.       13792475.      2331275.86     13789935.31
        2331635.     13789864.93      2332016.53     13789381.76
      2331874.38      13788999.7      2332067.15     13788521.77
      2331572.09     13787332.91      2331378.43     13787273.78
        2331317.     13786768.62      2330931.04     13786823.43
      2330778.31     13786623.26      2330971.97     13786226.39
        2330225.       13785075.      2330471.99     13784426.37
      2330214.92     13784463.93      2329785.47      13783934.8
      2329873.24     13783631.12       2329582.5     13783278.14
      2329825.48     13783104.84      2329476.05     13782364.56
      2329621.99     13782026.43       2328838.1     13781588.24
      2328914.96       13781365.      2328532.79     13781178.43
      2328569.48     13780722.56      2328128.75     13780323.45
      2328371.94     13779733.31      2327669.07     13779377.24
      2327176.27     13779421.53        2326925.       13779125.

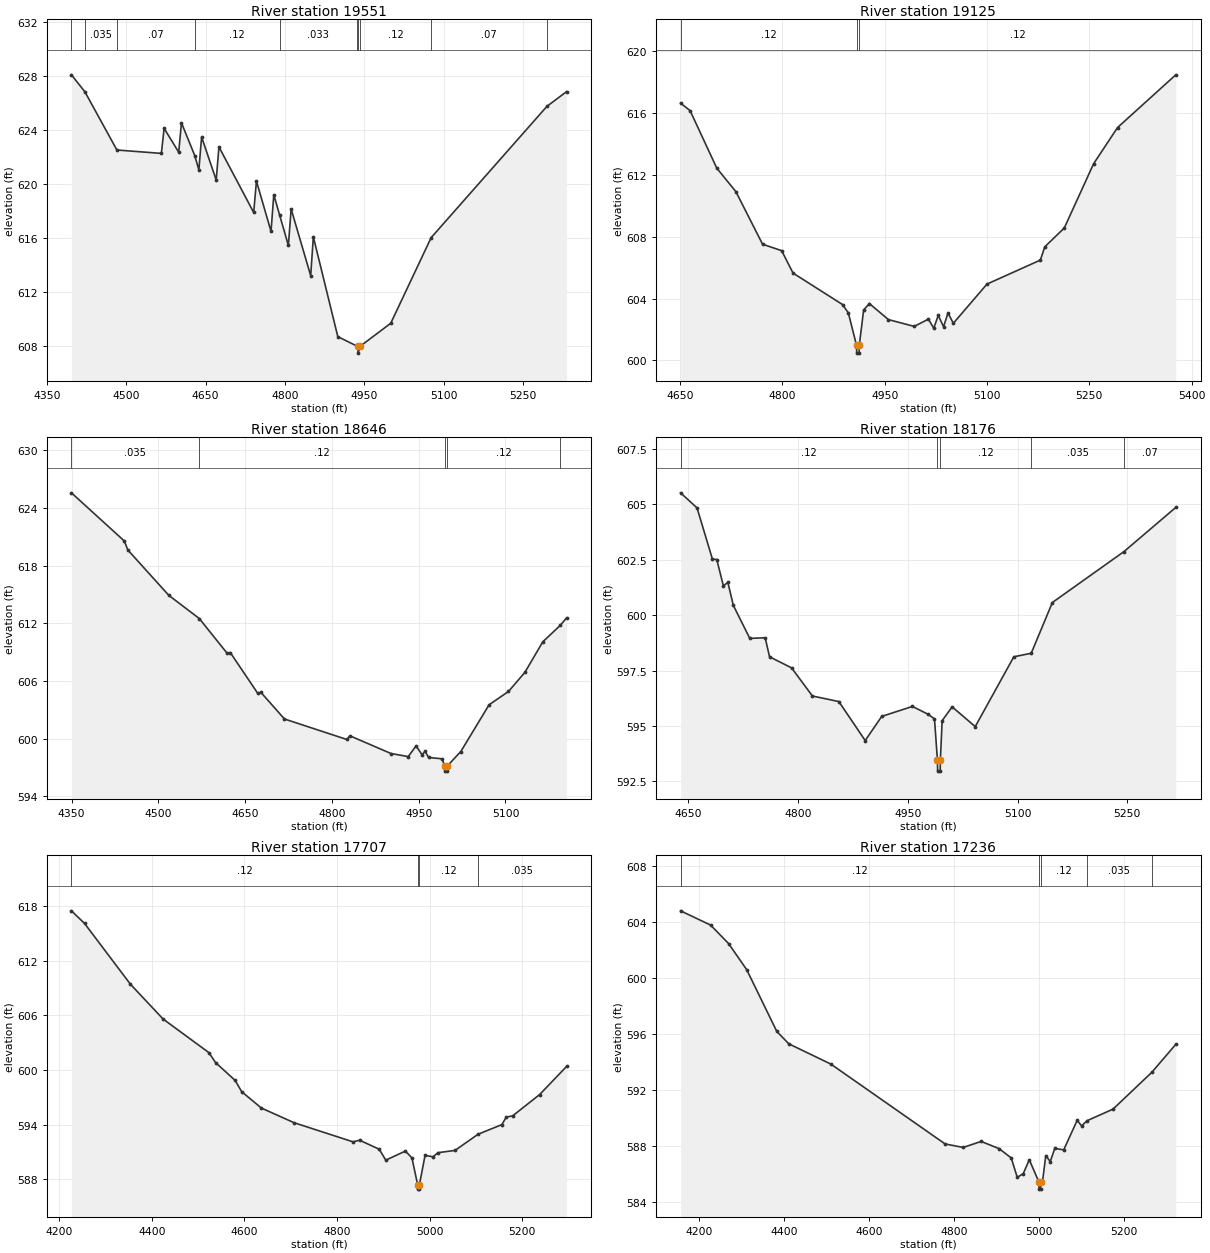
Type RM Length L Ch R = 1 ,19551   ,426,426,426
BEGIN DESCRIPTION:
MILL TRIBUTARY 16 38.0
END DESCRIPTION:
XS GIS Cut Line= 3
      2331809.35     13792259.39       2331382.3     13792389.58
      2330892.69     13792410.42
#Sta/Elev= 30
  4396.1  628.07  4421.5  626.82  4482.1  622.51  4566.2  622.26  4571.4  624.11
    4599  622.35  4604.2  624.52  4629.3   622.1  4637.1  621.04  4642.3  623.47
  4669.9  620.29  4675.1  622.74  4740.8  617.89    4746  620.21  4773.6  616.49
  4778.8   619.2    4790  617.68  4806.4  615.45  4811.6  618.15  4848.6  613.22
  4853.6  616.09  4899.9  608.71  4936.1  608.01  4937.9  607.99  4938.2  607.49
  4941.9  607.99    5000   609.7  5076.4  616.03  5295.4  625.74  5332.6  626.83
#Mann= 10 ,-1 , 0
  4396.1     .07       0  4421.5    .035       0  4482.1     .07       0
  4629.3     .12       0    4790    .033       0  4936.1     .12       0
  4937.9     .05       0  4941.9     .12       0  5076.4     .07       0
  5295.4     .12       0
Bank Sta=4937.9,4941.9
XS Rating Curve= 0 ,0
Exp/Cntr=0.3,0.1

Type RM Length L Ch R = 1 ,19125   ,479,479,479
BEGIN DESCRIPTION:
MILL TRIBUTARY 16 37.0
END DESCRIPTION:
XS GIS Cut Line= 3
      2331575.03     13792125.02        2331275.       13791975.
      2330974.97     13792225.02
#Sta/Elev= 30
  4650.7  616.65  4664.7  616.16  4703.8  612.44  4731.8  610.92  4770.9  607.52
  4798.9   607.1  4815.6  605.65  4888.3  603.61  4896.7  603.07  4908.7  600.97
  4908.9  600.47  4912.4  600.47  4912.7  600.97  4919.1  603.26  4927.5  603.68
  4955.4  602.64  4993.3   602.2  5014.1  602.67  5021.9  602.08  5028.5  602.91
  5036.3  602.18  5042.8  603.07  5050.6   602.4    5100  604.94  5178.2  606.49
  5184.7  607.35  5213.3  608.57  5256.3  612.73  5291.4  615.07  5376.7  618.48
#Mann= 3 ,-1 , 0
  4650.7     .12       0  4908.7     .05       0  4912.7     .12       0
Bank Sta=4908.7,4912.7
XS Rating Curve= 0 ,0
Exp/Cntr=0.3,0.1

Type RM Length L Ch R = 1 ,18646   ,470,470,470
BEGIN DESCRIPTION:
MILL TRIBUTARY 16 36.0
END DESCRIPTION:
XS GIS Cut Line= 3
      2331774.99       13791825.        2331175.       13791575.
      2330975.04     13791624.99
#Sta/Elev= 30
  4349.6  625.56  4441.1  620.55  4447.1  619.62    4518   614.9  4570.7  612.49
  4618.8  608.88  4624.2  608.96  4671.9   604.7  4677.3  604.81  4717.9  602.05
  4825.7  599.92  4831.1   600.3  4902.1  598.46  4931.9  598.14  4945.4  599.25
  4955.7  598.34  4961.1  598.69  4967.1  598.05  4990.4  597.91  4994.9  597.13
  4995.1  596.63  4998.6  596.63  4998.9  597.13  5022.8  598.67  5071.7  603.53
  5105.2  604.91  5133.6   606.9  5164.5  610.07  5194.7  611.78  5205.7  612.57
#Mann= 5 ,-1 , 0
  4349.6    .035       0  4570.7     .12       0  4994.9     .05       0
  4998.9     .12       0  5194.7     .07       0
Bank Sta=4994.9,4998.9
XS Rating Curve= 0 ,0
Exp/Cntr=0.3,0.1

Type RM Length L Ch R = 1 ,18176   ,469,469,469
BEGIN DESCRIPTION:
MILL TRIBUTARY 16 35.0
END DESCRIPTION:
XS GIS Cut Line= 3
      2331574.96     13791374.98        2331275.       13791175.
      2330975.04     13791274.99
#Sta/Elev= 30
  4639.5  605.52    4662  604.84    4683  602.53    4689  602.51    4698  601.32
  4704.1  601.48  4711.6  600.44  4734.1  598.95  4755.1  598.98  4761.1  598.12
  4791.2  597.62  4819.7  596.35  4855.8   596.1  4891.8  594.34  4914.4  595.43
  4956.4  595.88  4977.5  595.53  4986.5  595.32  4990.5  593.46  4990.8  592.96
  4994.3  592.96  4994.5  593.46    4997  595.24  5010.6  595.86  5042.2  594.97
  5094.9  598.12  5118.7  598.28  5147.6  600.57  5245.5  602.87  5316.2  604.86
#Mann= 5 ,-1 , 0
  4639.5     .12       0  4990.5     .05       0  4994.5     .12       0
  5118.7    .035       0  5245.5     .07       0
Bank Sta=4990.5,4994.5
XS Rating Curve= 0 ,0
Exp/Cntr=0.3,0.1

Type RM Length L Ch R = 1 ,17707   ,471,471,471
BEGIN DESCRIPTION:
MILL TRIBUTARY 16 34.0
END DESCRIPTION:
XS GIS Cut Line= 3
      2331825.03     13791325.03        2331275.       13790775.
      2331025.01     13790924.99
#Sta/Elev= 30
  4226.3  617.46  4254.6  616.08  4353.6  609.41  4424.3  605.58  4523.3  601.89
  4537.5  600.81  4579.9  598.84    4594  597.61  4636.5  595.81  4707.2   594.2
  4834.5   592.1  4848.6  592.28    4891  591.29  4905.2  590.09  4947.6  591.09
  4961.7  590.33  4973.9  587.41  4974.1  586.91  4977.6  586.91  4977.9  587.41
    4990  590.62  5007.1  590.46  5017.8  590.91  5054.7  591.16  5104.3  592.93
  5155.8  593.99  5165.5  594.82  5179.1  594.95  5237.4  597.29  5295.7  600.38
#Mann= 4 ,-1 , 0
  4226.3     .12       0  4973.9     .05       0  4977.9     .12       0
  5104.3    .035       0
Bank Sta=4973.9,4977.9
XS Rating Curve= 0 ,0
Exp/Cntr=0.3,0.1

Type RM Length L Ch R = 1 ,17236   ,459,459,459
BEGIN DESCRIPTION:
MILL TRIBUTARY 16 33.0
END DESCRIPTION:
XS GIS Cut Line= 3
      2331875.02     13790975.02        2331275.       13790375.
      2330974.99       13790275.
#Sta/Elev= 30
  4156.1  604.81  4226.8  603.79  4269.3  602.46  4311.7   600.6  4382.4  596.19
  4410.7   595.3  4509.7  593.85  4778.4  588.14  4820.8  587.89  4863.2  588.32
  4905.7   587.8  4933.9  587.14  4948.1  585.75  4962.2  586.02  4976.4  587.01
  4999.1  585.41  4999.4  584.91  5002.9  584.91  5003.1  585.41  5007.3  585.41
  5015.2  587.31  5025.7  586.88  5036.3  587.82  5057.4  587.72    5089  589.83
  5099.5  589.43  5112.1   589.8  5173.3  590.63  5264.5  593.26  5320.9  595.26
#Mann= 5 ,-1 , 0
  4156.1     .12       0  4999.1     .05       0  5003.1     .12       0
  5112.1    .035       0  5264.5     .07       0
Bank Sta=4999.1,5003.1
XS Rating Curve= 0 ,0
Exp/Cntr=0.3,0.1

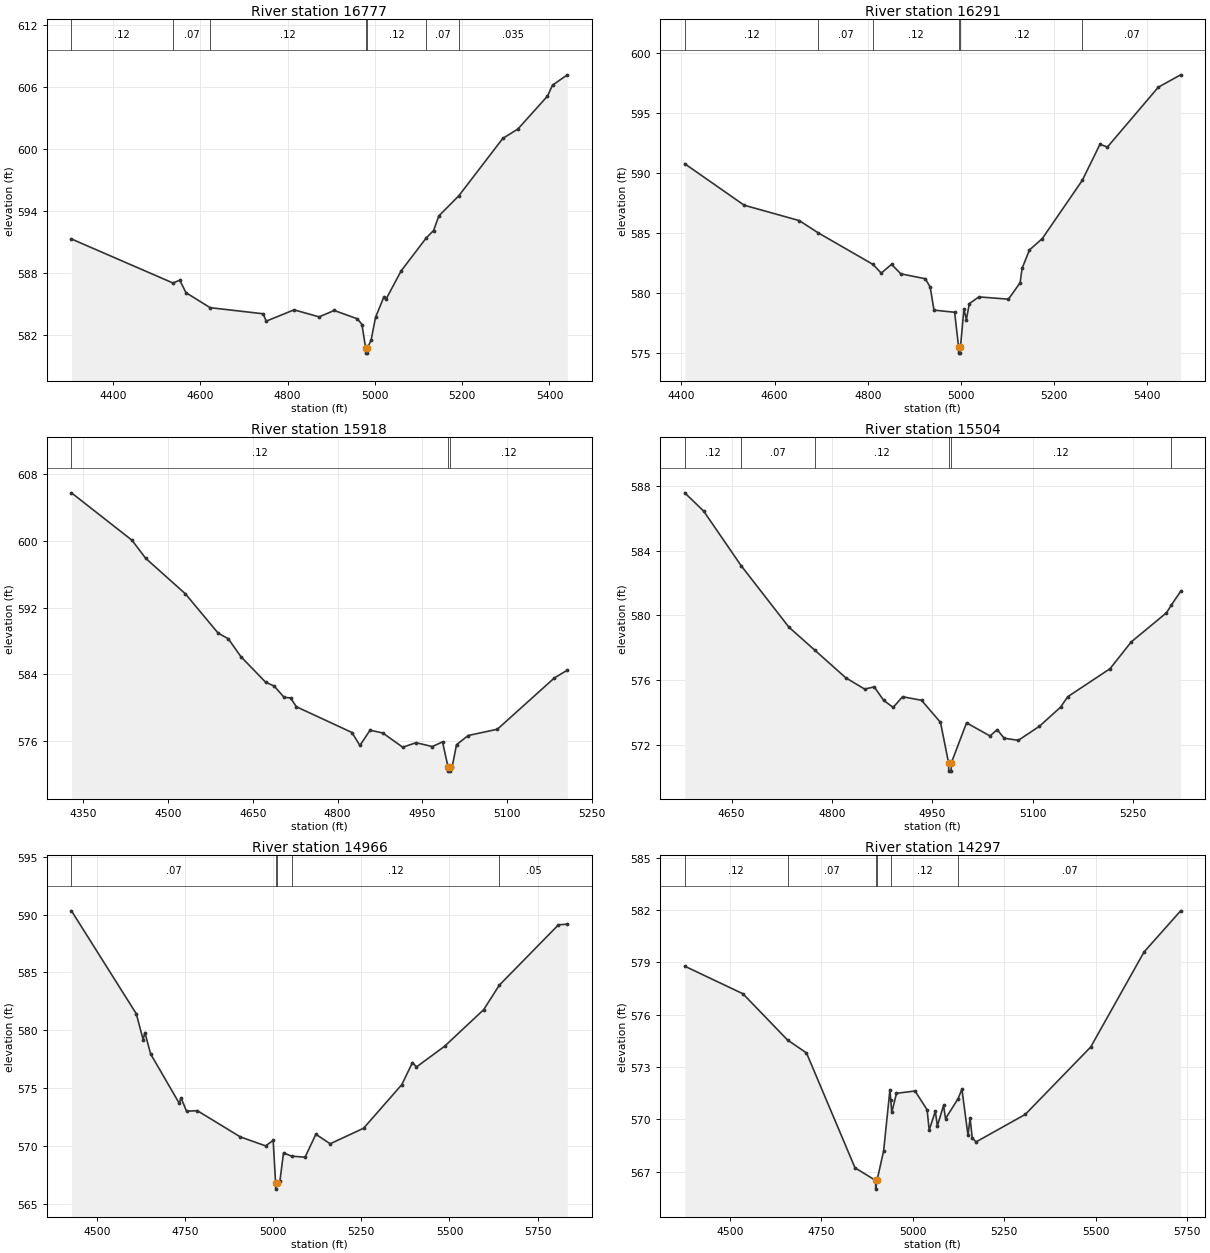
Type RM Length L Ch R = 1 ,16777   ,486,486,486
BEGIN DESCRIPTION:
MILL TRIBUTARY 16 32.0
END DESCRIPTION:
XS GIS Cut Line= 3
      2331775.01     13790475.01      2331403.14     13790051.04
      2330851.08     13789900.01
#Sta/Elev= 30
  4304.6  591.26  4537.1     587  4552.8  587.27    4567  586.06  4622.5  584.61
  4743.6  584.02  4751.1  583.31  4814.7   584.4  4872.2  583.72  4906.7  584.34
  4959.9  583.53  4970.3  582.98  4978.7  580.71  4978.9  580.21  4982.4  580.21
  4982.7  580.71  4991.2  581.45  5001.4  583.67  5020.5  585.65  5025.7  585.45
  5060.2  588.18    5118  591.38  5134.4  592.08  5146.5  593.49  5192.4  595.45
  5293.1     601  5327.6   601.9  5395.4  605.09    5407  606.15  5440.9  607.15
#Mann= 7 ,-1 , 0
  4304.6     .12       0  4537.1     .07       0  4622.5     .12       0
  4978.7     .05       0  4982.7     .12       0    5118     .07       0
  5192.4    .035       0
Bank Sta=4978.7,4982.7
XS Rating Curve= 0 ,0
Exp/Cntr=0.3,0.1

Type RM Length L Ch R = 1 ,16291   ,373,373,373
BEGIN DESCRIPTION:
MILL TRIBUTARY 16 31.0
END DESCRIPTION:
XS GIS Cut Line= 3
      2331804.17     13790436.45      2331585.43     13789754.17
      2331283.38     13789582.31
#Sta/Elev= 30
  4407.3  590.79  4534.8  587.34  4652.9  586.06  4693.7  585.04  4810.9  582.42
  4828.9  581.69    4851  582.42  4870.9  581.63  4923.4  581.22  4933.9  580.53
  4942.1  578.61  4986.4  578.43  4994.9  575.53  4995.1  575.03  4998.6  575.03
  4998.9  575.53  5006.3   578.7  5011.6  577.82  5017.9  579.15  5038.5  579.71
  5101.9  579.52  5126.9  580.89  5131.1  582.08    5147  583.62  5174.4  584.56
  5260.3  589.41  5298.3  592.41  5314.2  592.18  5423.4  597.16  5471.3  598.19
#Mann= 6 ,-1 , 0
  4407.3     .12       0  4693.7     .07       0  4810.9     .12       0
  4994.9     .05       0  4998.9     .12       0  5260.3     .07       0
Bank Sta=4994.9,4998.9
XS Rating Curve= 0 ,0
Exp/Cntr=0.3,0.1

Type RM Length L Ch R = 1 ,15918   ,414,414,414
BEGIN DESCRIPTION:
MILL TRIBUTARY 16 30.0
END DESCRIPTION:
XS GIS Cut Line= 3
      2332439.62     13789842.72        2331825.       13789575.
      2331624.96     13789524.99
#Sta/Elev= 30
  4329.6  605.73  4436.6  600.06  4460.8   597.9    4531  593.65  4588.9  588.95
  4606.9  588.27  4629.1  586.14  4672.8  583.08  4688.1  582.61  4705.5  581.27
  4716.9  581.19  4727.3  580.14  4825.5  577.06  4839.5  575.51  4857.5  577.34
    4880     577  4915.3   575.3  4938.7  575.84  4967.6  575.38  4985.6  575.94
  4995.3  572.94  4995.5  572.44    4999  572.44  4999.3  572.94  5002.6  572.94
  5010.3   575.6  5030.9   576.7  5082.5  577.45    5183  583.57  5206.2  584.52
#Mann= 3 ,-1 , 0
  4329.6     .12       0  4995.3     .05       0  4999.3     .12       0
Bank Sta=4995.3,4999.3
XS Rating Curve= 0 ,0
Exp/Cntr=0.3,0.1

Type RM Length L Ch R = 1 ,15504   ,538,538,538
BEGIN DESCRIPTION:
MILL TRIBUTARY 16 29.0
END DESCRIPTION:
XS GIS Cut Line= 3
      2332275.02     13789575.02        2331975.       13789275.
      2331675.02     13789374.99
#Sta/Elev= 30
  4580.1  587.56  4608.4  586.43  4664.2  583.07  4735.7  579.27  4774.1  577.86
  4820.5  576.15  4848.8  575.45    4863  575.59  4877.1  574.76  4891.3  574.32
  4905.4  574.98  4933.7  574.76    4962   573.4  4974.1  570.89  4974.4  570.39
  4977.9  570.39  4978.1  570.89  5000.9  573.37    5036  572.56  5046.6  572.95
  5057.1  572.42  5078.2  572.29  5109.8  573.16  5141.4  574.34    5152  574.98
  5215.2  576.71  5246.8  578.36  5299.5  580.16  5306.5  580.62  5320.6  581.48
#Mann= 6 ,-1 , 0
  4580.1     .12       0  4664.2     .07       0  4774.1     .12       0
  4974.1     .05       0  4978.1     .12       0  5306.5     .07       0
Bank Sta=4974.1,4978.1
XS Rating Curve= 0 ,0
Exp/Cntr=0.3,0.1

Type RM Length L Ch R = 1 ,14966   ,669,669,669
BEGIN DESCRIPTION:
B19503
END DESCRIPTION:
XS GIS Cut Line= 3
      2332585.43     13789030.21      2331741.68     13788863.54
      2331200.03     13788941.66
#Sta/Elev= 30
  4427.2  590.32  4611.1  581.43  4630.5   579.2  4635.6   579.8  4651.9  577.95
  4733.1  573.69  4738.2  574.16  4753.8     573  4784.4  573.05  4906.7  570.78
  4978.1  570.01  4999.7  570.48  5006.6  566.77  5006.9  566.27  5010.6  566.77
  5018.8  566.97    5029   569.4  5051.9  569.12  5090.2  569.03  5120.8  571.01
  5161.5  570.19  5256.2  571.53  5364.7   575.3    5395  577.21  5406.4  576.83
    5486  578.61  5597.1  581.78  5641.6   583.9  5809.3  589.11  5834.5  589.17
#Mann= 5 ,-1 , 0
  4427.2     .07       0  5006.6     .05       0  5010.6     .07       0
  5051.9     .12       0  5641.6     .05       0
Bank Sta=5006.6,5010.6
XS Rating Curve= 0 ,0
Exp/Cntr=0.3,0.1

Type RM Length L Ch R = 1 ,14297   ,292,292,292
BEGIN DESCRIPTION:
B19502
END DESCRIPTION:
XS GIS Cut Line= 3
      2332606.21     13788426.04      2332033.34     13788368.75
      2331335.44      13788717.7
#Sta/Elev= 30
  4376.5  578.78  4535.6   577.2  4657.7  574.55  4709.4  573.81  4842.1  567.23
  4898.3  566.51  4898.6  566.01  4902.3  566.51  4920.4  568.21  4937.6  571.71
  4939.8  571.13  4942.6   570.4  4955.5   571.5  5006.3  571.63  5039.3  570.55
  5044.9  569.39  5061.7  570.47  5067.3  569.63  5084.1   570.8  5089.7  570.05
  5124.2   571.2  5134.4  571.74  5151.1  569.09  5156.7  570.08  5162.8  568.92
  5173.5  568.72  5307.7  570.29  5486.6  574.15  5632.4  579.59  5732.5  581.95
#Mann= 6 ,-1 , 0
  4376.5     .12       0  4657.7     .07       0  4898.3     .05       0
  4902.3     .07       0  4939.8     .12       0  5124.2     .07       0
Bank Sta=4898.3,4902.3
XS Rating Curve= 0 ,0
Exp/Cntr=0.3,0.1

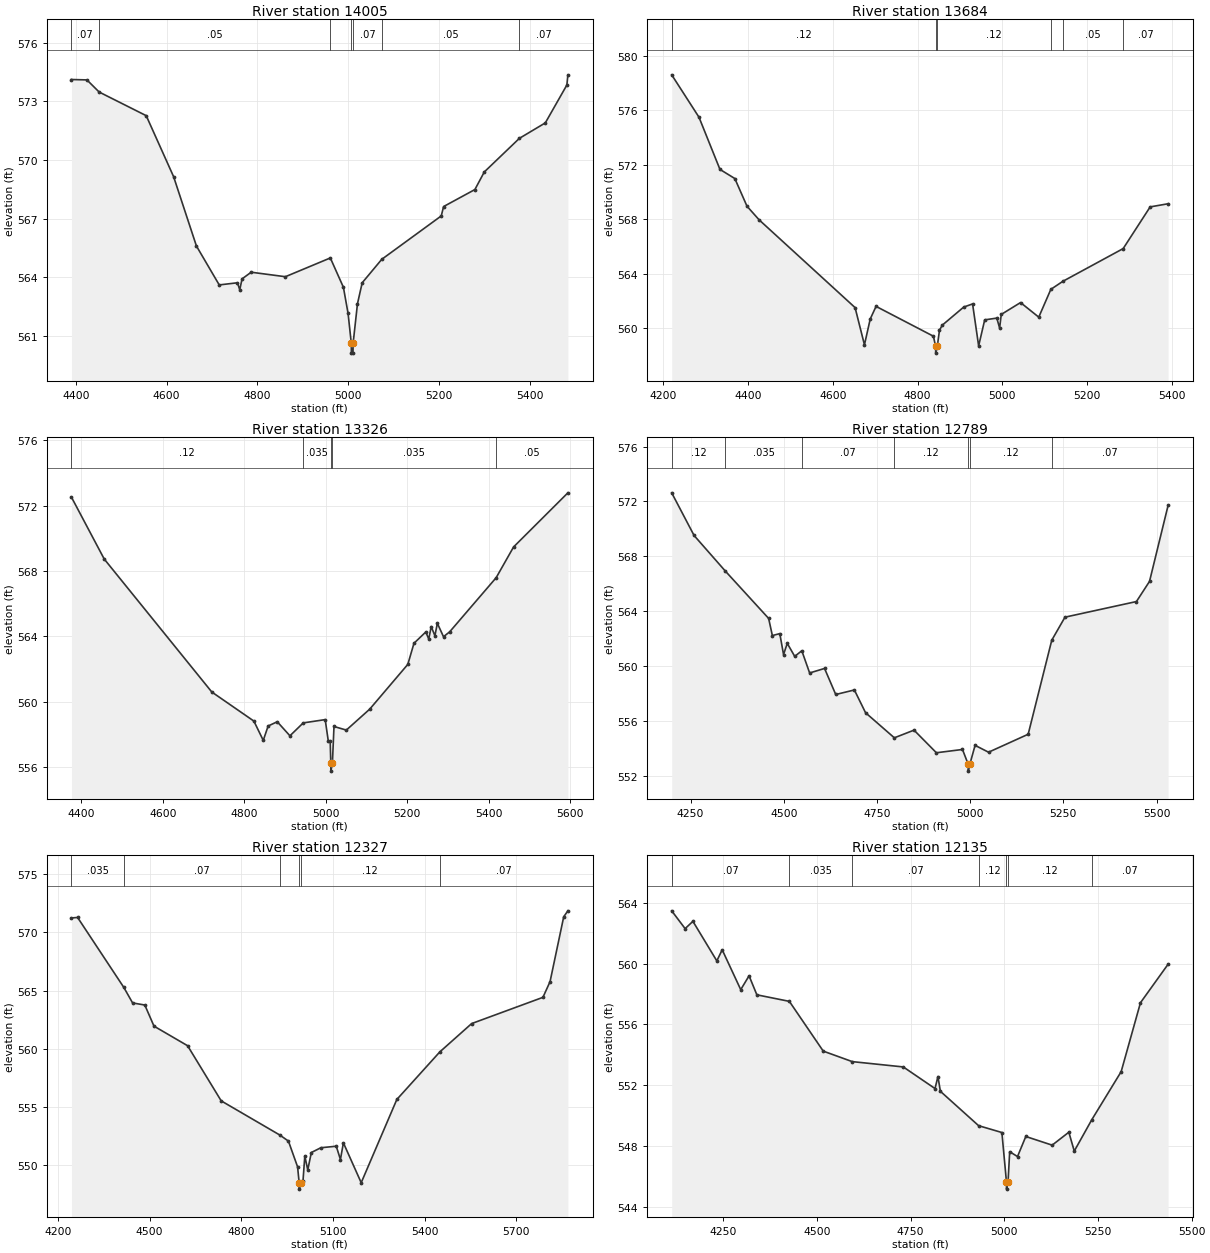
Type RM Length L Ch R = 1 ,14005   ,321,321,321
BEGIN DESCRIPTION:
MILL TRIBUTARY 16 27.0
END DESCRIPTION:
XS GIS Cut Line= 3
       2332418.8     13788196.88      2331897.93     13788144.79
      2331346.99     13788290.32
#Sta/Elev= 30
  4390.6  574.12  4424.6   574.1  4451.5  573.48  4555.2  572.27  4615.5  569.15
  4665.8   565.6    4716  563.61  4756.2  563.72  4761.2  563.36  4766.3  563.92
  4786.4  564.26  4861.7  564.03  4960.7  564.99  4989.5  563.49  4999.8  562.15
  5006.9  560.62  5007.1  560.12  5010.6  560.12  5010.9  560.62  5020.5  562.65
  5030.9  563.72    5074  564.92    5205  567.14  5210.2  567.62  5279.1  568.49
  5299.8  569.39  5377.1  571.11  5434.2   571.9  5481.7  573.84  5483.9  574.36
#Mann= 7 ,-1 , 0
  4390.6     .07       0  4451.5     .05       0  4960.7     .07       0
  5006.9     .05       0  5010.9     .07       0    5074     .05       0
  5377.1     .07       0
Bank Sta=5006.9,5010.9
XS Rating Curve= 0 ,0
Exp/Cntr=0.3,0.1

Type RM Length L Ch R = 1 ,13684   ,358,358,358
BEGIN DESCRIPTION:
MILL TRIBUTARY 16 26.0
END DESCRIPTION:
XS GIS Cut Line= 3
      2332324.99       13787375.        2331725.       13787875.
      2331425.02     13788124.98
#Sta/Elev= 30
  4219.5  578.61  4283.9   575.5  4333.4  571.67  4368.5     571  4397.2  568.97
  4425.8  567.97  4652.3  561.53  4674.4   558.8  4688.1   560.7  4701.8  561.62
  4837.2  559.43  4842.3  558.69  4842.6  558.19  4846.3  558.69  4851.5  559.87
    4858  560.24  4908.7  561.57  4929.6   561.8  4943.9  558.72  4958.2  560.63
  4986.8  560.76  4993.4  560.03  4997.3  561.03  5042.8   561.9  5085.8  560.83
  5114.3  562.87  5142.7  563.46    5285  565.86  5348.7  568.92    5391  569.15
#Mann= 6 ,-1 , 0
  4219.5     .12       0  4842.3     .05       0  4846.3     .12       0
  5114.3     .07       0  5142.7     .05       0    5285     .07       0
Bank Sta=4842.3,4846.3
XS Rating Curve= 0 ,0
Exp/Cntr=0.3,0.1

Type RM Length L Ch R = 1 ,13326   ,537,537,537
BEGIN DESCRIPTION:
MILL TRIBUTARY 16 25.0
END DESCRIPTION:
XS GIS Cut Line= 3
      2332174.97     13787275.01      2331621.89      13787587.5
       2331132.3     13787905.21
#Sta/Elev= 30
    4376  572.51  4456.4  568.73  4720.5   560.6  4823.9  558.82  4846.9  557.64
  4858.9  558.52  4881.3  558.78  4912.4  557.92  4945.1  558.71    4999  558.91
  5006.6   557.6  5011.3   557.6  5012.7  556.26  5012.9  555.76  5016.7  556.26
  5020.6  558.49  5050.9  558.27  5108.3  559.55  5201.9  562.29    5217  563.58
    5246  564.27  5253.3  563.84  5259.3   564.6  5268.4  564.04  5274.4   564.8
  5289.5  563.98  5304.7  564.28  5418.8  567.59  5461.6  569.47  5594.9  572.78
#Mann= 5 ,-1 , 0
    4376     .12       0  4945.1    .035       0  5012.7    .035       0
  5016.7    .035       0  5418.8     .05       0
Bank Sta=5012.7,5016.7
XS Rating Curve= 0 ,0
Exp/Cntr=0.3,0.1

Type RM Length L Ch R = 1 ,12789   ,462,462,462
BEGIN DESCRIPTION:
MILL TRIBUTARY 16 24.0
END DESCRIPTION:
XS GIS Cut Line= 3
      2332175.04       13787225.        2331375.       13787225.
      2330975.04     13787574.97
#Sta/Elev= 30
  4199.4  572.63  4259.4  569.52    4343  566.93  4459.4  563.47  4469.4  562.22
  4489.4  562.36  4499.4  560.83  4509.4  561.65  4529.4   560.7  4548.4  561.11
  4569.4  559.49  4609.4  559.82  4639.4  557.92  4689.4  558.25  4719.4  556.59
  4796.6  554.76  4849.4  555.32  4909.4  553.67  4979.4  553.91  4994.7  552.83
    4995  552.33  4999.1  552.83  5013.2  554.21  5049.3  553.71  5155.6  555.02
  5218.9  561.88  5254.3  563.56    5446   564.7  5481.1  566.17  5530.9  571.71
#Mann= 7 ,-1 , 0
  4199.4     .12       0    4343    .035       0  4548.4     .07       0
  4796.6     .12       0  4994.7     .05       0  4999.1     .12       0
  5218.9     .07       0
Bank Sta=4994.7,4999.1
XS Rating Curve= 0 ,0
Exp/Cntr=0.3,0.1

Type RM Length L Ch R = 1 ,12327   ,192,192,192
BEGIN DESCRIPTION:
MILL TRIBUTARY 16 23.0
END DESCRIPTION:
XS GIS Cut Line= 3
      2332074.98       13786775.        2331325.       13786775.
      2330875.01     13787524.98
#Sta/Elev= 30
  4244.6  571.23  4264.6  571.27  4415.9  565.27  4444.6  563.94  4484.6  563.76
  4514.6  561.95  4624.6  560.27  4734.6  555.54  4926.4  552.61  4954.6  552.09
  4984.6  549.88  4989.9  548.47  4990.2  547.97  4994.3  548.47  5002.3  548.67
  5008.2  550.81  5017.9  549.62  5029.6  551.11  5060.7  551.52  5111.2  551.65
  5124.8  550.51  5134.5  551.94  5192.8  548.52  5309.4  555.66  5450.1  559.74
  5554.3  562.17  5787.6  564.42  5810.9  565.77  5855.6  571.33  5869.2  571.84
#Mann= 6 ,-1 , 0
  4244.6    .035       0  4415.9     .07       0  4926.4     .12       0
  4989.9     .05       0  4994.3     .12       0  5450.1     .07       0
Bank Sta=4989.9,4994.3
XS Rating Curve= 0 ,0
Exp/Cntr=0.3,0.1

Type RM Length L Ch R = 1 ,12135   ,556,556,556
BEGIN DESCRIPTION:
MILL TRIBUTARY 16 22.0
END DESCRIPTION:
XS GIS Cut Line= 3
      2331724.98     13786025.03      2331059.39     13786827.08
      2330924.98     13787075.04
#Sta/Elev= 30
  4112.8  563.47  4148.6   562.3  4169.4  562.78  4233.2  560.18  4247.5  560.91
    4297  558.29  4319.2   559.2    4340  557.95  4426.7  557.52  4517.1  554.25
  4594.5  553.56  4730.7  553.21  4815.3  551.79  4823.1  552.58  4829.6  551.61
  4931.6  549.35  4993.7   548.9  5005.8  545.68  5006.1  545.18  5010.2  545.68
  5014.5  547.64  5035.4  547.32  5057.5  548.64  5127.8  548.07  5172.3  548.92
  5186.8  547.68  5233.5  549.74  5311.9   552.9  5363.4  557.43  5437.1  559.96
#Mann= 7 ,-1 , 0
  4112.8     .07       0  4426.7    .035       0  4594.5     .07       0
  4931.6     .12       0  5005.8     .05       0  5010.2     .12       0
  5233.5     .07       0
Bank Sta=5005.8,5010.2
XS Rating Curve= 0 ,0
Exp/Cntr=0.3,0.1

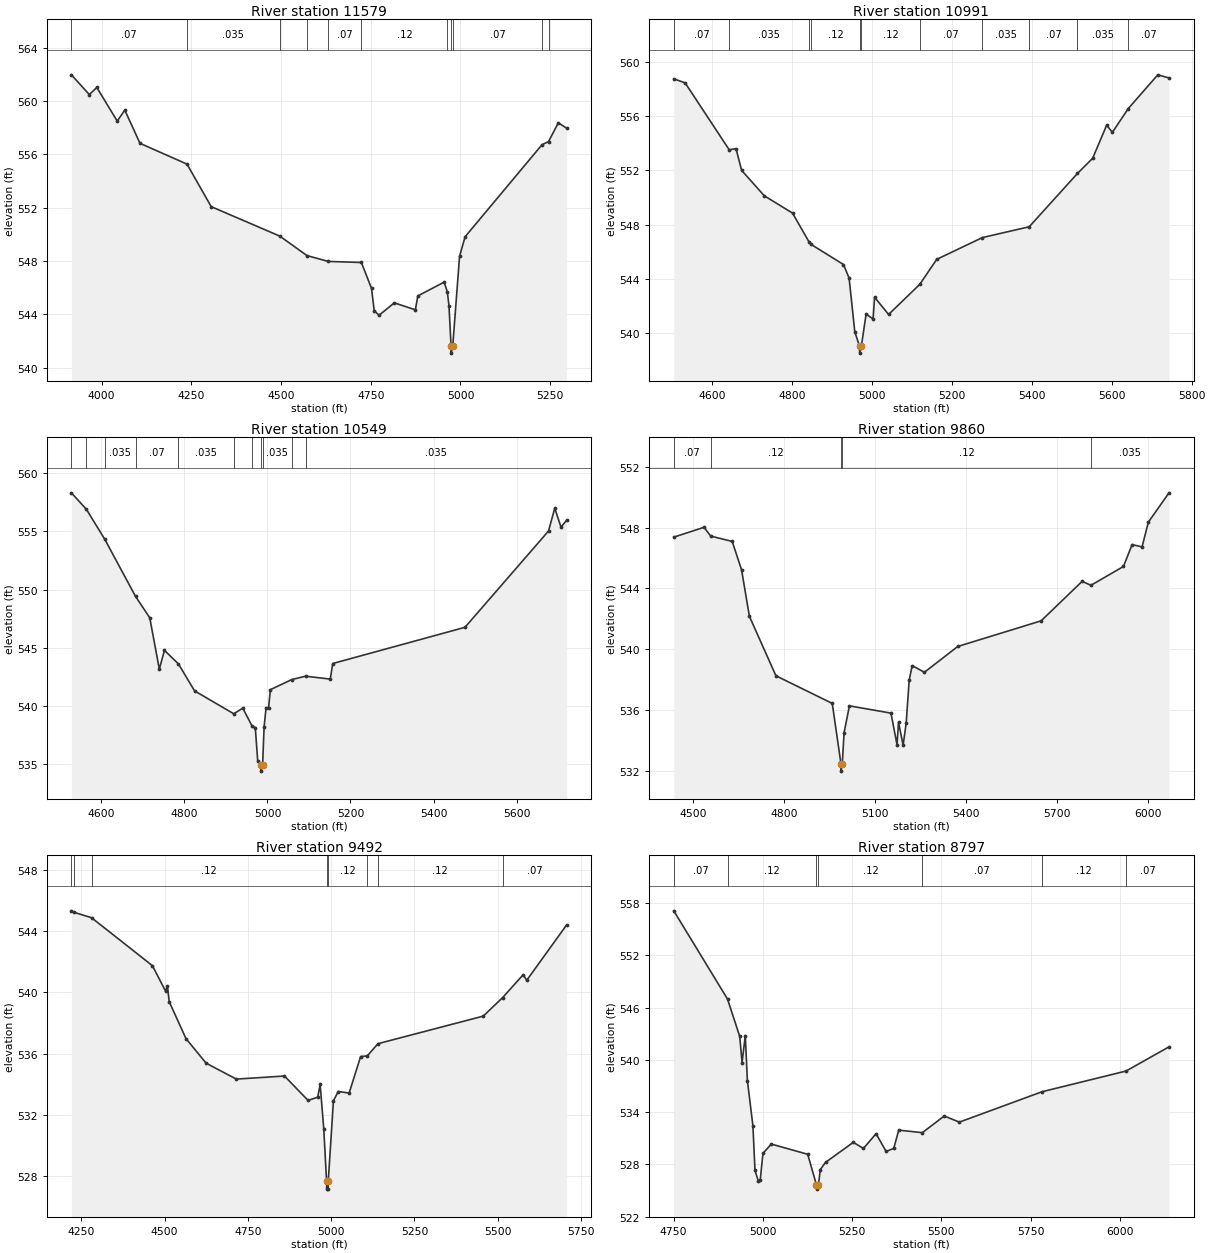
Type RM Length L Ch R = 1 ,11579   ,588,588,588
BEGIN DESCRIPTION:
MILL TRIBUTARY 16 21.0
END DESCRIPTION:
XS GIS Cut Line= 3
      2331606.25     13785926.05      2330918.76     13786535.42
        2330525.       13786775.
#Sta/Elev= 30
  3916.1  561.96  3965.9  560.48  3986.8  561.01  4043.7  558.49  4064.8  559.31
  4107.2  556.82  4238.1  555.26  4305.5  552.07  4496.6  549.86  4572.2   548.4
  4631.7  547.96  4723.9  547.88  4752.1  545.94  4759.6  544.27    4773  543.92
  4815.6  544.85  4874.3  544.33  4881.1  545.37  4954.7  546.41  4963.5  545.65
  4967.9  544.64  4973.8  541.58  4974.1  541.08  4978.3  541.58  4997.4  548.34
  5012.8  549.81  5227.2  556.72  5245.3  556.95  5272.5  558.36  5295.7  557.96
#Mann= 11 ,-1 , 0
  3916.1     .07       0  4238.1    .035       0  4496.6     .07       0
  4572.2    .035       0  4631.7     .07       0  4723.9     .12       0
  4963.5     .07       0  4973.8     .05       0  4978.3     .07       0
  5227.2    .035       0  5245.3     .07       0
Bank Sta=4973.8,4978.3
XS Rating Curve= 0 ,0
Exp/Cntr=0.3,0.1

Type RM Length L Ch R = 1 ,10991   ,442,442,442
BEGIN DESCRIPTION:
MILL TRIBUTARY 16 20.0
END DESCRIPTION:
XS GIS Cut Line= 3
      2331225.02     13785824.98        2330875.       13786175.
        2330375.       13786725.
#Sta/Elev= 30
    4505  558.77  4533.3  558.48  4643.6  553.53  4660.6  553.61  4674.7  552.01
  4731.3  550.13    4802  548.85  4843.2  546.72  4848.7  546.53  4929.3  545.05
  4943.4  544.05  4957.6  540.09  4969.5     539  4969.8   538.5    4974     539
  4985.9  541.38  5003.4  541.03  5007.1  542.63  5042.2  541.36    5120  543.58
  5162.5  545.43  5276.6  547.04  5393.8  547.84  5514.4  551.78  5552.4   552.9
  5587.5  555.35  5601.7  554.82  5641.6  556.58  5715.3  559.07  5743.3  558.84
#Mann= 11 ,-1 , 0
    4505     .07       0  4643.6    .035       0  4843.2     .07       0
  4848.7     .12       0  4969.5     .05       0    4974     .12       0
    5120     .07       0  5276.6    .035       0  5393.8     .07       0
  5514.4    .035       0  5641.6     .07       0
Bank Sta=4969.5,4974
XS Rating Curve= 0 ,0
Exp/Cntr=0.3,0.1

Type RM Length L Ch R = 1 ,10549   ,689,689,689
BEGIN DESCRIPTION:
MILL TRIBUTARY 16 19.0
END DESCRIPTION:
XS GIS Cut Line= 3
      2331025.04     13785624.97        2330625.       13785875.
      2330224.98     13786475.03
#Sta/Elev= 30
  4527.8  558.31  4563.9  556.89  4608.4   554.3  4682.2  549.41  4716.5  547.57
  4739.5  543.16  4751.9  544.77  4785.7   543.6  4824.4  541.29  4918.8  539.32
  4940.6   539.8  4963.1  538.26  4970.7  538.13  4976.6  535.25  4983.7  534.89
    4984  534.39  4988.3  534.89  4991.9  538.17  4996.6  539.81  5002.6  539.81
  5007.1  541.39  5058.5  542.26  5091.7  542.55  5151.3   542.3  5157.3  543.64
  5475.8  546.75  5677.1  555.03  5692.1  556.99  5707.1  555.36  5720.7  555.96
#Mann= 11 ,-1 , 0
  4527.8    .035       0  4563.9     .07       0  4608.4    .035       0
  4682.2     .07       0  4785.7    .035       0  4918.8     .07       0
  4963.1    .035       0  4983.7    .035       0  4988.3    .035       0
  5058.5     .07       0  5091.7    .035       0
Bank Sta=4983.7,4988.3
XS Rating Curve= 0 ,0
Exp/Cntr=0.3,0.1

Type RM Length L Ch R = 1 ,9860    ,368,368,368
BEGIN DESCRIPTION:
B19501
END DESCRIPTION:
XS GIS Cut Line= 4
      2330944.82     13785077.08       2330382.3       13785275.
      2330408.34     13785764.58      2330257.38     13786290.34
#Sta/Elev= 30
  4436.8  547.38  4536.7  548.03  4558.7  547.45  4629.6   547.1  4660.5  545.22
  4686.2  542.17  4773.8  538.25  4959.6  536.43  4988.2  532.47  4988.5  531.97
  4992.8  532.47  4998.5  534.49  5016.2  536.27  5153.3  535.79  5173.2  533.71
  5178.2  535.18  5193.4  533.68  5203.4  535.12  5213.4  537.97  5223.4  538.92
  5263.5  538.48  5373.6  540.18  5648.7  541.87  5783.9  544.47    5813  544.21
  5920.2  545.45  5948.7  546.89  5981.6  546.74  6002.4  548.37  6070.4   550.3
#Mann= 5 ,-1 , 0
  4436.8     .07       0  4558.7     .12       0  4988.2     .05       0
  4992.8     .12       0    5813    .035       0
Bank Sta=4988.2,4992.8
XS Rating Curve= 0 ,0
Exp/Cntr=0.3,0.1

Type RM Length L Ch R = 1 ,9492    ,695,695,695
BEGIN DESCRIPTION:
MILL TRIBUTARY 16 18.0
END DESCRIPTION:
XS GIS Cut Line= 3
      2330986.42     13785004.16      2330377.09     13784931.25
      2329575.02     13785274.99
#Sta/Elev= 30
  4220.4  545.32  4228.9  545.22  4280.8  544.87  4463.5  541.74  4503.4  540.06
  4508.4  540.43  4513.9  539.39  4564.3  536.98  4624.7  535.38  4715.3  534.34
  4859.9  534.54  4930.6  532.95  4959.6  533.16  4966.9  533.99  4977.8  531.08
  4986.2  527.66  4986.6  527.16  4990.8  527.16  4991.2  527.66  5006.8  532.93
  5021.3  533.53  5053.9  533.43  5088.4  535.81  5108.3  535.85  5140.3  536.65
  5456.5  538.45  5514.7  539.66  5576.2  541.15    5587  540.79  5706.7   544.4
#Mann= 8 ,-1 , 0
  4220.4     .12       0  4228.9     .07       0  4280.8     .12       0
  4986.2     .05       0  4991.2     .12       0  5108.3     .07       0
  5140.3     .12       0  5514.7     .07       0
Bank Sta=4986.2,4991.2
XS Rating Curve= 0 ,0
Exp/Cntr=0.3,0.1

Type RM Length L Ch R = 1 ,8797    ,514,514,514
BEGIN DESCRIPTION:
MILL TRIBUTARY 16 17.0
END DESCRIPTION:
XS GIS Cut Line= 3
      2330668.78     13784274.99      2330314.59     13784488.54
        2329625.       13785175.
#Sta/Elev= 30
  4750.6  557.11  4901.1  546.98  4935.3  542.69  4941.8   539.7  4950.8  542.79
  4956.7  537.62  4972.2  532.44    4978  527.32  4987.7  526.05  4992.7  526.23
  5000.2  529.26  5023.6  530.34  5125.6  529.17    5150  525.67  5150.4  525.17
  5155.6  525.67    5161  527.42  5175.5  528.24  5253.3  530.54  5281.6  529.84
    5317  531.53  5345.3  529.49  5366.5  529.85  5380.6  531.94  5446.6  531.65
  5507.9  533.56  5550.3  532.86  5781.9  536.35  6016.9  538.72  6137.2   541.5
#Mann= 7 ,-1 , 0
  4750.6     .07       0  4901.1     .12       0    5150     .05       0
  5155.6     .12       0  5446.6     .07       0  5781.9     .12       0
  6016.9     .07       0
Bank Sta=5150,5155.6
XS Rating Curve= 0 ,0
Exp/Cntr=0.3,0.1

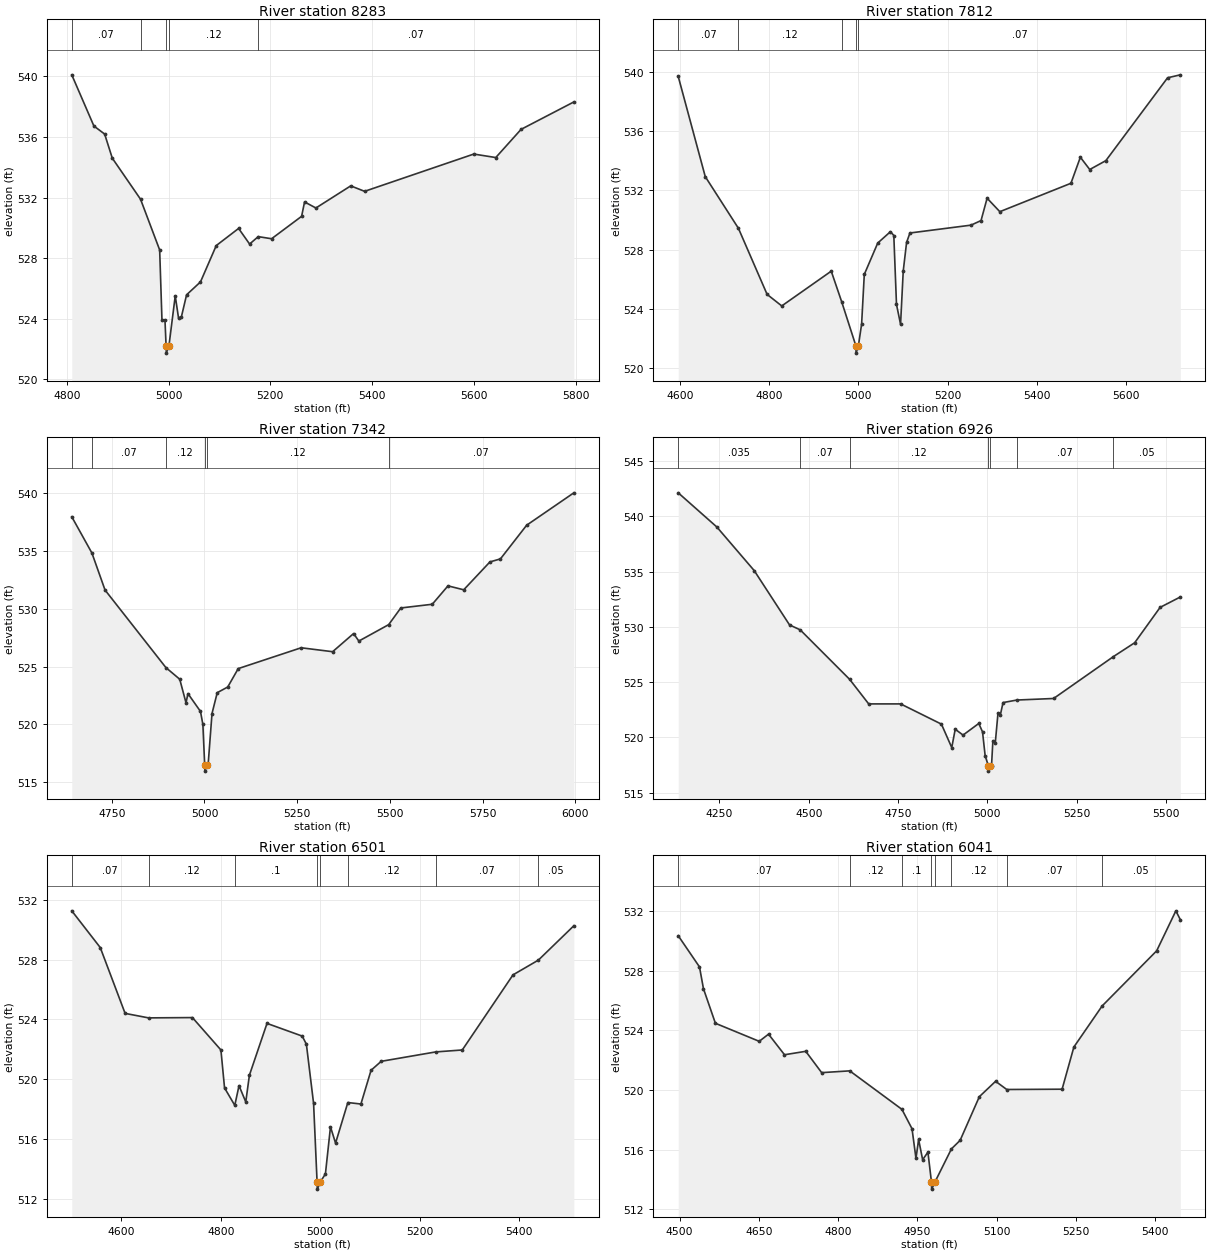
Type RM Length L Ch R = 1 ,8283    ,471,471,471
BEGIN DESCRIPTION:
MILL TRIBUTARY 16 16.0
END DESCRIPTION:
XS GIS Cut Line= 3
      2330324.97     13784175.02        2330175.       13784275.
      2329474.97     13784675.02
#Sta/Elev= 30
  4809.8  540.11  4853.3  536.73  4874.4   536.2  4889.4  534.61  4944.9   531.9
  4982.5  528.55    4987  523.94  4992.9  523.94  4995.1  522.24  4995.6  521.74
  5000.8  522.24  5013.1  525.52  5019.6  524.05  5025.3  524.15  5035.4  525.59
  5062.7  526.44  5093.7  528.84  5137.6  529.97  5159.2  528.94  5176.2  529.43
  5202.4  529.29  5261.4  530.77  5267.2  531.72  5289.5  531.32  5357.9  532.78
  5385.2  532.42  5599.7  534.88  5642.9  534.65  5692.6  536.51  5796.3  538.32
#Mann= 5 ,-1 , 0
  4809.8     .07       0  4944.9     .12       0  4995.1     .05       0
  5000.8     .12       0  5176.2     .07       0
Bank Sta=4995.1,5000.8
XS Rating Curve= 0 ,0
Exp/Cntr=0.3,0.1

Type RM Length L Ch R = 1 ,7812    ,470,470,470
BEGIN DESCRIPTION:
MILL TRIBUTARY 16 15.0
END DESCRIPTION:
XS GIS Cut Line= 3
        2330225.       13783925.        2329825.       13783975.
      2329225.02     13784374.99
#Sta/Elev= 30
  4596.6   539.7  4657.1  532.93  4731.3  529.44  4795.6  524.97  4828.4  524.19
  4939.2  526.54  4962.7  524.46  4994.3   521.5  4994.8     521    5000   521.5
  5007.2  522.96  5013.2  526.32  5043.3  528.44  5071.8  529.21  5079.3  528.95
  5085.3  524.29  5094.4  522.95  5100.4  526.55  5107.9  528.48  5115.4  529.12
  5252.1  529.65  5274.6  529.96  5288.2  531.47  5316.7  530.56  5475.9  532.48
    5497  534.24    5518  533.41  5554.1  534.01  5692.3  539.61  5720.8  539.81
#Mann= 5 ,-1 , 0
  4596.6     .07       0  4731.3     .12       0  4962.7     .07       0
  4994.3     .05       0    5000     .07       0
Bank Sta=4994.3,5000
XS Rating Curve= 0 ,0
Exp/Cntr=0.3,0.1

Type RM Length L Ch R = 1 ,7342    ,416,416,416
BEGIN DESCRIPTION:
MILL TRIBUTARY 16 14.0
END DESCRIPTION:
XS GIS Cut Line= 3
      2330175.04     13783675.01        2329825.       13783575.
        2329125.       13784275.
#Sta/Elev= 30
  4642.1  537.94  4696.4  534.81  4731.8  531.61  4895.9  524.91  4933.3   523.9
  4950.2  521.86  4955.4  522.66  4989.2  521.12  4995.7  519.99  5000.6  516.46
  5001.1  515.96  5006.4  516.46  5009.7  516.46  5020.3  520.94  5034.4  522.74
  5062.7  523.23    5091  524.82  5260.7  526.62  5345.6  526.28  5402.1  527.85
  5416.3   527.2  5496.8  528.62  5529.4  530.06  5614.3  530.38  5656.7  531.97
  5699.1  531.63  5769.8  534.04  5798.1   534.3  5868.8  537.21  5996.1  540.01
#Mann= 6 ,-1 , 0
  4642.1    .035       0  4696.4     .07       0  4895.9     .12       0
  5000.6     .05       0  5006.4     .12       0  5496.8     .07       0
Bank Sta=5000.6,5006.4
XS Rating Curve= 0 ,0
Exp/Cntr=0.3,0.1

Type RM Length L Ch R = 1 ,6926    ,425,425,425
BEGIN DESCRIPTION:
MILL TRIBUTARY 16 13.0
END DESCRIPTION:
XS GIS Cut Line= 3
      2330375.04     13783625.02        2329575.       13783275.
      2329174.97     13782924.98
#Sta/Elev= 30
    4135  542.12    4243  539.03  4347.5  535.09  4446.5  530.17  4476.2  529.73
  4614.6  525.25  4667.9  523.03  4757.2  523.03  4871.4   521.2  4900.3  519.08
    4910  520.74  4931.9  520.21  4975.9  521.26  4986.4   520.5  4993.8  518.33
  5002.6  517.45  5003.1  516.95  5008.4  517.45  5011.6  517.45  5015.4   519.7
    5022  519.48  5029.6  522.17  5036.3  522.04  5043.8  523.15  5082.7  523.38
  5185.3  523.52  5352.7  527.31  5412.1  528.56  5483.3  531.76  5539.8   532.7
#Mann= 7 ,-1 , 0
    4135    .035       0  4476.2     .07       0  4614.6     .12       0
  5002.6     .05       0  5008.4     .12       0  5082.7     .07       0
  5352.7     .05       0
Bank Sta=5002.6,5008.4
XS Rating Curve= 0 ,0
Exp/Cntr=0.3,0.1

Type RM Length L Ch R = 1 ,6501    ,460,460,460
BEGIN DESCRIPTION:
MILL TRIBUTARY 16 12.0
END DESCRIPTION:
XS GIS Cut Line= 3
      2330174.99     13782725.01        2329775.       13783025.
      2329274.99       13782925.
#Sta/Elev= 30
  4500.3  531.27  4557.6  528.81  4607.6   524.4  4654.7   524.1    4743  524.12
  4800.3  521.95  4807.6  519.41  4828.2  518.24  4836.7  519.56  4850.3  518.47
  4857.6  520.26    4893  523.73  4963.8  522.88  4972.2  522.34  4986.7  518.37
  4993.7  513.13  4994.2  512.63  5000.6  513.13  5010.5  513.65  5020.7   516.8
  5030.9  515.71  5055.6  518.43  5081.9  518.33  5102.3  520.59  5122.7  521.19
  5232.4  521.82  5285.8  521.95  5387.8  526.98  5438.9  527.97  5510.2  530.27
#Mann= 8 ,-1 , 0
  4500.3     .07       0  4654.7     .12       0  4828.2      .1       0
  4993.7     .05       0  5000.6      .1       0  5055.6     .12       0
  5232.4     .07       0  5438.9     .05       0
Bank Sta=4993.7,5000.6
XS Rating Curve= 0 ,0
Exp/Cntr=0.3,0.1

Type RM Length L Ch R = 1 ,6041    ,458,458,458
BEGIN DESCRIPTION:
MILL TRIBUTARY 16 11.0
END DESCRIPTION:
XS GIS Cut Line= 3
      2330124.99       13782675.        2329625.       13782625.
      2329224.99       13782825.
#Sta/Elev= 30
  4497.6  530.34  4537.8  528.25  4545.3  526.79  4567.9  524.47  4650.8  523.26
  4668.4  523.74  4698.6  522.36  4738.8  522.59  4768.9  521.16    4822  521.28
  4920.7   518.7  4939.8   517.4  4947.3  515.41  4952.3  516.68  4959.9  515.32
  4969.9  515.83  4976.5  513.85    4977  513.35  4983.5  513.85  5014.4  516.05
  5030.8  516.62  5067.2  519.55  5097.9  520.58    5119  520.03  5223.7  520.05
    5246  522.88  5299.4  525.63  5402.6  529.33  5438.9  532.01  5447.3  531.42
#Mann= 8 ,-1 , 0
  4497.6     .07       0    4822     .12       0  4920.7      .1       0
  4976.5     .05       0  4983.5      .1       0  5014.4     .12       0
    5119     .07       0  5299.4     .05       0
Bank Sta=4976.5,4983.5
XS Rating Curve= 0 ,0
Exp/Cntr=0.3,0.1