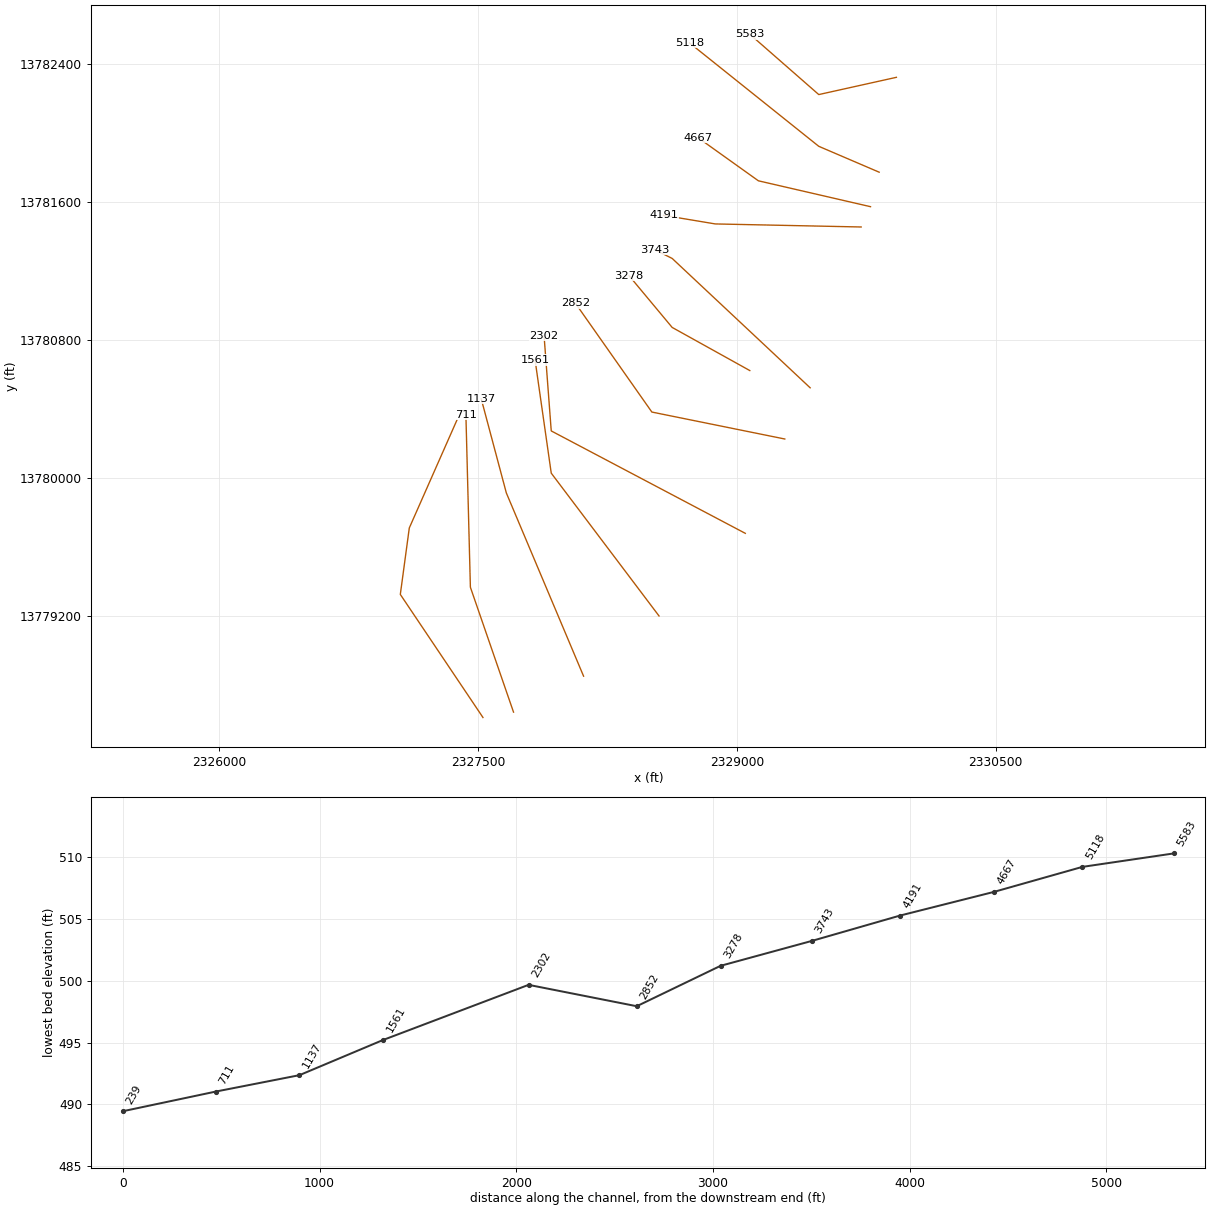
HEC-RAS study MILL TRIBUTARY 16.prj: MILL TRIBUTARY 16 Base Level Engineering

--- MILL TRIBUTARY 16.g01 (geometry) --- (continued)

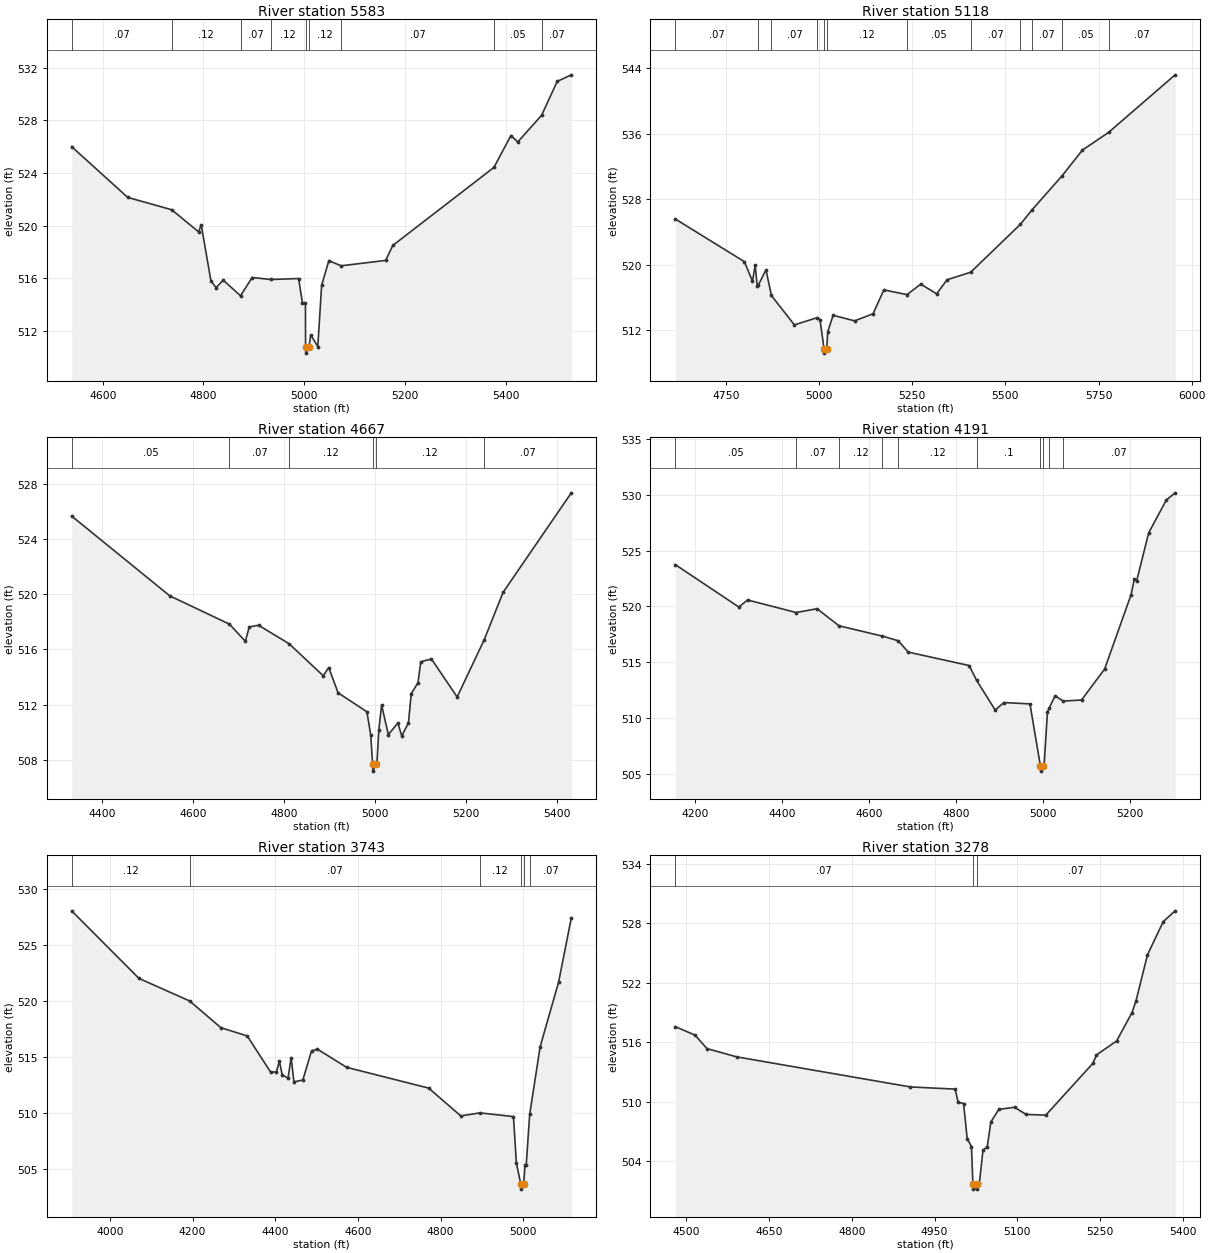
Type RM Length L Ch R = 1 ,5583    ,465,465,465
BEGIN DESCRIPTION:
MILL TRIBUTARY 16 10.0
END DESCRIPTION:
XS GIS Cut Line= 3
      2329924.96     13782324.99        2329475.       13782225.
      2329075.03     13782574.97
#Sta/Elev= 30
  4538.3  526.01  4649.7  522.15  4737.1  521.21  4790.5  519.53  4795.6  520.07
  4814.8  515.83  4825.1  515.28  4839.2  515.86  4873.7  514.67  4896.8  516.06
  4933.3  515.91    4989  515.98  4996.7  514.14  5002.6  514.14  5002.9  510.81
  5003.4  510.31  5009.9  510.81    5013   511.7  5027.2  510.81  5034.8  515.47
  5049.1  517.34  5073.6  516.95    5162  517.36  5176.2   518.5    5377  524.43
  5410.7  526.85  5424.4  526.37  5471.6  528.39  5502.7  530.97  5530.7  531.47
#Mann= 9 ,-1 , 0
  4538.3     .07       0  4737.1     .12       0  4873.7     .07       0
  4933.3     .12       0  5002.9     .05       0  5009.9     .12       0
  5073.6     .07       0    5377     .05       0  5471.6     .07       0
Bank Sta=5002.9,5009.9
XS Rating Curve= 0 ,0
Exp/Cntr=0.3,0.1

Type RM Length L Ch R = 1 ,5118    ,451,451,451
BEGIN DESCRIPTION:
MILL TRIBUTARY 16 9.0
END DESCRIPTION:
XS GIS Cut Line= 3
      2329825.02     13781774.99        2329475.       13781925.
      2328724.98     13782525.01
#Sta/Elev= 30
  4614.4  525.59  4799.4  520.39  4821.1  518.01  4828.4  519.97  4833.8  517.42
  4836.5  517.51  4857.4  519.39  4871.8  516.26  4933.6  512.67  4995.5  513.56
  5002.4   513.3  5013.3  509.72  5013.8  509.22  5020.4  509.72  5023.2  511.84
  5037.6  513.84  5095.3  513.16  5144.9  514.03  5173.7  516.94    5236  516.37
  5272.9  517.65  5315.4  516.46  5343.4  518.18  5406.8   519.1    5540  524.94
  5571.8  526.73  5652.8  530.91  5706.8  534.02  5776.8  536.17  5955.7  543.21
#Mann= 12 ,-1 , 0
  4614.4     .07       0  4836.5     .12       0  4871.8     .07       0
  4995.5     .12       0  5013.3     .05       0  5020.4     .12       0
    5236     .05       0  5406.8     .07       0    5540     .05       0
  5571.8     .07       0  5652.8     .05       0  5776.8     .07       0
Bank Sta=5013.3,5020.4
XS Rating Curve= 0 ,0
Exp/Cntr=0.3,0.1

Type RM Length L Ch R = 1 ,4667    ,476,476,476
BEGIN DESCRIPTION:
MILL TRIBUTARY 16 8.0
END DESCRIPTION:
XS GIS Cut Line= 3
      2329775.01       13781575.        2329125.       13781725.
      2328775.01     13781974.99
#Sta/Elev= 30
  4333.5  525.66    4549  519.88  4680.1  517.83  4714.9  516.59  4723.5  517.63
    4744  517.75  4811.2  516.41    4886  514.09    4898  514.69  4918.5  512.86
  4981.8  511.49  4990.3  509.79  4994.4  507.69  4994.9  507.19  5001.6  507.69
  5003.7  507.69    5008  510.17  5014.1  511.98  5028.9  509.83  5049.8  510.68
  5058.4  509.73  5073.1  510.69  5079.2   512.8    5094  513.59  5100.1  515.11
  5123.5  515.31    5180  512.56  5239.5  516.71  5280.8  520.13  5430.7  527.34
#Mann= 6 ,-1 , 0
  4333.5     .05       0  4680.1     .07       0  4811.2     .12       0
  4994.4     .05       0  5001.6     .12       0  5239.5     .07       0
Bank Sta=4994.4,5001.6
XS Rating Curve= 0 ,0
Exp/Cntr=0.3,0.1

Type RM Length L Ch R = 1 ,4191    ,448,448,448
BEGIN DESCRIPTION:
MILL TRIBUTARY 16 7.0
END DESCRIPTION:
XS GIS Cut Line= 3
      2329720.83     13781457.29        2328875.       13781475.
      2328574.95     13781525.01
#Sta/Elev= 30
    4154  523.73  4299.9  519.95  4319.9  520.58    4432  519.46  4479.9   519.8
  4530.6  518.27  4629.2  517.36  4666.5  516.94  4689.9  515.92    4830  514.72
  4847.3  513.39    4890  510.74    4910  511.41    4970  511.29  4993.9  505.78
  4994.4  505.28  5001.1  505.78  5002.5  505.78  5010.2  510.53  5013.9  510.89
  5027.9  512.02  5046.3  511.54  5088.7  511.64  5141.9  514.41  5202.8  521.06
  5210.4  522.48  5215.4  522.26  5243.3  526.58  5283.9  529.52  5304.2  530.16
#Mann= 10 ,-1 , 0
    4154     .05       0    4432     .07       0  4530.6     .12       0
  4629.2     .07       0  4666.5     .12       0  4847.3      .1       0
  4993.9     .05       0  5001.1      .1       0  5013.9     .12       0
  5046.3     .07       0
Bank Sta=4993.9,5001.1
XS Rating Curve= 0 ,0
Exp/Cntr=0.3,0.1

Type RM Length L Ch R = 1 ,3743    ,465,465,465
BEGIN DESCRIPTION:
MILL TRIBUTARY 16 6.0
END DESCRIPTION:
XS GIS Cut Line= 3
      2329425.04     13780524.97        2328625.       13781275.
      2328525.03     13781324.98
#Sta/Elev= 30
  3907.7  528.05  4070.6  522.02  4193.1  520.01  4268.5  517.63  4332.4  516.89
  4388.6  513.68  4402.8  513.67  4410.1  514.64    4417  513.41  4431.1  513.14
  4438.5  514.96  4445.3   512.8  4466.8  512.96  4487.8  515.56    4502  515.71
  4572.8  514.09  4771.1  512.24  4848.8  509.76  4894.9  510.03  4976.2   509.7
  4983.1  505.59  4993.6  503.73  4994.1  503.23  5000.9  503.73  5004.3  505.41
  5007.1  505.41  5015.4   509.9  5040.7  515.93  5085.4   521.7  5116.1  527.43
#Mann= 6 ,-1 , 0
  3907.7     .12       0  4193.1     .07       0  4894.9     .12       0
  4993.6     .05       0  5000.9     .12       0  5015.4     .07       0
Bank Sta=4993.6,5000.9
XS Rating Curve= 0 ,0
Exp/Cntr=0.3,0.1

Type RM Length L Ch R = 1 ,3278    ,426,426,426
BEGIN DESCRIPTION:
MILL TRIBUTARY 16 5.0
END DESCRIPTION:
XS GIS Cut Line= 3
      2329075.03     13780624.98        2328625.       13780875.
      2328375.02     13781174.98
#Sta/Elev= 30
  4480.5  517.58    4516  516.73  4537.7  515.37  4591.5  514.54  4906.1  511.51
  4987.3  511.29  4992.5  509.97  5002.5  509.84    5009  506.31  5016.8   505.5
  5019.4  501.71  5019.9  501.21  5026.7  501.21  5027.2  501.71  5031.1  501.81
  5037.6  505.11  5045.4   505.5  5051.9  507.98  5066.3  509.25  5094.9  509.46
  5115.7  508.74  5151.5  508.67  5236.8  513.89  5243.3  514.74  5279.7  516.14
  5307.7  519.01  5314.9  520.19  5335.7  524.83  5364.3  528.18  5385.8  529.26
#Mann= 3 ,-1 , 0
  4480.5     .07       0  5019.4     .05       0  5027.2     .07       0
Bank Sta=5019.4,5027.2
XS Rating Curve= 0 ,0
Exp/Cntr=0.3,0.1

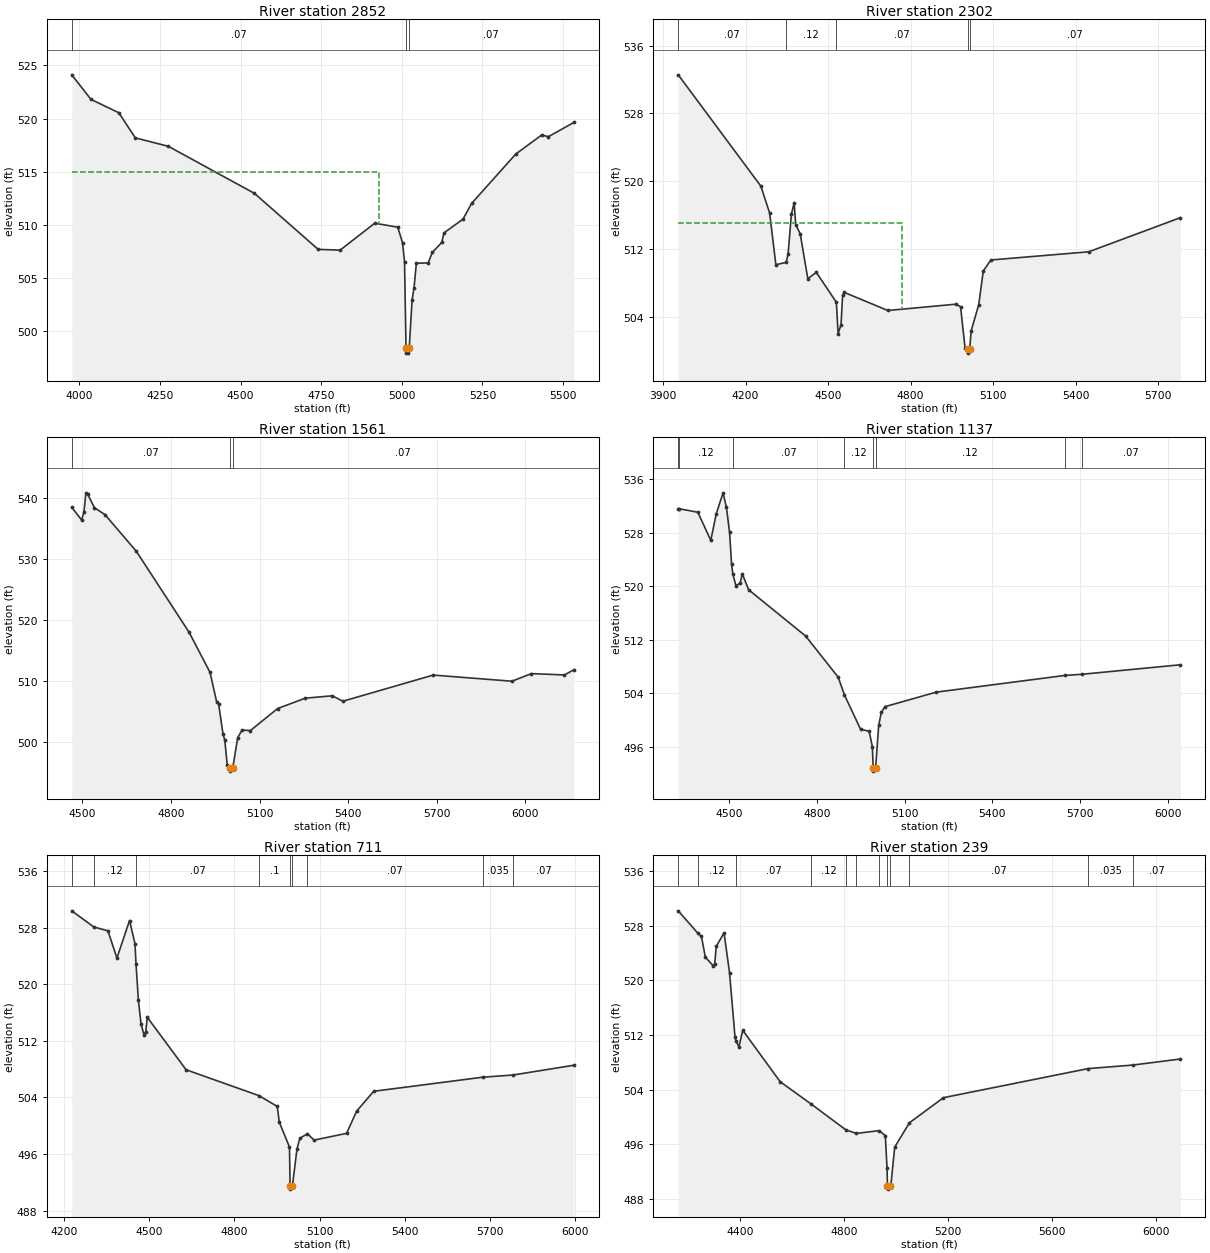
Type RM Length L Ch R = 1 ,2852    ,550,550,550
BEGIN DESCRIPTION:
B19500
END DESCRIPTION:
XS GIS Cut Line= 3
       2329278.1     13780228.13       2328507.3     13780384.38
      2328064.62     13781014.55
#Sta/Elev= 30
  3976.8  524.12  4036.3  521.81  4122.8  520.55  4173.8  518.19  4275.9   517.4
  4543.1  512.97  4740.7   507.7  4808.8  507.63    4916  510.16  4987.4  509.79
  5002.2  508.33  5008.5  506.54  5013.1  498.44  5013.6  497.94  5020.4  497.94
  5020.9  498.44  5023.2   498.5  5031.9  502.95    5038  504.08  5045.1  506.39
  5081.8  506.43  5094.6  507.41  5123.9  508.35  5130.7  509.25  5189.6  510.54
  5216.6  512.03  5353.4  516.67  5433.6  518.46  5454.5   518.3  5533.4  519.64
#Mann= 3 ,-1 , 0
  3976.8     .07       0  5013.1     .05       0  5020.9     .07       0
#XS Ineff= 2 , 0
       0    4930     515               0
Permanent Ineff=
       F       F
Bank Sta=5013.1,5020.9
XS Rating Curve= 0 ,0
Exp/Cntr=0.3,0.1

Type RM Length L Ch R = 1 ,2302    ,741,741,741
BEGIN DESCRIPTION:
B19499
END DESCRIPTION:
XS GIS Cut Line= 3
      2329048.97     13779681.25      2327923.97       13780275.
       2327882.3     13780827.06
#Sta/Elev= 30
  3955.1  532.57  4255.8   519.4  4287.5  516.22  4310.1  510.12  4347.8   510.4
  4354.6   511.4  4366.6   516.1  4376.6  517.44  4382.3  514.86  4398.6  513.78
  4426.3  508.47  4457.1  509.22  4530.2  505.68  4536.4  501.98  4547.1  503.03
  4552.8  506.53  4558.9  506.85  4717.2  504.71  4965.9  505.46  4981.8  505.14
  4998.2  500.23  5007.2  500.17  5007.7  499.67  5015.1  500.17  5020.2   502.3
  5047.9  505.41  5064.3  509.38  5091.9  510.68  5447.8  511.65  5780.8  515.68
#Mann= 5 ,-1 , 0
  3955.1     .07       0  4347.8     .12       0  4530.2     .07       0
  5007.2     .05       0  5015.1     .07       0
#XS Ineff= 2 , 0
       0    4770     515               0
Permanent Ineff=
       F       F
Bank Sta=5007.2,5015.1
XS Rating Curve= 0 ,0
Exp/Cntr=0.3,0.1

Type RM Length L Ch R = 1 ,1561    ,424,424,424
BEGIN DESCRIPTION:
B19498
END DESCRIPTION:
XS GIS Cut Line= 3
      2328548.96      13779202.1      2327923.97     13780030.21
      2327830.22     13780686.46
#Sta/Elev= 30
  4463.7  538.48  4496.9  536.41  4504.9  537.66  4511.5  540.86  4517.7  540.61
  4540.6  538.41    4576  537.29  4682.2  531.28  4861.2  517.97    4932   511.4
  4954.8  506.48  4961.1   506.2  4975.7  501.35  4981.9  500.29  4990.2  496.25
  5000.6   495.7  5001.1   495.2  5008.9   495.7  5025.6  500.68  5040.2  501.93
  5068.7  501.86  5160.9  505.47  5254.6  507.17  5346.2  507.56  5381.9  506.67
  5687.9  510.96  5954.5  509.95  6020.2   511.2  6132.3  510.98  6164.1  511.83
#Mann= 3 ,-1 , 0
  4463.7     .07       0  5000.6     .05       0  5008.9     .07       0
Bank Sta=5000.6,5008.9
XS Rating Curve= 0 ,0
Exp/Cntr=0.3,0.1

Type RM Length L Ch R = 1 ,1137    ,426,426,426
BEGIN DESCRIPTION:
B19497
END DESCRIPTION:
XS GIS Cut Line= 3
      2328111.46     13778853.14      2327663.55     13779915.63
      2327518.06     13780461.22
#Sta/Elev= 30
  4325.2   531.6  4326.9   531.6  4392.3  531.07  4436.6  526.86  4454.8  530.76
  4478.6  533.97    4490   531.8  4500.9  528.04  4507.7  523.29    4512  521.81
  4522.6  520.09  4536.9  520.45  4544.3  521.85    4566  519.48  4761.2  512.55
  4872.4  506.41  4893.7  503.77    4949  498.62  4978.4  498.32  4989.2  496.04
  4992.3  492.86  4992.8  492.36  5000.6  492.86  5010.9  499.19  5020.2  501.17
  5032.6     502  5207.9  504.17  5648.4  506.67  5706.2  506.84  6042.9  508.26
#Mann= 8 ,-1 , 0
  4325.2     .05       0  4326.9     .12       0    4512     .07       0
  4893.7     .12       0  4992.3     .05       0  5000.6     .12       0
  5648.4    .035       0  5706.2     .07       0
Bank Sta=4992.3,5000.6
XS Rating Curve= 0 ,0
Exp/Cntr=0.3,0.1

Type RM Length L Ch R = 1 ,711     ,472,472,472
BEGIN DESCRIPTION:
B19496
END DESCRIPTION:
XS GIS Cut Line= 3
      2327705.23     13778644.76      2327455.22     13779368.75
      2327429.18     13780368.77
#Sta/Elev= 30
    4228  530.39  4305.3  528.11  4355.2  527.56  4386.9  523.71  4431.2  529.02
  4450.4  525.74  4454.1  522.81  4462.4  517.73  4471.6   514.4  4482.2  512.83
  4488.3  513.31  4493.6  515.33  4630.3  507.91  4886.1  504.26  4950.8  502.73
  4958.2  500.49  4993.9  496.98    4996  491.53  4996.5  491.03  5004.4  491.53
  5020.2  496.69  5030.2  498.21  5057.2  498.87  5080.2  497.96  5194.8  498.92
  5230.3  502.07  5290.3  504.87  5674.1  506.86  5780.4  507.17  5994.3  508.55
#Mann= 9 ,-1 , 0
    4228     .05       0  4305.3     .12       0  4454.1     .07       0
  4886.1      .1       0    4996     .05       0  5004.4      .1       0
  5057.2     .07       0  5674.1    .035       0  5780.4     .07       0
Bank Sta=4996,5004.4
XS Rating Curve= 0 ,0
Exp/Cntr=0.3,0.1

Type RM Length L Ch R = 1 ,239     ,0,0,0
BEGIN DESCRIPTION:
B19495
END DESCRIPTION:
XS GIS Cut Line= 4
      2327528.16     13778613.51      2327048.97     13779327.08
      2327101.05      13779712.5      2327377.09      13780337.5
#Sta/Elev= 30
  4161.1  530.16  4236.5  526.89  4250.4  526.42  4265.3   523.4  4295.3  522.12
  4301.4  522.42  4307.4  524.96  4337.4  526.94  4358.4  521.12  4379.7  511.64
  4383.9   511.1  4394.4  510.25  4409.4  512.67  4553.4  505.15  4672.6  501.89
  4806.1  498.11  4846.3  497.59  4934.2     498  4957.9  497.26  4964.4  492.57
  4966.2  489.94  4966.7  489.44  4974.7  489.94  4979.4  490.08    4994  495.59
  5050.6  499.15  5181.4  502.82  5738.8  507.08  5909.4  507.59  6092.8  508.48
#Mann= 12 ,-1 , 0
  4161.1     .07       0  4236.5     .12       0  4383.9     .07       0
  4672.6     .12       0  4806.1     .07       0  4846.3     .12       0
  4934.2      .1       0  4966.2     .05       0  4974.7      .1       0
  5050.6     .07       0  5738.8    .035       0  5909.4     .07       0
Bank Sta=4966.2,4974.7
XS Rating Curve= 0 ,0
Exp/Cntr=0.3,0.1

Chan Stop Cuts=-1
Use User Specified Reach Order=0
Composite Channel Slope=5