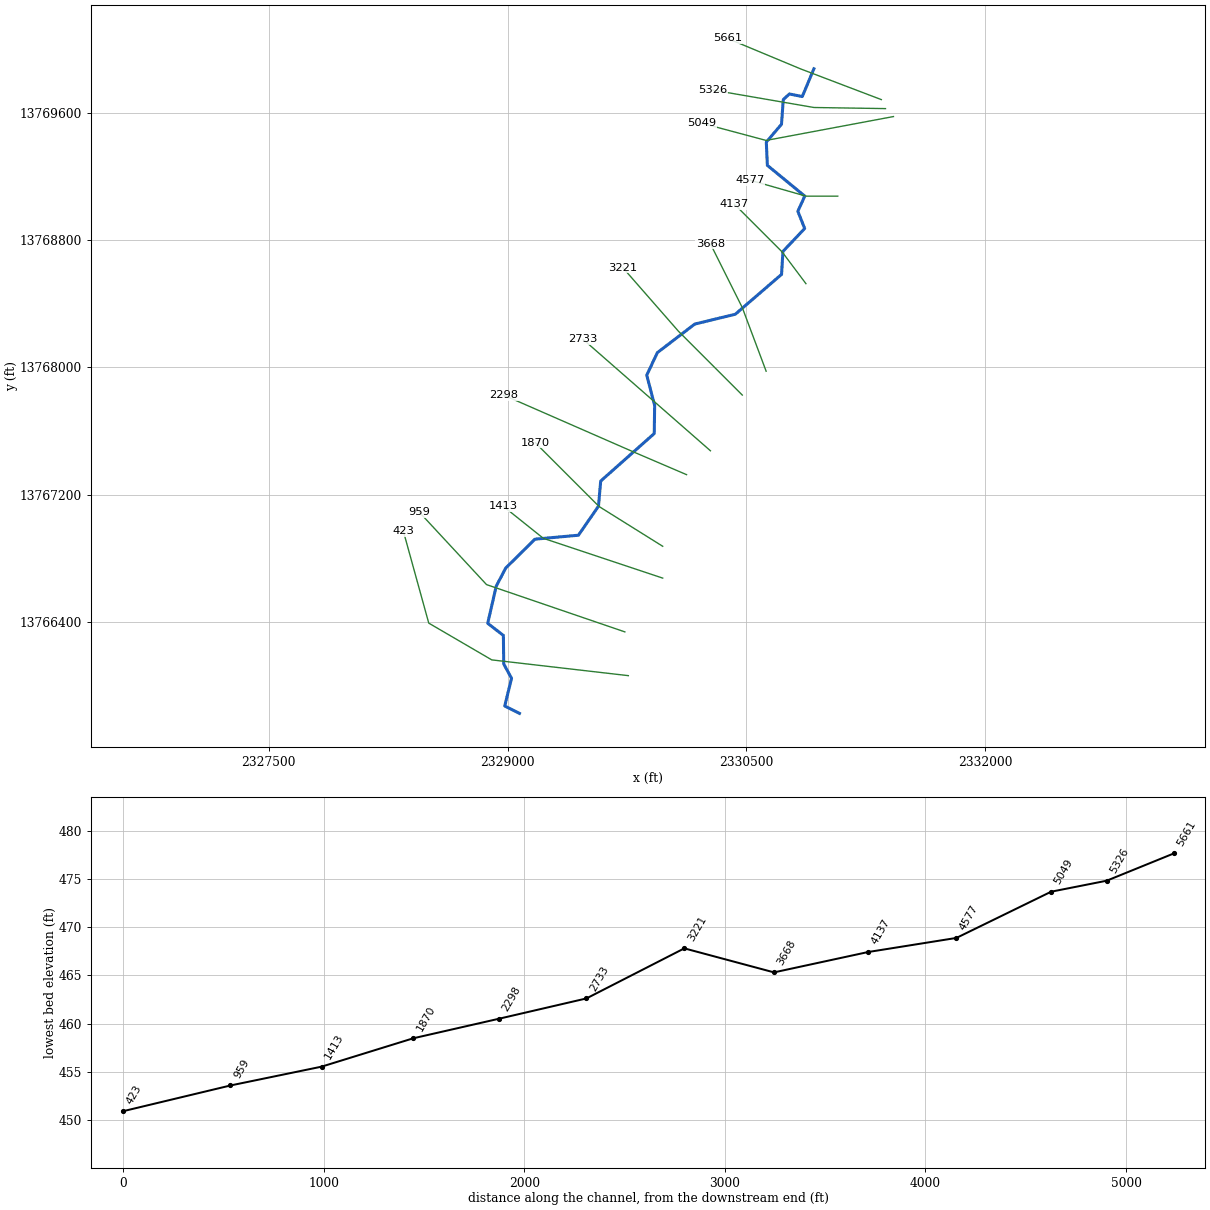
--- MILL TRIBUTARY 2.prj (project) ---

Proj Title=MILL TRIBUTARY 2 Base Level Engineering
Current Plan=p01
Default Exp/Contr=0.3,0.1
English Units
Geom File=g01
Flow File=f01
Plan File=p01
BEGIN DESCRIPTION:
MILL TRIBUTARY 2
END DESCRIPTION:

--- MILL TRIBUTARY 2.p01 (plan) ---

Plan Title=Multiple Run
Short Identifier=Multiple
Geom File=g01
Flow File=f01
Subcritical Flow
K Sum by GR= 0
Std Step Tol= 0.01
Critical Tol= 0.01
Num of Std Step Trials= 20
Max Error Tol= 0.3
Flow Tol Ratio= 0.001
Split Flow NTrial= 30
Split Flow Tol= 0.02
Split Flow Ratio= 0.02
Log Output Level= 0
Friction Slope Method= 1
Unsteady Friction Slope Method= 2
Unsteady Bridges Friction Slope Method= 1
Parabolic Critical Depth
Global Vel Dist=  1 , 1 , 1
Global Log Level= 0
CheckData=True
Encroach Param= -1, 0, 0, 0
BEGIN DESCRIPTION:
Multiple Run
END DESCRIPTION:

--- MILL TRIBUTARY 2.f01 (steady flow) ---

Flow Title=Multiple
Number of Profiles=7
Profile Names=10-year,25-year,50-year,1pct_min,100-year,1pct_plu,500-year
River Rch & RM= MILL TRIBUTARY 2,Reach-1,5661
     714    1167    1581    1037    2070    4130    3517
River Rch & RM= MILL TRIBUTARY 2,Reach-1,4577
     859    1416    1929    1271    2537    5062    4350
Boundary for River Rch & Prof#=MILL TRIBUTARY 2,Reach-1,1
Up Type=0
Dn Type=3
Dn Slope=0.005
Boundary for River Rch & Prof#=MILL TRIBUTARY 2,Reach-1,2
Up Type=0
Dn Type=3
Dn Slope=0.005
Boundary for River Rch & Prof#=MILL TRIBUTARY 2,Reach-1,3
Up Type=0
Dn Type=3
Dn Slope=0.005
Boundary for River Rch & Prof#=MILL TRIBUTARY 2,Reach-1,4
Up Type=0
Dn Type=3
Dn Slope=0.005
Boundary for River Rch & Prof#=MILL TRIBUTARY 2,Reach-1,5
Up Type=0
Dn Type=3
Dn Slope=0.005
Boundary for River Rch & Prof#=MILL TRIBUTARY 2,Reach-1,6
Up Type=0
Dn Type=3
Dn Slope=0.005
Boundary for River Rch & Prof#=MILL TRIBUTARY 2,Reach-1,7
Up Type=0
Dn Type=3
Dn Slope=0.005

--- MILL TRIBUTARY 2.g01 (geometry) ---

Geom Title=Existing Conditions

River Reach=MILL TRIBUTARY 2,Reach-1
Reach XY= 30
      2330925.00     13769875.00      2330852.12     13769700.58
      2330771.39     13769717.11      2330732.82     13769681.82
      2330721.44     13769526.47      2330626.04     13769414.56
      2330632.69     13769268.53      2330867.68     13769075.10
      2330824.26     13768980.04      2330867.20     13768871.58
      2330730.47     13768727.44      2330721.92     13768583.31
      2330431.17     13768332.86      2330176.58     13768271.18
      2329941.64     13768091.68      2329874.76     13767950.08
      2329924.48     13767759.78      2329921.93     13767583.30
      2329585.48     13767284.80      2329571.45     13767126.47
      2329445.55     13766944.44      2329172.55     13766919.54
      2328988.62     13766738.22      2328928.82     13766623.42
      2328875.54     13766390.90      2328973.99     13766314.71
      2328976.22     13766135.51      2329025.39     13766045.13
      2328982.50     13765871.38      2329075.00     13765825.00

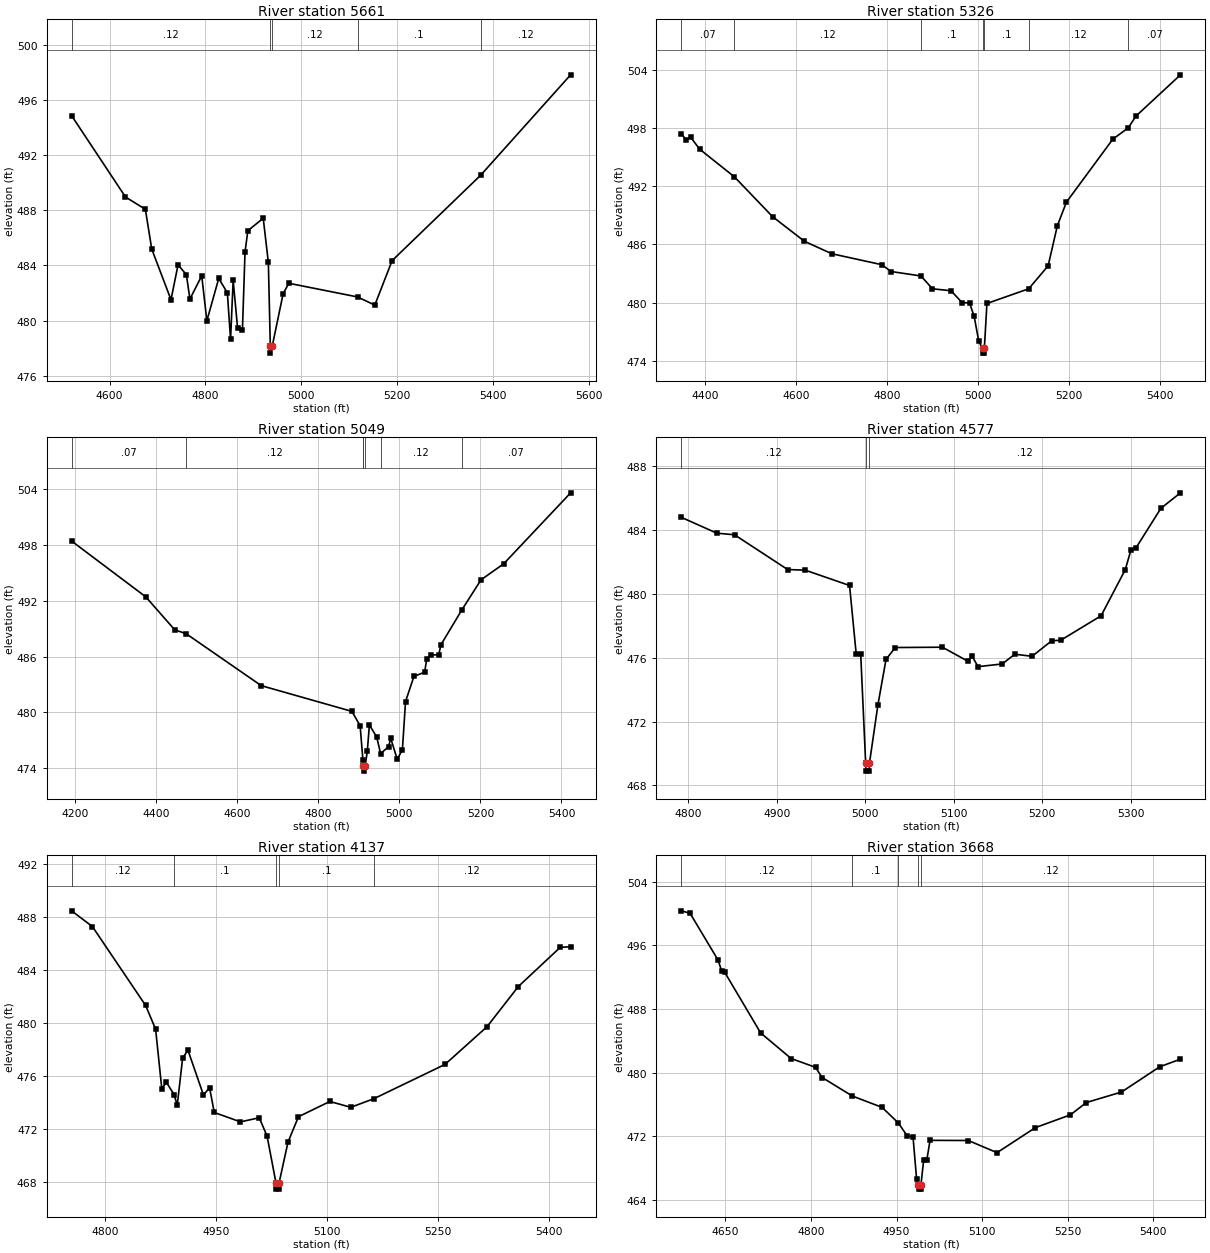
Type RM Length L Ch R = 1,5661,335,335,335
BEGIN DESCRIPTION:
B19506
END DESCRIPTION:
XS GIS Cut Line= 3
      2331348.94     13769681.47      2330842.88     13769874.00
      2330380.83     13770066.52
#Sta/Elev= 30
  4520.6  494.85  4633.1  488.96  4674.6  488.07  4687.9  485.19  4728.1  481.52
  4742.8  484.04  4760.2  483.34  4767.6  481.57  4792.3  483.25  4803.0  479.99
  4827.8  483.06  4845.8  482.02  4852.5  478.65  4857.9  482.92  4867.2  479.45
  4877.3  479.36  4882.7  484.98  4888.6  486.52  4920.7  487.42  4931.4  484.22
  4935.5  478.15  4935.8  477.65  4939.5  478.15  4962.3  481.96  4974.2  482.71
  5117.6  481.72  5153.7  481.13  5189.8  484.35  5374.5  490.53  5562.6  497.81
#Mann=5,-1,0
  4520.6    0.12       0  4935.5    0.05       0  4939.5    0.12       0
  5117.6     0.1       0  5374.5    0.12       0
Bank Sta=4935.5,4939.5
Exp/Cntr=0.3,0.1

Type RM Length L Ch R = 1,5326,277,277,277
BEGIN DESCRIPTION:
MILL TRIBUTARY 2 10.0
END DESCRIPTION:
XS GIS Cut Line= 3
      2331374.97     13769625.00      2330925.39     13769631.97
      2330288.62     13769741.76
#Sta/Elev= 30
  4348.4  497.39  4358.4  496.77  4368.4  497.05  4388.4  495.81  4464.7  492.96
  4548.4  488.87  4618.4  486.33  4678.4  485.05  4788.4  483.92  4808.6  483.22
  4874.5  482.76  4899.5  481.44  4940.5  481.24  4964.4  480.03  4981.1  479.98
  4991.2  478.60  5001.4  476.02  5009.5  475.32  5009.7  474.82  5013.3  474.82
  5013.6  475.32  5019.2  479.93  5110.9  481.44  5153.6  483.80  5173.9  487.94
  5193.8  490.36  5295.7  496.84  5329.7  498.01  5346.4  499.21  5444.2  503.46
#Mann=7,-1,0
  4348.4    0.07       0  4464.7    0.12       0  4874.5     0.1       0
  5009.5    0.05       0  5013.6     0.1       0  5110.9    0.12       0
  5329.7    0.07       0
Bank Sta=5009.5,5013.6
Exp/Cntr=0.3,0.1

Type RM Length L Ch R = 1,5049,472,472,472
BEGIN DESCRIPTION:
MILL TRIBUTARY 2 9.0
END DESCRIPTION:
XS GIS Cut Line= 3
      2331425.04     13769575.01      2330625.00     13769425.00
      2330221.27     13769532.97
#Sta/Elev= 30
  4190.8  498.44  4374.0  492.43  4445.2  488.89  4473.5  488.47  4658.9  482.88
  4882.7  480.11  4903.0  478.57  4909.9  474.88  4911.2  474.18  4911.4  473.68
  4915.3  474.18  4920.8  475.85  4925.9  478.65  4943.7  477.37  4953.7  475.57
  4973.4  476.32  4978.5  477.23  4994.6  474.95  5007.4  475.99  5015.1  481.16
  5035.8  483.87  5062.3  484.33  5067.5  485.77  5077.2  486.18  5097.2  486.20
  5102.3  487.26  5153.4  490.98  5201.5  494.27  5257.4  495.99  5422.7  503.63
#Mann=7,-1,0
  4190.8    0.07       0  4473.5    0.12       0  4909.9     0.1       0
  4911.2    0.05       0  4915.3     0.1       0  4953.7    0.12       0
  5153.4    0.07       0
Bank Sta=4911.2,4915.3
Exp/Cntr=0.3,0.1

Type RM Length L Ch R = 1,4577,440,440,440
BEGIN DESCRIPTION:
MILL TRIBUTARY 2 8.0
END DESCRIPTION:
XS GIS Cut Line= 3
      2331074.98     13769075.00      2330875.00     13769075.00
      2330524.98     13769175.00
#Sta/Elev= 30
  4792.1  484.80  4832.1  483.81  4852.1  483.71  4912.1  481.53  4932.1  481.49
  4982.1  480.53  4989.6  476.24  4994.7  476.24  5000.3  469.39  5000.6  468.89
  5004.4  468.89  5004.6  469.39  5014.2  473.06  5023.3  475.89  5033.7  476.64
  5087.0  476.66  5115.6  475.79  5120.8  476.08  5127.3  475.44  5154.6  475.61
  5168.9  476.22  5188.4  476.09  5210.5  477.06  5220.9  477.10  5266.4  478.63
  5293.7  481.52  5300.2  482.77  5305.4  482.85  5334.0  485.37  5356.1  486.34
#Mann=3,-1,0
  4792.1    0.12       0  5000.3    0.05       0  5004.6    0.12       0
Bank Sta=5000.3,5004.6
Exp/Cntr=0.3,0.1

Type RM Length L Ch R = 1,4137,469,469,469
BEGIN DESCRIPTION:
MILL TRIBUTARY 2 7.0
END DESCRIPTION:
XS GIS Cut Line= 3
      2330874.97     13768525.04      2330725.00     13768725.00
      2330425.01     13769024.99
#Sta/Elev= 30
  4754.7  488.45  4782.8  487.26  4854.7  481.30  4868.2  479.51  4876.5  475.03
  4882.8  475.49  4893.2  474.57  4897.4  473.76  4904.7  477.34  4911.9  477.92
  4932.8  474.54  4941.1  475.09  4947.4  473.22  4982.8  472.51  5008.2  472.82
  5018.8  471.43  5030.7  467.93  5031.0  467.43  5034.8  467.43  5035.1  467.93
  5047.1  470.99  5061.2  472.90  5103.6  474.05  5131.9  473.61  5163.1  474.26
  5259.2  476.85  5315.8  479.69  5358.2  482.73  5414.8  485.69  5428.9  485.74
#Mann=5,-1,0
  4754.7    0.12       0  4893.2     0.1       0  5030.7    0.05       0
  5035.1     0.1       0  5163.1    0.12       0
Bank Sta=5030.7,5035.1
Exp/Cntr=0.3,0.1

Type RM Length L Ch R = 1,3668,447,447,447
BEGIN DESCRIPTION:
MILL TRIBUTARY 2 6.0
END DESCRIPTION:
XS GIS Cut Line= 3
      2330625.00     13767975.00      2330475.00     13768375.00
      2330275.01     13768774.98
#Sta/Elev= 30
  4573.1  500.35  4588.2  500.04  4637.2  494.16  4643.4  492.81  4648.8  492.63
  4711.9  484.98  4765.3  481.76  4808.1  480.65  4819.6  479.37  4872.8  477.03
  4924.7  475.61  4953.0  473.66  4968.3  472.06  4978.9  471.88  4985.2  466.54
  4988.3  465.82  4988.6  465.32  4992.4  465.32  4992.7  465.82  4997.6  469.00
  5003.1  469.00  5008.7  471.46  5075.8  471.44  5126.1  469.91  5193.2  473.06
  5254.7  474.67  5282.6  476.22  5344.1  477.54  5411.2  480.72  5447.5  481.68
#Mann=5,-1,0
  4573.1    0.12       0  4872.8     0.1       0  4953.0    0.12       0
  4988.3    0.05       0  4992.7    0.12       0
Bank Sta=4988.3,4992.7
Exp/Cntr=0.3,0.1

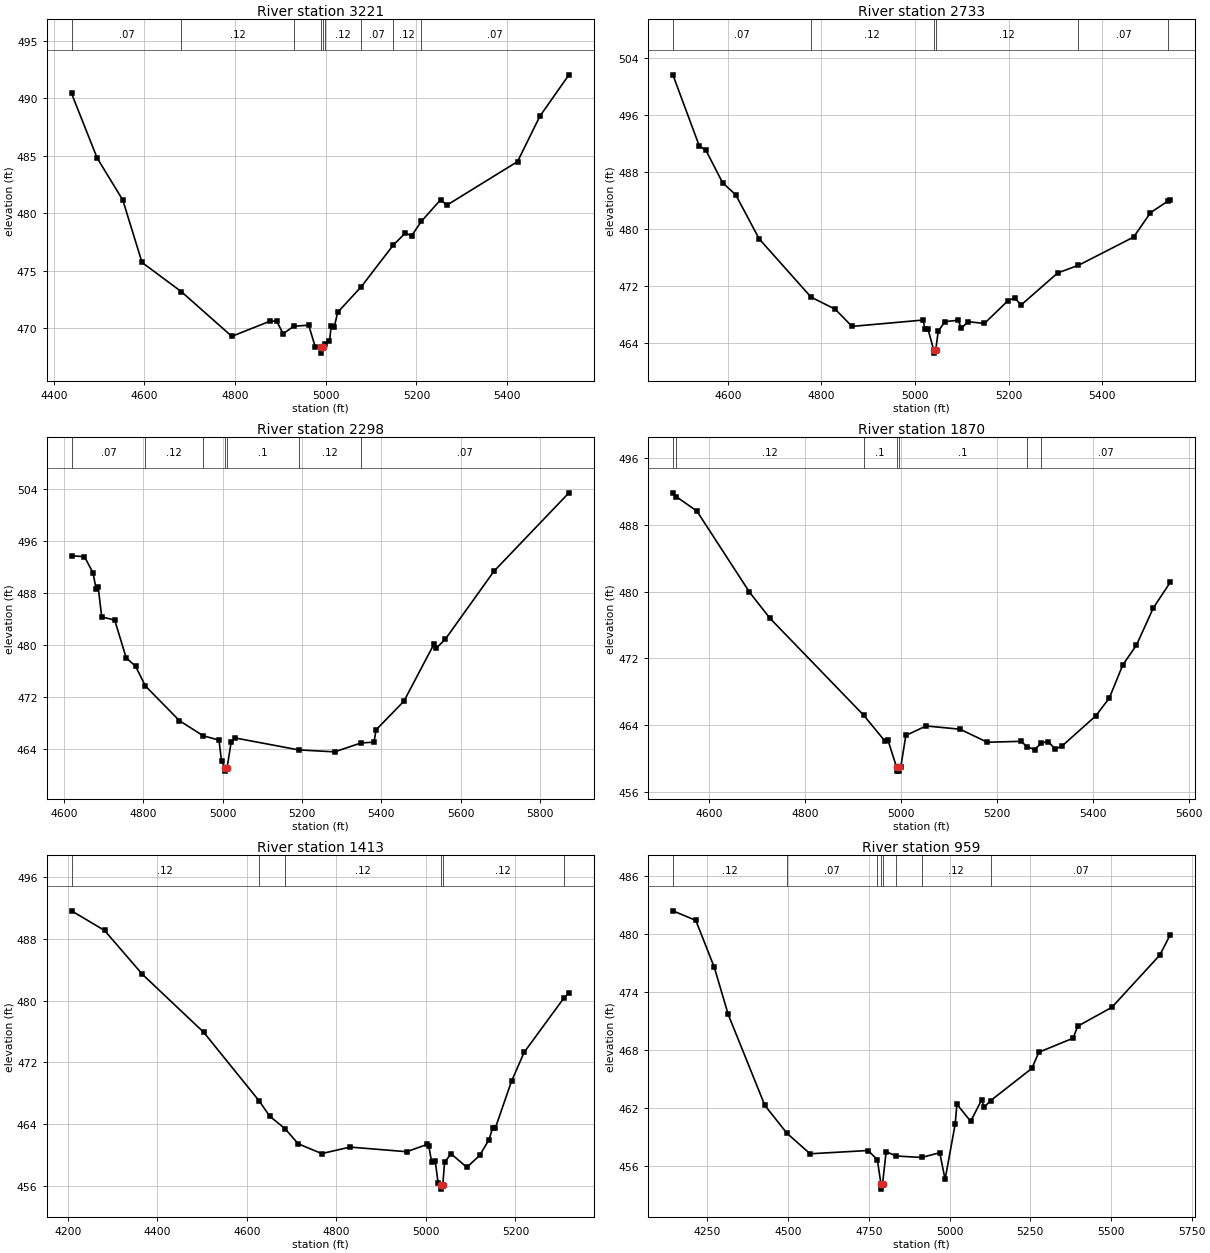
Type RM Length L Ch R = 1,3221,488,488,488
BEGIN DESCRIPTION:
MILL TRIBUTARY 2 5.0
END DESCRIPTION:
XS GIS Cut Line= 3
      2330474.99     13767825.01      2330075.00     13768225.00
      2329724.98     13768625.02
#Sta/Elev= 30
  4439.1  490.41  4495.7  484.78  4552.2  481.13  4594.6  475.70  4681.3  473.16
  4792.6  469.27  4877.5  470.60  4891.6  470.59  4905.8  469.50  4929.3  470.15
  4962.3  470.24  4976.5  468.37  4988.3  468.31  4988.7  467.81  4992.9  468.31
  4998.0  468.64  5008.1  468.84  5011.9  470.19  5018.5  470.06  5026.1  471.36
  5078.2  473.59  5148.5  477.20  5175.1  478.25  5189.4  478.03  5210.8  479.28
  5253.0  481.15  5267.2  480.69  5422.9  484.48  5472.2  488.43  5536.3  492.03
#Mann=9,-1,0
  4439.1    0.07       0  4681.3    0.12       0  4929.3    0.07       0
  4988.3    0.05       0  4992.9    0.07       0  4998.0    0.12       0
  5078.2    0.07       0  5148.5    0.12       0  5210.8    0.07       0
Bank Sta=4988.3,4992.9
Exp/Cntr=0.3,0.1

Type RM Length L Ch R = 1,2733,435,435,435
BEGIN DESCRIPTION:
MILL TRIBUTARY 2 4.0
END DESCRIPTION:
XS GIS Cut Line= 3
      2330274.97     13767475.03      2329875.00     13767825.00
      2329474.98     13768175.02
#Sta/Elev= 30
  4482.5  501.66  4538.9  491.69  4553.2  491.06  4588.8  486.52  4616.8  484.83
  4667.1  478.63  4777.7  470.48  4829.4  468.78  4865.4  466.37  5017.3  467.26
  5021.1  465.99  5027.7  466.00  5039.6  463.12  5040.0  462.62  5044.3  463.12
  5049.6  465.69  5063.8  467.04  5092.3  467.23  5098.9  466.10  5113.2  467.03
  5148.3  466.78  5198.6  469.98  5212.8  470.38  5226.6  469.37  5304.9  473.87
  5349.2  474.94  5467.2  478.90  5503.2  482.32  5541.5  484.00  5545.5  484.05
#Mann=6,-1,0
  4482.5    0.07       0  4777.7    0.12       0  5039.6    0.05       0
  5044.3    0.12       0  5349.2    0.07       0  5541.5    0.12       0
Bank Sta=5039.6,5044.3
Exp/Cntr=0.3,0.1

Type RM Length L Ch R = 1,2298,428,428,428
BEGIN DESCRIPTION:
MILL TRIBUTARY 2 3.0
END DESCRIPTION:
XS GIS Cut Line= 3
      2330124.99     13767325.01      2329775.00     13767475.00
      2328974.99     13767825.00
#Sta/Elev= 30
  4619.2  493.69  4651.8  493.56  4673.6  491.02  4680.8  488.65  4686.3  488.89
  4695.3  484.27  4728.0  483.80  4757.0  477.96  4780.6  476.69  4805.2  473.65
  4891.2  468.29  4951.0  465.97  4990.9  465.30  4997.3  462.10  5006.6  461.02
  5006.9  460.52  5011.3  461.02  5021.8  465.08  5032.3  465.62  5191.9  463.79
  5282.6  463.49  5348.9  464.86  5381.6  464.98  5387.1  466.89  5457.2  471.30
  5532.9  480.08  5538.3  479.43  5561.7  480.86  5684.1  491.31  5873.2  503.39
#Mann=7,-1,0
  4619.2    0.07       0  4805.2    0.12       0  4951.0     0.1       0
  5006.6    0.05       0  5011.3     0.1       0  5191.9    0.12       0
  5348.9    0.07       0
Bank Sta=5006.6,5011.3
Exp/Cntr=0.3,0.1

Type RM Length L Ch R = 1,1870,457,457,457
BEGIN DESCRIPTION:
MILL TRIBUTARY 2 2.0
END DESCRIPTION:
XS GIS Cut Line= 3
      2329975.01     13766874.99      2329575.00     13767125.00
      2329175.00     13767525.00
#Sta/Elev= 30
  4524.0  491.83  4530.7  491.39  4574.1  489.64  4683.8  479.93  4726.3  476.81
  4922.2  465.17  4966.8  462.05  4972.7  462.18  4990.4  458.99  4990.8  458.49
  4994.8  458.49  4995.1  458.99  4999.3  458.99  5009.9  462.77  5052.3  463.90
  5123.0  463.51  5179.6  461.95  5250.3  462.06  5263.0  461.40  5278.6  461.08
  5292.6  461.87  5306.8  462.03  5321.0  461.14  5335.1  461.47  5405.8  465.10
  5434.1  467.23  5462.4  471.22  5490.7  473.57  5526.0  478.04  5561.4  481.12
#Mann=7,-1,0
  4524.0    0.07       0  4530.7    0.12       0  4922.2     0.1       0
  4990.4    0.05       0  4995.1     0.1       0  5263.0    0.12       0
  5292.6    0.07       0
Bank Sta=4990.4,4995.1
Exp/Cntr=0.3,0.1

Type RM Length L Ch R = 1,1413,454,454,454
BEGIN DESCRIPTION:
MILL TRIBUTARY 2 1.0
END DESCRIPTION:
XS GIS Cut Line= 3
      2329975.05     13766674.98      2329225.00     13766925.00
      2328974.98     13767125.02
#Sta/Elev= 30
  4208.7  491.63  4282.5  489.08  4366.9  483.40  4503.9  475.88  4627.8  466.98
  4651.5  464.99  4685.6  463.38  4714.7  461.43  4767.4  460.16  4830.7  461.00
  4957.2  460.40  5002.5  461.34  5006.5  461.17  5012.9  459.03  5020.9  459.23
  5027.3  456.32  5032.9  456.05  5033.3  455.55  5037.7  456.05  5041.7  459.01
  5056.1  460.14  5091.4  458.38  5120.2  459.92  5141.0  461.97  5149.0  463.46
  5155.4  463.52  5191.4  469.56  5219.4  473.28  5308.0  480.31  5319.5  480.99
#Mann=6,-1,0
  4208.7    0.12       0  4627.8    0.07       0  4685.6    0.12       0
  5032.9    0.05       0  5037.7    0.12       0  5308.0    0.07       0
Bank Sta=5032.9,5037.7
Exp/Cntr=0.3,0.1

Type RM Length L Ch R = 1,959,536,536,536
BEGIN DESCRIPTION:
B19505
END DESCRIPTION:
XS GIS Cut Line= 3
      2329737.23     13766337.07      2328868.13     13766634.10
      2328444.87     13767090.35
#Sta/Elev= 30
  4143.0  482.42  4214.0  481.43  4271.3  476.57  4314.4  471.69  4427.9  462.27
  4496.5  459.38  4568.1  457.26  4747.7  457.60  4776.4  456.65  4787.6  454.10
  4787.9  453.60  4792.4  454.10  4803.6  457.48  4834.3  457.03  4913.3  456.88
  4969.6  457.37  4986.2  454.61  5017.5  460.34  5022.8  462.39  5065.5  460.62
  5099.8  462.87  5106.6  462.07  5127.5  462.77  5255.2  466.11  5276.7  467.78
  5382.7  469.23  5396.9  470.47  5502.9  472.43  5651.4  477.84  5683.8  479.95
#Mann=8,-1,0
  4143.0    0.12       0  4496.5    0.07       0  4776.4    0.12       0
  4787.6    0.05       0  4792.4    0.12       0  4834.3    0.07       0
  4913.3    0.12       0  5127.5    0.07       0
Bank Sta=4787.6,4792.4
Exp/Cntr=0.3,0.1

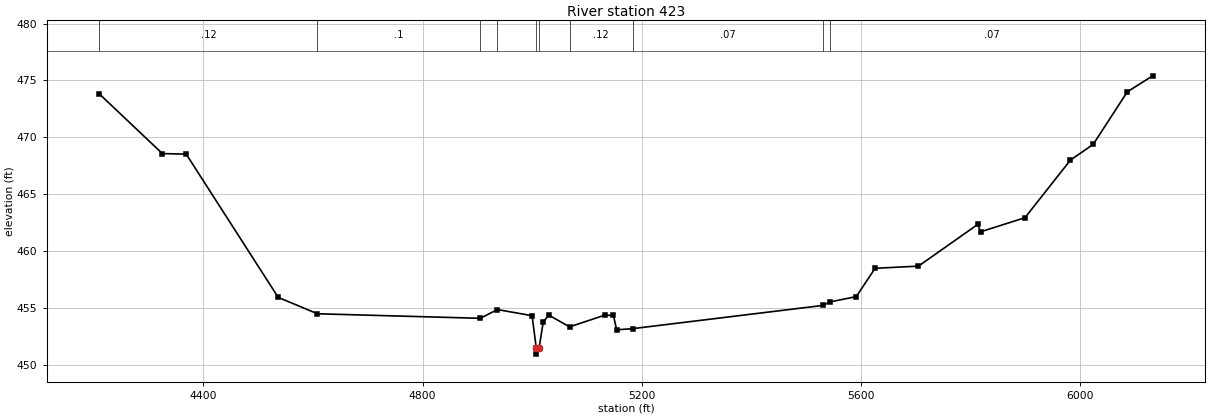
Type RM Length L Ch R = 1,423,0,0,0
BEGIN DESCRIPTION:
B19504
END DESCRIPTION:
XS GIS Cut Line= 4
      2329759.24     13766062.03      2328901.14     13766161.04
      2328505.09     13766392.07      2328345.57     13766969.65
#Sta/Elev= 30
  4210.3  473.82  4325.3  468.57  4368.8  468.52  4536.6  455.92  4608.2  454.48
  4905.3  454.08  4936.4  454.85  4999.7  454.31  5007.4  451.43  5007.7  450.93
  5012.3  451.43  5019.9  453.73  5029.9  454.37  5068.0  453.33  5132.4  454.36
  5148.1  454.33  5153.9  453.07  5183.0  453.17  5531.0  455.22  5543.0  455.52
  5591.0  455.99  5625.3  458.48  5704.4  458.67  5812.6  462.34  5817.8  461.69
  5898.7  462.93  5981.7  468.00  6023.2  469.38  6085.5  474.01  6131.8  475.41
#Mann=10,-1,0
  4210.3    0.12       0  4608.2     0.1       0  4905.3    0.12       0
  4936.4     0.1       0  5007.4    0.05       0  5012.3     0.1       0
  5068.0    0.12       0  5183.0    0.07       0  5531.0     0.1       0
  5543.0    0.07       0
Bank Sta=5007.4,5012.3
Exp/Cntr=0.3,0.1

Chan Stop Cuts=-1