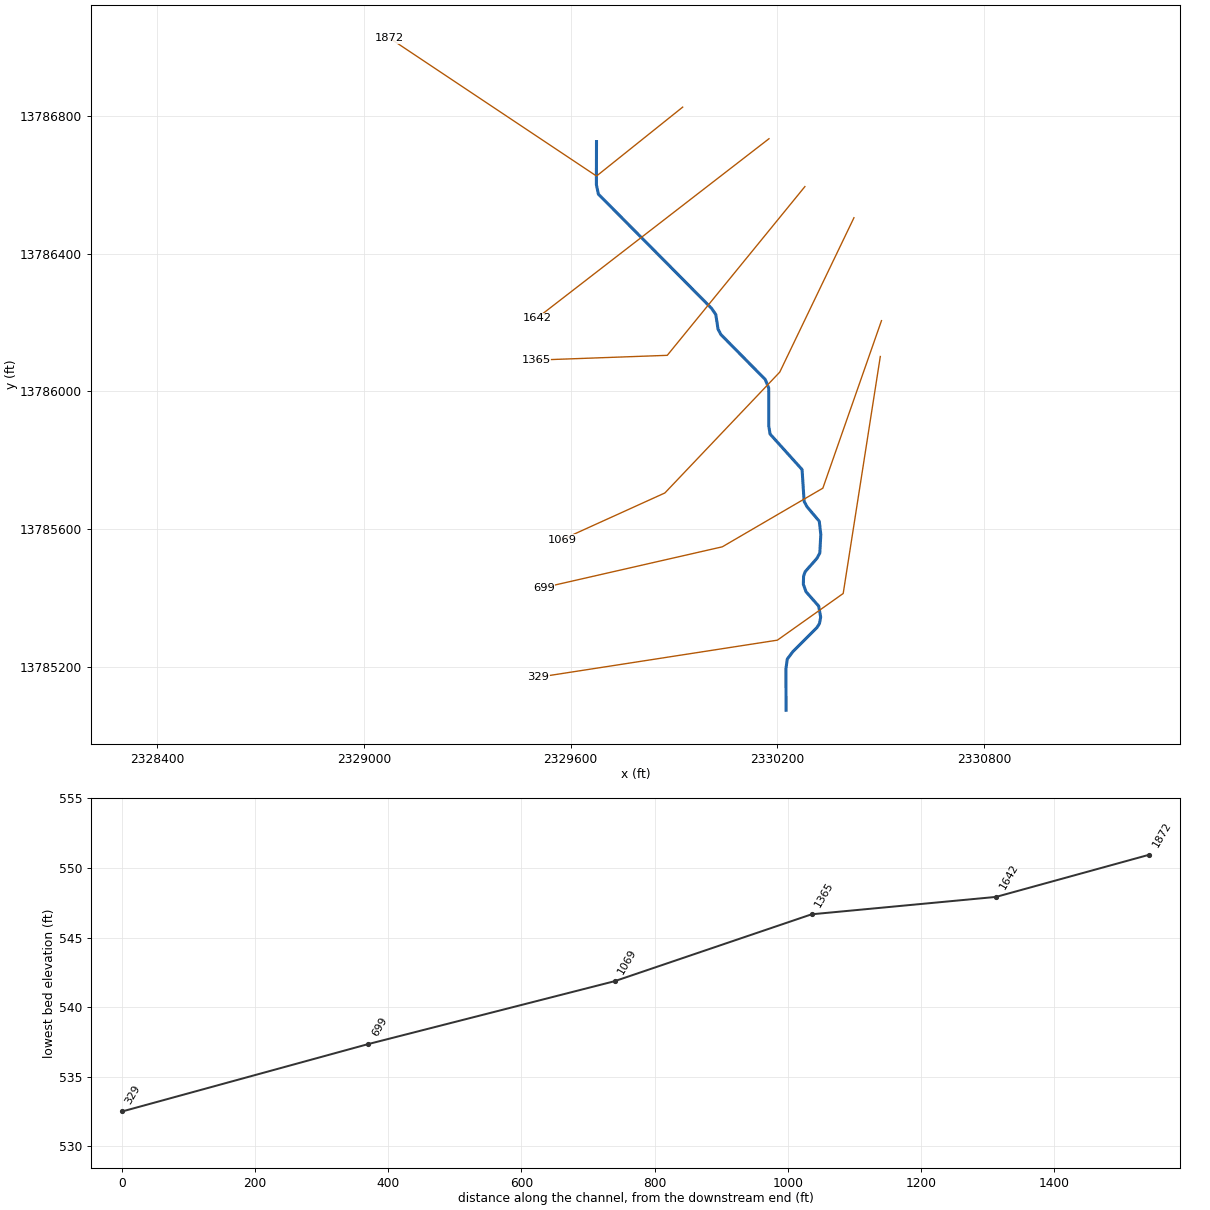
--- MILL TRIBUTARY 20.prj (project) ---

Proj Title=MILL TRIBUTARY 20 Base Level Engineering
Current Plan=p01
Default Exp/Contr=0.3,0.1
English Units
Geom File=g01
Flow File=f01
Plan File=p01
BEGIN DESCRIPTION:
MILL TRIBUTARY 20
END DESCRIPTION:

--- MILL TRIBUTARY 20.p01 (plan) ---

Plan Title=Multiple Run
Short Identifier=Multiple
Geom File=g01
Flow File=f01
Subcritical Flow
K Sum by GR= 0
Std Step Tol= 0.01
Critical Tol= 0.01
Num of Std Step Trials= 20
Max Error Tol= 0.3
Flow Tol Ratio= 0.001
Split Flow NTrial= 30
Split Flow Tol= 0.02
Split Flow Ratio= 0.02
Log Output Level= 0
Friction Slope Method= 1
Unsteady Friction Slope Method= 2
Unsteady Bridges Friction Slope Method= 1
Parabolic Critical Depth
Global Vel Dist=  1 , 1 , 1
Global Log Level= 0
CheckData=True
Encroach Param= -1, 0, 0, 0
BEGIN DESCRIPTION:
Multiple Run
END DESCRIPTION:

--- MILL TRIBUTARY 20.f01 (steady flow) ---

Flow Title=Multiple
Number of Profiles=7
Profile Names=10-year,25-year,50-year,1pct_min,100-year,1pct_plu,500-year
River Rch & RM= MILL TRIBUTARY 2,Reach-1,1872
     196     295     379     237     472     943     726
Boundary for River Rch & Prof#=MILL TRIBUTARY 2,Reach-1,1
Up Type=0
Dn Type=3
Dn Slope=0.005
Boundary for River Rch & Prof#=MILL TRIBUTARY 2,Reach-1,2
Up Type=0
Dn Type=3
Dn Slope=0.005
Boundary for River Rch & Prof#=MILL TRIBUTARY 2,Reach-1,3
Up Type=0
Dn Type=3
Dn Slope=0.005
Boundary for River Rch & Prof#=MILL TRIBUTARY 2,Reach-1,4
Up Type=0
Dn Type=3
Dn Slope=0.005
Boundary for River Rch & Prof#=MILL TRIBUTARY 2,Reach-1,5
Up Type=0
Dn Type=3
Dn Slope=0.005
Boundary for River Rch & Prof#=MILL TRIBUTARY 2,Reach-1,6
Up Type=0
Dn Type=3
Dn Slope=0.005
Boundary for River Rch & Prof#=MILL TRIBUTARY 2,Reach-1,7
Up Type=0
Dn Type=3
Dn Slope=0.005

--- MILL TRIBUTARY 20.g01 (geometry) ---

Geom Title=Existing Conditions

River Reach=MILL TRIBUTARY 2,Reach-1
Reach XY= 30
      2329675.00     13786725.00      2329674.62     13786599.84
      2329680.43     13786572.54      2330008.35     13786241.67
      2330021.02     13786223.35      2330027.54     13786181.05
      2330035.78     13786165.32      2330164.52     13786034.80
      2330174.60     13786009.84      2330174.73     13785899.89
      2330178.56     13785876.47      2330271.38     13785773.50
      2330277.36     13785680.98      2330285.90     13785665.37
      2330321.30     13785623.40      2330325.77     13785585.05
      2330322.81     13785530.97      2330314.13     13785515.35
      2330280.38     13785477.18      2330275.77     13785464.31
      2330275.11     13785440.39      2330282.86     13785419.06
      2330319.61     13785377.19      2330325.39     13785345.13
      2330321.86     13785326.64      2330314.79     13785315.33
      2330244.65     13785245.15      2330228.51     13785223.55
      2330224.49     13785195.21      2330225.00     13785075.00

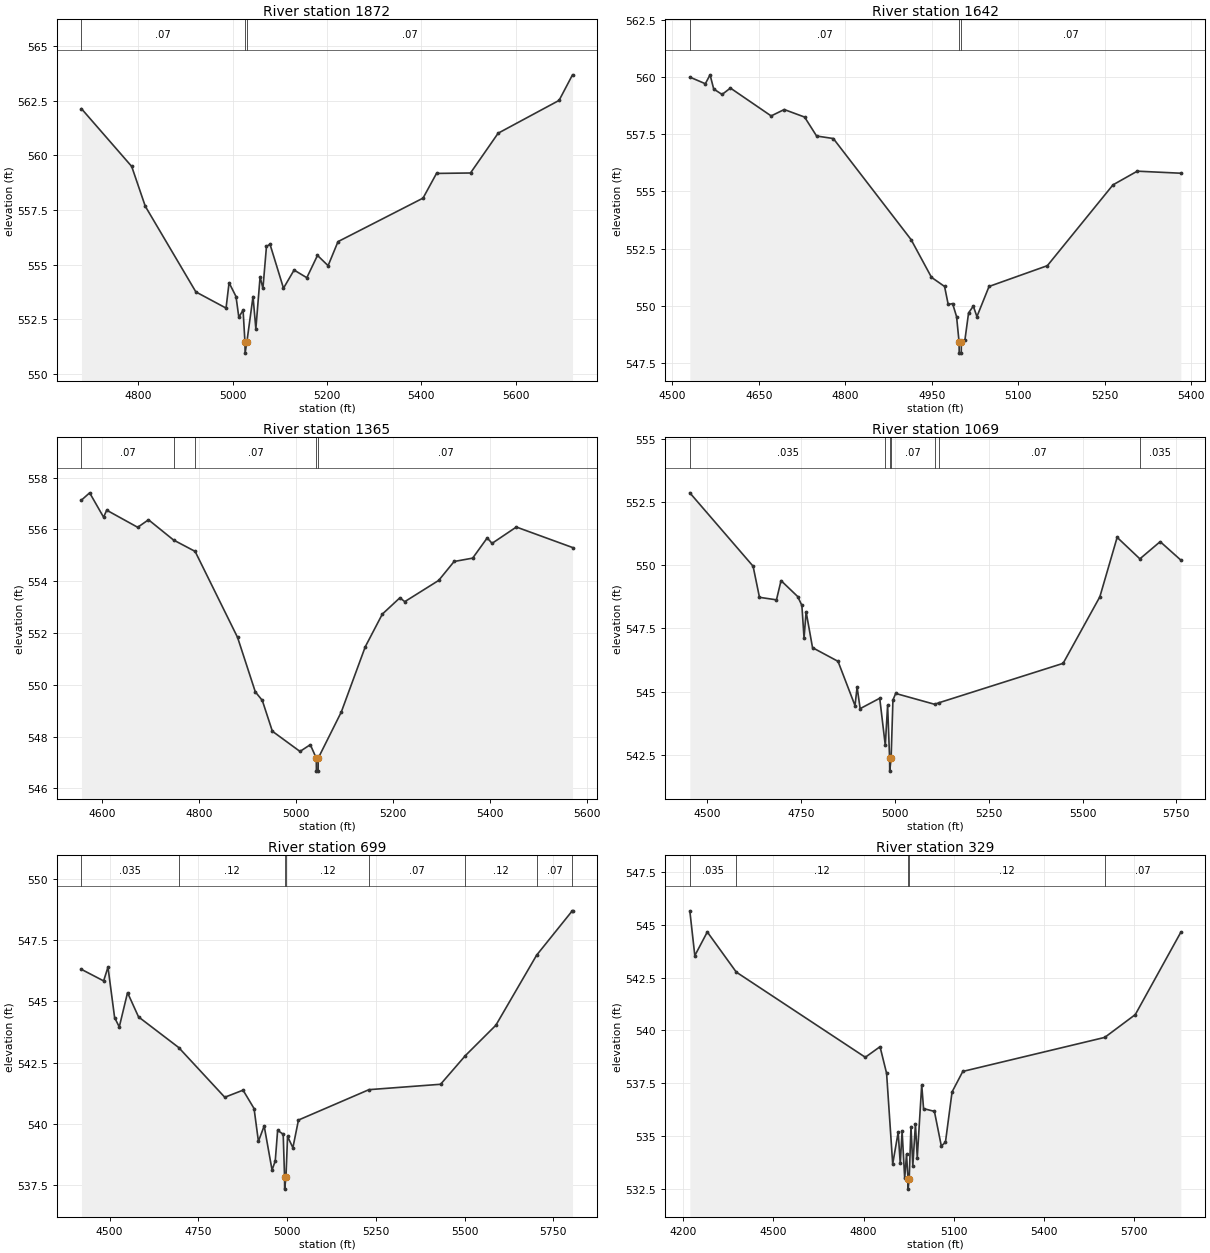
Type RM Length L Ch R = 1,1872,230,230,230
BEGIN DESCRIPTION:
MILL TRIBUTARY 20 2.0
END DESCRIPTION:
XS GIS Cut Line= 3
      2329925.03     13786825.02      2329675.00     13786625.00
      2329075.00     13787025.00
#Sta/Elev= 30
  4679.2  562.13  4785.7  559.49  4814.5  557.67  4921.8  553.75  4985.8  553.01
  4992.2  554.17  5006.9  553.54  5012.9  552.59  5021.9  552.92  5025.9  551.45
  5026.2  550.95  5029.9  551.45  5043.0  553.54  5049.0  552.06  5058.0  554.44
  5064.0  553.91  5071.5  555.83  5079.0  555.93  5107.6  553.92  5130.1  554.75
  5157.1  554.40  5179.7  555.42  5202.2  554.95  5223.2  556.05  5403.5  558.04
  5432.1  559.17  5504.2  559.19  5562.8  561.01  5692.0  562.51  5720.5  563.68
#Mann=3,-1,0
  4679.2    0.07       0  5025.9    0.05       0  5029.9    0.07       0
Bank Sta=5025.9,5029.9
Exp/Cntr=0.3,0.1

Type RM Length L Ch R = 1,1642,277,277,277
BEGIN DESCRIPTION:
B19511
END DESCRIPTION:
XS GIS Cut Line= 2
      2330175.41     13786733.31      2329501.86     13786212.52
#Sta/Elev= 30
  4530.4  560.01  4557.3  559.72  4565.5  560.11  4571.8  559.49  4586.3  559.25
  4600.8  559.53  4671.4  558.31  4694.1  558.59  4729.4  558.26  4750.2  557.43
  4779.2  557.32  4914.1  552.89  4949.4  551.24  4972.1  550.84  4978.4  550.05
  4986.0  550.09  4992.9  549.52  4997.2  548.42  4997.5  547.92  5001.0  547.92
  5001.2  548.42  5007.4  548.50  5013.7  549.68  5021.9  549.98  5028.2  549.52
  5049.2  550.84  5150.3  551.75  5264.1  555.29  5306.2  555.89  5381.8  555.80
#Mann=3,-1,0
  4530.4    0.07       0  4997.2    0.05       0  5001.2    0.07       0
Bank Sta=4997.2,5001.2
Exp/Cntr=0.3,0.1

Type RM Length L Ch R = 1,1365,296,296,296
BEGIN DESCRIPTION:
B19510
END DESCRIPTION:
XS GIS Cut Line= 3
      2330279.61     13786594.45      2329880.30     13786104.86
      2329499.13     13786091.00
#Sta/Elev= 30
  4556.8  557.13  4573.7  557.41  4602.4  556.47  4608.9  556.74  4672.8  556.08
  4695.1  556.37  4746.7  555.59  4791.3  555.15  4878.9  551.83  4915.5  549.73
  4929.9  549.40  4950.7  548.21  5007.7  547.43  5029.0  547.69  5041.3  547.17
  5041.6  546.67  5045.1  546.67  5045.3  547.17  5092.9  548.95  5142.4  551.47
  5177.6  552.73  5213.9  553.36  5223.9  553.21  5293.9  554.03  5325.7  554.76
  5364.0  554.89  5394.0  555.67  5404.0  555.46  5454.1  556.09  5570.0  555.30
#Mann=5,-1,0
  4556.8    0.07       0  4746.7   0.035       0  4791.3    0.07       0
  5041.3    0.05       0  5045.3    0.07       0
Bank Sta=5041.3,5045.3
Exp/Cntr=0.3,0.1

Type RM Length L Ch R = 1,1069,370,370,370
BEGIN DESCRIPTION:
B19509
END DESCRIPTION:
XS GIS Cut Line= 4
      2330421.95     13786504.13      2330206.69     13786056.25
      2329873.36     13785705.56      2329574.79     13785570.16
#Sta/Elev= 30
  4453.5  552.86  4622.1  549.96  4639.1  548.73  4684.4  548.63  4696.6  549.39
  4741.0  548.76  4752.1  548.41  4757.9  547.12  4763.4  548.16  4780.5  546.74
  4848.4  546.20  4893.7  544.45  4899.3  545.18  4907.4  544.33  4959.6  544.74
  4974.4  542.88  4980.6  544.47  4985.9  542.36  4986.2  541.86  4989.9  542.36
  4994.8  544.67  5002.1  544.93  5106.3  544.50  5116.8  544.56  5448.3  546.12
  5546.2  548.75  5592.3  551.10  5652.9  550.25  5707.0  550.93  5762.1  550.20
#Mann=7,-1,0
  4453.5   0.035       0  4974.4    0.07       0  4985.9    0.05       0
  4989.9    0.07       0  5106.3   0.035       0  5116.8    0.07       0
  5652.9   0.035       0
Bank Sta=4985.9,4989.9
Exp/Cntr=0.3,0.1

Type RM Length L Ch R = 1,699,370,370,370
BEGIN DESCRIPTION:
B19508
END DESCRIPTION:
XS GIS Cut Line= 4
      2330501.81     13786205.51      2330331.69     13785719.44
      2330040.02     13785549.31      2329522.66     13785431.25
#Sta/Elev= 30
  4420.7  546.31  4483.1  545.84  4495.4  546.40  4514.1  544.34  4527.2  543.96
  4550.5  545.36  4581.5  544.37  4694.6  543.12  4824.4  541.09  4875.9  541.38
  4906.9  540.63  4919.2  539.29  4935.4  539.92  4957.6  538.12  4966.6  538.49
  4973.3  539.74  4989.0  539.58  4992.8  537.84  4993.1  537.34  4996.8  537.84
  5001.3  539.49  5016.3  539.03  5032.0  540.16  5230.6  541.40  5432.3  541.62
  5502.2  542.79  5588.1  544.03  5702.9  546.89  5803.3  548.70  5804.0  548.70
#Mann=8,-1,0
  4420.7   0.035       0  4694.6    0.12       0  4992.8    0.05       0
  4996.8    0.12       0  5230.6    0.07       0  5502.2    0.12       0
  5702.9    0.07       0  5803.3   0.035       0
Bank Sta=4992.8,4996.8
Exp/Cntr=0.3,0.1

Type RM Length L Ch R = 1,329,0,0,0
BEGIN DESCRIPTION:
B19507
END DESCRIPTION:
XS GIS Cut Line= 4
      2330498.36     13786101.44      2330390.72     13785413.89
      2330199.75     13785278.47      2329505.27     13785170.83
#Sta/Elev= 30
  4222.0  545.66  4238.6  543.54  4280.1  544.66  4376.5  542.76  4805.5  538.73
  4854.5  539.23  4876.3  537.97  4896.6  533.68  4914.8  535.18  4921.7  533.71
  4927.9  535.22  4936.5  533.00  4942.6  534.14  4947.5  532.99  4947.7  532.49
  4951.5  532.99  4957.4  535.45  4963.5  533.60  4972.2  535.57  4978.3  533.98
  4993.1  537.43  4999.2  536.30  5035.3  536.17  5058.3  534.53  5072.0  534.71
  5094.0  537.09  5129.7  538.06  5601.7  539.67  5703.3  540.75  5854.8  544.65
#Mann=5,-1,0
  4222.0   0.035       0  4376.5    0.12       0  4947.5    0.05       0
  4951.5    0.12       0  5601.7    0.07       0
Bank Sta=4947.5,4951.5
Exp/Cntr=0.3,0.1

Chan Stop Cuts=-1