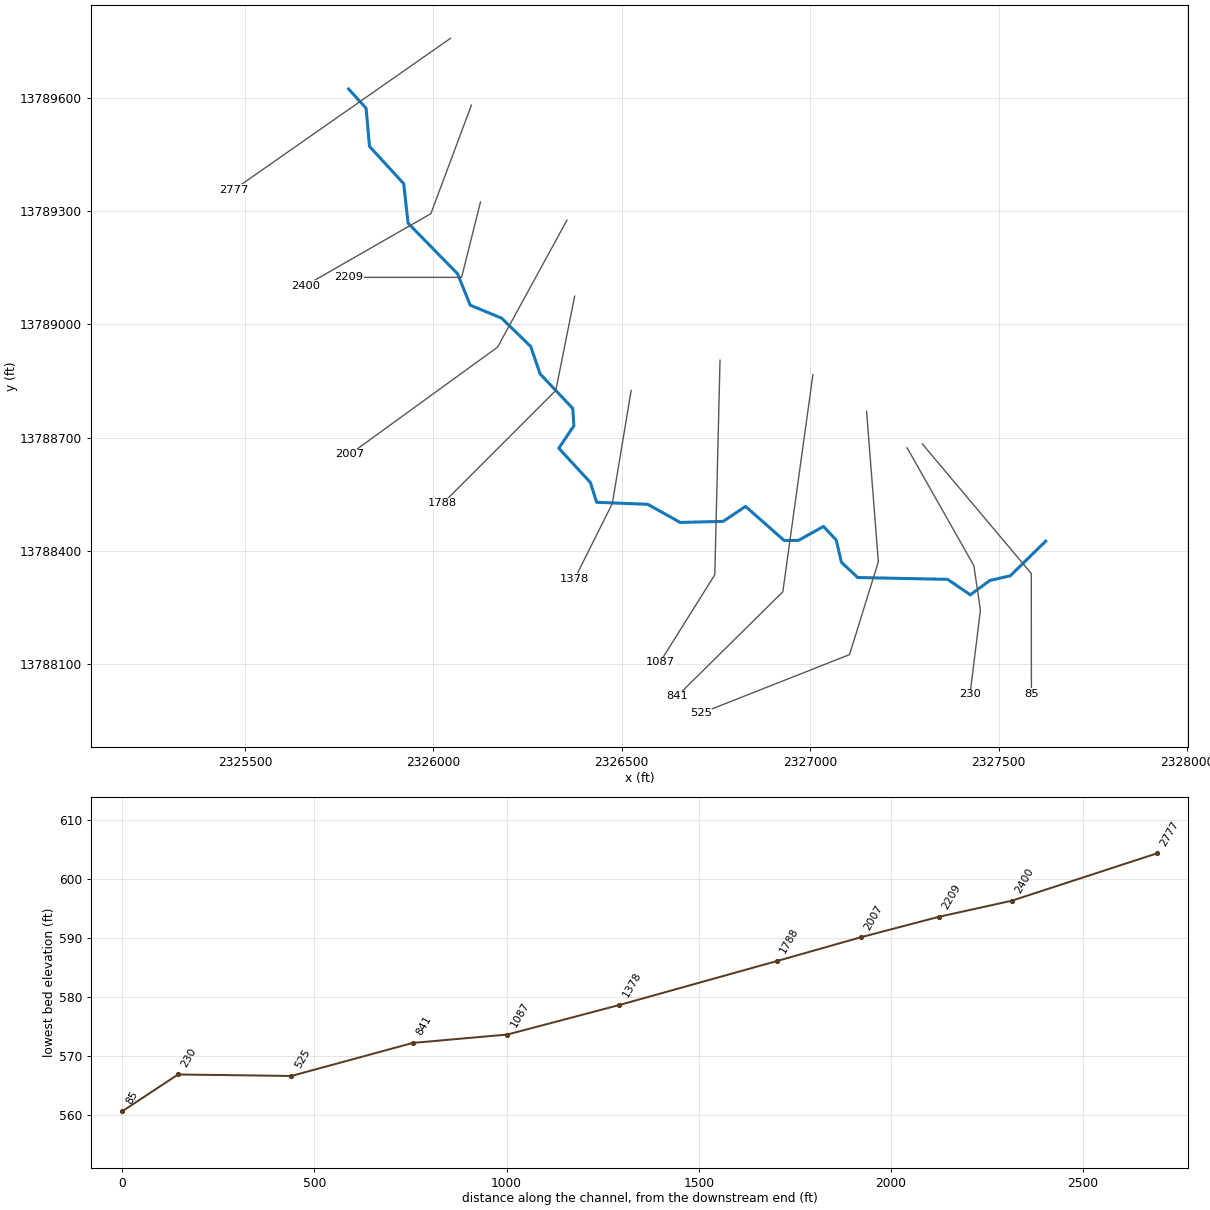
--- MILL TRIBUTARY 22.prj (project) ---

Proj Title=MILL TRIBUTARY 22 Base Level Engineering
Current Plan=p01
Default Exp/Contr=0.3,0.1
English Units
Geom File=g01
Flow File=f01
Plan File=p01
BEGIN DESCRIPTION:
MILL TRIBUTARY 22
END DESCRIPTION:

--- MILL TRIBUTARY 22.p01 (plan) ---

Plan Title=Multiple Run
Short Identifier=Multiple
Geom File=g01
Flow File=f01
Subcritical Flow
K Sum by GR= 0
Std Step Tol= 0.01
Critical Tol= 0.01
Num of Std Step Trials= 20
Max Error Tol= 0.3
Flow Tol Ratio= 0.001
Split Flow NTrial= 30
Split Flow Tol= 0.02
Split Flow Ratio= 0.02
Log Output Level= 0
Friction Slope Method= 1
Unsteady Friction Slope Method= 2
Unsteady Bridges Friction Slope Method= 1
Parabolic Critical Depth
Global Vel Dist=  1 , 1 , 1
Global Log Level= 0
CheckData=True
Encroach Param= -1, 0, 0, 0
BEGIN DESCRIPTION:
Multiple Run
END DESCRIPTION:

--- MILL TRIBUTARY 22.f01 (steady flow) ---

Flow Title=Multiple
Number of Profiles=7
Profile Names=10-year,25-year,50-year,1pct_min,100-year,1pct_plu,500-year
River Rch & RM= MILL TRIBUTARY 2,Reach-1,2777
     231     354     459     291     580    1158     913
Boundary for River Rch & Prof#=MILL TRIBUTARY 2,Reach-1,1
Up Type=0
Dn Type=3
Dn Slope=0.005
Boundary for River Rch & Prof#=MILL TRIBUTARY 2,Reach-1,2
Up Type=0
Dn Type=3
Dn Slope=0.005
Boundary for River Rch & Prof#=MILL TRIBUTARY 2,Reach-1,3
Up Type=0
Dn Type=3
Dn Slope=0.005
Boundary for River Rch & Prof#=MILL TRIBUTARY 2,Reach-1,4
Up Type=0
Dn Type=3
Dn Slope=0.005
Boundary for River Rch & Prof#=MILL TRIBUTARY 2,Reach-1,5
Up Type=0
Dn Type=3
Dn Slope=0.005
Boundary for River Rch & Prof#=MILL TRIBUTARY 2,Reach-1,6
Up Type=0
Dn Type=3
Dn Slope=0.005
Boundary for River Rch & Prof#=MILL TRIBUTARY 2,Reach-1,7
Up Type=0
Dn Type=3
Dn Slope=0.005

--- MILL TRIBUTARY 22.g01 (geometry) ---

Geom Title=Existing Conditions

River Reach=MILL TRIBUTARY 2,Reach-1
Reach XY= 30
      2325775.00     13789625.00      2325821.61     13789573.59
      2325830.52     13789472.57      2325921.37     13789373.50
      2325932.86     13789268.83      2326064.21     13789134.66
      2326097.86     13789051.16      2326181.05     13789016.84
      2326258.36     13788941.71      2326283.18     13788868.96
      2326369.87     13788777.28      2326373.01     13788731.05
      2326332.83     13788671.60      2326416.66     13788580.70
      2326433.30     13788528.08      2326569.05     13788522.72
      2326654.87     13788474.61      2326769.14     13788477.46
      2326828.41     13788517.19      2326931.05     13788426.68
      2326968.96     13788427.00      2327035.37     13788464.02
      2327069.14     13788427.82      2327083.02     13788368.66
      2327126.25     13788328.45      2327364.56     13788323.62
      2327425.01     13788282.53      2327476.65     13788320.55
      2327531.07     13788333.06      2327625.00     13788425.00

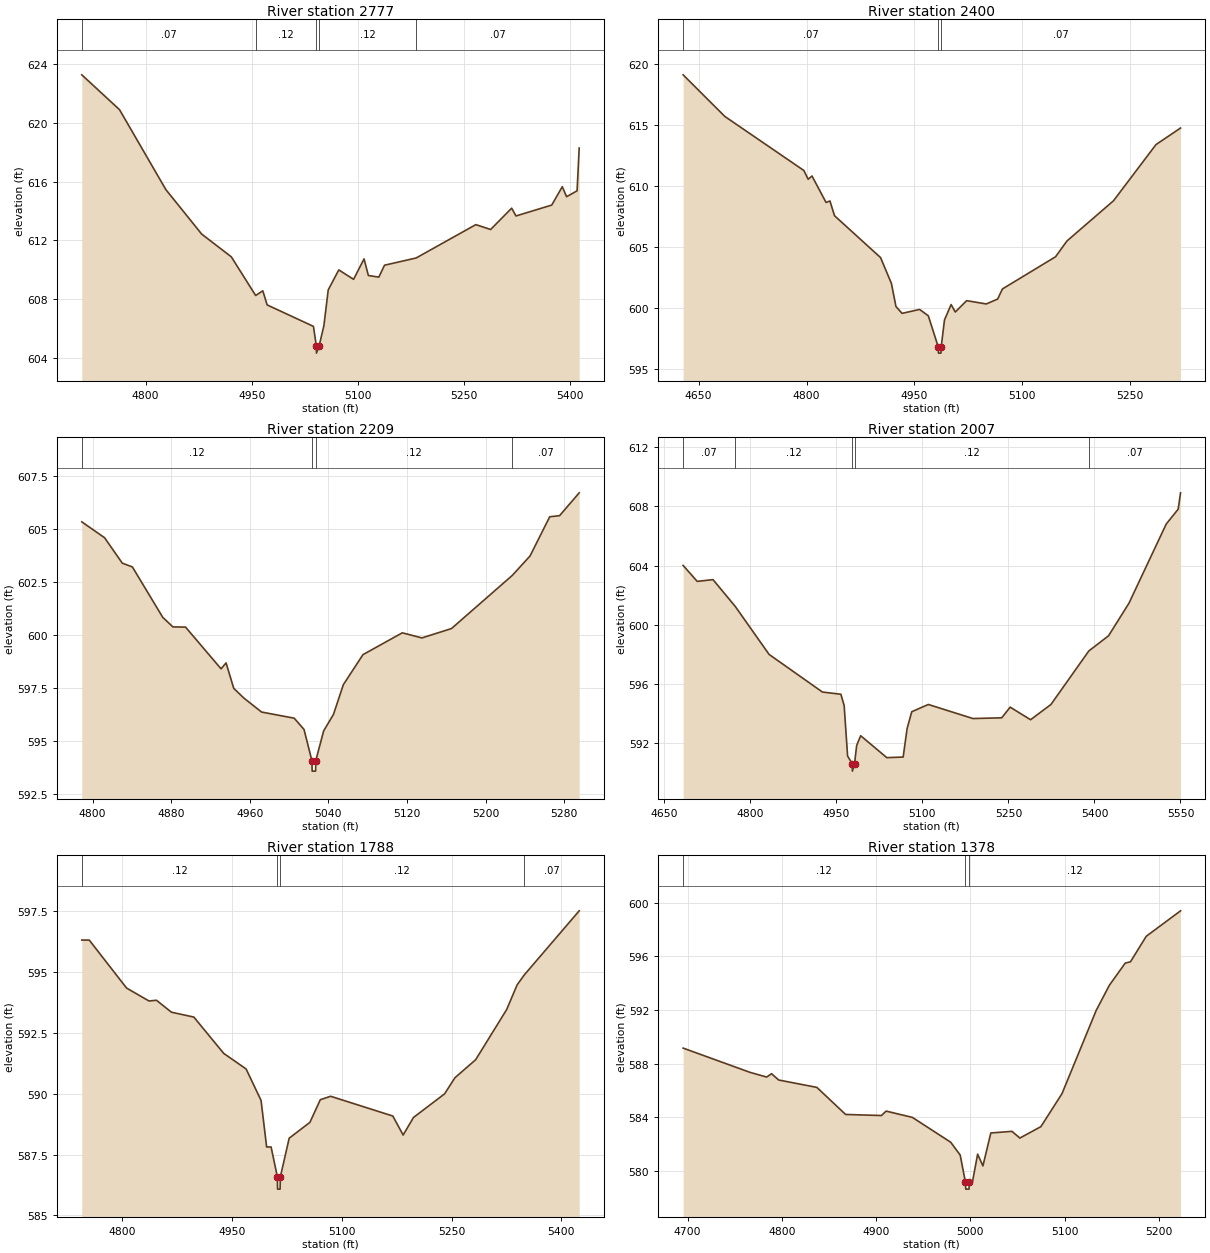
Type RM Length L Ch R = 1,2777,377,377,377
BEGIN DESCRIPTION:
B19519
END DESCRIPTION:
XS GIS Cut Line= 2
      2326045.48     13789759.32      2325469.56     13789356.87
#Sta/Elev= 30
  4710.0  623.26  4763.3  620.89  4828.8  615.45  4879.3  612.43  4921.2  610.88
  4955.6  608.25  4965.7  608.57  4971.8  607.61  5037.2  606.15  5041.3  604.83
  5041.5  604.33  5045.3  604.83  5052.0  606.20  5058.1  608.63  5073.0  609.99
  5093.9  609.35  5108.7  610.74  5114.8  609.61  5129.6  609.50  5137.6  610.31
  5182.2  610.80  5266.6  613.07  5287.5  612.74  5317.2  614.19  5323.3  613.66
  5373.8  614.40  5388.7  615.65  5394.8  614.97  5409.6  615.37  5412.6  618.28
#Mann=5,-1,0
  4710.0    0.07       0  4955.6    0.12       0  5041.3    0.05       0
  5045.3    0.12       0  5182.2    0.07       0
Bank Sta=5041.3,5045.3
Exp/Cntr=0.3,0.1

Type RM Length L Ch R = 1,2400,191,191,191
BEGIN DESCRIPTION:
B19518
END DESCRIPTION:
XS GIS Cut Line= 3
      2326101.06     13789582.27      2325993.40     13789294.04
      2325660.11     13789103.09
#Sta/Elev= 30
  4628.4  619.13  4686.4  615.72  4796.3  611.29  4802.3  610.57  4807.6  610.84
  4827.2  608.67  4832.6  608.79  4839.0  607.58  4903.0  604.15  4918.1  602.03
  4924.4  600.14  4932.9  599.58  4957.3  599.90  4969.4  599.38  4983.3  596.82
  4983.5  596.32  4987.0  596.32  4987.3  596.82  4991.9  599.04  5001.1  600.30
  5006.9  599.69  5022.7  600.62  5050.0  600.35  5065.8  600.75  5072.5  601.58
  5146.4  604.22  5162.2  605.51  5227.0  608.81  5286.0  613.41  5320.2  614.77
#Mann=3,-1,0
  4628.4    0.07       0  4983.3    0.05       0  4987.3    0.07       0
Bank Sta=4983.3,4987.3
Exp/Cntr=0.3,0.1

Type RM Length L Ch R = 1,2209,202,202,202
BEGIN DESCRIPTION:
MILL TRIBUTARY 22 5.0
END DESCRIPTION:
XS GIS Cut Line= 3
      2326124.99     13789324.96      2326075.00     13789125.00
      2325775.01     13789125.00
#Sta/Elev= 30
  4789.1  605.34  4812.3  604.59  4830.3  603.39  4840.6  603.21  4871.5  600.83
  4881.8  600.38  4894.7  600.37  4930.8  598.40  4935.9  598.68  4943.7  597.48
  4954.0  597.02  4972.0  596.36  5005.2  596.07  5015.2  595.54  5023.2  594.07
  5023.5  593.57  5027.0  593.57  5027.2  594.07  5035.2  595.47  5045.2  596.25
  5055.2  597.65  5075.2  599.07  5115.2  600.10  5135.2  599.86  5165.2  600.30
  5227.1  602.81  5245.2  603.73  5265.2  605.58  5275.2  605.63  5295.2  606.71
#Mann=4,-1,0
  4789.1    0.12       0  5023.2    0.05       0  5027.2    0.12       0
  5227.1    0.07       0
Bank Sta=5023.2,5027.2
Exp/Cntr=0.3,0.1

Type RM Length L Ch R = 1,2007,219,219,219
BEGIN DESCRIPTION:
B19517
END DESCRIPTION:
XS GIS Cut Line= 3
      2326354.51     13789276.67      2326170.49     13788939.88
      2325779.07     13788655.84
#Sta/Elev= 30
  4682.7  604.01  4707.3  602.93  4734.8  603.05  4773.8  601.23  4832.6  598.00
  4925.6  595.46  4957.8  595.31  4963.5  594.55  4969.5  591.14  4977.6  590.62
  4977.9  590.12  4981.6  590.62  4985.3  591.85  4992.3  592.51  5037.9  591.03
  5066.4  591.07  5073.3  593.00  5081.4  594.13  5110.3  594.62  5188.1  593.67
  5238.3  593.72  5253.0  594.44  5288.6  593.59  5324.1  594.62  5390.1  598.23
  5424.6  599.26  5460.2  601.46  5525.1  606.80  5546.0  607.81  5550.1  608.91
#Mann=5,-1,0
  4682.7    0.07       0  4773.8    0.12       0  4977.6    0.05       0
  4981.6    0.12       0  5390.1    0.07       0
Bank Sta=4977.6,4981.6
Exp/Cntr=0.3,0.1

Type RM Length L Ch R = 1,1788,410,410,410
BEGIN DESCRIPTION:
MILL TRIBUTARY 22 4.0
END DESCRIPTION:
XS GIS Cut Line= 3
      2326375.00     13789075.01      2326325.00     13788825.00
      2326025.01     13788525.01
#Sta/Elev= 30
  4745.1  596.30  4755.3  596.30  4806.3  594.33  4836.9  593.80  4847.1  593.83
  4867.5  593.34  4898.1  593.14  4938.9  591.65  4969.5  591.01  4989.9  589.72
  4997.5  587.81  5003.6  587.81  5012.2  586.58  5012.4  586.08  5015.9  586.08
  5016.2  586.58  5028.3  588.17  5056.6  588.82  5070.8  589.75  5084.9  589.89
  5169.8  589.08  5183.9  588.30  5198.0  589.02  5240.5  589.99  5254.6  590.65
  5282.9  591.39  5325.3  593.45  5339.5  594.46  5349.3  594.87  5424.3  597.50
#Mann=4,-1,0
  4745.1    0.12       0  5012.2    0.05       0  5016.2    0.12       0
  5349.3    0.07       0
Bank Sta=5012.2,5016.2
Exp/Cntr=0.3,0.1

Type RM Length L Ch R = 1,1378,291,291,291
BEGIN DESCRIPTION:
MILL TRIBUTARY 22 3.0
END DESCRIPTION:
XS GIS Cut Line= 3
      2326525.00     13788825.01      2326475.00     13788525.00
      2326374.98     13788324.96
#Sta/Elev= 30
  4695.3  589.15  4766.3  587.34  4784.0  586.99  4789.1  587.24  4796.7  586.77
  4837.2  586.22  4867.7  584.20  4905.7  584.12  4910.7  584.45  4938.6  583.98
  4979.2  582.13  4989.3  581.17  4994.9  579.13  4995.2  578.63  4998.7  578.63
  4998.9  579.13  5002.2  579.13  5007.8  581.24  5013.4  580.36  5021.8  582.82
  5044.2  582.94  5052.6  582.44  5074.9  583.29  5097.3  585.75  5133.6  591.96
  5147.6  593.84  5164.4  595.49  5170.0  595.59  5186.7  597.49  5223.1  599.39
#Mann=3,-1,0
  4695.3    0.12       0  4994.9    0.05       0  4998.9    0.12       0
Bank Sta=4994.9,4998.9
Exp/Cntr=0.3,0.1

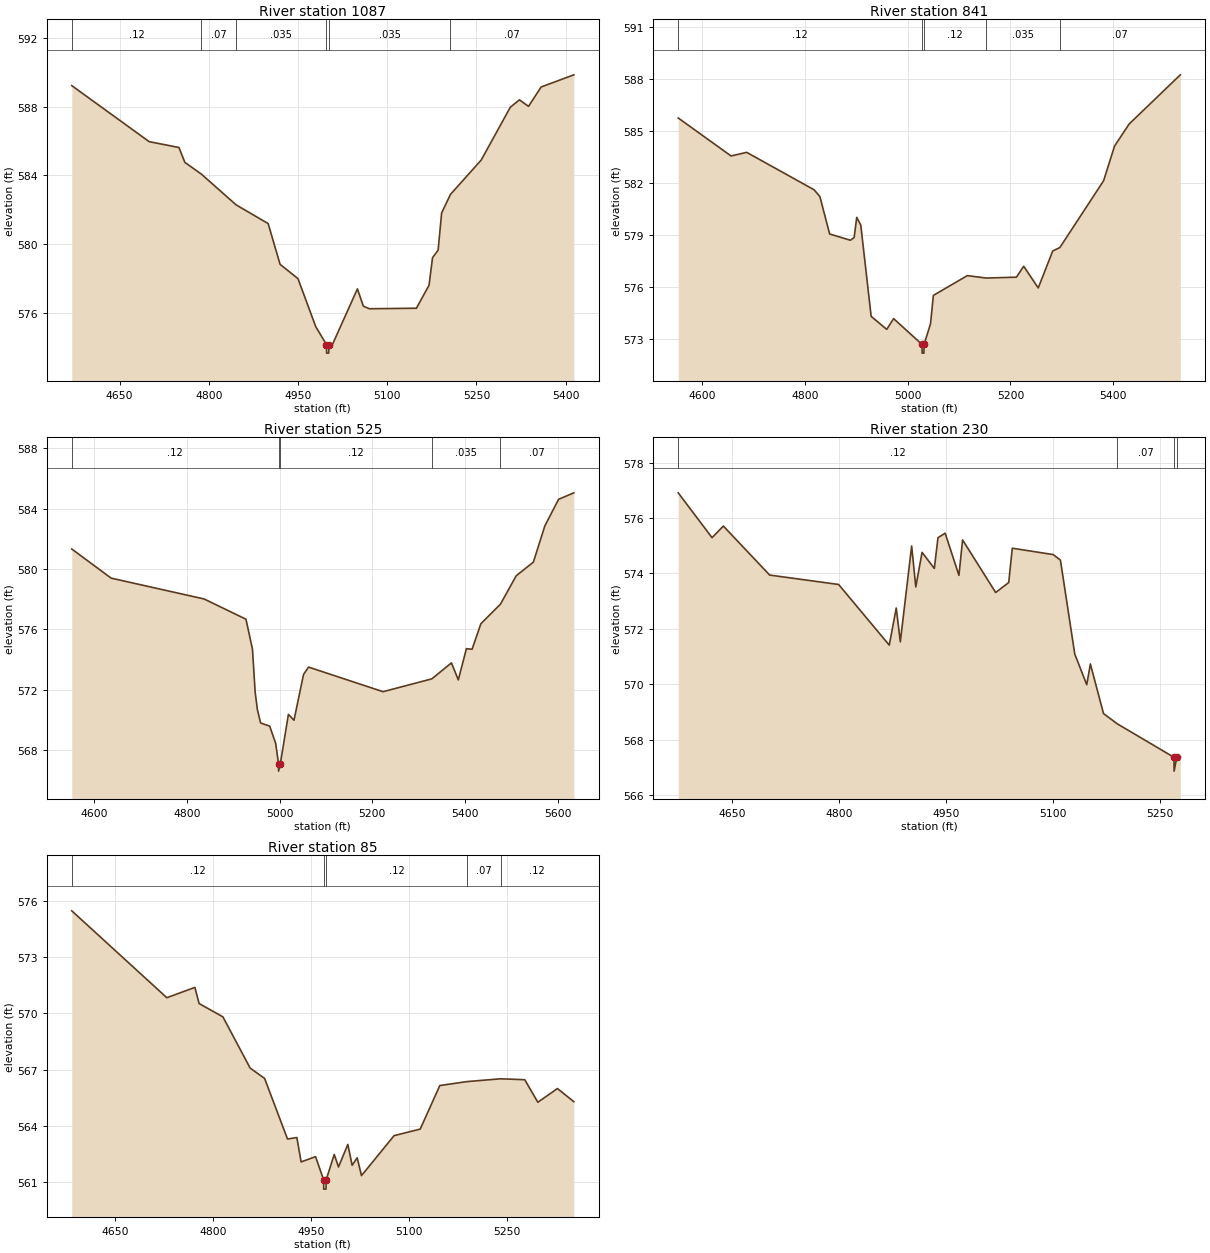
Type RM Length L Ch R = 1,1087,246,246,246
BEGIN DESCRIPTION:
B19516
END DESCRIPTION:
XS GIS Cut Line= 3
      2326760.76     13788905.15      2326746.88     13788335.71
      2326601.03     13788103.05
#Sta/Elev= 30
  4569.6  589.24  4699.8  585.97  4749.8  585.63  4759.8  584.76  4787.4  584.08
  4846.0  582.28  4899.8  581.19  4919.9  578.81  4949.9  577.98  4979.9  575.17
  4997.9  574.13  4998.1  573.63  5001.6  573.63  5001.9  574.13  5008.0  574.14
  5049.9  577.38  5059.9  576.37  5069.9  576.22  5149.1  576.25  5170.3  577.59
  5176.2  579.20  5185.6  579.64  5191.5  581.81  5206.3  582.89  5258.1  584.90
  5307.0  587.98  5322.3  588.41  5337.6  588.03  5358.8  589.16  5413.8  589.87
#Mann=6,-1,0
  4569.6    0.12       0  4787.4    0.07       0  4846.0   0.035       0
  4997.9   0.035       0  5001.9   0.035       0  5206.3    0.07       0
Bank Sta=4997.9,5001.9
Exp/Cntr=0.3,0.1

Type RM Length L Ch R = 1,841,316,316,316
BEGIN DESCRIPTION:
B19515
END DESCRIPTION:
XS GIS Cut Line= 3
      2327007.29     13788866.95      2326927.43     13788290.57
      2326646.17     13788012.78
#Sta/Elev= 30
  4553.5  585.77  4656.4  583.58  4686.7  583.79  4818.0  581.63  4829.2  581.24
  4848.2  579.08  4888.6  578.72  4895.9  578.88  4900.9  580.04  4908.8  579.59
  4929.0  574.33  4959.3  573.58  4972.7  574.20  5028.0  572.71  5028.2  572.21
  5031.7  572.21  5032.0  572.71  5044.5  573.90  5050.1  575.54  5116.2  576.68
  5152.8  576.54  5211.7  576.59  5225.9  577.22  5254.2  575.97  5282.4  578.10
  5296.3  578.30  5381.4  582.15  5402.7  584.15  5431.0  585.42  5530.7  588.26
#Mann=5,-1,0
  4553.5    0.12       0  5028.0    0.05       0  5032.0    0.12       0
  5152.8   0.035       0  5296.3    0.07       0
Bank Sta=5028,5032
Exp/Cntr=0.3,0.1

Type RM Length L Ch R = 1,525,295,295,295
BEGIN DESCRIPTION:
B19514
END DESCRIPTION:
XS GIS Cut Line= 4
      2327149.65     13788769.72      2327180.90     13788370.43
      2327104.51     13788123.90      2326709.39     13787967.93
#Sta/Elev= 30
  4551.4  581.32  4636.4  579.39  4837.0  578.01  4927.3  576.67  4941.3  574.69
  4947.1  571.85  4951.9  570.69  4958.9  569.80  4978.5  569.59  4991.5  568.44
  4997.5  567.11  4997.7  566.61  5001.5  567.11  5018.9  570.37  5030.9  569.98
  5051.5  573.01  5062.3  573.50  5223.1  571.87  5328.4  572.72  5370.7  573.78
  5385.5  572.65  5403.0  574.72  5415.2  574.68  5434.2  576.37  5476.5  577.67
  5510.5  579.55  5547.5  580.45  5572.2  582.85  5601.9  584.61  5634.8  585.04
#Mann=5,-1,0
  4551.4    0.12       0  4997.5    0.05       0  5001.5    0.12       0
  5328.4   0.035       0  5476.5    0.07       0
Bank Sta=4997.5,5001.5
Exp/Cntr=0.3,0.1

Type RM Length L Ch R = 1,230,145,145,145
BEGIN DESCRIPTION:
B19513
END DESCRIPTION:
XS GIS Cut Line= 4
      2327257.32     13788672.47      2327434.38     13788360.01
      2327451.74     13788241.96      2327424.19     13788018.11
#Sta/Elev= 30
  4574.1  576.91  4621.5  575.29  4637.4  575.71  4702.3  573.94  4799.0  573.60
  4870.0  571.41  4879.8  572.75  4885.5  571.53  4901.4  574.99  4907.2  573.51
  4916.0  574.76  4933.2  574.18  4938.3  575.29  4948.4  575.45  4967.7  573.93
  4972.8  575.21  5019.2  573.31  5037.5  573.67  5042.5  574.91  5099.9  574.68
  5110.0  574.48  5130.1  571.09  5146.9  569.98  5152.0  570.73  5170.4  568.94
  5189.6  568.57  5269.2  567.36  5269.4  566.86  5273.2  567.36  5278.1  567.36
#Mann=4,-1,0
  4574.1    0.12       0  5189.6    0.07       0  5269.2    0.05       0
  5273.2    0.07       0
Bank Sta=5269.2,5273.2
Exp/Cntr=0.3,0.1

Type RM Length L Ch R = 1,85,0,0,0
BEGIN DESCRIPTION:
B19512
END DESCRIPTION:
XS GIS Cut Line= 3
      2327297.66     13788682.92      2327586.72     13788339.18
      2327587.15     13788019.91
#Sta/Elev= 30
  4584.2  575.46  4729.7  570.83  4772.6  571.38  4779.1  570.52  4815.5  569.81
  4857.2  567.08  4879.3  566.53  4914.4  563.30  4928.7  563.38  4935.2  562.08
  4957.3  562.36  4969.6  561.13  4969.8  560.63  4973.3  560.63  4973.6  561.13
  4985.9  562.48  4992.4  561.81  5006.7  563.01  5013.3  561.90  5021.0  562.30
  5027.6  561.35  5077.5  563.48  5117.5  563.83  5147.5  566.15  5189.1  566.36
  5240.7  566.51  5277.5  566.46  5297.5  565.26  5327.5  565.99  5352.6  565.29
#Mann=5,-1,0
  4584.2    0.12       0  4969.6    0.05       0  4973.6    0.12       0
  5189.1    0.07       0  5240.7    0.12       0
Bank Sta=4969.6,4973.6
Exp/Cntr=0.3,0.1

Chan Stop Cuts=-1