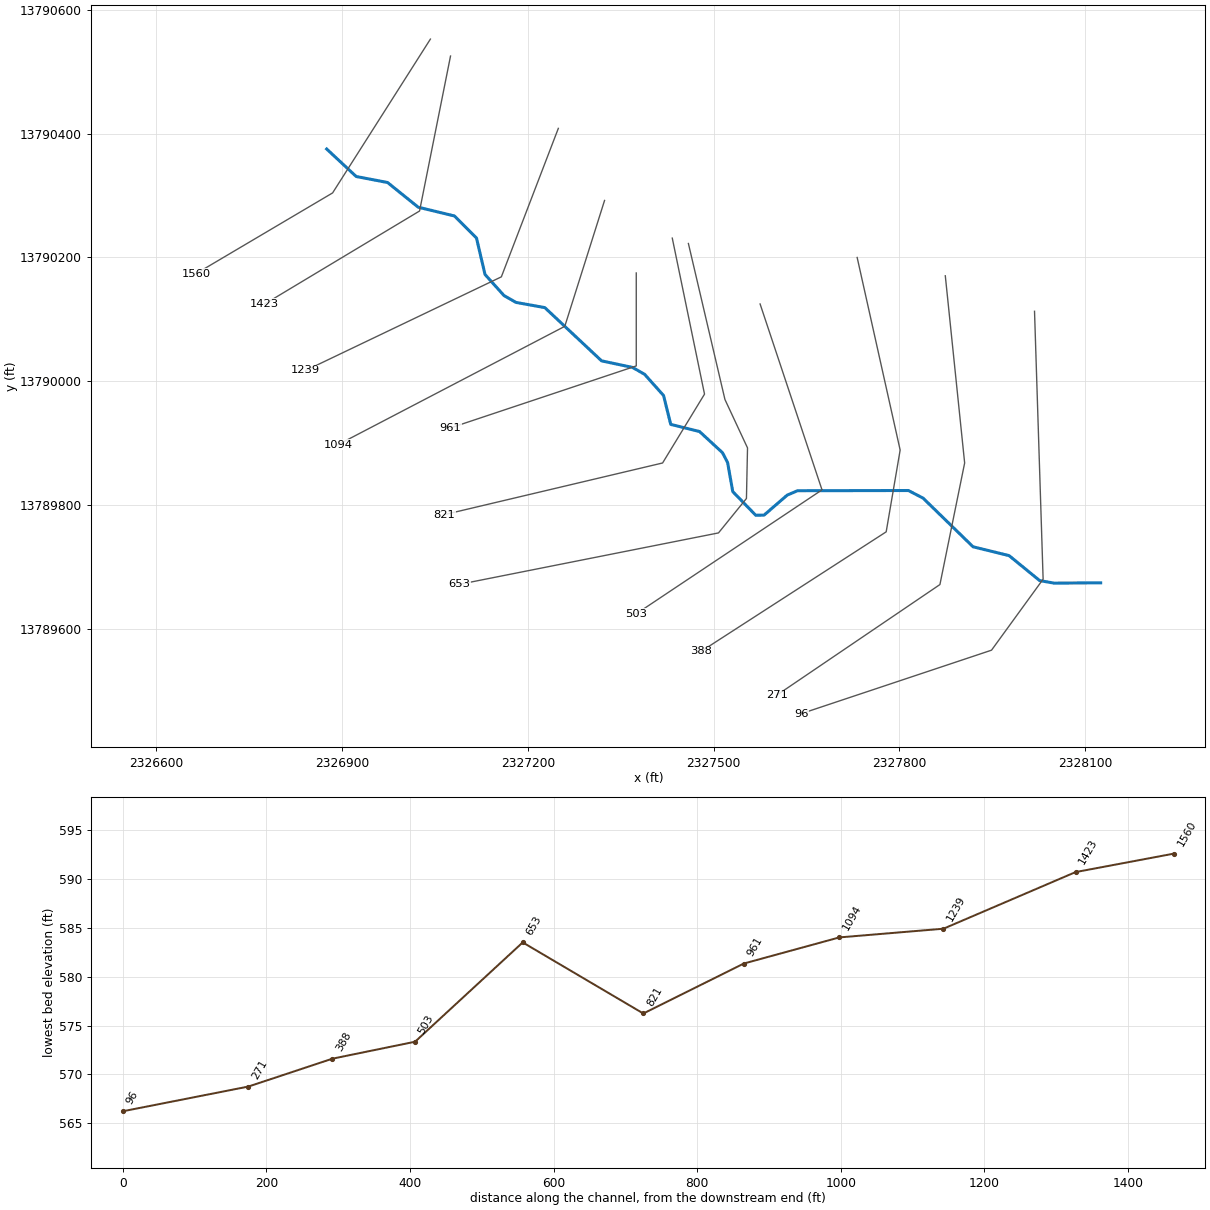
--- MILL TRIBUTARY 23.prj (project) ---

Proj Title=MILL TRIBUTARY 23 Base Level Engineering
Current Plan=p01
Default Exp/Contr=0.3,0.1
English Units
Geom File=g01
Flow File=f01
Plan File=p01
Y Axis Title=Elevation
X Axis Title(PF)=Main Channel Distance
X Axis Title(XS)=Station
BEGIN DESCRIPTION:
MILL TRIBUTARY 23
END DESCRIPTION:
DSS Export Rating Curves= 0
DSS Export Rating Curve Sorted= 0
DSS Export Volume Flow Curves= 0
DXF OffsetX= 0
DXF OffsetY= 0
DXF ScaleX= 1
DXF ScaleY= 10

--- MILL TRIBUTARY 23.p01 (plan) ---

Plan Title=Multiple Run
Short Identifier=Multiple
Geom File=g01
Flow File=f01
Subcritical Flow
K Sum by GR= 0
Std Step Tol= 0.01
Critical Tol= 0.01
Num of Std Step Trials= 20
Max Error Tol= 0.3
Flow Tol Ratio= 0.001
Split Flow NTrial= 30
Split Flow Tol= 0.02
Split Flow Ratio= 0.02
Log Output Level= 0
Friction Slope Method= 1
Unsteady Friction Slope Method= 2
Unsteady Bridges Friction Slope Method= 1
Parabolic Critical Depth
Global Vel Dist=  1 , 1 , 1
Global Log Level= 0
CheckData=True
Encroach Param= -1, 0, 0, 0
BEGIN DESCRIPTION:
Multiple Run
END DESCRIPTION:

--- MILL TRIBUTARY 23.f01 (steady flow) ---

Flow Title=Multiple
Number of Profiles=7
Profile Names=10-year,25-year,50-year,1pct_min,100-year,1pct_plu,500-year
River Rch & RM= MILL TRIBUTARY 2,Reach-1,1560
     157     234     298     185     370     738     561
Boundary for River Rch & Prof#=MILL TRIBUTARY 2,Reach-1,1
Up Type=0
Dn Type=3
Dn Slope=0.005
Boundary for River Rch & Prof#=MILL TRIBUTARY 2,Reach-1,2
Up Type=0
Dn Type=3
Dn Slope=0.005
Boundary for River Rch & Prof#=MILL TRIBUTARY 2,Reach-1,3
Up Type=0
Dn Type=3
Dn Slope=0.005
Boundary for River Rch & Prof#=MILL TRIBUTARY 2,Reach-1,4
Up Type=0
Dn Type=3
Dn Slope=0.005
Boundary for River Rch & Prof#=MILL TRIBUTARY 2,Reach-1,5
Up Type=0
Dn Type=3
Dn Slope=0.005
Boundary for River Rch & Prof#=MILL TRIBUTARY 2,Reach-1,6
Up Type=0
Dn Type=3
Dn Slope=0.005
Boundary for River Rch & Prof#=MILL TRIBUTARY 2,Reach-1,7
Up Type=0
Dn Type=3
Dn Slope=0.005

--- MILL TRIBUTARY 23.g01 (geometry) ---

Geom Title=Existing Conditions
Program Version=4.10

River Reach=MILL TRIBUTARY 2,Reach-1
Reach XY= 30
        2326875.       13790375.      2326922.64     13790330.67
      2326973.33     13790320.96      2327022.83     13790281.11
      2327081.34     13790266.98      2327116.95     13790231.31
      2327130.76     13790172.49      2327161.44     13790138.49
      2327180.87     13790127.46      2327227.26     13790119.12
      2327318.98     13790033.18      2327369.12     13790022.52
      2327388.53     13790011.45      2327419.11     13789977.21
      2327430.66     13789930.66      2327477.21     13789919.11
       2327514.3     13789884.94      2327522.52     13789869.04
      2327530.86     13789822.18      2327567.98     13789784.01
      2327581.38     13789784.22      2327618.79     13789816.52
      2327635.43     13789823.61      2327814.56     13789823.95
      2327838.31      13789811.6      2327918.95     13789733.16
      2327977.18     13789718.89       2328026.5     13789678.63
       2328049.8     13789674.52        2328125.       13789675.

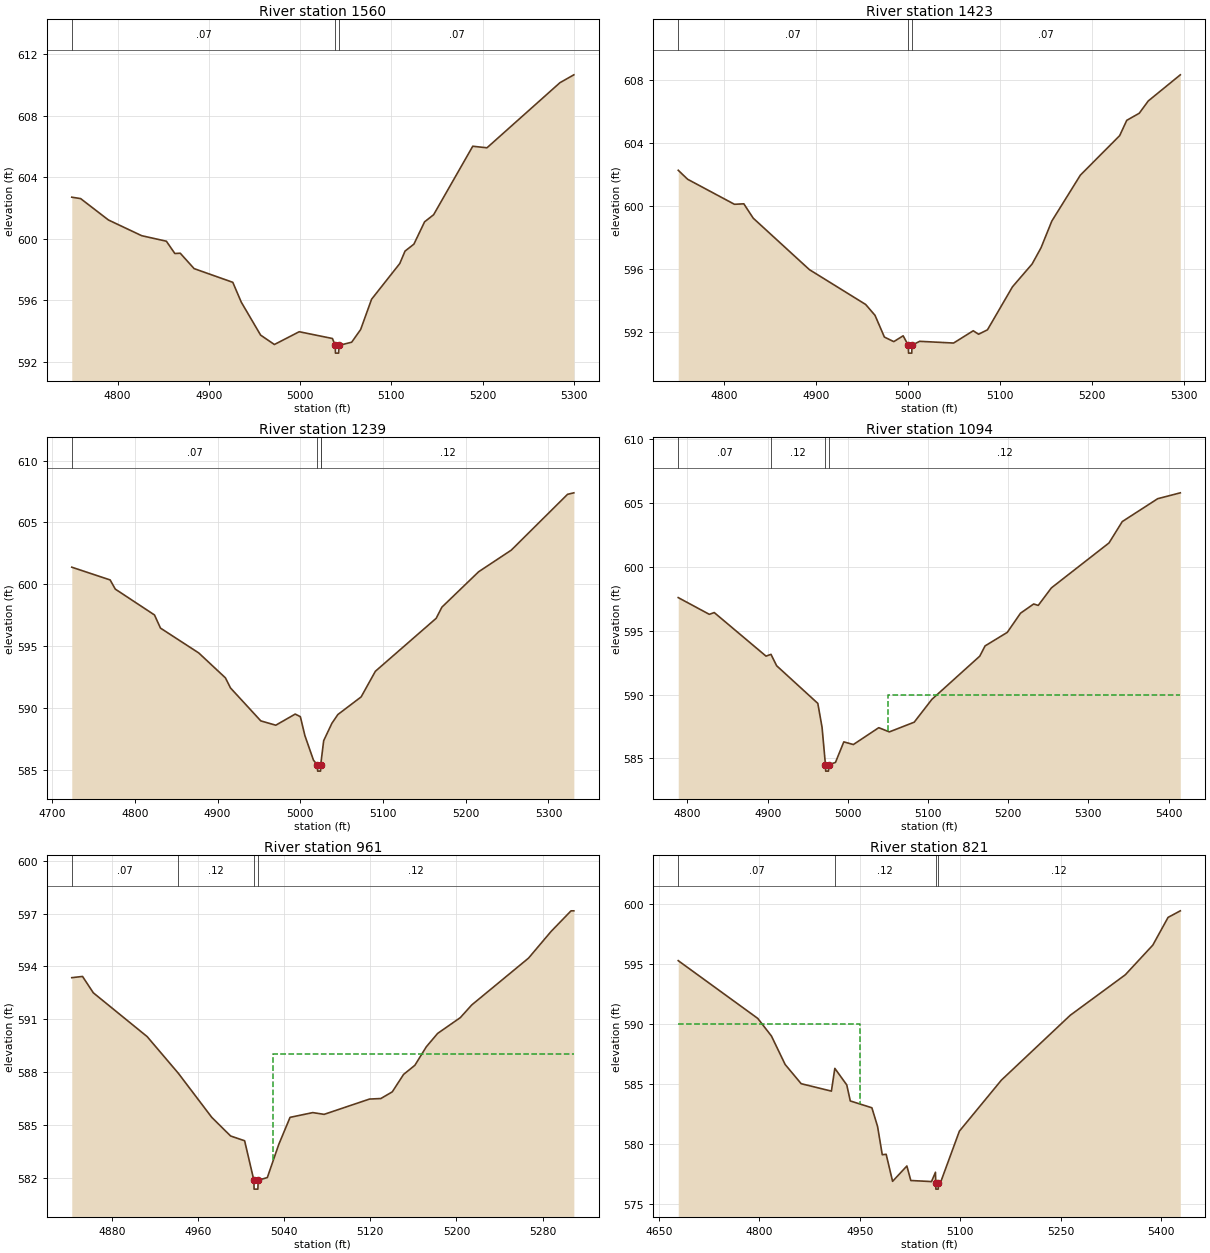
Type RM Length L Ch R = 1 ,1560    ,137,137,137
BEGIN DESCRIPTION:
B19527
END DESCRIPTION:
XS GIS Cut Line= 3
      2327042.52     13790552.39      2326884.55     13790304.16
      2326664.06     13790173.95
#Sta/Elev= 30
  4749.8  602.71  4759.5  602.62    4790  601.23  4826.4  600.21  4853.5  599.85
  4862.8  599.05  4868.7  599.07  4883.9  598.07  4926.3  597.18  4935.6  595.89
  4956.8  593.75  4971.9  593.14  4999.1  593.97  5035.5  593.53  5038.6  593.08
  5038.8  592.58  5042.3  592.58  5042.6  593.08  5056.6  593.29  5066.4  594.11
  5078.4  596.08  5109.3   598.4  5115.1  599.21  5124.8  599.66  5136.5  601.11
  5146.4  601.57  5189.3  606.02  5204.9  605.92  5284.9  610.15  5300.1  610.66
#Mann= 3 ,-1 , 0
  4749.8     .07       0  5038.6     .05       0  5042.6     .07       0
Bank Sta=5038.6,5042.6
XS Rating Curve= 0 ,0
Exp/Cntr=0.3,0.1

Type RM Length L Ch R = 1 ,1423    ,184,184,184
BEGIN DESCRIPTION:
MILL TRIBUTARY 23 3.0
END DESCRIPTION:
XS GIS Cut Line= 3
      2327075.01     13790525.04        2327025.       13790275.
      2326775.04     13790125.02
#Sta/Elev= 30
  4749.7   602.3  4759.9  601.73  4810.9  600.14  4821.1  600.17  4831.3  599.26
  4892.5  595.99  4953.7  593.78  4963.9  593.09  4974.1  591.71  4984.3  591.42
  4994.5  591.79  5000.1  591.19  5000.4  590.69  5003.9  590.69  5004.1  591.19
  5012.5  591.44  5049.4  591.33  5070.8  592.11  5076.6  591.89  5086.3  592.17
  5113.5   594.9  5134.9  596.35  5144.6  597.38  5156.3  599.07  5187.4  601.99
  5230.2   604.5  5237.9  605.47  5251.5  605.92  5261.3   606.7  5296.2  608.36
#Mann= 3 ,-1 , 0
  4749.7     .07       0  5000.1     .05       0  5004.1     .07       0
Bank Sta=5000.1,5004.1
XS Rating Curve= 0 ,0
Exp/Cntr=0.3,0.1

Type RM Length L Ch R = 1 ,1239    ,145,145,145
BEGIN DESCRIPTION:
B19526
END DESCRIPTION:
XS GIS Cut Line= 3
      2327249.13     13790408.33      2327157.12     13790168.74
      2326841.12     13790017.68
#Sta/Elev= 30
  4723.8  601.38  4770.2  600.35  4776.4  599.61  4823.8  597.52    4831  596.46
  4877.3  594.45  4909.5  592.44  4915.7  591.62  4952.3  588.96  4970.4  588.61
  4993.9  589.51  5000.1   589.3  5005.6  587.77    5016  585.78  5020.7   585.4
    5021   584.9  5024.5   584.9  5024.7   585.4  5025.3  585.73  5028.3  587.36
  5038.2  588.76  5045.4  589.47  5073.6   590.9  5090.8  592.97  5164.3  597.25
  5171.2  598.15  5215.6  601.01  5255.1  602.76  5323.1  607.27  5330.7  607.39
#Mann= 4 ,-1 , 0
  4723.8     .07       0  5020.7     .05       0  5024.7     .07       0
  5025.3     .12       0
Bank Sta=5020.7,5024.7
XS Rating Curve= 0 ,0
Exp/Cntr=0.3,0.1

Type RM Length L Ch R = 1 ,1094    ,133,133,133
BEGIN DESCRIPTION:
B19525
END DESCRIPTION:
XS GIS Cut Line= 3
      2327323.79       13790292.      2327259.55     13790088.88
      2326893.19     13789897.88
#Sta/Elev= 30
  4788.5  597.59  4827.3  596.28  4833.4  596.42    4898  593.01  4904.2  593.15
  4911.2  592.26  4962.6  589.31  4967.9  587.43  4972.1  584.51  4972.4  584.01
  4975.9  584.01  4976.1  584.51  4984.6  584.69    4995   586.3  5006.9  586.09
  5038.6  587.41  5051.8  587.08  5082.8  587.84  5104.9  589.63  5164.6  593.01
  5171.2  593.81  5198.9  594.87  5215.4  596.37  5231.8  597.09  5237.5  596.98
  5253.9  598.35  5325.8  601.87  5342.3  603.54  5386.5  605.33  5414.7  605.79
#Mann= 4 ,-1 , 0
  4788.5     .07       0  4904.2     .12       0  4972.1     .05       0
  4976.1     .12       0
#XS Ineff= 2 , 0
       0                    5050       0     590
Permanent Ineff=
       F       F
Bank Sta=4972.1,4976.1
XS Rating Curve= 0 ,0
Exp/Cntr=0.3,0.1

Type RM Length L Ch R = 1 ,961     ,140,140,140
BEGIN DESCRIPTION:
MILL TRIBUTARY 23 2.0
END DESCRIPTION:
XS GIS Cut Line= 3
        2327375.     13790174.99        2327375.       13790025.
      2327075.02     13789925.01
#Sta/Elev= 30
  4842.8  593.36  4852.8  593.43  4862.8   592.5  4912.8  590.01  4941.7  587.93
  4972.8  585.42  4990.3  584.36  5003.3  584.09  5011.9  581.84  5012.1  581.34
  5015.6  581.34  5015.9  581.84  5024.4     582    5035  583.88  5045.5  585.42
  5066.6  585.69  5077.1  585.59  5119.3  586.46  5129.8  586.49  5140.4  586.87
  5150.9  587.86  5161.4  588.38    5172  589.43  5182.5  590.19  5203.6  591.09
  5214.2  591.81  5266.9  594.47  5287.9  595.99  5306.4  597.16    5309  597.16
#Mann= 4 ,-1 , 0
  4842.8     .07       0  4941.7     .12       0  5011.9     .05       0
  5015.9     .12       0
#XS Ineff= 2 , 0
       0                    5030       0     589
Permanent Ineff=
       F       F
Bank Sta=5011.9,5015.9
XS Rating Curve= 0 ,0
Exp/Cntr=0.3,0.1

Type RM Length L Ch R = 1 ,821     ,168,168,168
BEGIN DESCRIPTION:
B19524
END DESCRIPTION:
XS GIS Cut Line= 4
      2327433.16     13790231.25      2327485.24      13789979.5
      2327417.53     13789868.39      2327065.15     13789785.07
#Sta/Elev= 30
  4678.9   595.3  4797.6  590.48    4818  589.01  4838.5  586.63  4862.4  585.03
  4907.5  584.41  4912.6  586.31  4930.4  584.93  4935.7  583.59  4967.9  583.02
  4976.4  581.46  4983.4   579.1  4989.2  579.14  4998.8  576.88  5020.1  578.16
    5026  576.95  5056.9  576.86  5062.8  577.64  5063.2  576.73  5063.4  576.23
  5066.9  576.23  5067.2  576.73    5070  576.73  5098.5  581.07  5161.2  585.33
  5263.9  590.74  5346.1  594.12  5387.2   596.6  5409.9  598.91  5428.2  599.46
#Mann= 4 ,-1 , 0
  4678.9     .07       0  4912.6     .12       0  5063.2     .05       0
  5067.2     .12       0
#XS Ineff= 2 , 0
       0    4950     590               0
Permanent Ineff=
       F       F
Bank Sta=5063.2,5067.2
XS Rating Curve= 0 ,0
Exp/Cntr=0.3,0.1

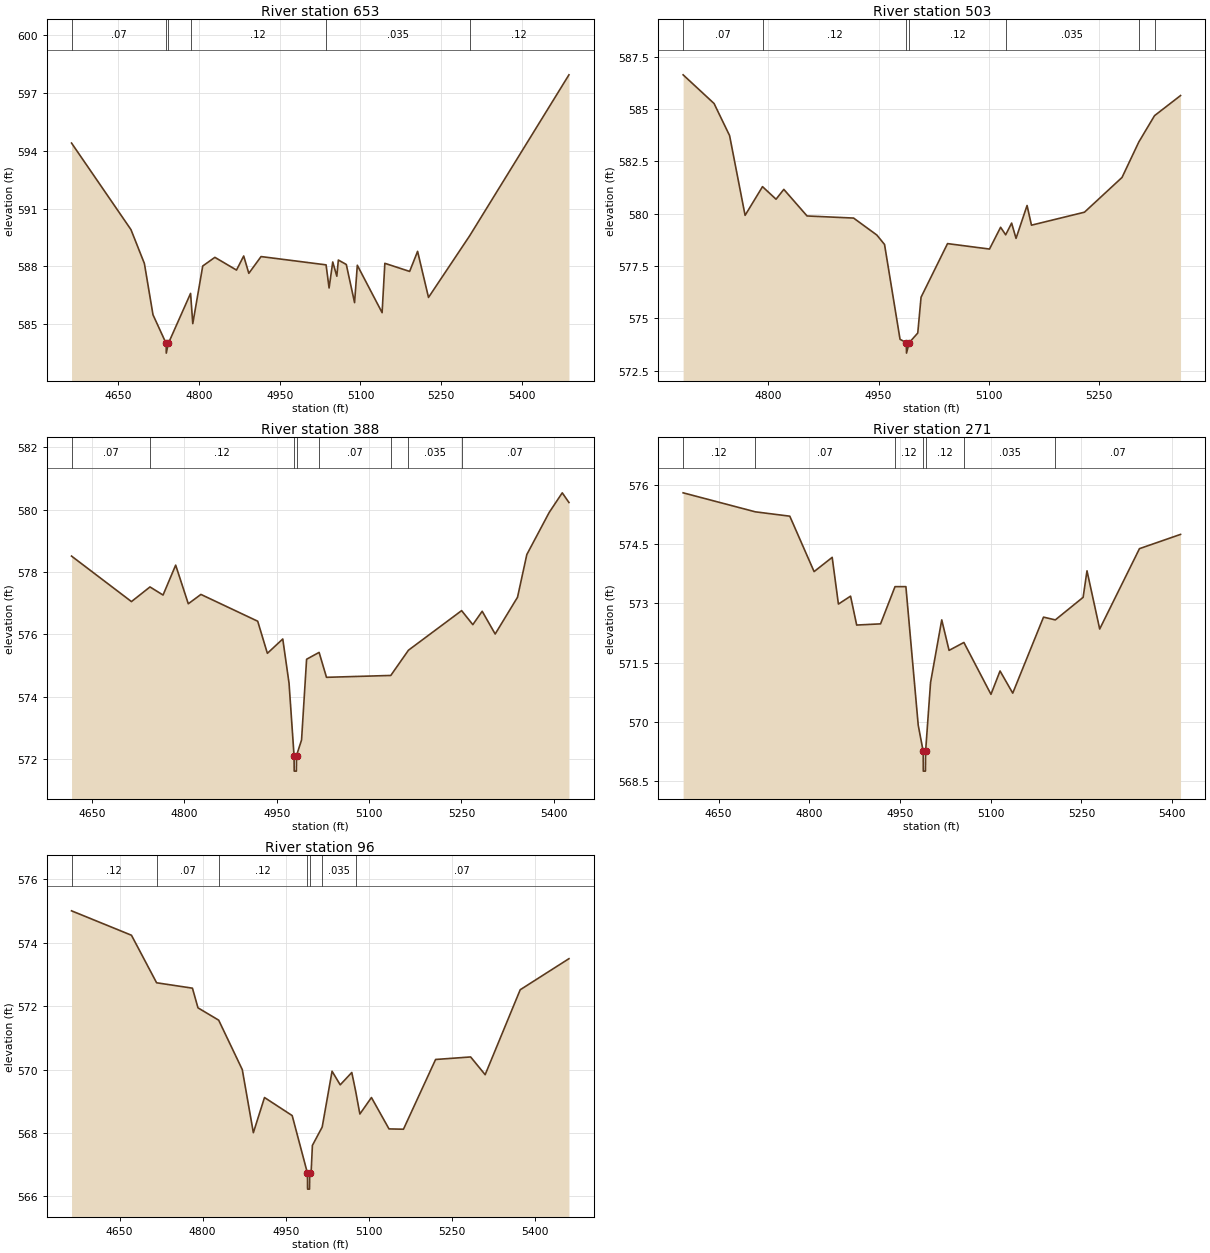
Type RM Length L Ch R = 1 ,653     ,150,150,150
BEGIN DESCRIPTION:
B19523
END DESCRIPTION:
XS GIS Cut Line= 6
       2327459.2     13790222.54      2327518.23     13789970.82
      2327554.69      13789892.7      2327552.95      13789811.1
      2327507.81     13789755.54      2327088.84     13789672.44
#Sta/Elev= 30
  4562.7   594.4  4673.2  589.91  4698.2  588.15  4714.2  585.49  4738.7     584
  4738.9   583.5  4742.7     584  4784.1   586.6  4788.2  585.03  4806.7  588.02
  4829.3  588.47  4869.5  587.81  4882.9  588.54  4892.4  587.64  4915.2  588.51
  5036.1  588.08  5041.7  586.88  5048.5  588.23  5056.1  587.49  5058.9  588.33
  5073.7   588.1  5089.1  586.12  5094.2  588.06  5140.3   585.6  5145.4  588.16
  5191.5  587.74  5206.3  588.78  5226.6  586.39  5303.2  589.59  5487.8  597.94
#Mann= 6 ,-1 , 0
  4562.7     .07       0  4738.7     .05       0  4742.7     .07       0
  4784.1     .12       0  5036.1    .035       0  5303.2     .12       0
Bank Sta=4738.7,4742.7
XS Rating Curve= 0 ,0
Exp/Cntr=0.3,0.1

Type RM Length L Ch R = 1 ,503     ,115,115,115
BEGIN DESCRIPTION:
MILL TRIBUTARY 23 1.0
END DESCRIPTION:
XS GIS Cut Line= 3
      2327575.01     13790124.96        2327675.       13789825.
      2327375.03     13789625.02
#Sta/Elev= 30
  4684.2  586.63  4726.3  585.26  4747.4  583.73  4768.5  579.92  4792.2  581.29
  4810.6  580.69  4821.2  581.16  4852.8  579.89  4916.1  579.79  4947.7  578.98
  4958.2  578.53  4979.3     574  4987.8  573.84  4988.1  573.34  4991.8  573.84
  5003.4   574.3  5007.9  576.01  5043.9  578.57    5101  578.31  5116.1  579.35
    5123  578.99  5131.1  579.55  5137.1  578.82  5152.1  580.39  5158.1  579.45
  5230.2  580.07  5281.3  581.73  5304.1  583.42  5325.5  584.68  5360.9  585.64
#Mann= 7 ,-1 , 0
  4684.2     .07       0  4792.2     .12       0  4987.8     .05       0
  4991.8     .12       0    5123    .035       0  5304.1     .07       0
  5325.5    .035       0
Bank Sta=4987.8,4991.8
XS Rating Curve= 0 ,0
Exp/Cntr=0.3,0.1

Type RM Length L Ch R = 1 ,388     ,117,117,117
BEGIN DESCRIPTION:
B19522
END DESCRIPTION:
XS GIS Cut Line= 4
      2327731.77       13790200.      2327801.22     13789889.22
      2327778.65     13789757.28      2327480.03     13789564.57
#Sta/Elev= 30
  4616.9  578.51  4714.2  577.05  4744.3  577.52  4765.5  577.26    4786  578.22
  4806.5  576.98    4827  577.28  4919.2  576.42  4934.9  575.39  4959.9  575.85
  4970.1  574.43  4978.2  572.11  4978.5  571.61    4982  571.61  4982.2  572.11
  4990.4  572.61  4998.6   575.2  5018.9  575.42  5030.9  574.62  5135.3  574.68
    5164  575.49  5250.3  576.76  5268.5  576.31  5283.7  576.74  5304.8  576.01
  5341.1  577.19  5356.2  578.56  5392.5  579.91  5413.7  580.54  5424.6  580.23
#Mann= 8 ,-1 , 0
  4616.9     .07       0  4744.3     .12       0  4978.2     .05       0
  4982.2     .12       0  5018.9     .07       0  5135.3     .12       0
    5164    .035       0  5250.3     .07       0
Bank Sta=4978.2,4982.2
XS Rating Curve= 0 ,0
Exp/Cntr=0.3,0.1

Type RM Length L Ch R = 1 ,271     ,175,175,175
BEGIN DESCRIPTION:
B19521
END DESCRIPTION:
XS GIS Cut Line= 4
      2327874.13     13790170.45      2327905.38     13789868.39
      2327865.45     13789672.21       2327601.6     13789493.41
#Sta/Elev= 30
  4591.2  575.79  4710.6  575.31  4767.6   575.2  4807.8   573.8  4837.7  574.16
    4848  572.98  4868.1  573.18  4878.2  572.45  4917.7  572.48  4941.6  573.42
  4959.6  573.42    4980  569.92  4988.2  569.26  4988.4  568.76  4991.9  568.76
  4992.2  569.26  5000.4     571  5018.9  572.58    5031  571.81  5055.5  572.01
  5100.3   570.7  5115.3  571.29  5136.3  570.73  5187.2  572.65  5206.7  572.58
  5252.7  573.15  5259.1  573.82  5280.1  572.35  5345.9  574.38  5413.8  574.74
#Mann= 7 ,-1 , 0
  4591.2     .12       0  4710.6     .07       0  4941.6     .12       0
  4988.2     .05       0  4992.2     .12       0  5055.5    .035       0
  5206.7     .07       0
Bank Sta=4988.2,4992.2
XS Rating Curve= 0 ,0
Exp/Cntr=0.3,0.1

Type RM Length L Ch R = 1 ,96      ,0,0,0
BEGIN DESCRIPTION:
B19520
END DESCRIPTION:
XS GIS Cut Line= 4
      2328018.23     13790113.18      2328032.12     13789680.89
      2327948.78     13789566.31       2327641.5     13789463.88
#Sta/Elev= 30
  4563.3  575.01  4671.5  574.24  4716.9  572.74  4781.6  572.57  4791.6  571.95
    4829  571.56  4871.6     570  4891.6  568.01  4911.7  569.12  4961.7  568.55
  4989.3  566.73  4989.5  566.23    4993  566.23  4993.3  566.73  4995.8  566.73
  4998.2  567.61  5015.9  568.19  5033.7  569.95  5048.4  569.52  5069.3  569.91
  5076.3  569.32  5083.9   568.6  5104.8  569.12  5136.5  568.13  5162.6  568.12
  5220.6  570.32  5283.9   570.4  5310.1  569.84  5373.4  572.52  5461.4   573.5
#Mann= 7 ,-1 , 0
  4563.3     .12       0  4716.9     .07       0    4829     .12       0
  4989.3     .05       0  4993.3     .12       0  5015.9    .035       0
  5076.3     .07       0
Bank Sta=4989.3,4993.3
XS Rating Curve= 0 ,0
Exp/Cntr=0.3,0.1

Chan Stop Cuts=-1
Use User Specified Reach Order=0
Composite Channel Slope=5