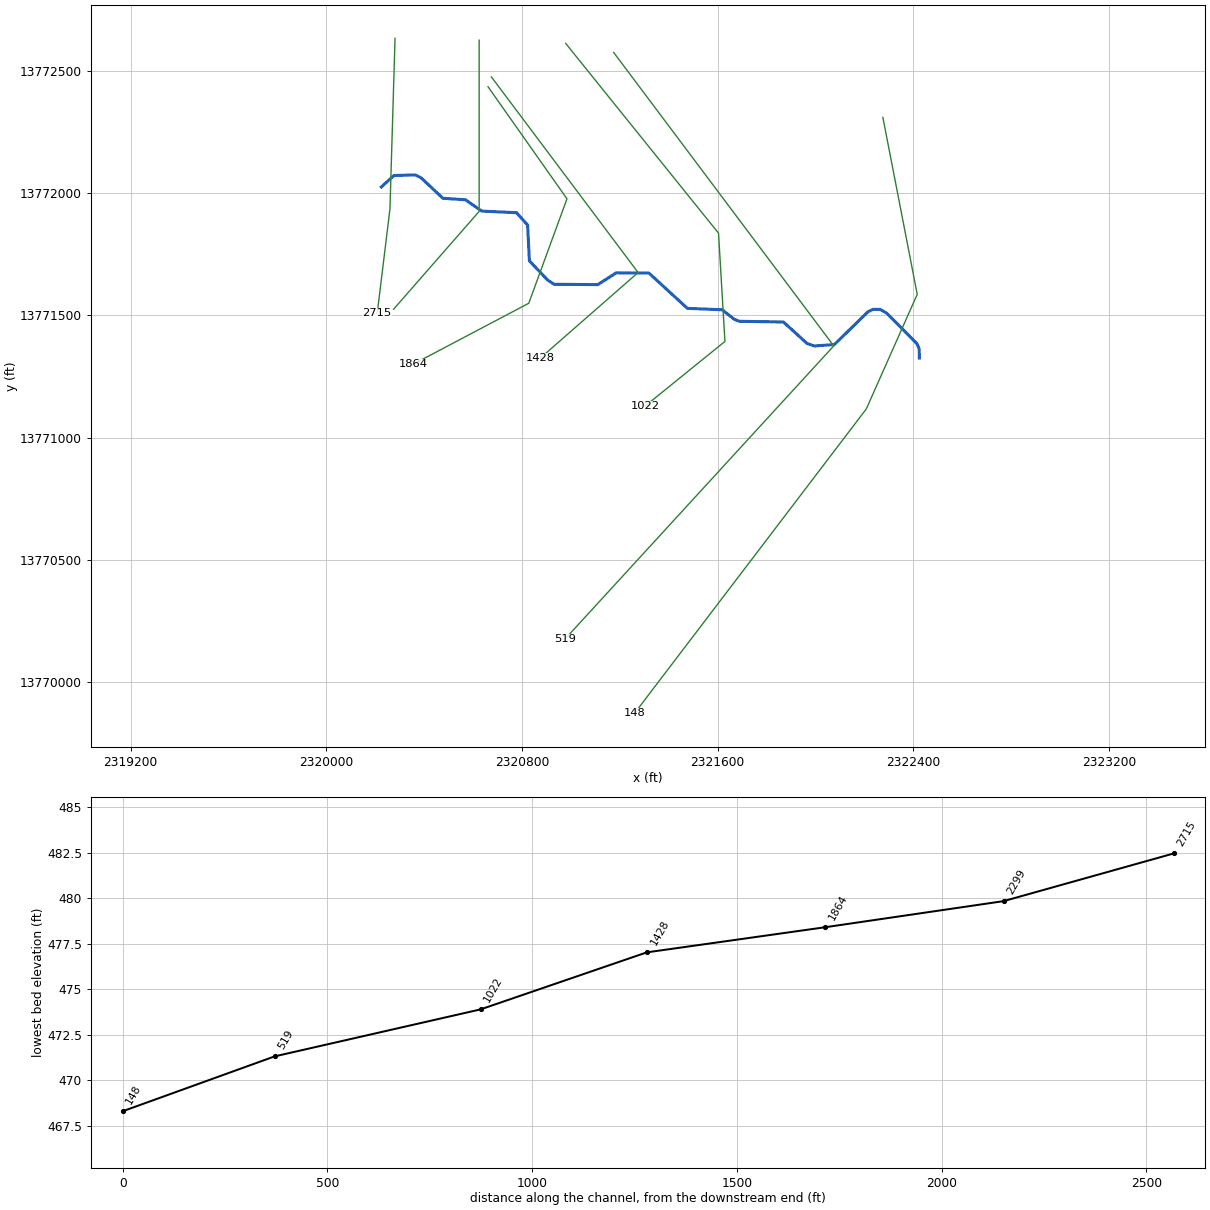
--- MILL TRIBUTARY 5.prj (project) ---

Proj Title=MILL TRIBUTARY 5 Base Level Engineering
Current Plan=p01
Default Exp/Contr=0.3,0.1
English Units
Geom File=g01
Flow File=f01
Plan File=p01
BEGIN DESCRIPTION:
MILL TRIBUTARY 5
END DESCRIPTION:

--- MILL TRIBUTARY 5.p01 (plan) ---

Plan Title=Multiple Run
Short Identifier=Multiple
Geom File=g01
Flow File=f01
Subcritical Flow
K Sum by GR= 0
Std Step Tol= 0.01
Critical Tol= 0.01
Num of Std Step Trials= 20
Max Error Tol= 0.3
Flow Tol Ratio= 0.001
Split Flow NTrial= 30
Split Flow Tol= 0.02
Split Flow Ratio= 0.02
Log Output Level= 0
Friction Slope Method= 1
Unsteady Friction Slope Method= 2
Unsteady Bridges Friction Slope Method= 1
Parabolic Critical Depth
Global Vel Dist=  1 , 1 , 1
Global Log Level= 0
CheckData=True
Encroach Param= -1, 0, 0, 0
BEGIN DESCRIPTION:
Multiple Run
END DESCRIPTION:

--- MILL TRIBUTARY 5.f01 (steady flow) ---

Flow Title=Multiple
Number of Profiles=7
Profile Names=10-year,25-year,50-year,1pct_min,100-year,1pct_plu,500-year
River Rch & RM= MILL TRIBUTARY 5,Reach-1,2715
     806    1323    1798    1183    2360    4708    4028
Boundary for River Rch & Prof#=MILL TRIBUTARY 5,Reach-1,1
Up Type=0
Dn Type=3
Dn Slope=0.005
Boundary for River Rch & Prof#=MILL TRIBUTARY 5,Reach-1,2
Up Type=0
Dn Type=3
Dn Slope=0.005
Boundary for River Rch & Prof#=MILL TRIBUTARY 5,Reach-1,3
Up Type=0
Dn Type=3
Dn Slope=0.005
Boundary for River Rch & Prof#=MILL TRIBUTARY 5,Reach-1,4
Up Type=0
Dn Type=3
Dn Slope=0.005
Boundary for River Rch & Prof#=MILL TRIBUTARY 5,Reach-1,5
Up Type=0
Dn Type=3
Dn Slope=0.005
Boundary for River Rch & Prof#=MILL TRIBUTARY 5,Reach-1,6
Up Type=0
Dn Type=3
Dn Slope=0.005
Boundary for River Rch & Prof#=MILL TRIBUTARY 5,Reach-1,7
Up Type=0
Dn Type=3
Dn Slope=0.005

--- MILL TRIBUTARY 5.g01 (geometry) ---

Geom Title=Existing Conditions

River Reach=MILL TRIBUTARY 5,Reach-1
Reach XY= 30
      2320225.00     13772025.00      2320276.41     13772071.82
      2320364.53     13772074.07      2320388.30     13772061.63
      2320476.50     13771978.62      2320569.02     13771972.64
      2320635.51     13771926.23      2320777.74     13771919.65
      2320823.02     13771869.35      2320830.46     13771722.54
      2320904.79     13771644.59      2320930.84     13771627.05
      2321109.78     13771625.52      2321185.51     13771673.79
      2321319.14     13771672.95      2321476.47     13771528.54
      2321619.06     13771522.73      2321668.94     13771483.14
      2321690.22     13771475.52      2321869.14     13771472.93
      2321965.22     13771385.46      2321995.06     13771374.79
      2322077.43     13771380.40      2322215.32     13771514.83
      2322235.64     13771524.45      2322264.36     13771524.45
      2322291.67     13771508.79      2322414.49     13771384.79
      2322424.41     13771363.16      2322425.00     13771325.00

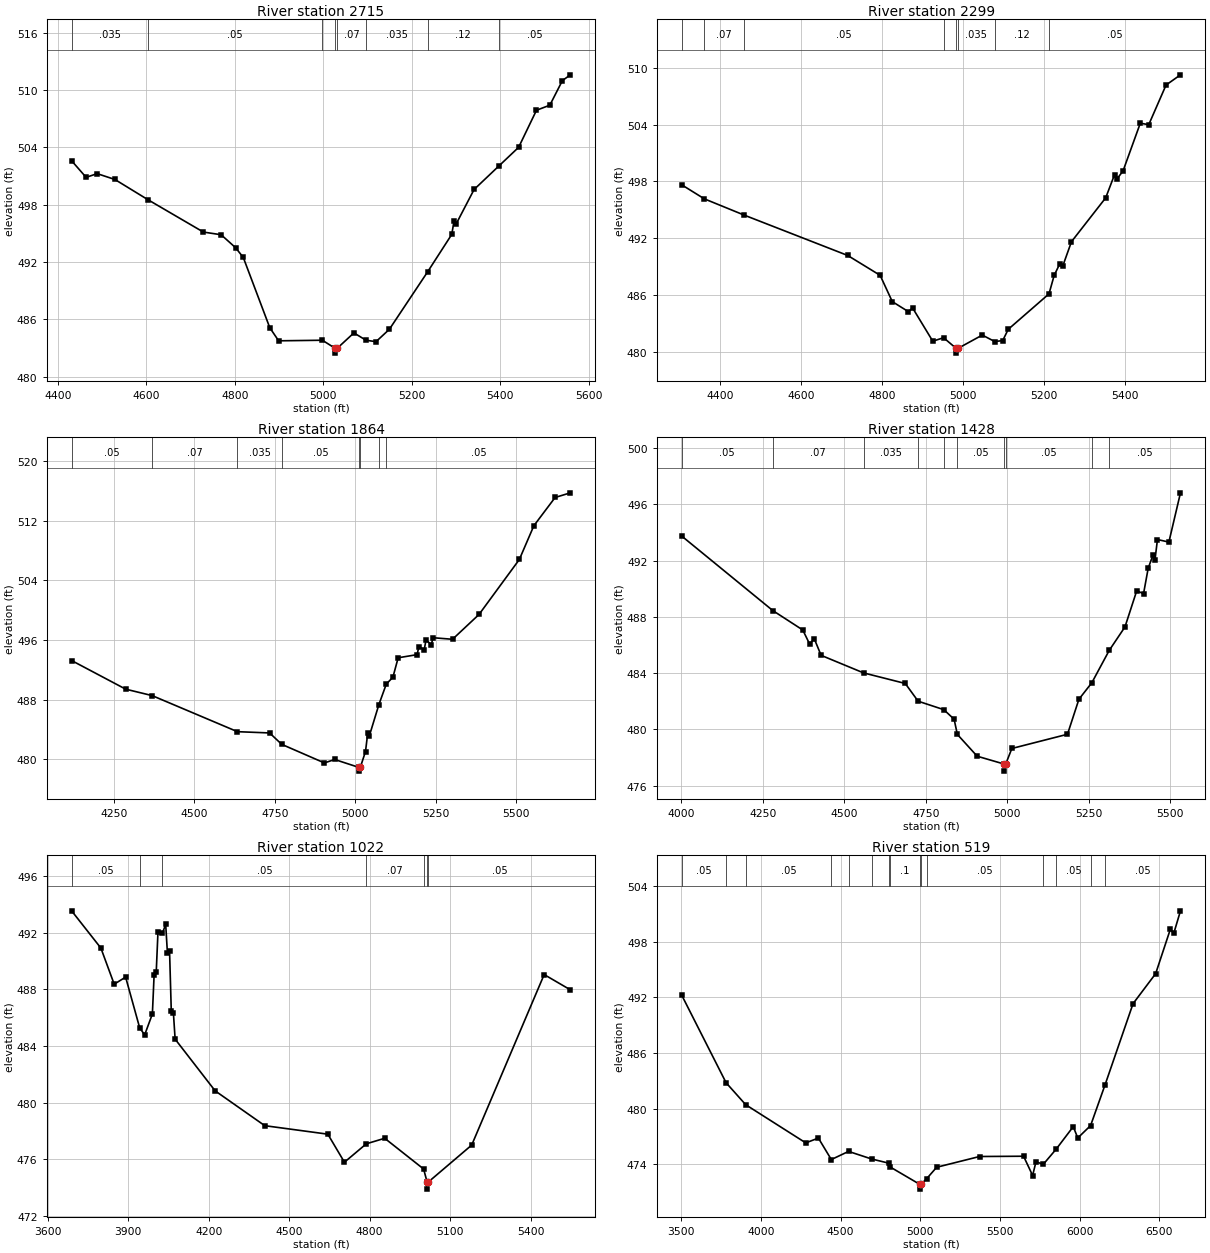
Type RM Length L Ch R = 1,2715,416,416,416
BEGIN DESCRIPTION:
B19531
END DESCRIPTION:
XS GIS Cut Line= 3
      2320280.98     13772632.71      2320260.15     13771934.80
      2320208.20     13771508.88
#Sta/Elev= 30
  4431.2  502.61  4464.0  500.87  4488.9  501.26  4529.0  500.65  4603.7  498.53
  4729.0  495.14  4769.1  494.86  4801.6  493.51  4819.1  492.49  4879.1  485.12
  4899.1  483.75  4997.9  483.81  5027.0  482.96  5027.3  482.46  5031.3  482.96
  5069.2  484.58  5096.5  483.81  5119.2  483.66  5149.4  484.96  5236.0  490.99
  5290.4  494.90  5295.6  496.35  5300.7  496.03  5340.8  499.60  5397.0  502.07
  5441.5  504.02  5481.8  507.90  5512.0  508.43  5540.4  511.01  5558.5  511.61
#Mann=8,-1,0
  4431.2   0.035       0  4603.7    0.05       0  4997.9    0.07       0
  5027.0    0.05       0  5031.3    0.07       0  5096.5   0.035       0
  5236.0    0.12       0  5397.0    0.05       0
Bank Sta=5027,5031.3
Exp/Cntr=0.3,0.1

Type RM Length L Ch R = 1,2299,435,435,435
BEGIN DESCRIPTION:
MILL TRIBUTARY 5 3.0
END DESCRIPTION:
XS GIS Cut Line= 3
      2320625.00     13772624.98      2320625.00     13771925.00
      2320274.99     13771524.99
#Sta/Elev= 30
  4304.6  497.65  4360.6  496.16  4459.0  494.44  4714.6  490.17  4794.6  488.07
  4824.6  485.29  4864.6  484.22  4874.6  484.63  4924.6  481.10  4951.2  481.47
  4982.4  480.34  4982.7  479.84  4986.7  480.34  5046.8  481.75  5077.3  481.07
  5097.1  481.16  5110.9  482.36  5211.5  486.11  5224.3  488.07  5238.5  489.32
  5245.2  489.02  5267.0  491.63  5351.5  496.27  5373.3  498.72  5380.0  498.31
  5394.2  499.10  5436.9  504.16  5457.8  504.01  5500.5  508.20  5536.1  509.28
#Mann=8,-1,0
  4304.6   0.035       0  4360.6    0.07       0  4459.0    0.05       0
  4951.2   0.035       0  4982.4   0.035       0  4986.7   0.035       0
  5077.3    0.12       0  5211.5    0.05       0
Bank Sta=4982.4,4986.7
Exp/Cntr=0.3,0.1

Type RM Length L Ch R = 1,1864,436,436,436
BEGIN DESCRIPTION:
B19530
END DESCRIPTION:
XS GIS Cut Line= 4
      2320661.18     13772434.81      2320984.10     13771976.47
      2320827.85     13771549.38      2320354.51     13771299.71
#Sta/Elev= 30
  4118.7  493.24  4286.9  489.40  4368.9  488.54  4634.2  483.70  4734.2  483.53
  4771.9  482.00  4904.5  479.51  4936.5  479.97  5011.8  478.91  5012.0  478.41
  5016.1  478.91  5032.3  481.04  5039.1  483.46  5044.4  483.16  5073.8  487.32
  5097.0  490.09  5117.5  491.00  5133.8  493.61  5192.7  494.03  5198.3  495.12
  5214.7  494.67  5220.4  495.99  5236.7  495.37  5242.4  496.30  5302.8  496.09
  5385.2  499.42  5510.5  506.79  5555.7  511.32  5621.8  515.11  5669.3  515.73
#Mann=8,-1,0
  4118.7    0.05       0  4368.9    0.07       0  4634.2   0.035       0
  4771.9    0.05       0  5011.8    0.05       0  5016.1    0.05       0
  5073.8    0.12       0  5097.0    0.05       0
Bank Sta=5011.8,5016.1
Exp/Cntr=0.3,0.1

Type RM Length L Ch R = 1,1428,406,406,406
BEGIN DESCRIPTION:
MILL TRIBUTARY 5 2.0
END DESCRIPTION:
XS GIS Cut Line= 3
      2320675.00     13772475.01      2321275.00     13771675.00
      2320875.01     13771325.01
#Sta/Elev= 30
  4000.6  493.74  4280.5  488.44  4372.5  487.06  4393.3  486.07  4407.9  486.43
  4428.7  485.26  4559.2  484.01  4687.1  483.26  4726.6  482.00  4805.3  481.40
  4837.1  480.72  4847.0  479.64  4907.9  478.09  4991.1  477.53  4991.4  477.03
  4995.5  477.53  5014.4  478.64  5185.2  479.65  5220.3  482.14  5259.9  483.31
  5313.3  485.61  5361.7  487.28  5397.8  489.85  5418.7  489.64  5432.9  491.44
  5447.2  492.36  5453.8  492.04  5461.4  493.49  5496.5  493.31  5532.1  496.81
#Mann=10,-1,0
  4000.6    0.05       0  4280.5    0.07       0  4559.2   0.035       0
  4726.6    0.05       0  4805.3    0.12       0  4847.0    0.05       0
  4991.1    0.05       0  4995.5    0.05       0  5259.9    0.12       0
  5313.3    0.05       0
Bank Sta=4991.1,4995.5
Exp/Cntr=0.3,0.1

Type RM Length L Ch R = 1,1022,503,503,503
BEGIN DESCRIPTION:
B19529
END DESCRIPTION:
XS GIS Cut Line= 4
      2320978.92     13772611.86      2321603.90     13771835.84
      2321629.94     13771393.13      2321303.39     13771128.78
#Sta/Elev= 30
  3688.8  493.55  3798.0  490.92  3847.6  488.37  3890.2  488.87  3942.6  485.29
  3961.2  484.79  3990.0  486.27  3996.4  489.00  4004.4  489.24  4010.8  492.04
  4027.5  491.97  4039.6  492.60  4046.0  490.59  4054.0  490.74  4060.4  486.51
  4068.3  486.37  4074.8  484.49  4224.0  480.84  4409.1  478.38  4644.2  477.78
  4706.1  475.80  4787.7  477.10  4856.3  477.49  5001.4  475.32  5014.4  474.40
  5014.7  473.90  5018.8  474.40  5180.7  477.01  5450.9  489.05  5548.8  487.97
#Mann=7,-1,0
  3688.8    0.05       0  3942.6    0.07       0  4027.5    0.05       0
  4787.7    0.07       0  5001.4    0.05       0  5014.4    0.05       0
  5018.8    0.05       0
Bank Sta=5014.4,5018.8
Exp/Cntr=0.3,0.1

Type RM Length L Ch R = 1,519,371,371,371
BEGIN DESCRIPTION:
MILL TRIBUTARY 5 1.0
END DESCRIPTION:
XS GIS Cut Line= 3
      2321174.97     13772575.04      2322075.00     13771375.00
      2320975.02     13770175.02
#Sta/Elev= 30
  3503.9  492.26  3782.5  482.80  3905.4  480.43  4282.1  476.31  4361.2  476.83
  4442.3  474.51  4550.4  475.39  4695.4  474.57  4802.8  474.12  4812.4  473.70
  4998.6  471.82  4998.9  471.32  5003.0  471.82  5039.9  472.44  5102.9  473.68
  5371.8  474.84  5648.0  474.87  5704.7  472.79  5725.7  474.27  5771.7  474.00
  5852.1  475.63  5959.4  478.06  5987.8  476.84  6068.2  478.18  6159.2  482.59
  6334.3  491.33  6476.1  494.57  6568.0  499.35  6589.6  498.91  6631.8  501.35
#Mann=15,-1,0
  3503.9    0.05       0  3782.5    0.07       0  3905.4    0.05       0
  4442.3    0.07       0  4550.4    0.05       0  4695.4     0.1       0
  4802.8    0.05       0  4812.4     0.1       0  4998.6    0.05       0
  5003.0     0.1       0  5039.9    0.05       0  5771.7    0.07       0
  5852.1    0.05       0  6068.2    0.07       0  6159.2    0.05       0
Bank Sta=4998.6,5003
Exp/Cntr=0.3,0.1

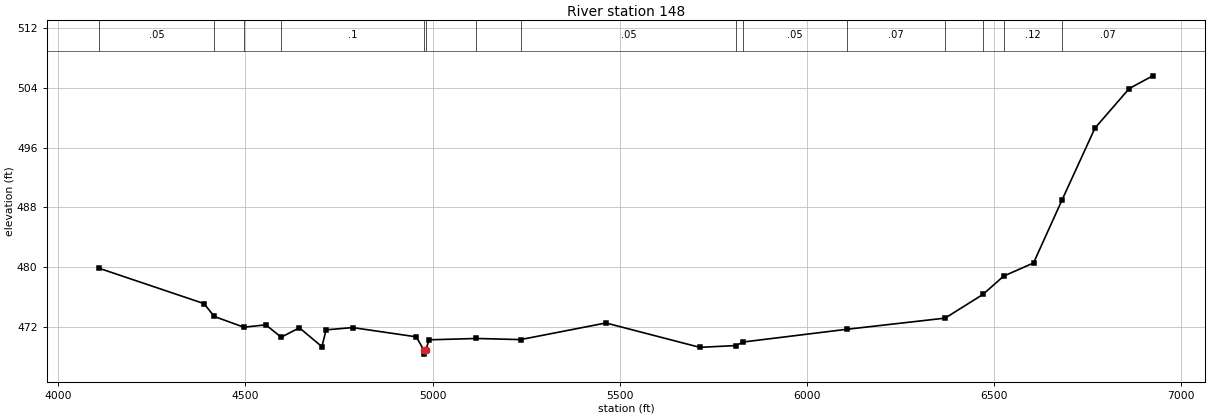
Type RM Length L Ch R = 1,148,0,0,0
BEGIN DESCRIPTION:
B19528
END DESCRIPTION:
XS GIS Cut Line= 4
      2322275.77     13772309.82      2322416.40     13771585.84
      2322208.06     13771117.09      2321260.14     13769872.30
#Sta/Elev= 30
  4109.4  479.82  4389.0  475.09  4416.7  473.36  4495.7  471.92  4554.3  472.24
  4595.4  470.58  4644.0  471.84  4704.3  469.31  4715.3  471.57  4786.6  471.87
  4956.5  470.63  4976.8  468.81  4977.1  468.31  4981.5  468.81  4990.7  470.23
  5117.3  470.41  5235.1  470.26  5463.1  472.49  5714.0  469.22  5811.4  469.46
  5829.2  469.93  6108.1  471.65  6369.6  473.14  6470.7  476.32  6526.1  478.78
  6605.9  480.54  6682.6  489.05  6770.1  498.64  6861.6  503.94  6924.5  505.65
#Mann=15,-1,0
  4109.4    0.05       0  4416.7    0.07       0  4495.7    0.12       0
  4595.4     0.1       0  4976.8    0.05       0  4981.5     0.1       0
  5117.3    0.07       0  5235.1    0.05       0  5811.4    0.07       0
  5829.2    0.05       0  6108.1    0.07       0  6369.6    0.12       0
  6470.7    0.07       0  6526.1    0.12       0  6682.6    0.07       0
Bank Sta=4976.8,4981.5
Exp/Cntr=0.3,0.1

Chan Stop Cuts=-1