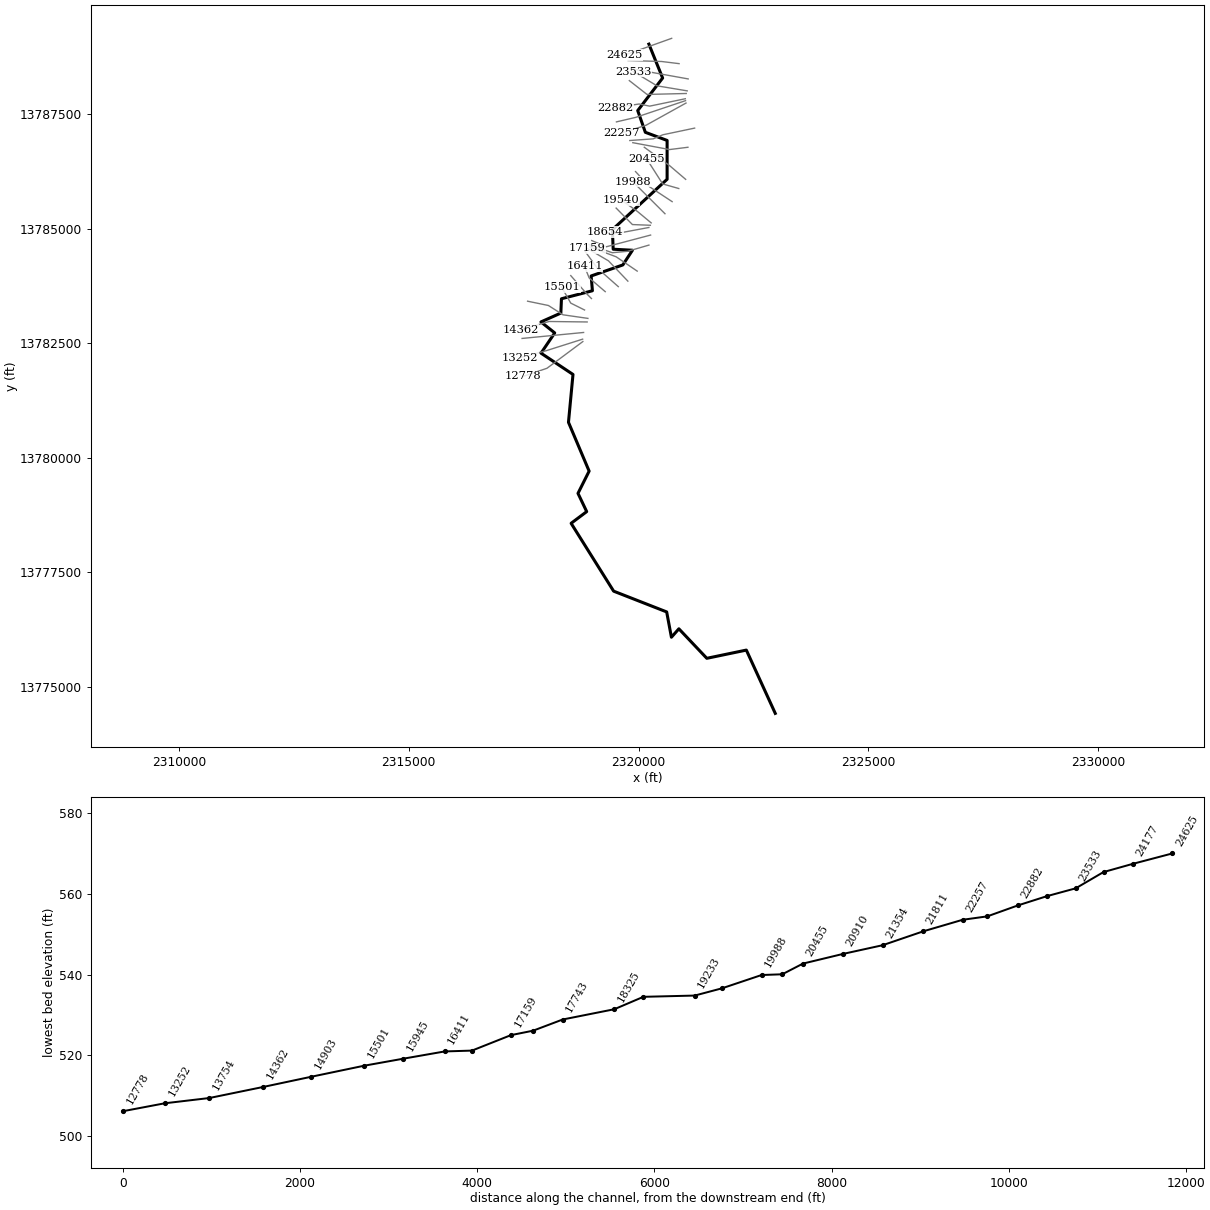
--- MILL TRIBUTARY 7.prj (project) ---

Proj Title=MILL TRIBUTARY 7 Base Level Engineering
Current Plan=p01
Default Exp/Contr=0.3,0.1
English Units
Geom File=g01
Flow File=f01
Plan File=p01
Y Axis Title=Elevation
X Axis Title(PF)=Main Channel Distance
X Axis Title(XS)=Station
BEGIN DESCRIPTION:
MILL TRIBUTARY 7
END DESCRIPTION:
DSS Export Rating Curves= 0
DSS Export Rating Curve Sorted= 0
DSS Export Volume Flow Curves= 0
DXF OffsetX= 0
DXF OffsetY= 0
DXF ScaleX= 1
DXF ScaleY= 10

--- MILL TRIBUTARY 7.p01 (plan) ---

Plan Title=Multiple Run
Short Identifier=Multiple
Geom File=g01
Flow File=f01
Subcritical Flow
K Sum by GR= 0
Std Step Tol= 0.01
Critical Tol= 0.01
Num of Std Step Trials= 20
Max Error Tol= 0.3
Flow Tol Ratio= 0.001
Split Flow NTrial= 30
Split Flow Tol= 0.02
Split Flow Ratio= 0.02
Log Output Level= 0
Friction Slope Method= 1
Unsteady Friction Slope Method= 2
Unsteady Bridges Friction Slope Method= 1
Parabolic Critical Depth
Global Vel Dist=  1 , 1 , 1
Global Log Level= 0
CheckData=True
Encroach Param= -1, 0, 0, 0
BEGIN DESCRIPTION:
Multiple Run
END DESCRIPTION:

--- MILL TRIBUTARY 7.f01 (steady flow) ---

Flow Title=Multiple
Number of Profiles=7
Profile Names=10-year,25-year,50-year,1pct_min,100-year,1pct_plu,500-year
River Rch & RM= MILL TRIBUTARY 7,Reach-1,24625
     643    1054    1432     944    1884    3758    3226
River Rch & RM= MILL TRIBUTARY 7,Reach-1,22882
    1020    1704    2343    1559    3111    6207    5434
River Rch & RM= MILL TRIBUTARY 7,Reach-1,14903
    1219    2049    2829    1888    3767    7516    6622
River Rch & RM= MILL TRIBUTARY 7,Reach-1,10967
    1391    2354    3265    2188    4366    8712    7744
River Rch & RM= MILL TRIBUTARY 7,Reach-1,10655
    1505    2550    3539    2372    4734    9445    8400
River Rch & RM= MILL TRIBUTARY 7,Reach-1,8108
    1577    2677    3720    2496    4979    9935    8851
River Rch & RM= MILL TRIBUTARY 7,Reach-1,7217
    1747    2974    4140    2781    5549   11071    9889
River Rch & RM= MILL TRIBUTARY 7,Reach-1,4156
    1901    3238    4509    3028    6042   12055   10765
Boundary for River Rch & Prof#=MILL TRIBUTARY 7,Reach-1,1
Up Type=0
Dn Type=3
Dn Slope=0.005
Boundary for River Rch & Prof#=MILL TRIBUTARY 7,Reach-1,2
Up Type=0
Dn Type=3
Dn Slope=0.005
Boundary for River Rch & Prof#=MILL TRIBUTARY 7,Reach-1,3
Up Type=0
Dn Type=3
Dn Slope=0.005
Boundary for River Rch & Prof#=MILL TRIBUTARY 7,Reach-1,4
Up Type=0
Dn Type=3
Dn Slope=0.005
Boundary for River Rch & Prof#=MILL TRIBUTARY 7,Reach-1,5
Up Type=0
Dn Type=3
Dn Slope=0.005
Boundary for River Rch & Prof#=MILL TRIBUTARY 7,Reach-1,6
Up Type=0
Dn Type=3
Dn Slope=0.005
Boundary for River Rch & Prof#=MILL TRIBUTARY 7,Reach-1,7
Up Type=0
Dn Type=3
Dn Slope=0.005

--- MILL TRIBUTARY 7.g01 (geometry) ---

Geom Title=Existing Conditions
Program Version=4.10

River Reach=MILL TRIBUTARY 7,Reach-1
Reach XY= 30
        2320225.       13789025.      2320523.97     13788285.43
      2319981.99     13787575.22      2320147.84     13787101.42
      2320621.56     13786923.78      2320621.46     13786076.47
      2319430.46     13784977.45      2319448.01     13784550.53
      2319867.33     13784528.66      2319658.42     13784207.98
       2318968.5     13783967.27      2318996.07     13783644.78
      2318322.42     13783470.05      2318308.97     13783157.87
      2317875.86     13782964.68      2318175.85     13782724.99
      2317877.46     13782283.17      2318573.38     13781818.97
        2318475.       13780775.      2318924.63     13779709.72
       2318682.1       13779225.      2318871.52     13778826.44
      2318532.58     13778571.68      2319457.69     13777091.27
      2320611.89     13776638.24      2320715.14     13776085.89
      2320877.28     13776269.95       2321485.5     13775626.22
      2322345.66      13775805.6        2322975.       13774425.

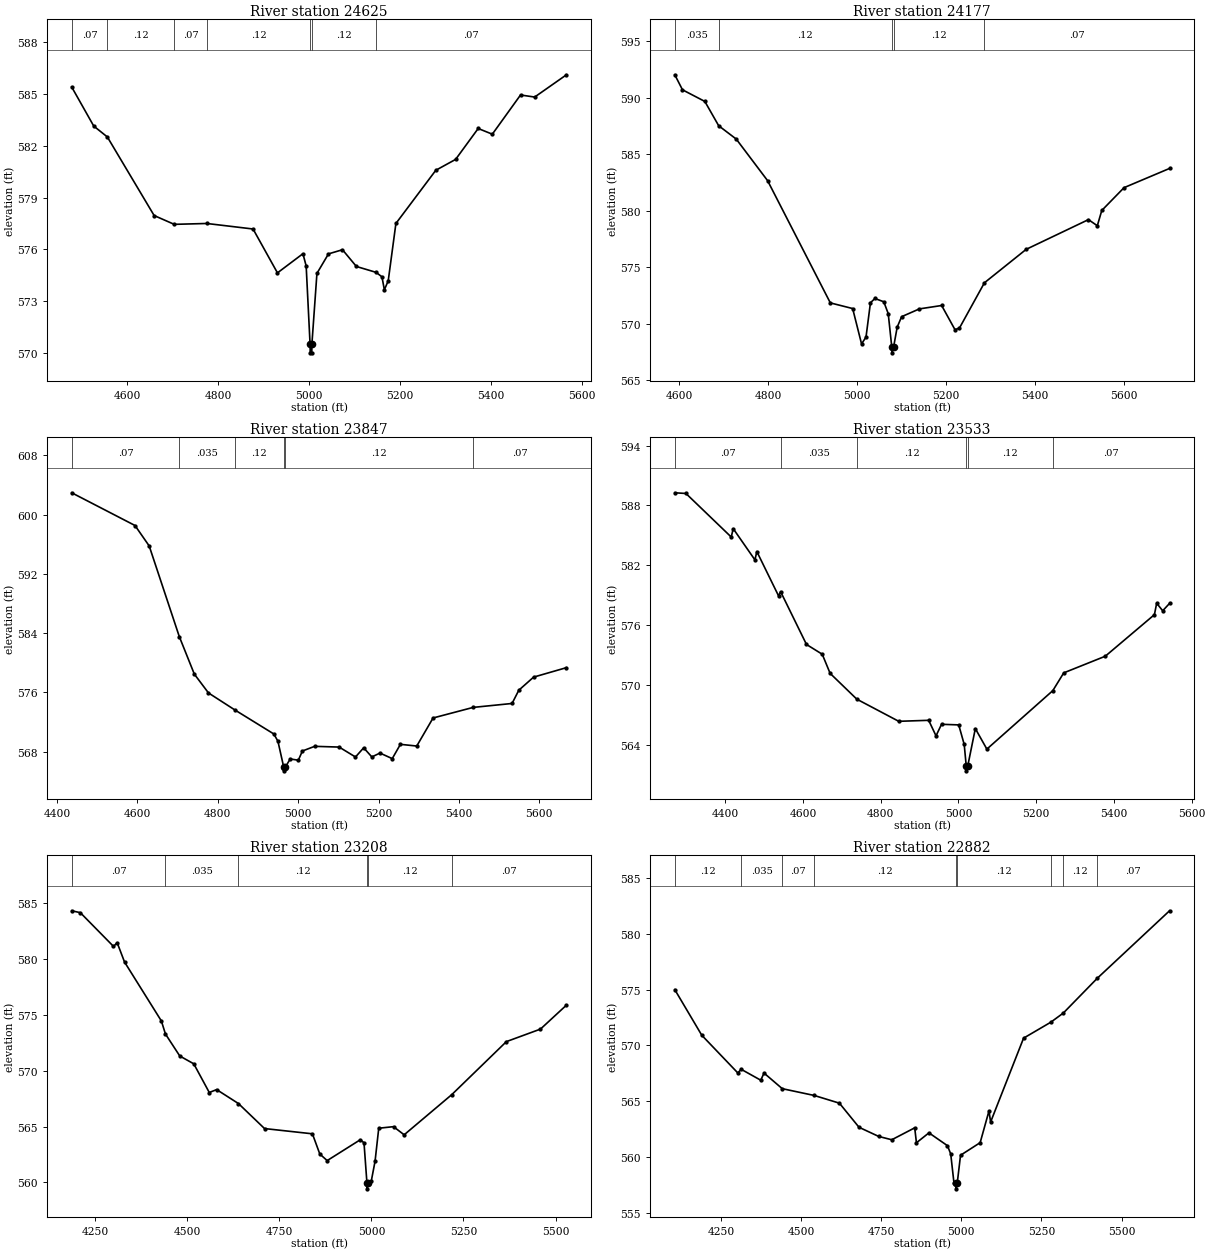
Type RM Length L Ch R = 1 ,24625   ,448,448,448
BEGIN DESCRIPTION:
B19579
END DESCRIPTION:
XS GIS Cut Line= 3
      2320720.67     13789151.29      2320038.33     13788906.48
      2319694.62     13788786.71
#Sta/Elev= 30
  4477.4   585.4  4525.9  583.14  4555.8  582.51  4658.8  577.96    4703  577.45
  4774.8   577.5  4876.5  577.18  4930.2  574.64  4986.3  575.75  4993.4  575.04
    5002  570.51  5002.3  570.01  5005.8  570.01    5006  570.51  5017.1  574.61
  5042.5  575.74  5073.3  575.98    5104  575.01  5147.3  574.67  5160.2  574.41
  5165.5  573.66    5174  574.18  5190.9   577.5  5278.7  580.58  5322.3  581.21
    5372     583  5403.1  582.67  5465.2  584.94  5496.3  584.82  5566.3  586.11
#Mann= 7 ,-1 , 0
  4477.4     .07       0  4555.8     .12       0    4703     .07       0
  4774.8     .12       0    5002     .05       0    5006     .12       0
  5147.3     .07       0
Bank Sta=5002,5006
XS Rating Curve= 0 ,0
Exp/Cntr=0.3,0.1

Type RM Length L Ch R = 1 ,24177   ,330,330,330
BEGIN DESCRIPTION:
B19578
END DESCRIPTION:
XS GIS Cut Line= 3
      2320882.13     13788599.19      2320501.87     13788646.07
       2319772.7      13788666.9
#Sta/Elev= 30
  4590.5  592.03  4607.8   590.7  4658.1  589.67  4689.2  587.52  4728.7  586.34
  4799.2  582.66  4940.3  571.84  4990.5  571.34  5010.5  568.21  5020.5  568.81
  5030.5  571.85  5040.5  572.23  5060.5  571.94  5070.5  570.89  5078.5  567.92
  5078.8  567.42  5082.5  567.92  5090.6  569.69  5100.6  570.62  5140.6  571.31
  5190.6  571.61  5220.6  569.47  5230.6  569.61  5286.8  573.62  5380.7  576.58
  5520.7  579.21  5540.7  578.67  5550.7  580.02  5600.8  582.04  5703.1  583.74
#Mann= 5 ,-1 , 0
  4590.5    .035       0  4689.2     .12       0  5078.5     .05       0
  5082.5     .12       0  5286.8     .07       0
Bank Sta=5078.5,5082.5
XS Rating Curve= 0 ,0
Exp/Cntr=0.3,0.1

Type RM Length L Ch R = 1 ,23847   ,314,314,314
BEGIN DESCRIPTION:
B19577
END DESCRIPTION:
XS GIS Cut Line= 2
      2321080.04     13788265.85      2319868.27     13788484.28
#Sta/Elev= 30
  4436.5  602.95    4594  598.53  4629.3  595.77  4704.2  583.53  4741.6  578.46
  4776.9  575.91  4842.4  573.62  4939.5  570.37  4949.7  569.39  4964.1  565.89
  4964.3  565.39  4968.1  565.89  4980.2  566.99  5000.5  566.83  5010.6  568.07
  5041.1   568.7  5102.1   568.6  5142.7  567.26  5163.1   568.5  5183.4  567.27
  5203.7  567.79  5234.2  567.04  5254.5  568.97  5295.2  568.74  5335.8  572.53
  5435.7  573.96  5532.4  574.49  5549.2  576.28    5586  578.05  5667.8  579.33
#Mann= 6 ,-1 , 0
  4436.5     .07       0  4704.2    .035       0  4842.4     .12       0
  4964.1     .05       0  4968.1     .12       0  5435.7     .07       0
Bank Sta=4964.1,4968.1
XS Rating Curve= 0 ,0
Exp/Cntr=0.3,0.1

Type RM Length L Ch R = 1 ,23533   ,325,325,325
BEGIN DESCRIPTION:
B19576
END DESCRIPTION:
XS GIS Cut Line= 3
      2321059.17     13788005.44      2320402.91     13788114.82
      2319882.08     13788427.32
#Sta/Elev= 30
  4270.4  589.26  4299.1  589.19  4415.6  584.82  4420.7  585.66  4476.5  582.53
  4481.5  583.36  4537.3  578.92  4542.6  579.34  4609.2  574.04  4649.7  573.06
    4670  571.14  4738.7  568.55  4846.5  566.33  4923.5  566.43  4942.4  564.87
  4956.6  566.03  5000.8  565.97  5014.9  564.01  5020.1  561.86  5020.4  561.36
  5024.1  561.86  5043.5   565.6  5073.2  563.54  5242.9  569.41  5270.9  571.19
  5377.8  572.86  5504.2  577.03    5510  578.18  5525.5  577.42  5543.1  578.16
#Mann= 6 ,-1 , 0
  4270.4     .07       0  4542.6    .035       0  4738.7     .12       0
  5020.1     .05       0  5024.1     .12       0  5242.9     .07       0
Bank Sta=5020.1,5024.1
XS Rating Curve= 0 ,0
Exp/Cntr=0.3,0.1

Type RM Length L Ch R = 1 ,23208   ,326,326,326
BEGIN DESCRIPTION:
B19575
END DESCRIPTION:
XS GIS Cut Line= 3
      2321038.35     13787948.15      2320184.16     13787927.32
       2319799.4     13788228.89
#Sta/Elev= 30
  4186.4  584.33  4209.8  584.16  4299.8  581.14  4309.8  581.47  4329.8  579.74
  4429.8  574.46  4440.9  573.29  4479.8  571.32  4517.8  570.62  4559.9  568.05
  4579.9  568.31  4639.1  567.06  4709.9  564.82  4839.9  564.35    4860  562.54
    4880  561.95    4970  563.82    4980  563.54    4988  559.92  4988.2  559.42
    4992  559.92    5000  560.16    5010  561.89    5020  564.85  5060.1  564.99
    5089  564.26  5218.3  567.86  5366.6  572.61  5459.1  573.73  5529.7  575.88
#Mann= 6 ,-1 , 0
  4186.4     .07       0  4440.9    .035       0  4639.1     .12       0
    4988     .05       0    4992     .12       0  5218.3     .07       0
Bank Sta=4988,4992
XS Rating Curve= 0 ,0
Exp/Cntr=0.3,0.1

Type RM Length L Ch R = 1 ,22882   ,346,346,346
BEGIN DESCRIPTION:
B19574
END DESCRIPTION:
XS GIS Cut Line= 4
      2321017.48     13787833.56      2320241.46     13787672.11
      2320012.29     13787718.98      2319501.88     13787640.86
#Sta/Elev= 30
  4106.4     575  4190.6  570.91    4303  567.53  4313.3  567.86  4374.5  566.88
  4384.7  567.52  4441.6  566.12  4541.5  565.51  4619.8  564.82  4680.9  562.66
  4742.2  561.84  4783.1  561.54  4854.6  562.61    4860  561.27    4899  562.16
  4956.7  561.01  4966.9  560.27  4977.1  557.65  4983.2  557.64  4983.5  557.14
  4987.2  557.64  4997.5  560.15  5058.7  561.28  5086.2  564.12  5091.3  563.13
  5194.1  570.65  5279.1  572.08    5318   572.9    5424  576.02  5649.3  582.07
#Mann= 9 ,-1 , 0
  4106.4     .12       0  4313.3    .035       0  4441.6     .07       0
  4541.5     .12       0  4983.2     .05       0  4987.2     .12       0
  5279.1     .07       0    5318     .12       0    5424     .07       0
Bank Sta=4983.2,4987.2
XS Rating Curve= 0 ,0
Exp/Cntr=0.3,0.1

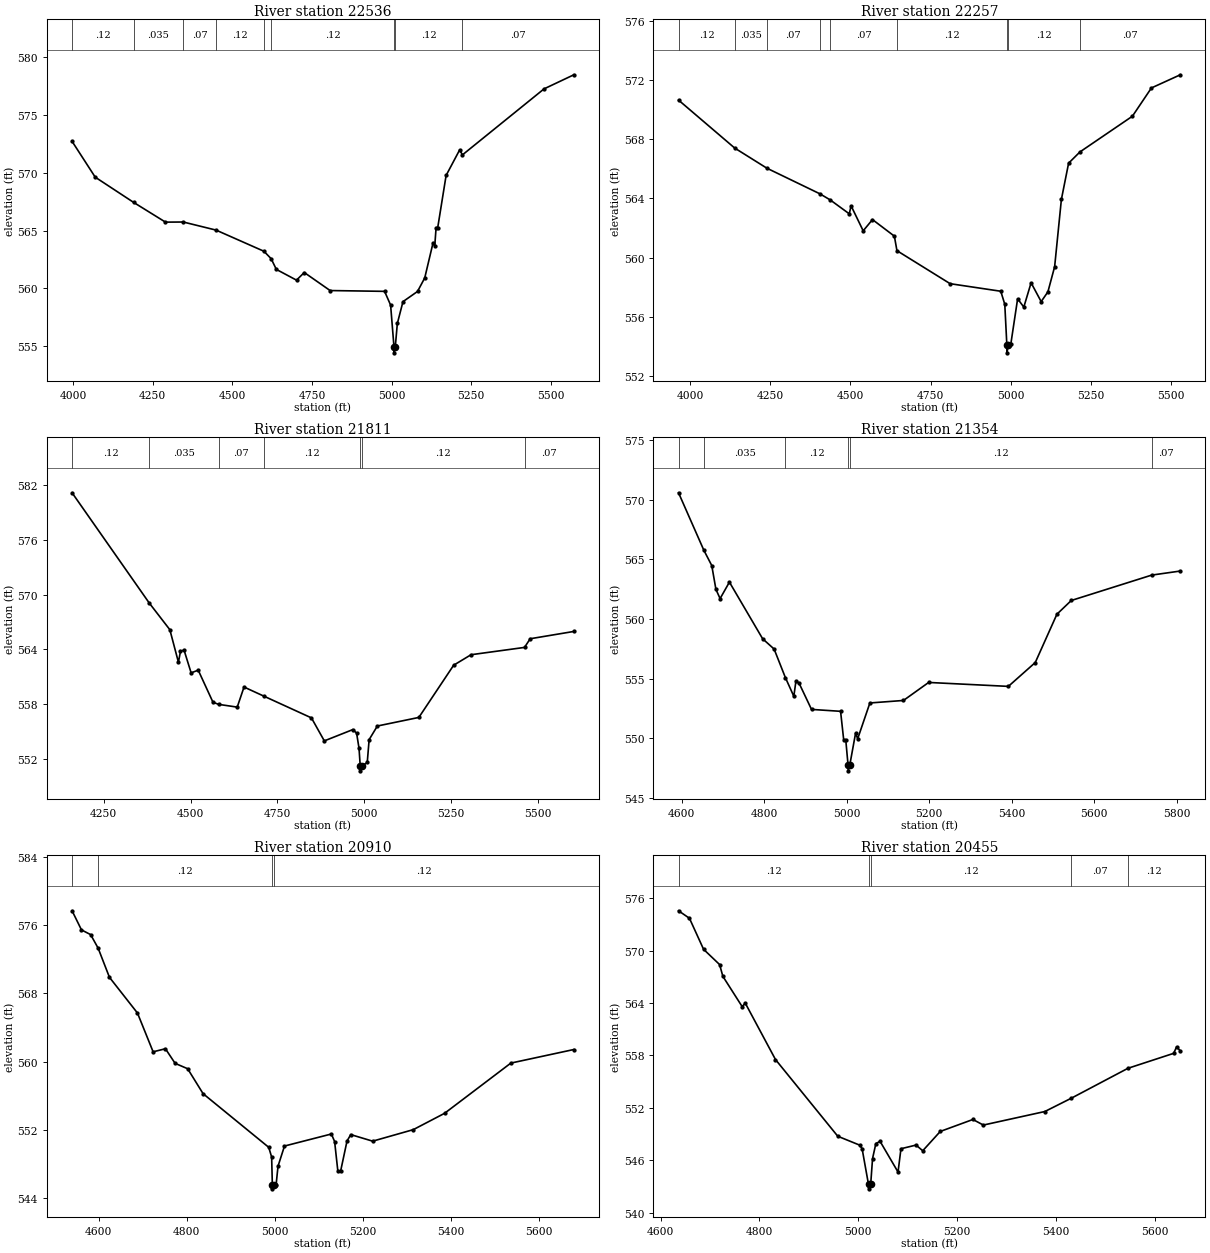
Type RM Length L Ch R = 1 ,22536   ,279,279,279
BEGIN DESCRIPTION:
B19573
END DESCRIPTION:
XS GIS Cut Line= 3
      2321022.69     13787791.89      2319939.37     13787427.32
      2319518.71     13787328.64
#Sta/Elev= 30
  3997.2  572.72  4069.9  569.62  4190.3  567.44  4290.4  565.73  4346.3  565.74
  4449.2  565.04  4599.4  563.21    4622  562.57  4638.4  561.64  4701.7  560.71
  4726.1  561.37  4807.2  559.81  4978.2  559.74  4997.1  558.55  5007.7  554.92
  5007.9  554.42  5011.7  554.92  5018.2  556.96  5035.9  558.85  5081.5  559.73
  5104.2   560.9  5130.4  563.95  5135.7   563.7  5139.9  565.26    5145  565.26
  5171.3  569.77  5213.8  571.98  5222.6  571.55  5478.7  577.26  5572.3  578.48
#Mann= 9 ,-1 , 0
  3997.2     .12       0  4190.3    .035       0  4346.3     .07       0
  4449.2     .12       0  4599.4     .07       0    4622     .12       0
  5007.7     .05       0  5011.7     .12       0  5222.6     .07       0
Bank Sta=5007.7,5011.7
XS Rating Curve= 0 ,0
Exp/Cntr=0.3,0.1

Type RM Length L Ch R = 1 ,22257   ,446,446,446
BEGIN DESCRIPTION:
B19572
END DESCRIPTION:
XS GIS Cut Line= 3
      2321033.14     13787739.83      2320163.33     13787255.44
      2319621.64     13787083.56
#Sta/Elev= 30
  3964.6  570.64  4139.7   567.4    4240  566.04  4405.2  564.31  4437.2   563.9
  4496.7  562.96  4502.4   563.5  4540.1  561.81  4569.1  562.57  4637.3  561.45
  4645.3  560.47  4811.1  558.24  4968.9  557.73  4981.4  556.85  4987.9  554.07
  4988.2  553.57  4991.9  554.07  5000.4  554.19  5021.4  557.22  5040.7  556.66
  5063.4   558.3  5094.8  557.03  5115.8  557.69  5136.8  559.39  5157.8  563.93
  5180.3  566.38  5215.7  567.14  5379.1  569.55  5438.4  571.46  5528.5  572.35
#Mann= 9 ,-1 , 0
  3964.6     .12       0  4139.7    .035       0    4240     .07       0
  4405.2     .12       0  4437.2     .07       0  4645.3     .12       0
  4987.9     .05       0  4991.9     .12       0  5215.7     .07       0
Bank Sta=4987.9,4991.9
XS Rating Curve= 0 ,0
Exp/Cntr=0.3,0.1

Type RM Length L Ch R = 1 ,21811   ,457,457,457
BEGIN DESCRIPTION:
B19571
END DESCRIPTION:
XS GIS Cut Line= 4
      2321220.63     13787192.94      2320527.91     13787047.11
      2320319.58     13786958.57      2319809.55     13786922.14
#Sta/Elev= 30
  4158.8  581.16  4381.2  569.08  4440.5  566.16  4465.2   562.6  4471.1  563.78
  4481.3  563.94  4501.8  561.43  4522.2  561.73  4564.8  558.21  4581.3  557.98
  4634.6  557.68  4654.2  559.88  4711.5  558.88  4848.4   556.5  4885.5  553.98
  4967.7  555.22  4978.5  554.83  4985.5  553.17    4989   551.2  4989.2   550.7
    4993   551.2  5009.2  551.62  5014.6  554.12  5038.3  555.61  5157.8  556.55
  5258.1  562.27  5308.2  563.42  5462.2  564.22  5478.6  565.17  5604.4  565.97
#Mann= 7 ,-1 , 0
  4158.8     .12       0  4381.2    .035       0  4581.3     .07       0
  4711.5     .12       0    4989     .05       0    4993     .12       0
  5462.2     .07       0
Bank Sta=4989,4993
XS Rating Curve= 0 ,0
Exp/Cntr=0.3,0.1

Type RM Length L Ch R = 1 ,21354   ,444,444,444
BEGIN DESCRIPTION:
MILL TRIBUTARY 7 40.0
END DESCRIPTION:
XS GIS Cut Line= 3
      2321074.97       13786775.        2320675.       13786725.
      2319875.03     13786874.99
#Sta/Elev= 30
  4592.1  570.58  4653.4  565.77  4672.7  564.48  4682.8  562.48  4692.9  561.71
  4715.5  563.09  4796.1  558.34  4823.9  557.48  4851.2  555.09  4871.7  553.52
  4876.8  554.78  4884.3  554.63  4914.6  552.42  4985.1  552.26  4992.7  549.86
  4997.7  549.86  5003.2  547.77  5003.5  547.27  5007.5  547.77  5021.5  550.43
  5026.6  549.96  5056.2  552.96  5137.6  553.17  5198.7  554.68    5392  554.35
  5457.3  556.35  5509.8   560.4  5544.6  561.55  5739.8  563.68  5809.1  564.02
#Mann= 6 ,-1 , 0
  4592.1     .12       0  4653.4    .035       0  4851.2     .12       0
  5003.2     .05       0  5007.5     .12       0  5739.8     .07       0
Bank Sta=5003.2,5007.5
XS Rating Curve= 0 ,0
Exp/Cntr=0.3,0.1

Type RM Length L Ch R = 1 ,20910   ,455,455,455
BEGIN DESCRIPTION:
MILL TRIBUTARY 7 39.0
END DESCRIPTION:
XS GIS Cut Line= 3
      2321024.97     13786075.03        2320675.       13786375.
      2320125.01     13786774.99
#Sta/Elev= 30
  4539.2  577.68  4560.6  575.44  4581.4  574.89  4598.5   573.3  4624.2  569.89
  4687.9  565.71  4723.5  561.17  4751.5  561.53  4773.5  559.82    4802  559.19
  4837.1  556.27  4986.4  549.99    4993  548.85  4994.6  545.63  4994.9  545.13
    4999  545.63  5003.2  545.63  5007.5  547.78  5022.2  550.14  5128.8  551.55
  5136.2  550.67  5143.5  547.23  5149.7  547.17  5164.4  550.73  5172.9  551.48
  5222.7  550.71  5315.1  552.06  5386.2  553.97  5536.9  559.85  5680.2  561.44
#Mann= 4 ,-1 , 0
  4539.2    .035       0  4598.5     .12       0  4994.6     .05       0
    4999     .12       0
Bank Sta=4994.6,4999
XS Rating Curve= 0 ,0
Exp/Cntr=0.3,0.1

Type RM Length L Ch R = 1 ,20455   ,234,234,234
BEGIN DESCRIPTION:
MILL TRIBUTARY 7 38.0
END DESCRIPTION:
XS GIS Cut Line= 3
      2320874.98     13785875.01        2320525.       13785975.
        2320175.     13786524.99
#Sta/Elev= 30
  4636.3  574.55  4658.4  573.69    4687  570.14  4719.5  568.39    4726  567.05
    4765  563.59  4771.5  563.97  4832.6  557.52  4958.7  548.74  5003.2  547.72
  5007.9  547.33  5020.9  543.22  5021.2  542.72  5025.3  543.22  5029.1  546.19
  5035.8   547.9  5044.3  548.16  5080.7  544.64  5086.6  547.31  5117.1  547.73
  5130.7  547.08  5166.2  549.29  5232.3  550.66  5253.4  550.02  5377.9  551.57
  5431.7   553.1  5546.2  556.52  5638.7  558.23  5644.6  558.97  5652.2  558.52
#Mann= 5 ,-1 , 0
  4636.3     .12       0  5020.9     .05       0  5025.3     .12       0
  5431.7     .07       0  5546.2     .12       0
Bank Sta=5020.9,5025.3
XS Rating Curve= 0 ,0
Exp/Cntr=0.3,0.1

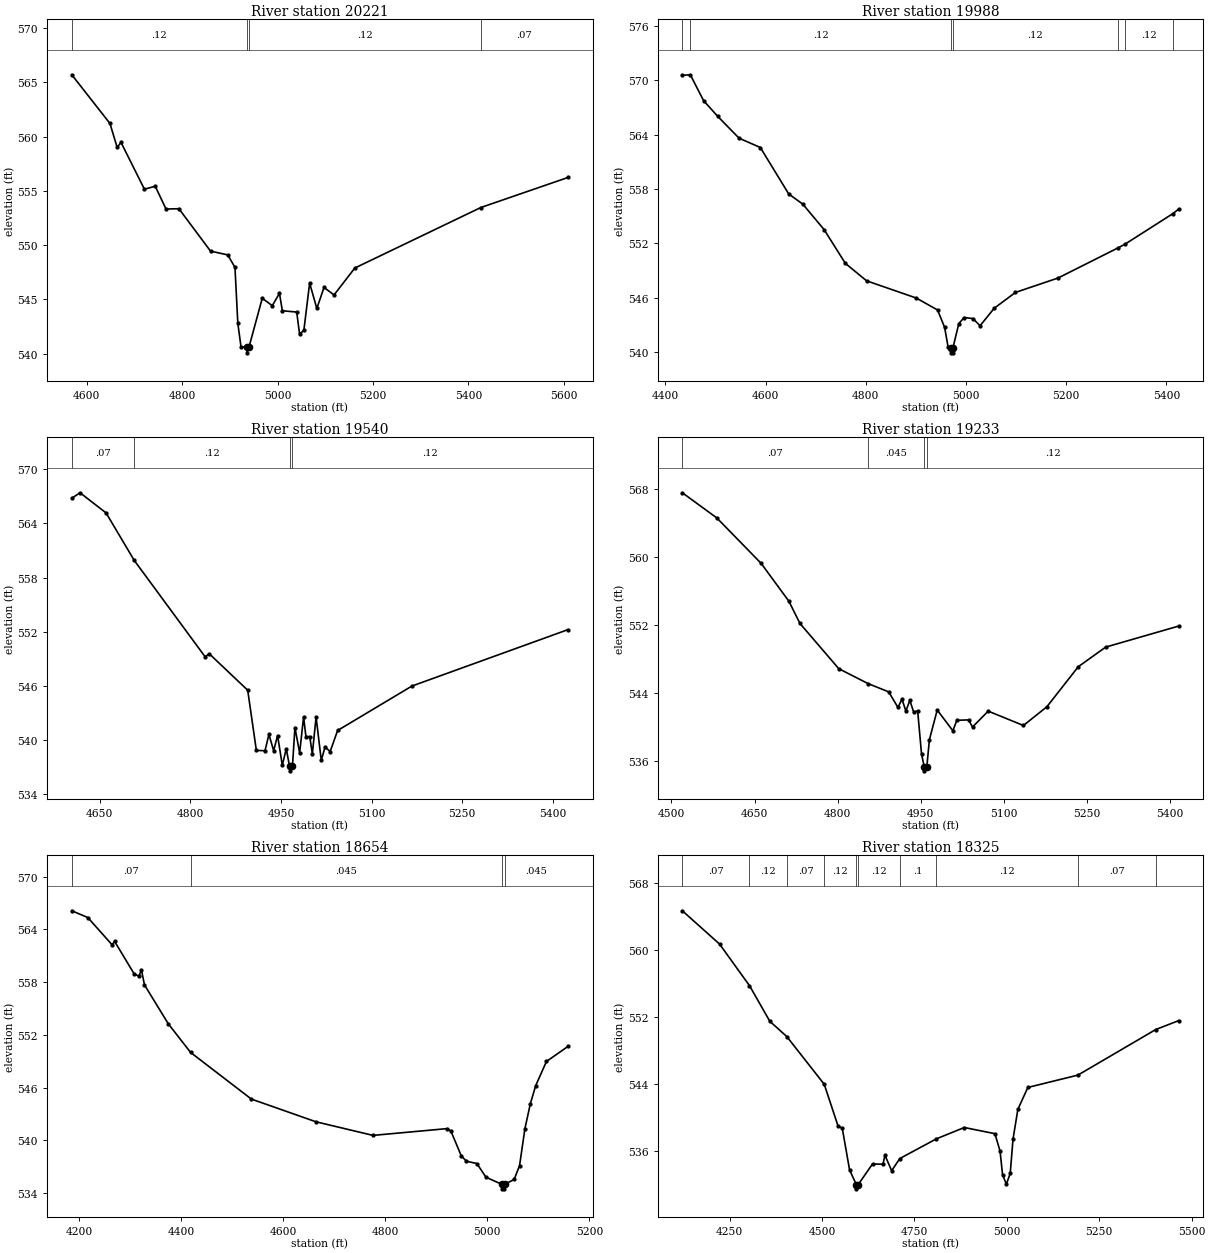
Type RM Length L Ch R = 1 ,20221   ,233,233,233
BEGIN DESCRIPTION:
B19570
END DESCRIPTION:
XS GIS Cut Line= 3
      2320731.04     13785588.78      2320241.46     13785911.69
      2319934.13     13786245.06
#Sta/Elev= 30
  4568.7  565.71  4648.7  561.22  4663.8  559.01  4671.8  559.48  4720.9  555.16
  4743.6  555.43  4766.2  553.33  4793.2  553.36  4859.5  549.45  4895.6   549.1
  4910.7  547.95  4916.7  542.79  4923.3  540.65  4935.5  540.57  4935.8  540.07
  4939.9  540.57  4967.9   545.1  4988.9  544.42    5004  545.56    5010  543.95
  5040.1  543.83  5046.1   541.8  5055.1  542.14  5067.2   546.5  5082.3  544.16
  5097.3   546.1  5118.4  545.41  5161.9  547.89    5426  553.47  5608.6  556.24
#Mann= 4 ,-1 , 0
  4568.7     .12       0  4935.5     .05       0  4939.9     .12       0
    5426     .07       0
Bank Sta=4935.5,4939.9
XS Rating Curve= 0 ,0
Exp/Cntr=0.3,0.1

Type RM Length L Ch R = 1 ,19988   ,448,448,448
BEGIN DESCRIPTION:
MILL TRIBUTARY 7 37.0
END DESCRIPTION:
XS GIS Cut Line= 3
      2320575.03     13785324.97        2320175.       13785725.
        2319875.       13786025.
#Sta/Elev= 30
    4434  570.57  4449.9  570.63  4476.5  567.76  4504.8  566.02  4547.2  563.62
  4589.6  562.59  4646.2  557.46  4674.5  556.32  4716.9  553.51  4759.3  549.78
  4801.7  547.85  4900.7  545.95  4943.2  544.63  4957.3  542.71  4964.4  540.49
  4969.2  540.39  4969.5  539.89  4973.4  539.89  4973.7  540.39  4985.6  543.12
  4996.2  543.79  5013.9  543.68    5028  542.88  5056.3  544.82  5098.7  546.57
  5183.6  548.16  5303.2  551.49  5316.6  551.88  5412.8  555.28    5424  555.77
#Mann= 7 ,-1 , 0
    4434     .07       0  4449.9     .12       0  4969.2     .05       0
  4973.7     .12       0  5303.2     .07       0  5316.6     .12       0
  5412.8     .07       0
Bank Sta=4969.2,4973.7
XS Rating Curve= 0 ,0
Exp/Cntr=0.3,0.1

Type RM Length L Ch R = 1 ,19540   ,307,307,307
BEGIN DESCRIPTION:
MILL TRIBUTARY 7 36.0
END DESCRIPTION:
XS GIS Cut Line= 3
      2320275.03     13785124.97        2319975.       13785375.
      2319624.98     13785625.02
#Sta/Elev= 30
  4604.1  566.79  4617.8  567.39  4660.8  565.16  4707.3  559.91  4824.8  549.21
  4831.3  549.57  4895.1  545.52  4909.4  538.85  4923.7  538.82  4930.2  540.62
    4938  538.82  4944.5   540.5  4952.3  537.22  4958.9  539.03  4964.3  537.09
  4964.6  536.59  4969.1  537.09  4973.2  541.39    4981  538.57  4987.5  542.56
  4991.4  540.38  4997.7  540.38    5002  538.48  5008.2  542.55  5016.8  537.74
  5022.9  539.22  5031.5  538.73  5043.8  541.06  5166.7  545.98  5424.8  552.23
#Mann= 4 ,-1 , 0
  4604.1     .07       0  4707.3     .12       0  4964.3     .05       0
  4969.1     .12       0
Bank Sta=4964.3,4969.1
XS Rating Curve= 0 ,0
Exp/Cntr=0.3,0.1

Type RM Length L Ch R = 1 ,19233   ,579,579,579
BEGIN DESCRIPTION:
B19569
END DESCRIPTION:
XS GIS Cut Line= 3
      2320257.11     13785073.15      2319866.46     13785088.78
      2319512.31     13785448.13
#Sta/Elev= 30
  4519.7  567.54  4581.9  564.58  4661.9  559.23    4712  554.77    4732  552.15
    4802  546.83    4855  545.07  4892.1   544.1  4908.9  542.26  4916.1  543.25
  4923.1  541.84  4930.3  543.09  4937.3  541.71  4944.4  541.87  4951.4  536.78
  4956.2   535.3  4956.5   534.8    4961   535.3  4965.6  538.47  4979.7  541.96
    5008  539.52  5015.1  540.75  5036.3   540.8  5043.4  539.96  5071.7  541.83
  5135.3  540.14  5177.7  542.35  5234.3  547.06  5283.8  549.37  5415.2  551.84
#Mann= 4 ,-1 , 0
  4519.7     .07       0    4855    .045       0  4956.2     .05       0
    4961     .12       0
Bank Sta=4956.2,4961
XS Rating Curve= 0 ,0
Exp/Cntr=0.3,0.1

Type RM Length L Ch R = 1 ,18654   ,329,329,329
BEGIN DESCRIPTION:
MILL TRIBUTARY 7 35.0
END DESCRIPTION:
XS GIS Cut Line= 3
      2320224.98       13785025.        2319425.       13784875.
      2319275.04     13784924.99
#Sta/Elev= 30
  4186.1  566.12  4217.5  565.35  4264.9  562.26    4270  562.64  4308.2  558.95
  4317.5  558.68  4322.6  559.38  4328.5  557.69  4375.2  553.26  4418.8  550.01
  4537.9   544.7  4664.3  542.12  4776.2  540.57  4921.2  541.34  4928.8  541.06
  4949.2  538.23  4959.3  537.63  4979.7  537.37  4997.5  535.81  5029.2  534.99
  5029.6  534.49  5033.7  534.49    5034  534.99  5052.7  535.56  5063.3  537.13
  5073.8  541.34  5084.4  544.16  5094.9  546.23    5116  548.98  5158.1  550.69
#Mann= 4 ,-1 , 0
  4186.1     .07       0  4418.8    .045       0  5029.2    .045       0
    5034    .045       0
Bank Sta=5029.2,5034
XS Rating Curve= 0 ,0
Exp/Cntr=0.3,0.1

Type RM Length L Ch R = 1 ,18325   ,582,582,582
BEGIN DESCRIPTION:
B19568
END DESCRIPTION:
XS GIS Cut Line= 3
       2320262.3     13784859.61      2319298.75      13784604.4
      2318981.08      13784739.8
#Sta/Elev= 30
  4122.4  564.73  4223.1  560.74    4304  555.76    4359  551.49  4405.1  549.65
  4506.2  543.94  4543.7  538.92  4554.9  538.69  4574.8  533.67  4593.1  531.91
  4593.4  531.41  4597.9  531.91  4636.8  534.39  4665.2  534.36  4670.4  535.44
  4688.6  533.58  4710.6  535.04  4809.5   537.4  4885.1  538.76  4967.9  538.02
  4981.8  535.93  4988.6   533.1  4998.9  531.97  5009.3  533.25  5016.8  537.34
    5030  540.94    5057  543.56  5192.5  545.04    5403   550.5  5464.5  551.56
#Mann= 10 ,-1 , 0
  4122.4     .07       0    4304     .12       0  4405.1     .07       0
  4506.2     .12       0  4593.1     .05       0  4597.9     .12       0
  4710.6      .1       0  4809.5     .12       0  5192.5     .07       0
    5403    .045       0
Bank Sta=4593.1,4597.9
XS Rating Curve= 0 ,0
Exp/Cntr=0.3,0.1

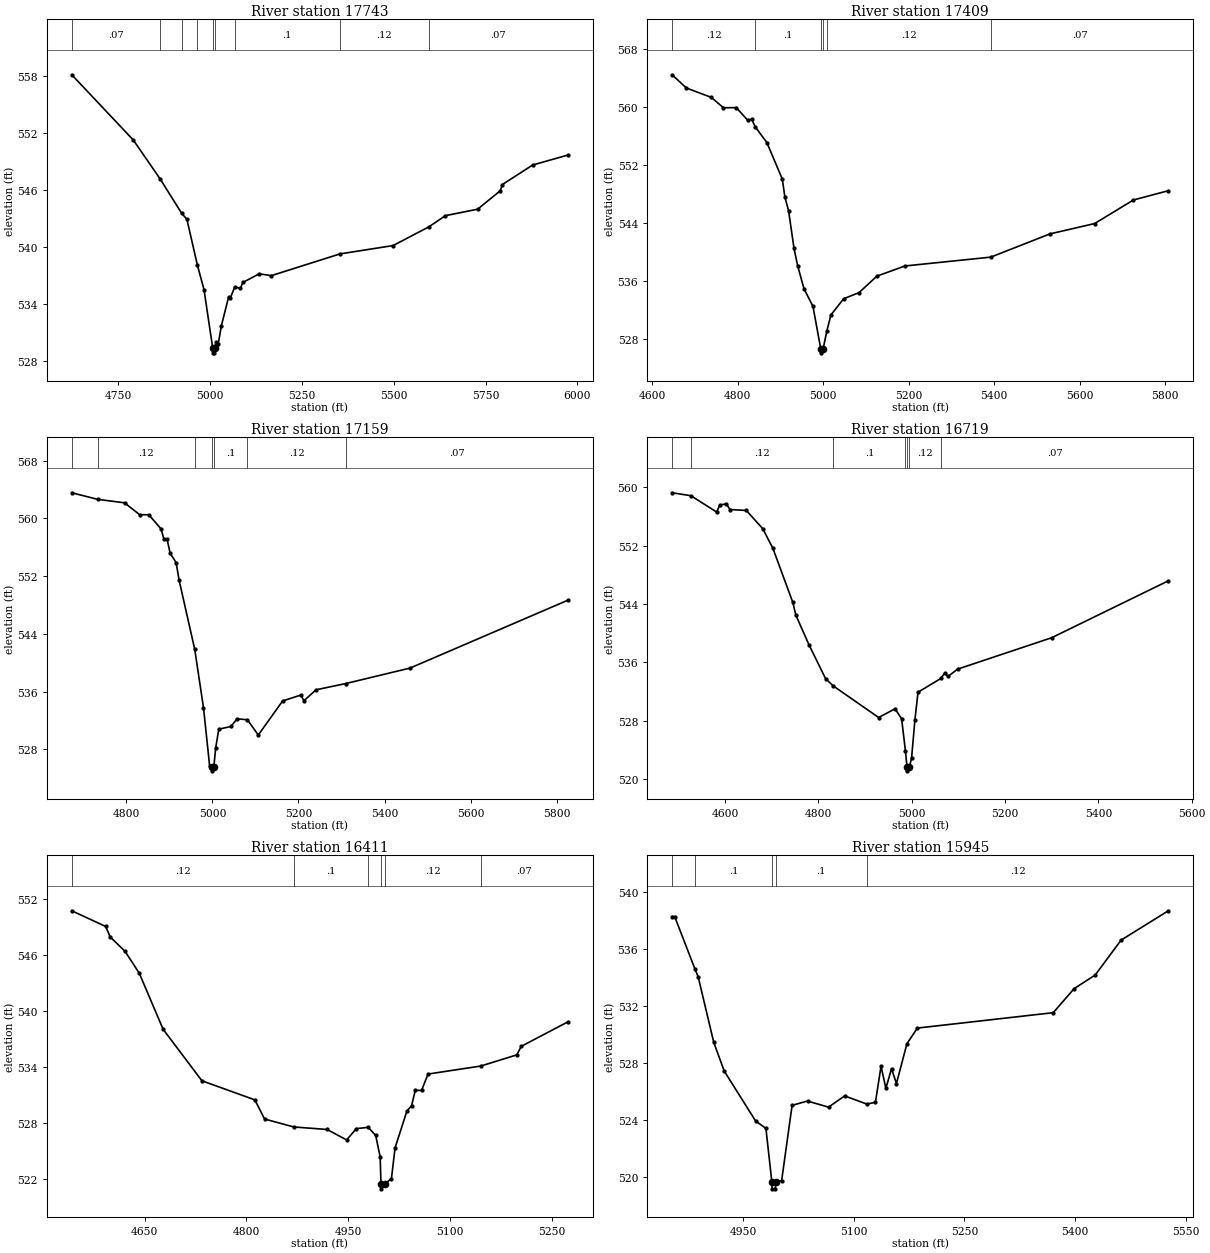
Type RM Length L Ch R = 1 ,17743   ,334,334,334
BEGIN DESCRIPTION:
B19567
END DESCRIPTION:
XS GIS Cut Line= 4
      2320225.84     13784640.86      2319762.29     13784505.44
      2319428.96     13784474.19       2318925.6     13784650.63
#Sta/Elev= 30
  4623.2  558.08  4790.8  551.22  4863.4  547.16  4922.5  543.52  4936.6   542.9
  4965.1   538.1  4983.2  535.51  5006.9  529.37  5007.3  528.87  5011.7  528.87
  5012.1  529.37  5016.6  530.02  5021.9  529.78  5030.4   531.7  5050.1  534.72
  5055.3  534.66  5066.8  535.79  5082.5  535.66  5088.8  536.26  5133.5  537.17
  5166.6  536.98  5353.2  539.26  5498.1  540.14  5595.2   542.1  5640.5  543.28
  5728.2  543.96  5790.3  545.91  5795.6  546.55    5878   548.6  5974.3  549.65
#Mann= 9 ,-1 , 0
  4623.2     .07       0  4863.4     .12       0  4922.5      .1       0
  4965.1     .12       0  5006.9     .05       0  5012.1     .12       0
  5066.8      .1       0  5353.2     .12       0  5595.2     .07       0
Bank Sta=5006.9,5012.1
XS Rating Curve= 0 ,0
Exp/Cntr=0.3,0.1

Type RM Length L Ch R = 1 ,17409   ,250,250,250
BEGIN DESCRIPTION:
B19566
END DESCRIPTION:
XS GIS Cut Line= 3
      2319970.62     13784073.15      2319512.29     13784385.65
      2318944.55      13784599.2
#Sta/Elev= 30
  4646.6  564.45  4680.1  562.62  4738.1  561.34  4766.8   559.9  4796.7  559.92
  4823.7  558.17  4832.6  558.33  4841.2  557.27  4868.5  555.08  4904.4  550.07
  4910.4  547.64  4919.3  545.65  4931.8  540.53  4940.3  538.13  4955.2  534.94
  4976.2  532.51  4994.6   526.6    4995   526.1  4999.8   526.6  5008.5  529.06
  5018.2  531.32    5048  533.56  5083.9   534.4  5125.9  536.68  5191.6  538.08
  5392.3   539.3  5530.6   542.5  5635.4  543.93  5726.1  547.18  5807.9  548.46
#Mann= 6 ,-1 , 0
  4646.6     .12       0  4841.2      .1       0  4994.6     .05       0
  4999.8      .1       0  5008.5     .12       0  5392.3     .07       0
Bank Sta=4994.6,4999.8
XS Rating Curve= 0 ,0
Exp/Cntr=0.3,0.1

Type RM Length L Ch R = 1 ,17159   ,440,440,440
BEGIN DESCRIPTION:
B19565
END DESCRIPTION:
XS GIS Cut Line= 3
      2319767.52     13783854.38      2319345.62     13784297.11
      2318878.47     13784572.21
#Sta/Elev= 30
  4672.9  563.56    4733  562.65  4795.5  562.17  4830.7  560.52  4852.1  560.51
  4880.4  558.55  4887.3   557.1  4894.6  557.09  4901.5  555.19  4915.6  553.86
  4922.5  551.41  4958.8  541.83  4979.1  533.76  4993.3  525.73  4997.9   525.5
  4998.3     525  5003.1   525.5  5007.4  528.15  5014.7  530.78    5043  531.15
  5057.2  532.22  5081.2  532.08  5106.5  529.97  5163.1  534.69  5205.6  535.51
  5212.5  534.72  5240.8  536.24  5309.5   537.1  5459.3  539.25  5826.6  548.67
#Mann= 7 ,-1 , 0
  4672.9     .07       0    4733     .12       0  4958.8      .1       0
  4997.9     .05       0  5003.1      .1       0  5081.2     .12       0
  5309.5     .07       0
Bank Sta=4997.9,5003.1
XS Rating Curve= 0 ,0
Exp/Cntr=0.3,0.1

Type RM Length L Ch R = 1 ,16719   ,308,308,308
BEGIN DESCRIPTION:
B19564
END DESCRIPTION:
XS GIS Cut Line= 3
      2319559.15     13783734.62      2319100.83     13784140.86
      2318835.22     13784505.42
#Sta/Elev= 30
  4486.5  559.23  4526.7  558.83    4582  556.59  4588.7  557.56  4602.9  557.71
  4610.4  556.94  4645.5  556.81  4680.7  554.32  4702.4  551.64  4745.1  544.24
  4751.8  542.46  4780.2  538.37  4815.3   533.8  4831.7   532.8  4929.1  528.47
  4964.2  529.66  4978.4   528.3  4986.6  523.84    4990  521.67  4990.4  521.17
  4995.2  521.67  4999.8  522.97  5006.8  528.11  5013.5  531.93  5062.5  533.82
  5070.4  534.52  5077.9  534.09  5098.3  535.09    5300  539.39    5550  547.18
#Mann= 7 ,-1 , 0
  4486.5     .07       0  4526.7     .12       0  4831.7      .1       0
  4986.6     .12       0    4990     .05       0  4995.2     .12       0
  5062.5     .07       0
Bank Sta=4990,4995.2
XS Rating Curve= 0 ,0
Exp/Cntr=0.3,0.1

Type RM Length L Ch R = 1 ,16411   ,466,466,466
BEGIN DESCRIPTION:
MILL TRIBUTARY 7 32.0
END DESCRIPTION:
XS GIS Cut Line= 3
      2319274.97     13783625.03        2318925.       13783925.
        2318825.     13784175.01
#Sta/Elev= 30
    4543  550.71  4592.9  549.03  4599.5  547.91  4621.4  546.37  4642.3  544.03
  4677.4  538.03  4734.5  532.52  4812.4  530.48  4826.7  528.43  4869.8  527.58
  4918.9  527.31  4947.4  526.19  4961.7   527.4  4979.1  527.54  4990.2  526.68
  4996.8  524.37    4998  521.46  4998.4  520.96  5003.2  521.46  5013.4  522.06
  5018.7  525.34  5036.2   529.3    5043  529.84  5048.4  531.49  5057.8   531.5
  5067.2  533.24  5144.9   534.1  5197.8  535.29  5204.5  536.21  5273.2  538.83
#Mann= 6 ,-1 , 0
    4543     .12       0  4869.8      .1       0  4979.1     .12       0
    4998     .05       0  5003.2     .12       0  5144.9     .07       0
Bank Sta=4998,5003.2
XS Rating Curve= 0 ,0
Exp/Cntr=0.3,0.1

Type RM Length L Ch R = 1 ,15945   ,444,444,444
BEGIN DESCRIPTION:
MILL TRIBUTARY 7 31.0
END DESCRIPTION:
XS GIS Cut Line= 3
      2318974.97     13783475.03        2318875.       13783575.
      2318524.99     13783975.01
#Sta/Elev= 30
  4853.7  538.27  4857.2  538.27  4884.6   534.6    4889  534.05  4910.2  529.44
  4924.4  527.43  4966.8  523.94  4980.9  523.41  4988.9  519.67  4989.3  519.17
  4993.7  519.17  4994.2  519.67  5002.2  519.74  5016.4  525.03  5037.3  525.33
  5065.8   524.9  5087.6  525.69  5117.6  525.12  5129.4  525.24    5137  527.77
  5143.6  526.22  5151.2   527.6  5157.9  526.56  5172.1  529.35  5186.3  530.45
  5370.5  531.53  5398.9  533.22  5427.4  534.17  5462.5  536.62  5526.6  538.68
#Mann= 5 ,-1 , 0
  4853.7     .12       0  4884.6      .1       0  4988.9     .05       0
  4994.2      .1       0  5117.6     .12       0
Bank Sta=4988.9,4994.2
XS Rating Curve= 0 ,0
Exp/Cntr=0.3,0.1

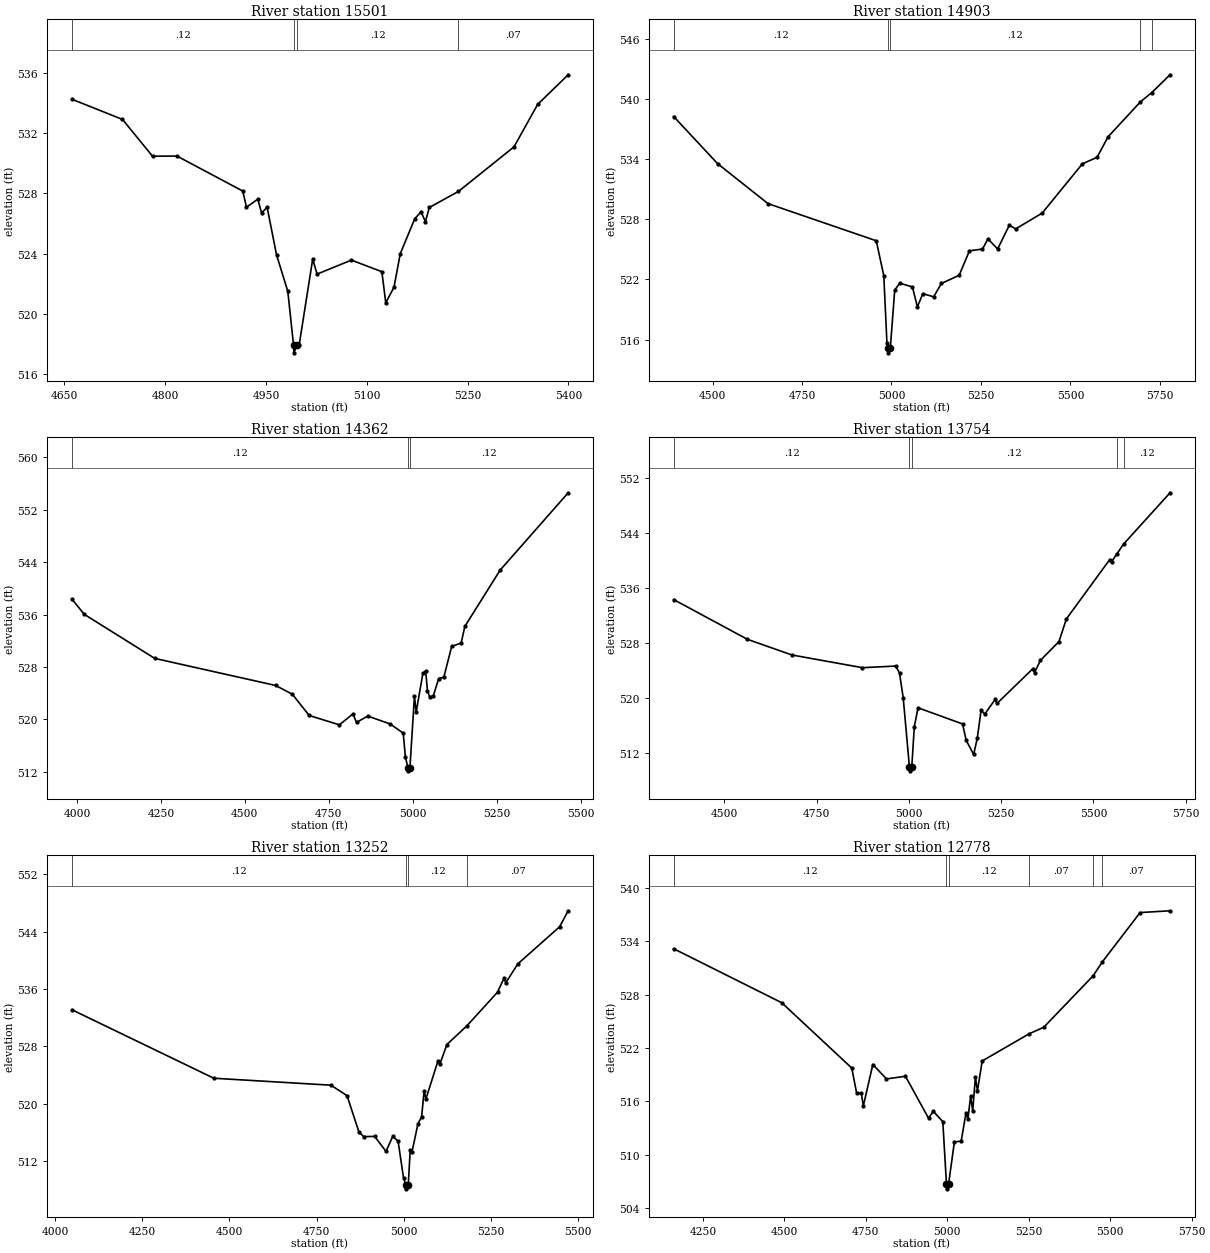
Type RM Length L Ch R = 1 ,15501   ,598,598,598
BEGIN DESCRIPTION:
MILL TRIBUTARY 7 30.0
END DESCRIPTION:
XS GIS Cut Line= 3
      2318824.96     13783225.02        2318525.       13783375.
      2318324.99     13783725.02
#Sta/Elev= 30
  4661.1  534.24  4736.5   532.9  4781.2  530.46  4817.6  530.47  4915.4  528.15
    4921  527.08  4937.8  527.61  4943.4   526.7  4951.7  527.07  4965.7  523.92
  4982.5  521.49    4991  517.92  4991.4  517.42  4996.3  517.92  4999.3  517.92
  5019.5  523.64    5026  522.64  5077.1  523.57  5122.4   522.8  5128.2  520.74
  5140.4  521.77  5149.8     524  5171.4  526.32  5180.7  526.77  5187.2  526.12
    5193  527.06  5236.2  528.12    5319  531.08  5354.2   533.9  5399.6  535.86
#Mann= 4 ,-1 , 0
  4661.1     .12       0    4991     .05       0  4996.3     .12       0
  5236.2     .07       0
Bank Sta=4991,4996.3
XS Rating Curve= 0 ,0
Exp/Cntr=0.3,0.1

Type RM Length L Ch R = 1 ,14903   ,541,541,541
BEGIN DESCRIPTION:
B19563
END DESCRIPTION:
XS GIS Cut Line= 4
      2318897.73      13783041.9      2318356.04     13783120.03
      2318038.33     13783323.15      2317585.22      13783416.9
#Sta/Elev= 30
  4391.4  538.23  4514.3  533.53  4655.1  529.55  4957.5  525.85  4978.6  522.37
  4987.4  515.68  4990.7  515.18  4991.2  514.68  4996.9  515.18  5009.1  520.93
    5023  521.62  5058.6  521.25  5072.5  519.26  5087.7  520.58    5118  520.26
  5139.3  521.59  5189.2  522.41    5218  524.85  5254.4  525.02  5269.6  526.04
  5296.7  525.03  5329.4   527.4  5347.2  527.03  5421.3  528.61  5533.6  533.52
  5574.5  534.16  5605.1   536.2  5695.9   539.7  5727.5  540.62  5778.5  542.39
#Mann= 5 ,-1 , 0
  4391.4     .12       0  4990.7     .05       0  4996.9     .12       0
  5695.9     .07       0  5727.5     .12       0
Bank Sta=4990.7,4996.9
XS Rating Curve= 0 ,0
Exp/Cntr=0.3,0.1

Type RM Length L Ch R = 1 ,14362   ,608,608,608
BEGIN DESCRIPTION:
B19562
END DESCRIPTION:
XS GIS Cut Line= 3
      2318882.05     13782963.78      2318053.96     13782974.19
      2317429.43     13782792.04
#Sta/Elev= 30
  3984.5   538.4  4021.5  536.05  4231.6  529.32  4591.6  525.19  4641.6  523.85
  4691.6  520.61  4781.6  519.18    4822  520.85  4832.6  519.55  4866.1  520.52
  4933.1  519.31  4971.8  517.91  4978.2  514.29  4985.6  512.66  4986.1  512.16
  4991.8  512.66  5005.2  523.57  5010.4  521.13  5030.3  527.04  5038.7  527.41
  5043.9  524.37  5051.2  523.38  5061.6  523.64  5077.4  526.24  5092.8  526.47
  5116.1  531.14  5144.4  531.67  5155.3   534.2  5260.4  542.79  5463.2   554.6
#Mann= 3 ,-1 , 0
  3984.5     .12       0  4985.6     .05       0  4991.8     .12       0
Bank Sta=4985.6,4991.8
XS Rating Curve= 0 ,0
Exp/Cntr=0.3,0.1

Type RM Length L Ch R = 1 ,13754   ,502,502,502
BEGIN DESCRIPTION:
B19561
END DESCRIPTION:
XS GIS Cut Line= 2
      2318803.98     13782734.61       2317465.4      13782604.4
#Sta/Elev= 30
  4362.8  534.36  4562.7  528.57  4683.3  526.29  4874.2  524.44  4964.6  524.68
  4974.7  523.66  4984.7  520.09  5001.7  509.92  5002.2  509.42  5007.9  509.92
  5014.8  515.84  5024.9   518.6  5145.5  516.25  5155.5  513.85  5175.6   511.8
  5185.6  514.22  5195.7  518.24  5205.7  517.69  5233.8  519.81  5238.8  519.23
  5335.7  524.28  5340.7  523.72  5356.4   525.5  5406.7  528.24  5426.8  531.54
  5544.4  540.19  5549.5  539.89    5563  540.95  5581.8  542.44  5707.7  549.91
#Mann= 5 ,-1 , 0
  4362.8     .12       0  5001.7     .05       0  5007.9     .12       0
    5563     .07       0  5581.8     .12       0
Bank Sta=5001.7,5007.9
XS Rating Curve= 0 ,0
Exp/Cntr=0.3,0.1

Type RM Length L Ch R = 1 ,13252   ,474,474,474
BEGIN DESCRIPTION:
B19560
END DESCRIPTION:
XS GIS Cut Line= 3
      2318783.09     13782588.76      2317996.66     13782338.78
      2317419.28     13782182.73
#Sta/Elev= 30
  4048.2  533.11  4455.4  523.55  4791.2  522.58  4837.4  521.12  4871.6  516.03
  4885.5  515.41  4916.6  515.43  4949.1  513.35  4968.4  515.43  4983.8  514.77
  4999.4  509.62  5006.6  508.62  5007.1  508.12  5012.9  508.62  5018.5  513.53
  5023.7  513.29  5040.9  517.22  5051.2  518.15  5058.4  521.77  5063.6  520.67
  5098.3  525.99  5103.4   525.5  5123.7  528.25    5181  530.86  5268.8  535.55
  5287.3  537.48  5292.5  536.87  5327.2  539.51  5446.8  544.67  5471.5  546.91
#Mann= 4 ,-1 , 0
  4048.2     .12       0  5006.6     .05       0  5012.9     .12       0
    5181     .07       0
Bank Sta=5006.6,5012.9
XS Rating Curve= 0 ,0
Exp/Cntr=0.3,0.1

Type RM Length L Ch R = 1 ,12778   ,381,381,381
BEGIN DESCRIPTION:
B19559
END DESCRIPTION:
XS GIS Cut Line= 3
      2318788.35     13782536.71      2318007.08     13781953.36
      2317488.09      13781776.9
#Sta/Elev= 30
  4160.5  533.17  4492.3  527.09  4707.1  519.74  4721.7  516.97  4736.3   516.9
  4742.5  515.48  4771.7  520.14  4813.6  518.52  4871.8  518.82  4942.6   514.1
  4957.2  514.88  4986.4  513.71  4997.7  506.65  4998.2  506.15    5004  506.65
  5021.9  511.43  5042.7  511.51  5057.3  514.63  5063.5  514.03  5071.9  516.61
  5078.1  514.92  5086.5  518.72  5092.7  517.17  5107.3  520.54  5251.5   523.6
  5296.1  524.33  5447.6  530.12  5475.9  531.69  5591.9  537.24  5683.7  537.44
#Mann= 6 ,-1 , 0
  4160.5     .12       0  4997.7     .05       0    5004     .12       0
  5251.5     .07       0  5447.6     .12       0  5475.9     .07       0
Bank Sta=4997.7,5004
XS Rating Curve= 0 ,0
Exp/Cntr=0.3,0.1