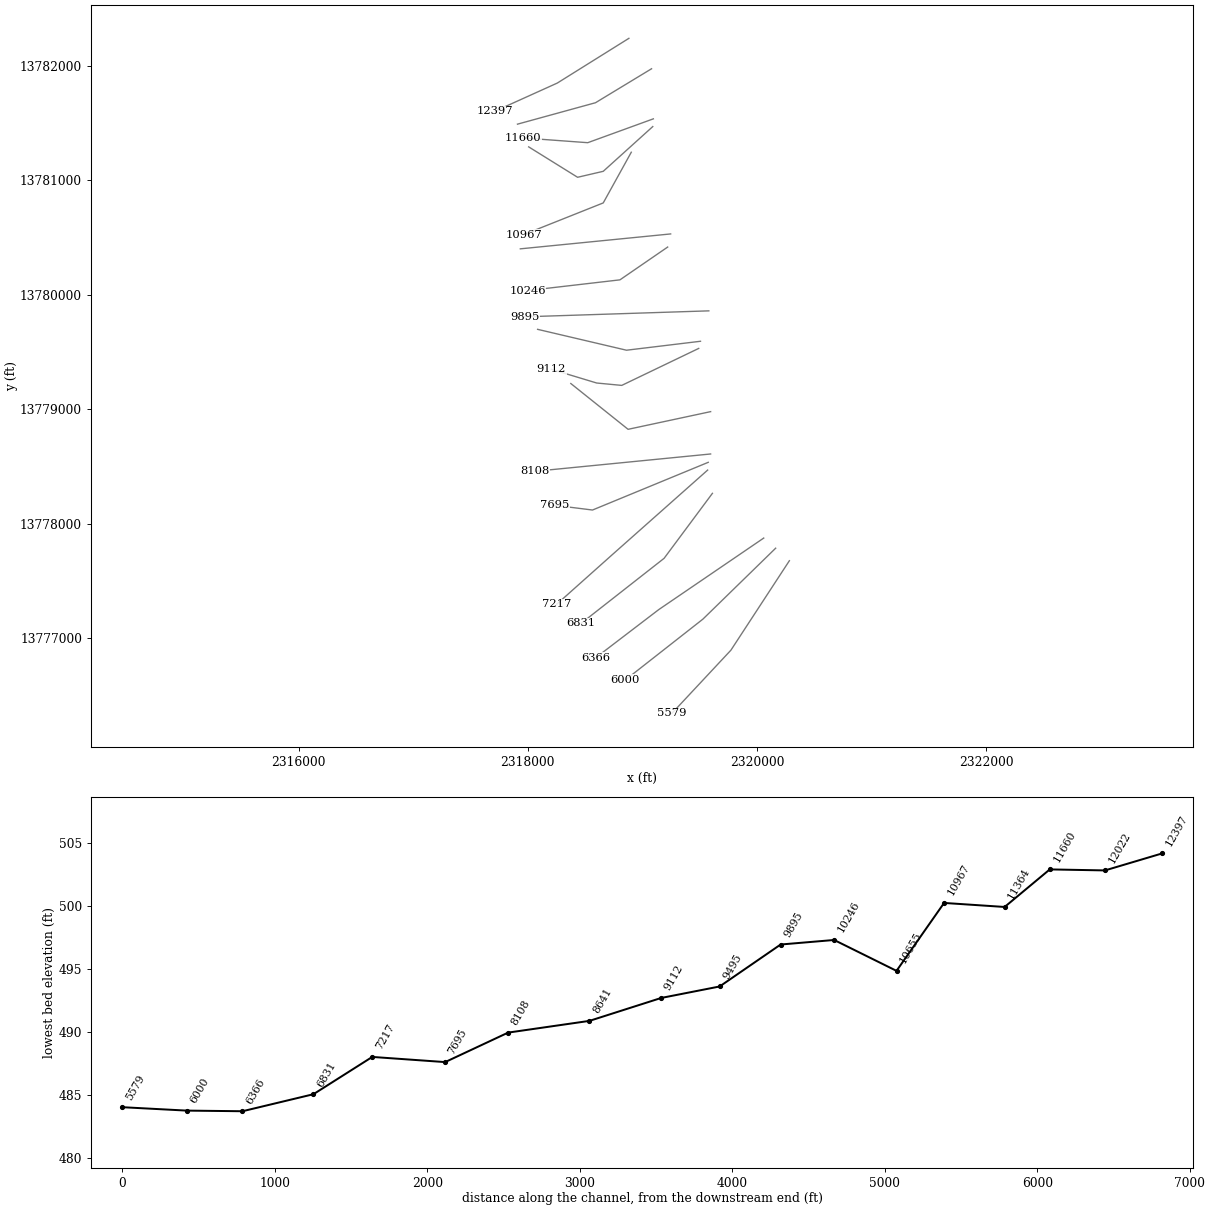
HEC-RAS study MILL TRIBUTARY 7.prj: MILL TRIBUTARY 7 Base Level Engineering

--- MILL TRIBUTARY 7.g01 (geometry) --- (continued)

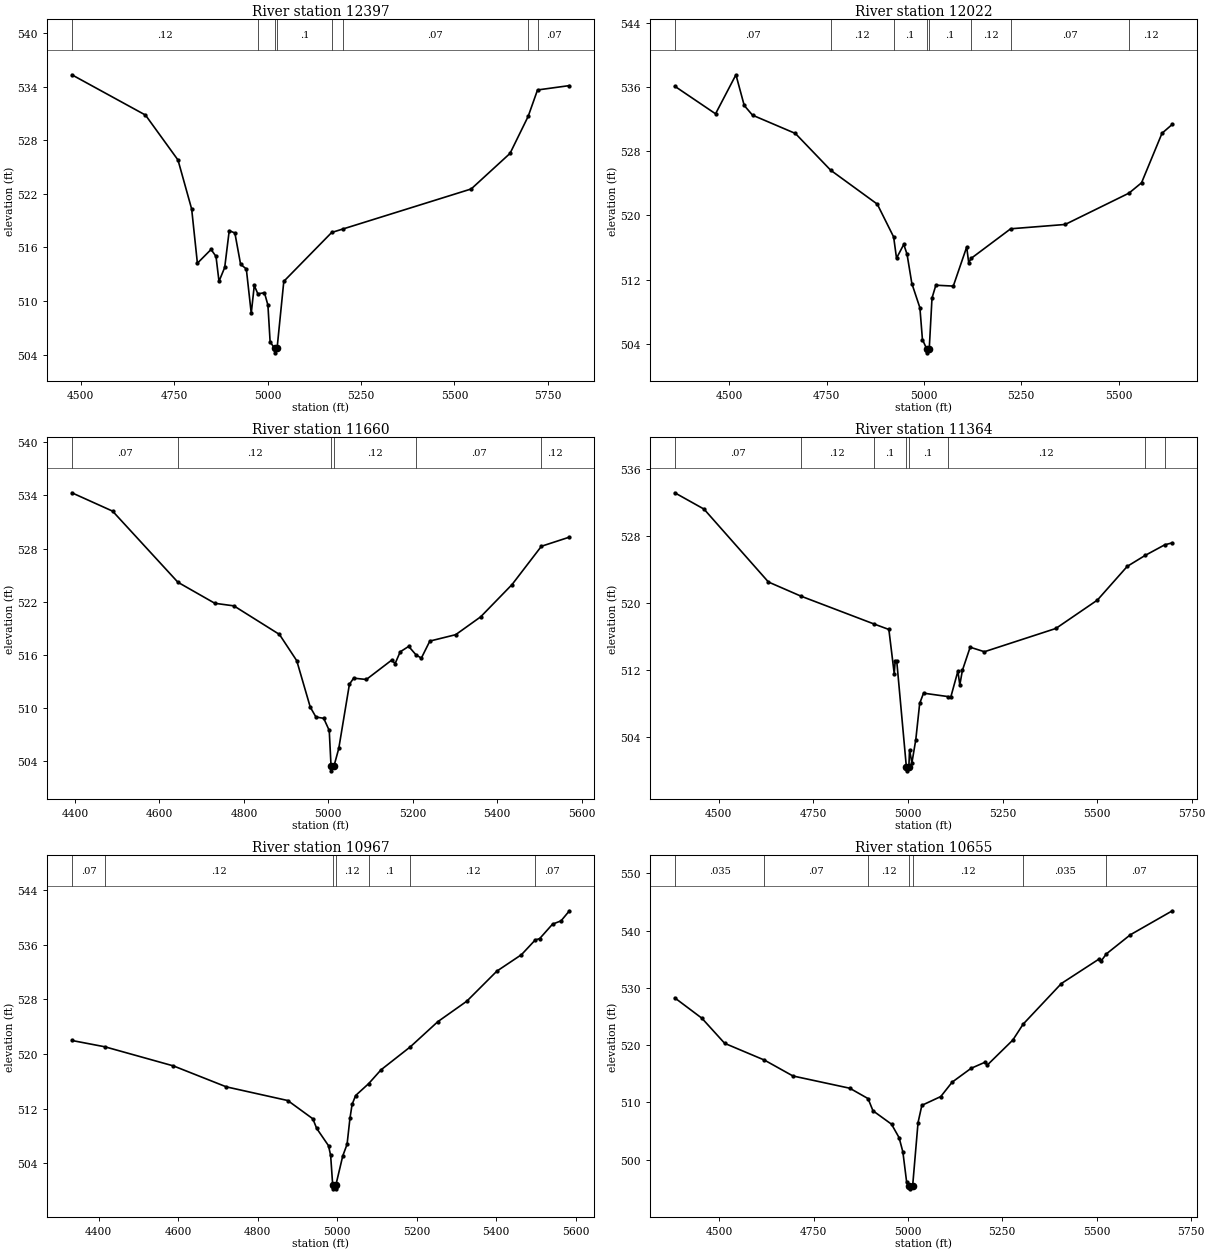
Type RM Length L Ch R = 1 ,12397   ,375,375,375
BEGIN DESCRIPTION:
B19558
END DESCRIPTION:
XS GIS Cut Line= 3
      2318882.06      13782239.8      2318257.08     13781849.19
      2317715.43     13781604.41
#Sta/Elev= 30
  4476.3  535.33  4673.3  530.82  4760.3  525.79  4796.9   520.3  4812.2  514.24
  4848.8  515.78    4862     515    4870  512.21  4885.3  513.77  4897.4  517.89
  4912.5  517.62  4927.8  514.12  4943.1   513.6  4956.3  508.63  4964.4  511.75
  4973.9  510.82  4991.7  510.93  5000.9  509.55  5006.8  505.44  5018.8  504.71
  5019.3  504.21  5025.4  504.71  5043.4  512.21  5171.5  517.68  5200.8  518.06
  5544.8  522.55  5648.7  526.53  5697.2  530.67  5722.3  533.63  5807.7  534.12
#Mann= 8 ,-1 , 0
  4476.3     .12       0  4973.9      .1       0  5018.8     .05       0
  5025.4      .1       0  5171.5     .12       0  5200.8     .07       0
  5697.2     .12       0  5722.3     .07       0
Bank Sta=5018.8,5025.4
XS Rating Curve= 0 ,0
Exp/Cntr=0.3,0.1

Type RM Length L Ch R = 1 ,12022   ,362,362,362
BEGIN DESCRIPTION:
B19557
END DESCRIPTION:
XS GIS Cut Line= 3
      2319079.97     13781974.17      2318590.41     13781677.32
      2317909.39     13781490.17
#Sta/Elev= 30
  4359.5  536.13  4464.3  532.69  4516.7  537.56    4538  533.73  4559.3  532.52
  4669.4  530.24  4760.2  525.65  4879.9  521.42    4922  517.32  4929.4  514.67
    4948  516.39  4956.4  515.18  4968.8  511.51  4989.5  508.48    4996  504.52
  5006.9  503.36  5007.4  502.86  5013.5  503.36  5020.6   509.7  5030.5   511.3
  5075.3  511.19  5109.7  516.06  5114.9  514.13  5121.5  514.66  5222.8  518.34
  5362.8  518.88  5526.8  522.79  5559.1  524.08  5611.7  530.26  5638.3  531.38
#Mann= 8 ,-1 , 0
  4359.5     .07       0  4760.2     .12       0    4922      .1       0
  5006.9     .05       0  5013.5      .1       0  5121.5     .12       0
  5222.8     .07       0  5526.8     .12       0
Bank Sta=5006.9,5013.5
XS Rating Curve= 0 ,0
Exp/Cntr=0.3,0.1

Type RM Length L Ch R = 1 ,11660   ,296,296,296
BEGIN DESCRIPTION:
B19556
END DESCRIPTION:
XS GIS Cut Line= 3
      2319095.66     13781536.71      2318522.71     13781328.36
      2317955.19     13781370.01
#Sta/Elev= 30
  4392.5  534.29    4489  532.22  4643.8   524.2  4731.2  521.83  4776.3  521.54
  4884.2  518.32  4925.2  515.36  4957.2  510.13  4970.6  509.01  4989.1  508.86
  5002.2  507.49  5006.5  503.44    5007  502.94  5013.2  503.44  5024.8  505.47
    5050   512.7    5060  513.39  5090.1  513.24  5150.3  515.43  5158.2  515.03
  5170.3  516.36  5190.4  516.97  5207.9  516.01  5220.4  515.65  5240.5  517.57
  5301.7  518.29  5360.8   520.3  5435.2  523.94  5504.8  528.26  5571.2  529.29
#Mann= 6 ,-1 , 0
  4392.5     .07       0  4643.8     .12       0  5006.5     .05       0
  5013.2     .12       0  5207.9     .07       0  5504.8     .12       0
Bank Sta=5006.5,5013.2
XS Rating Curve= 0 ,0
Exp/Cntr=0.3,0.1

Type RM Length L Ch R = 1 ,11364   ,397,397,397
BEGIN DESCRIPTION:
B19555
END DESCRIPTION:
XS GIS Cut Line= 4
      2319090.43       13781469.      2318658.12     13781078.36
      2318434.16     13781026.28      2318007.12     13781291.88
#Sta/Elev= 30
  4383.5  533.18  4460.8  531.23  4631.1  522.52  4717.1  520.83  4909.9  517.51
  4949.5  516.85  4963.7  511.57  4966.2   513.1  4970.3   513.1  4995.7  500.46
  4996.2  499.96  5002.4  500.46  5004.2  502.48  5010.4  500.91  5020.7  503.68
    5031  508.02  5041.2  509.24  5104.6  508.84  5113.1  508.75    5132  511.87
  5137.1  510.22  5143.9  511.96  5164.4  514.73  5202.1  514.19    5391  516.97
  5500.8  520.36  5579.8  524.39  5627.2   525.7  5679.2  526.97    5699   527.2
#Mann= 8 ,-1 , 0
  4383.5     .07       0  4717.1     .12       0  4909.9      .1       0
  4995.7     .05       0  5002.4      .1       0  5104.6     .12       0
  5627.2     .07       0  5679.2     .12       0
Bank Sta=4995.7,5002.4
XS Rating Curve= 0 ,0
Exp/Cntr=0.3,0.1

Type RM Length L Ch R = 1 ,10967   ,312,312,312
BEGIN DESCRIPTION:
B19554
END DESCRIPTION:
XS GIS Cut Line= 3
       2318902.9       13781245.      2318658.12     13780802.32
      2317965.44     13780526.29
#Sta/Elev= 30
  4332.6  521.97  4416.1  521.04  4588.1  518.25  4721.1  515.19  4875.6  513.19
  4938.7  510.52  4948.4  509.11  4978.1  506.59  4983.5  505.16  4988.7  500.78
  4989.2  500.28  4995.9  500.28  4996.4  500.78    5014   505.1  5024.8  506.79
    5032  510.57  5037.4  512.61  5046.3  513.92  5079.1  515.66  5110.2  517.68
  5183.9  521.04  5253.1  524.72  5325.9  527.71  5401.6  532.11  5463.4  534.51
  5498.2  536.67  5509.2  536.86  5541.5  538.97    5563  539.46  5584.1  540.93
#Mann= 7 ,-1 , 0
  4332.6     .07       0  4416.1     .12       0  4988.7     .05       0
  4996.4     .12       0  5079.1      .1       0  5183.9     .12       0
  5498.2     .07       0
Bank Sta=4988.7,4996.4
XS Rating Curve= 0 ,0
Exp/Cntr=0.3,0.1

Type RM Length L Ch R = 1 ,10655   ,409,409,409
BEGIN DESCRIPTION:
B19553
END DESCRIPTION:
XS GIS Cut Line= 2
      2319246.66     13780531.48       2317934.2     13780401.28
#Sta/Elev= 30
    4382  528.24    4454  524.68  4514.3   520.3  4619.8  517.37  4695.2   514.6
  4845.9  512.46  4894.3  510.65  4907.4  508.52  4956.5  506.18  4976.6  503.83
  4986.6  501.34  4996.7  496.02  5004.1  495.39  5004.6  494.89  5012.5  495.39
  5026.8  506.45  5036.9  509.47  5087.1  511.01  5117.2  513.52  5167.5  515.94
    5205  517.02    5210  516.48    5278  520.87  5305.4  523.65  5406.8  530.75
  5507.7  535.07  5512.7  534.72  5525.8  535.91  5589.6  539.26  5700.9  543.45
#Mann= 7 ,-1 , 0
    4382    .035       0  4619.8     .07       0  4894.3     .12       0
  5004.1     .05       0  5012.5     .12       0  5305.4    .035       0
  5525.8     .07       0
Bank Sta=5004.1,5012.5
XS Rating Curve= 0 ,0
Exp/Cntr=0.3,0.1

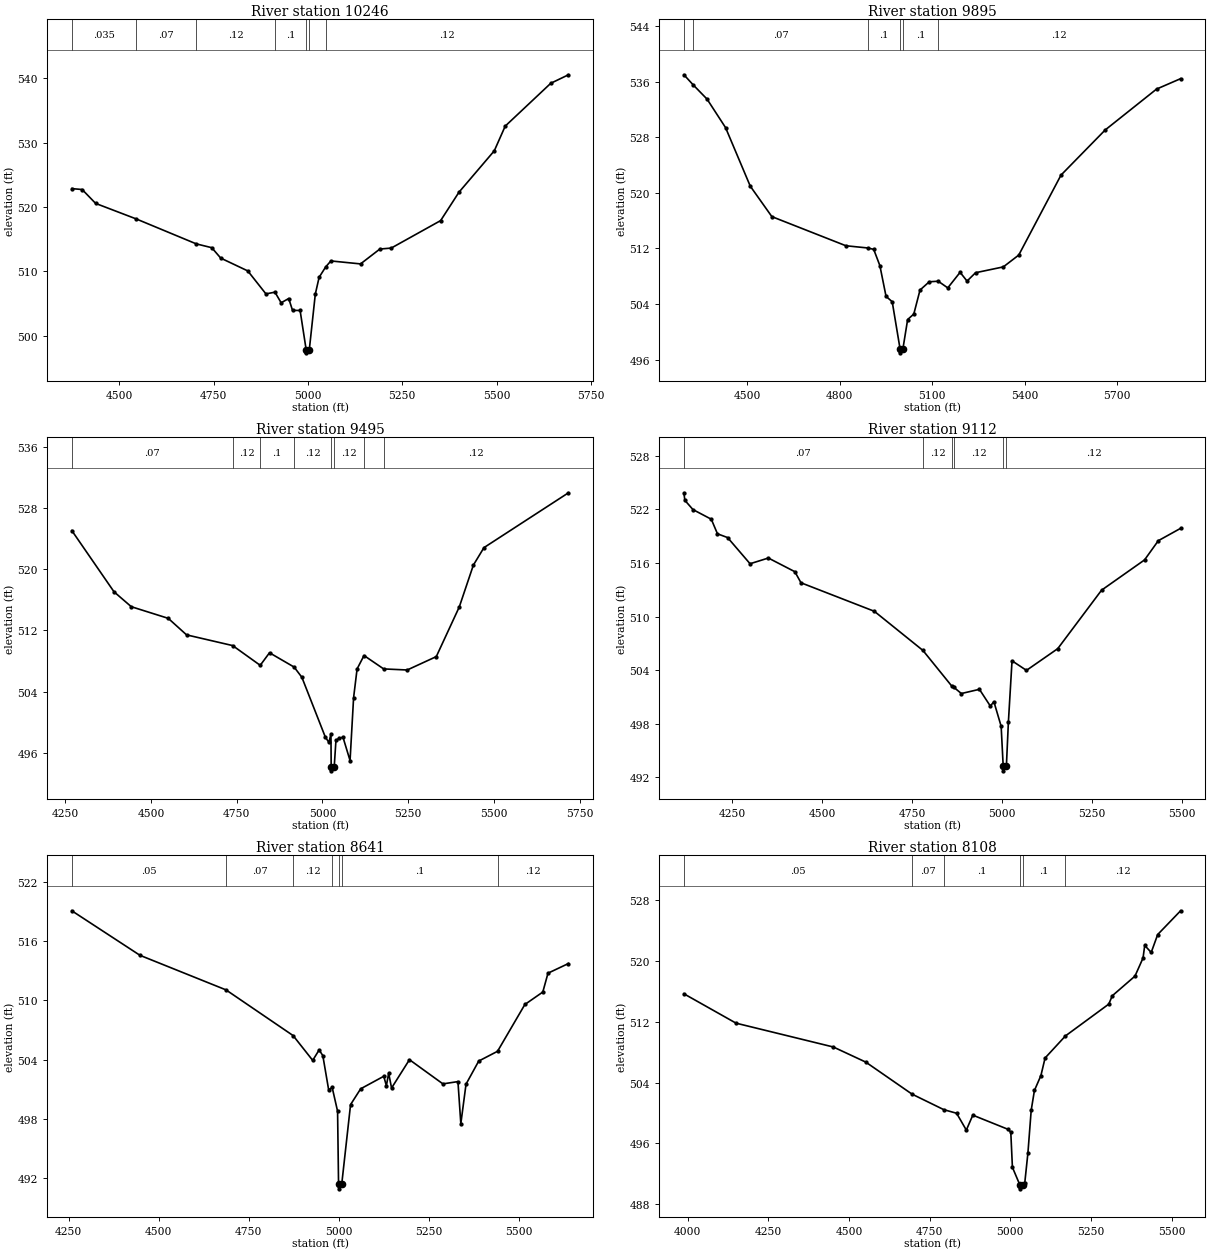
Type RM Length L Ch R = 1 ,10246   ,351,351,351
BEGIN DESCRIPTION:
B19552
END DESCRIPTION:
XS GIS Cut Line= 3
      2319220.59     13780416.88      2318803.96     13780130.44
      2317998.37     13780036.89
#Sta/Elev= 30
  4374.1  522.86  4401.5  522.72  4437.3  520.56  4544.4  518.16  4704.2  514.27
  4745.1  513.68  4768.9  512.06  4840.6  510.07  4888.7   506.5  4912.6  506.77
    4929  505.12  4949.1  505.78  4959.2  503.94  4979.3  503.92  4995.3  497.84
  4995.8  497.34  5003.7  497.84  5019.6  506.47  5029.7  509.08  5047.2   510.7
  5060.9  511.62  5139.5  511.16  5190.7  513.47  5220.9  513.62  5351.8  517.89
  5400.4   522.3  5494.1  528.74    5523  532.57  5643.8  539.23  5690.7  540.55
#Mann= 7 ,-1 , 0
  4374.1    .035       0  4544.4     .07       0  4704.2     .12       0
  4912.6      .1       0  4995.3     .05       0  5003.7      .1       0
  5047.2     .12       0
Bank Sta=4995.3,5003.7
XS Rating Curve= 0 ,0
Exp/Cntr=0.3,0.1

Type RM Length L Ch R = 1 ,9895    ,400,400,400
BEGIN DESCRIPTION:
B19551
END DESCRIPTION:
XS GIS Cut Line= 2
      2319579.95     13779859.61       2317970.6     13779807.52
#Sta/Elev= 30
  4294.8  536.97  4325.2   535.5  4369.8  533.47  4429.8  529.37  4509.9  520.95
  4579.9  516.57    4820  512.38  4891.3  512.06  4910.1  511.86  4930.1  509.52
  4950.1   505.1  4970.1  504.33  4995.8  497.48  4996.3  496.98  5004.5  497.48
  5020.1  501.77  5040.1  502.56  5060.2  506.01  5090.2   507.2  5119.3  507.28
  5150.2  506.32  5190.2  508.56  5212.7   507.3  5240.2   508.5  5330.3  509.34
  5380.3  511.04  5517.3  522.54  5660.5  529.03    5827  534.91    5905  536.41
#Mann= 6 ,-1 , 0
  4294.8     .12       0  4325.2     .07       0  4891.3      .1       0
  4995.8     .05       0  5004.5      .1       0  5119.3     .12       0
Bank Sta=4995.8,5004.5
XS Rating Curve= 0 ,0
Exp/Cntr=0.3,0.1

Type RM Length L Ch R = 1 ,9495    ,383,383,383
BEGIN DESCRIPTION:
B19550
END DESCRIPTION:
XS GIS Cut Line= 3
      2319507.13     13779593.99      2318861.25     13779515.86
      2318085.16     13779698.16
#Sta/Elev= 30
  4269.5  525.05  4392.5  517.05  4442.9   515.1  4550.6  513.58    4604  511.42
  4738.4  510.02  4818.7  507.44  4845.8  509.08  4917.6  507.21  4940.1  505.88
  5008.7  498.04    5019  497.37  5024.9  498.46  5025.6  494.15  5026.1  493.65
  5034.4  494.15  5039.5  497.64  5049.8  497.92    5060  498.04  5080.6  494.99
  5090.9  503.21  5101.1  506.97  5121.3  508.72  5178.6  506.97  5247.2  506.83
    5332  508.58    5399  515.07  5440.1  520.54  5470.9  522.82  5717.3  529.99
#Mann= 8 ,-1 , 0
  4269.5     .07       0  4738.4     .12       0  4818.7      .1       0
  4917.6     .12       0  5025.6     .05       0  5034.4     .12       0
  5121.3      .1       0  5178.6     .12       0
Bank Sta=5025.6,5034.4
XS Rating Curve= 0 ,0
Exp/Cntr=0.3,0.1

Type RM Length L Ch R = 1 ,9112    ,471,471,471
BEGIN DESCRIPTION:
B19549
END DESCRIPTION:
XS GIS Cut Line= 4
      2319491.44     13779531.48      2318819.58     13779208.57
      2318600.83      13779229.4      2318205.03     13779349.18
#Sta/Elev= 30
    4117  523.85  4119.5  523.01  4142.1  521.97    4193  520.89  4210.1  519.26
  4238.2  518.84  4300.6  515.91  4351.4  516.55  4424.9  515.02    4442  513.78
  4645.6  510.59  4780.5  506.21  4861.2  502.19  4866.5  502.08  4887.1  501.39
  4937.3  501.86  4967.5  499.99  4977.5  500.47  4997.6  497.73  5003.3  493.24
  5003.8  492.74  5012.1  493.24  5017.7  498.19  5027.8  505.05  5067.9  503.98
  5154.7  506.41  5276.3  512.95  5395.7  516.34  5433.9  518.49  5495.7  519.87
#Mann= 6 ,-1 , 0
    4117     .07       0  4780.5     .12       0  4861.2      .1       0
  4866.5     .12       0  5003.3     .05       0  5012.1     .12       0
Bank Sta=5003.3,5012.1
XS Rating Curve= 0 ,0
Exp/Cntr=0.3,0.1

Type RM Length L Ch R = 1 ,8641    ,533,533,533
BEGIN DESCRIPTION:
MILL TRIBUTARY 7 16.0
END DESCRIPTION:
XS GIS Cut Line= 3
      2319595.64      13778979.4        2318875.       13778825.
        2318375.       13779225.
#Sta/Elev= 30
    4259  519.08    4448  514.57  4686.5  511.07  4872.7  506.44    4927  503.93
  4944.9  504.99  4955.1  504.41  4971.3  500.94    4981  501.19    4996  498.78
  4998.7  491.42  4999.2  490.92  5007.6  491.42    5032  499.45    5060  501.05
  5124.1  502.32  5131.3  501.36  5137.7  502.63  5145.7  501.13  5195.3     504
  5288.1  501.55  5329.8  501.78  5337.8  497.52  5352.2  501.52  5387.4  503.86
  5439.6  504.85  5515.4  509.59  5565.1  510.85  5579.5  512.76  5636.3  513.74
#Mann= 7 ,-1 , 0
    4259     .05       0  4686.5     .07       0  4872.7     .12       0
    4981      .1       0  4998.7     .05       0  5007.6      .1       0
  5439.6     .12       0
Bank Sta=4998.7,5007.6
XS Rating Curve= 0 ,0
Exp/Cntr=0.3,0.1

Type RM Length L Ch R = 1 ,8108    ,413,413,413
BEGIN DESCRIPTION:
B19548
END DESCRIPTION:
XS GIS Cut Line= 2
      2319595.67     13778609.61       2318064.4     13778458.57
#Sta/Elev= 30
  3988.9  515.69  4150.4  511.82  4451.8  508.68  4552.3  506.69  4695.6  502.47
  4794.2  500.42  4833.7  499.95  4863.8  497.73  4883.9   499.7  4994.4  497.81
  5001.6  497.43  5006.6  492.83  5029.8  490.49  5030.3  489.99  5039.4  490.49
  5044.7   490.7  5054.7  494.75  5064.8  500.35  5074.8  502.95  5094.9  504.92
  5107.8  507.23  5170.9  510.14  5305.1  514.33    5316  515.43  5386.3  518.02
  5411.3  520.41  5416.5  522.06  5436.6  521.14  5456.7   523.5  5527.6  526.63
#Mann= 6 ,-1 , 0
  3988.9     .05       0  4695.6     .07       0  4794.2      .1       0
  5029.8     .05       0  5039.4      .1       0  5170.9     .12       0
Bank Sta=5029.8,5039.4
XS Rating Curve= 0 ,0
Exp/Cntr=0.3,0.1

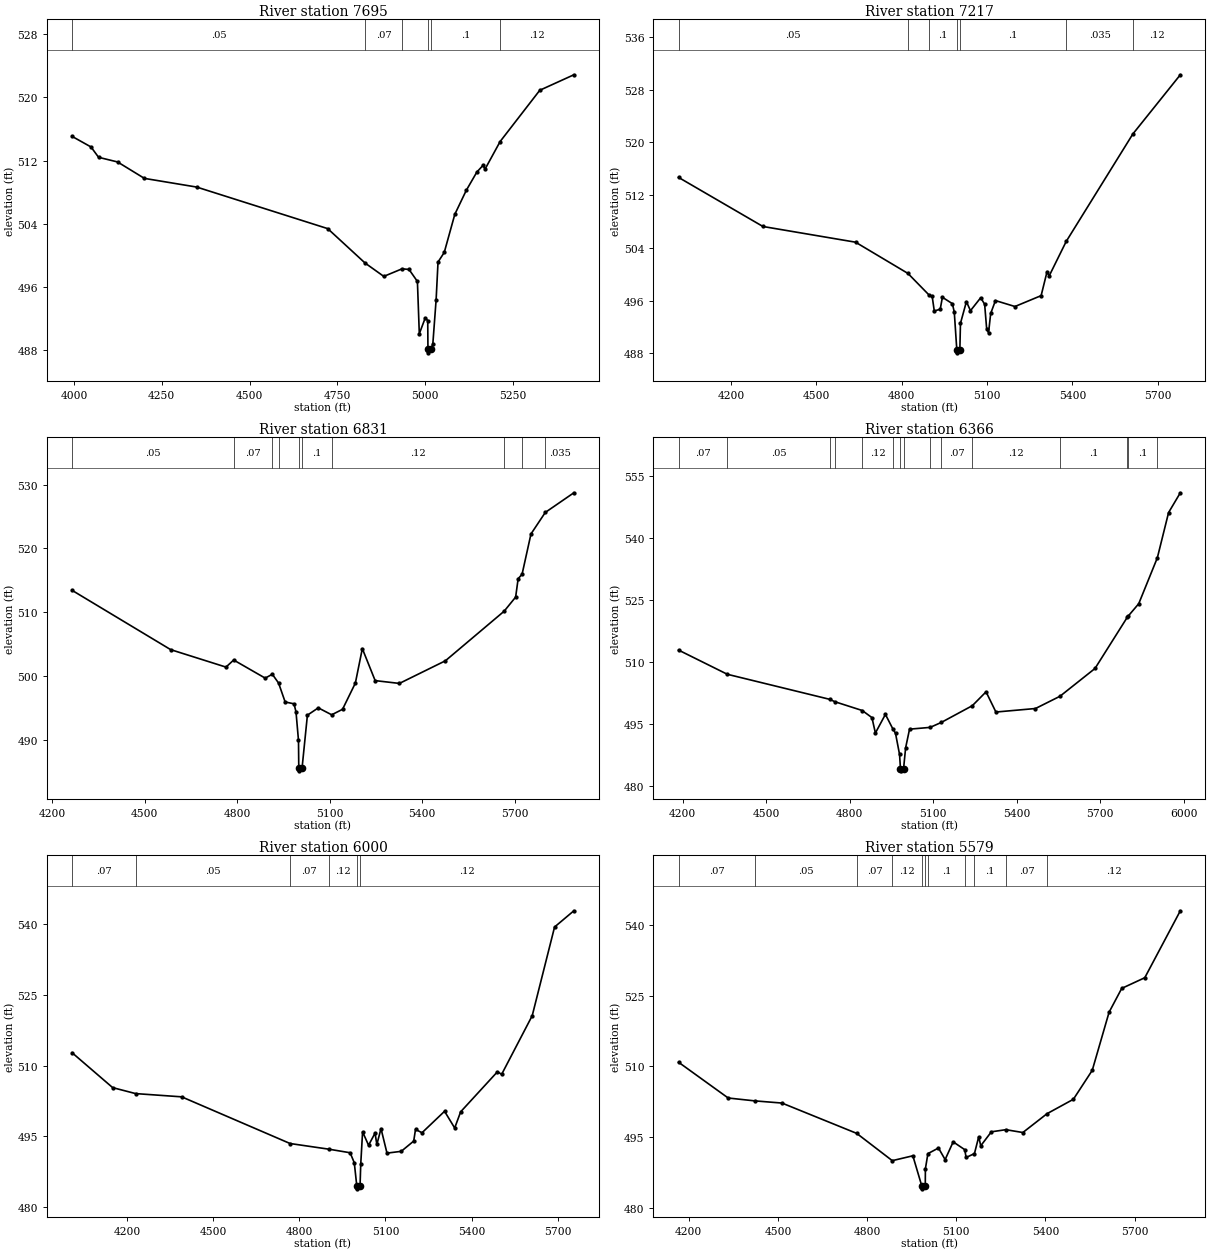
Type RM Length L Ch R = 1 ,7695    ,478,478,478
BEGIN DESCRIPTION:
B19547
END DESCRIPTION:
XS GIS Cut Line= 3
      2319574.81      13778536.7      2318564.37     13778120.03
      2318231.04     13778161.69
#Sta/Elev= 30
  3994.7  515.06  4048.6  513.72  4070.2  512.41  4124.3  511.82  4200.7  509.74
  4349.7  508.64  4722.6  503.38  4829.1  499.02  4882.4  497.33  4934.4  498.29
  4954.2  498.21  4978.1  496.69  4983.5  490.07  5000.5  492.08  5007.5  491.73
  5008.1  488.15  5008.6  487.65  5017.7  488.15  5022.1  488.83  5031.4  494.39
  5036.8  499.15  5054.5  500.36  5084.6  505.19  5117.3  508.23  5147.5  510.55
  5165.4  511.41  5170.4  510.89  5213.7  514.41  5326.6   520.9  5423.6  522.86
#Mann= 6 ,-1 , 0
  3994.7     .05       0  4829.1     .07       0  4934.4      .1       0
  5008.1     .05       0  5017.7      .1       0  5213.7     .12       0
Bank Sta=5008.1,5017.7
XS Rating Curve= 0 ,0
Exp/Cntr=0.3,0.1

Type RM Length L Ch R = 1 ,7217    ,386,386,386
BEGIN DESCRIPTION:
B19546
END DESCRIPTION:
XS GIS Cut Line= 3
       2319569.6       13778469.      2318736.25      13777729.4
      2318251.84     13777297.08
#Sta/Elev= 30
  4015.9  514.68  4312.6  507.23  4637.9  504.85  4822.1  500.11  4895.5  496.87
  4907.2  496.66  4914.7  494.41  4935.6  494.68  4943.2  496.49  4978.3  495.52
    4985  494.24  4993.8  488.56  4994.3  488.06  5004.6  488.56  5006.7  492.53
  5027.6  495.83  5041.9  494.46  5077.8  496.42  5091.7  495.43  5098.7  491.74
  5105.4  491.09  5112.9  494.03  5129.7  495.99  5198.2  495.09  5290.2  496.74
  5311.1  500.39  5318.6  499.74  5378.3  504.96  5612.6  521.27  5779.4  530.25
#Mann= 7 ,-1 , 0
  4015.9     .05       0  4822.1     .07       0  4895.5      .1       0
  4993.8     .05       0  5004.6      .1       0  5378.3    .035       0
  5612.6     .12       0
Bank Sta=4993.8,5004.6
XS Rating Curve= 0 ,0
Exp/Cntr=0.3,0.1

Type RM Length L Ch R = 1 ,6831    ,465,465,465
BEGIN DESCRIPTION:
B19545
END DESCRIPTION:
XS GIS Cut Line= 3
      2319611.22     13778265.82      2319189.37     13777698.15
      2318465.38     13777130.42
#Sta/Elev= 30
  4264.8  513.41  4584.5  504.11  4763.9  501.37  4788.9  502.48  4891.1  499.64
  4914.2  500.25  4934.5  498.87  4955.8   495.9  4984.6  495.61    4991  494.35
  4999.1  489.86    5000   485.6  5000.5   485.1  5010.8   485.6    5028  493.83
  5063.3  494.98  5106.7  493.89  5141.9  494.75  5183.5  498.86  5206.1  504.27
  5247.7  499.25  5326.3  498.81  5475.5  502.36  5666.1  510.14  5703.3  512.35
  5711.4  515.23  5724.2  515.94    5753  522.25  5799.5  525.63  5892.1  528.71
#Mann= 10 ,-1 , 0
  4264.8     .05       0  4788.9     .07       0  4914.2     .12       0
  4934.5      .1       0    5000     .05       0  5010.8      .1       0
  5106.7     .12       0  5666.1      .1       0  5724.2     .12       0
  5799.5    .035       0
Bank Sta=5000,5010.8
XS Rating Curve= 0 ,0
Exp/Cntr=0.3,0.1

Type RM Length L Ch R = 1 ,6366    ,366,366,366
BEGIN DESCRIPTION:
B19544
END DESCRIPTION:
XS GIS Cut Line= 3
      2320059.15     13777875.22       2319142.5     13777250.23
       2318591.5     13776829.19
#Sta/Elev= 30
  4184.9  512.93  4360.3  507.08  4728.1  501.03    4747  500.44  4844.9  498.33
  4879.8  496.61  4892.2  492.89  4928.2  497.39  4954.5  493.94  4964.5  492.81
    4979  487.71  4982.3  484.25  4982.8  483.75  4993.4  484.25  5000.8  489.31
  5014.9  493.82  5088.9  494.25  5129.1  495.45  5240.4  499.49  5289.8  502.84
  5325.2  497.96  5467.4  498.81  5555.4  501.77  5681.3  508.49  5797.9  520.93
  5800.5  521.14  5838.4  524.14  5905.3  535.24  5945.6  546.16  5987.8  550.94
#Mann= 15 ,-1 , 0
  4184.9     .07       0  4360.3     .05       0  4728.1     .12       0
    4747     .05       0  4844.9     .12       0  4954.5      .1       0
  4982.3     .05       0  4993.4      .1       0  5088.9     .12       0
  5129.1     .07       0  5240.4     .12       0  5555.4      .1       0
  5797.9     .12       0  5800.5      .1       0  5905.3     .12       0
Bank Sta=4982.3,4993.4
XS Rating Curve= 0 ,0
Exp/Cntr=0.3,0.1

Type RM Length L Ch R = 1 ,6000    ,421,421,421
BEGIN DESCRIPTION:
B19543
END DESCRIPTION:
XS GIS Cut Line= 3
      2320163.36     13777786.72      2319527.91      13777166.9
      2318850.82     13776635.65
#Sta/Elev= 30
  4008.2  512.73  4149.6  505.31  4229.7  504.04  4390.1  503.35  4767.8  493.43
  4902.6  492.23    4977  491.47  4991.5  489.34  5000.4   484.3  5000.9   483.8
  5011.5   484.3    5014  489.08  5020.4  495.92  5041.2  493.06  5063.8  495.64
  5070.1  493.23  5084.6   496.6  5105.4  491.39  5155.1  491.77  5198.5  493.95
  5204.8  496.43  5227.4  495.72    5306  500.28  5341.3  496.73  5362.1  500.17
  5490.4  508.69  5504.9  508.13  5611.4  520.59  5689.3  539.44  5756.5  542.89
#Mann= 6 ,-1 , 0
  4008.2     .07       0  4229.7     .05       0  4767.8     .07       0
  4902.6     .12       0  5000.4     .05       0  5011.5     .12       0
Bank Sta=5000.4,5011.5
XS Rating Curve= 0 ,0
Exp/Cntr=0.3,0.1

Type RM Length L Ch R = 1 ,5579    ,491,491,491
BEGIN DESCRIPTION:
B19542
END DESCRIPTION:
XS GIS Cut Line= 3
      2320283.12     13777677.32      2319772.71     13776896.07
       2319257.1     13776344.01
#Sta/Elev= 30
  4165.5  510.89  4332.6  503.31  4422.4   502.7  4513.6  502.24    4765  495.82
  4884.8  490.04    4954  491.07  4984.6  484.57  4985.1  484.07  4995.8  484.57
  4996.2  488.32  5004.7  491.53  5040.3  492.72  5062.6  490.26  5089.7  494.02
  5128.6  492.37  5133.2  490.71  5161.3  491.54  5175.7  495.11  5182.5  493.19
  5218.2  496.15  5267.1   496.6  5324.2     496  5405.6  499.99  5494.2  503.04
  5557.7  509.17  5614.4  521.49  5656.9  526.53  5734.5  528.79  5854.1  542.97
#Mann= 11 ,-1 , 0
  4165.5     .07       0  4422.4     .05       0    4765     .07       0
  4884.8     .12       0  4984.6     .05       0  4995.8     .12       0
  5004.7      .1       0  5128.6     .12       0  5161.3      .1       0
  5267.1     .07       0  5405.6     .12       0
Bank Sta=4984.6,4995.8
XS Rating Curve= 0 ,0
Exp/Cntr=0.3,0.1