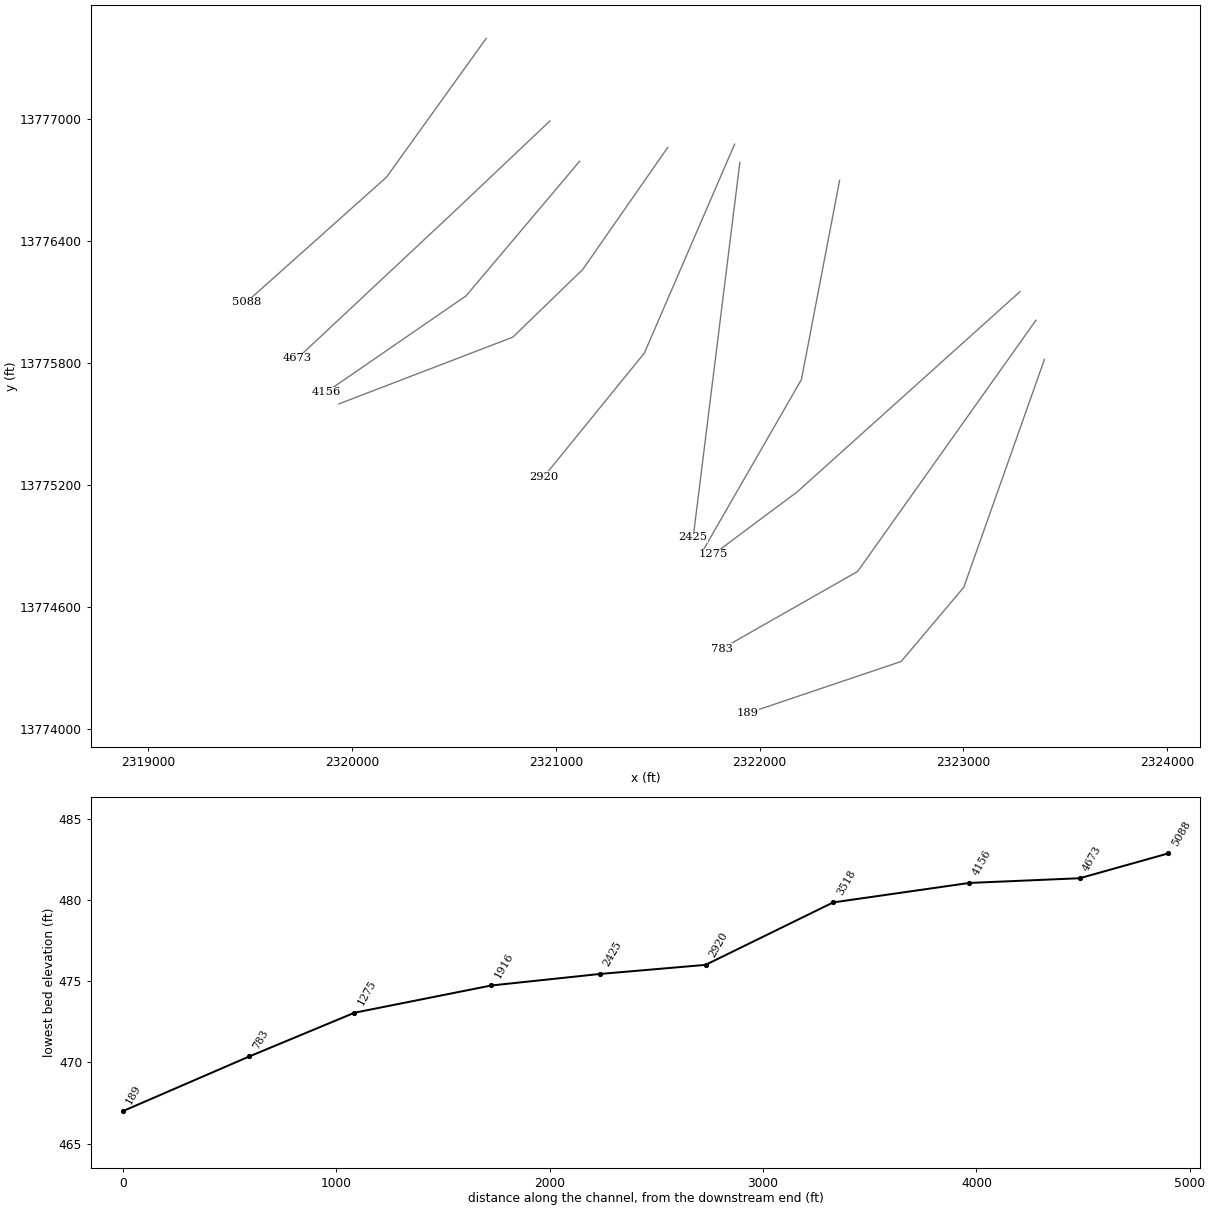
HEC-RAS study MILL TRIBUTARY 7.prj: MILL TRIBUTARY 7 Base Level Engineering

--- MILL TRIBUTARY 7.g01 (geometry) --- (continued)

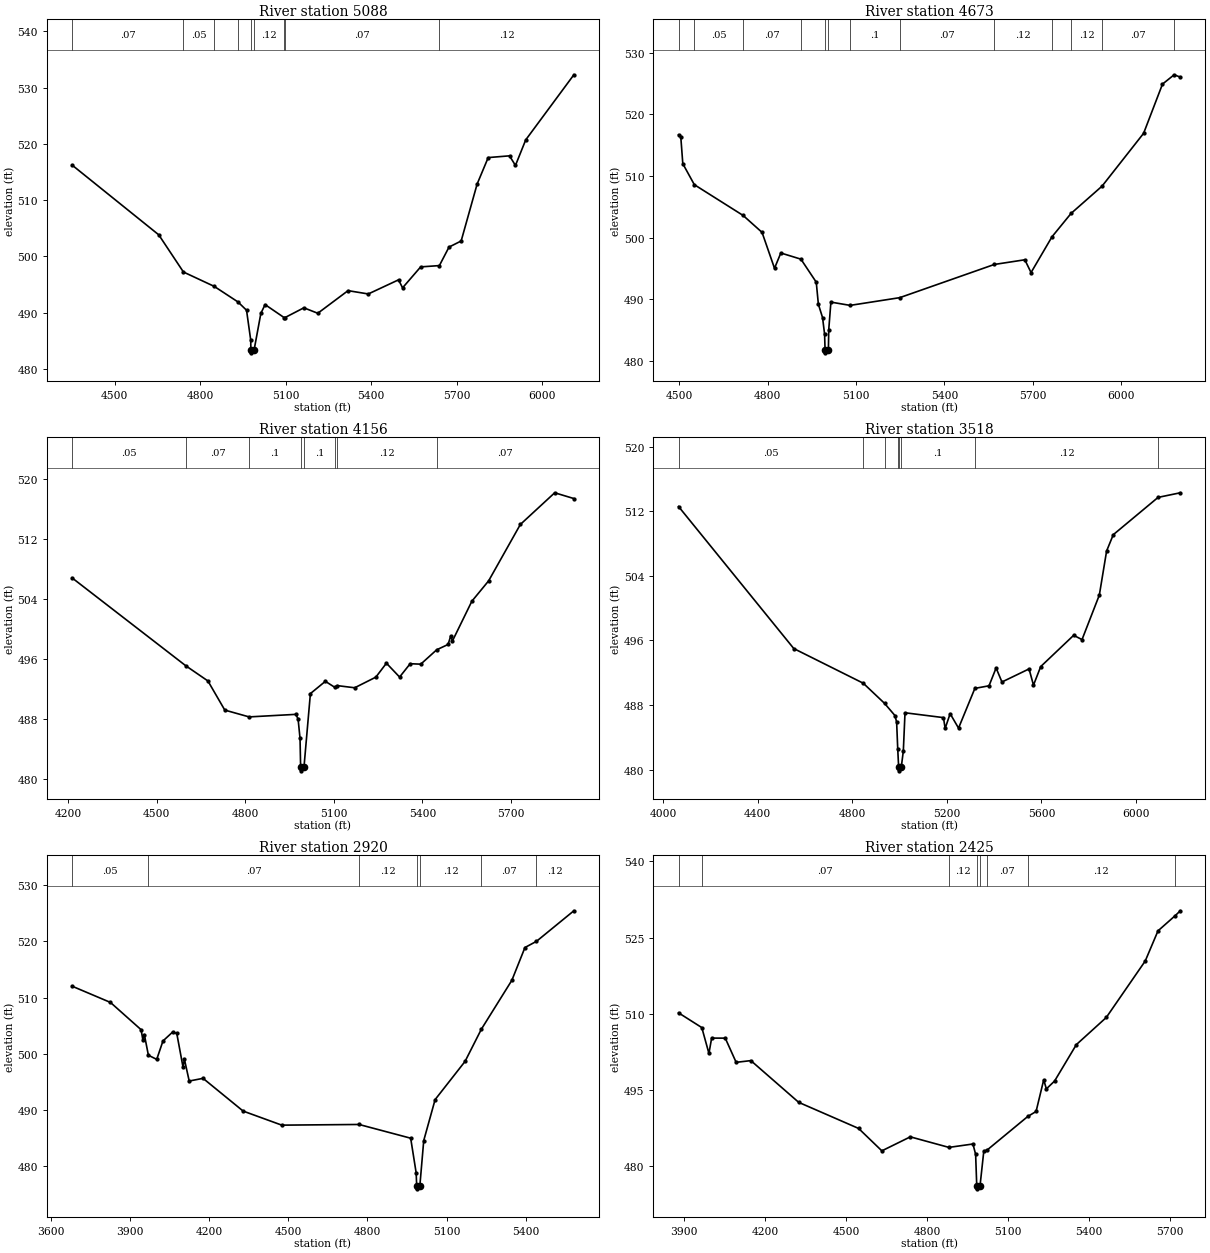
Type RM Length L Ch R = 1 ,5088    ,415,415,415
BEGIN DESCRIPTION:
B19541
END DESCRIPTION:
XS GIS Cut Line= 3
       2320658.1     13777396.04      2320168.54     13776713.78
      2319481.48     13776099.58
#Sta/Elev= 30
  4350.4  516.24  4654.6  503.85  4741.3  497.24  4849.3  494.69  4932.5  491.93
  4962.8  490.45  4977.5  485.13    4978  483.38  4978.5  482.88  4989.3  483.38
  5013.1   489.9  5027.9  491.45  5094.8  489.14  5096.8  489.12    5164  490.88
  5212.9  489.91  5319.1  493.93  5390.1  493.34  5496.3  495.85  5510.5  494.43
    5574  498.15  5639.7  498.38  5673.5  501.67  5716.1  502.75  5772.2  512.87
    5811  517.57  5885.8  517.88  5906.7  516.17  5942.7  520.71  6111.7  532.28
#Mann= 9 ,-1 , 0
  4350.4     .07       0  4741.3     .05       0  4849.3     .07       0
  4932.5     .12       0    4978     .05       0  4989.3     .12       0
  5094.8      .1       0  5096.8     .07       0  5639.7     .12       0
Bank Sta=4978,4989.3
XS Rating Curve= 0 ,0
Exp/Cntr=0.3,0.1

Type RM Length L Ch R = 1 ,4673    ,517,517,517
BEGIN DESCRIPTION:
B19540
END DESCRIPTION:
XS GIS Cut Line= 3
      2320970.66     13776989.85      2320475.83     13776521.07
      2319731.05     13775823.16
#Sta/Elev= 30
  4497.9  516.68  4505.5  516.37  4512.4     512  4551.5   508.6  4717.1  503.61
  4781.2  500.87  4823.5  495.05  4844.9  497.53  4913.1  496.53  4965.1   492.8
  4972.3  489.22  4986.5  487.06  4993.4  484.36    4995  481.85  4995.5  481.35
  5006.3  481.85  5007.5  485.11  5014.8  489.57  5080.1  489.04  5248.2  490.29
    5569  495.67  5672.7  496.43  5693.8  494.36  5764.9  500.16  5829.5  503.94
  5934.6  508.36  6075.7  516.93  6139.7   524.9  6179.2  526.41  6200.2  526.03
#Mann= 13 ,-1 , 0
  4497.9     .07       0  4551.5     .05       0  4717.1     .07       0
  4913.1     .12       0    4995     .05       0  5006.3     .12       0
  5080.1      .1       0  5248.2     .07       0    5569     .12       0
  5764.9     .07       0  5829.5     .12       0  5934.6     .07       0
  6179.2     .12       0
Bank Sta=4995,5006.3
XS Rating Curve= 0 ,0
Exp/Cntr=0.3,0.1

Type RM Length L Ch R = 1 ,4156    ,638,638,638
BEGIN DESCRIPTION:
B19539
END DESCRIPTION:
XS GIS Cut Line= 3
      2321116.48     13776791.93      2320559.16     13776130.44
      2319871.67     13775656.49
#Sta/Elev= 30
  4212.9  506.82  4598.4  495.08  4673.1  493.06  4730.3  489.17  4812.7  488.26
  4970.9   488.6  4978.6  487.99  4985.2   485.4  4987.2  481.56  4987.7  481.06
  4998.6  481.56  5020.3  491.37    5071  493.01  5103.7  492.19  5110.7  492.44
  5170.4  492.15  5242.1  493.57  5277.9  495.43  5322.5  493.58  5358.4  495.36
  5394.2   495.3  5448.2  497.22  5486.8  497.93  5495.7  499.06  5501.7  498.41
  5567.3   503.7  5624.1  506.42  5731.6  513.95    5848  518.18  5912.9  517.41
#Mann= 8 ,-1 , 0
  4212.9     .05       0  4598.4     .07       0  4812.7      .1       0
  4987.2     .05       0  4998.6      .1       0  5103.7     .07       0
  5110.7     .12       0  5448.2     .07       0
Bank Sta=4987.2,4998.6
XS Rating Curve= 0 ,0
Exp/Cntr=0.3,0.1

Type RM Length L Ch R = 1 ,3518    ,598,598,598
BEGIN DESCRIPTION:
B19538
END DESCRIPTION:
XS GIS Cut Line= 4
      2321548.77     13776859.65      2321132.08     13776260.65
      2320788.33     13775927.32      2319935.22      13775599.6
#Sta/Elev= 30
  4064.8  512.59  4552.3     495  4846.1  490.71    4936  488.22  4980.3   486.7
  4987.3  485.89    4992  482.53  4995.7  480.36  4996.2  479.86  5007.1  480.36
  5015.6  482.31  5022.7  487.05  5185.3  486.45  5192.5  485.11  5213.6  486.94
  5249.1  485.15  5318.2  490.07    5378  490.39    5408   492.6  5432.7  490.86
  5547.4  492.48  5566.1  490.47  5596.7  492.77    5736  496.64  5771.4  496.11
  5844.6  501.62  5875.4  507.08  5903.6   509.1  6093.1  513.72  6187.2  514.29
#Mann= 8 ,-1 , 0
  4064.8     .05       0  4846.1     .07       0    4936     .12       0
    4992      .1       0  4995.7     .05       0  5007.1      .1       0
  5318.2     .12       0  6093.1     .07       0
Bank Sta=4995.7,5007.1
XS Rating Curve= 0 ,0
Exp/Cntr=0.3,0.1

Type RM Length L Ch R = 1 ,2920    ,495,495,495
BEGIN DESCRIPTION:
B19537
END DESCRIPTION:
XS GIS Cut Line= 3
      2321876.89     13776875.28      2321434.16     13775849.19
      2320939.74     13775240.27
#Sta/Elev= 30
  3680.3  512.03  3825.8  509.14    3942  504.29  3948.8  502.44  3954.2  503.44
  3969.6  499.75  4001.2  499.02  4024.8  502.29  4061.8  503.89  4077.2  503.62
  4100.7  497.68  4106.2  499.01  4124.3  495.17  4176.7  495.65  4328.7  489.83
  4475.2  487.33    4768  487.45  4963.7  485.01  4984.5  478.85  4986.5  476.51
    4987  476.01  4998.4  476.51  5013.2  484.59  5056.3  491.87  5169.8  498.66
  5231.7  504.39  5347.3  513.08  5396.8   518.9  5440.5     520  5582.2  525.43
#Mann= 7 ,-1 , 0
  3680.3     .05       0  3969.6     .07       0    4768     .12       0
  4986.5     .05       0  4998.4     .12       0  5231.7     .07       0
  5440.5     .12       0
Bank Sta=4986.5,4998.4
XS Rating Curve= 0 ,0
Exp/Cntr=0.3,0.1

Type RM Length L Ch R = 1 ,2425    ,509,509,509
BEGIN DESCRIPTION:
B19536
END DESCRIPTION:
XS GIS Cut Line= 2
      2321902.91     13776786.65      2321673.75     13774942.94
#Sta/Elev= 30
  3879.9  510.15  3966.1  507.24  3992.4  502.15  4002.5  505.17  4052.9  505.16
  4093.2  500.39  4147.7  500.73  4324.9   492.5  4546.6  487.36  4632.7  482.94
  4738.1   485.7    4881  483.62  4969.9  484.29  4979.9  482.26  4984.1  475.95
  4984.6  475.45    4996  475.95  5010.2  482.91  5021.6  483.06    5173  489.72
  5203.7   490.7  5231.9  496.93  5241.9  495.16  5272.2   496.7  5352.8  503.88
  5463.6  509.23  5607.9  520.37  5655.1  526.31  5718.4  529.29  5737.8  530.27
#Mann= 8 ,-1 , 0
  3879.9     .05       0  3966.1     .07       0    4881     .12       0
  4984.1     .05       0    4996     .12       0  5021.6     .07       0
    5173     .12       0  5718.4     .07       0
Bank Sta=4984.1,4996
XS Rating Curve= 0 ,0
Exp/Cntr=0.3,0.1

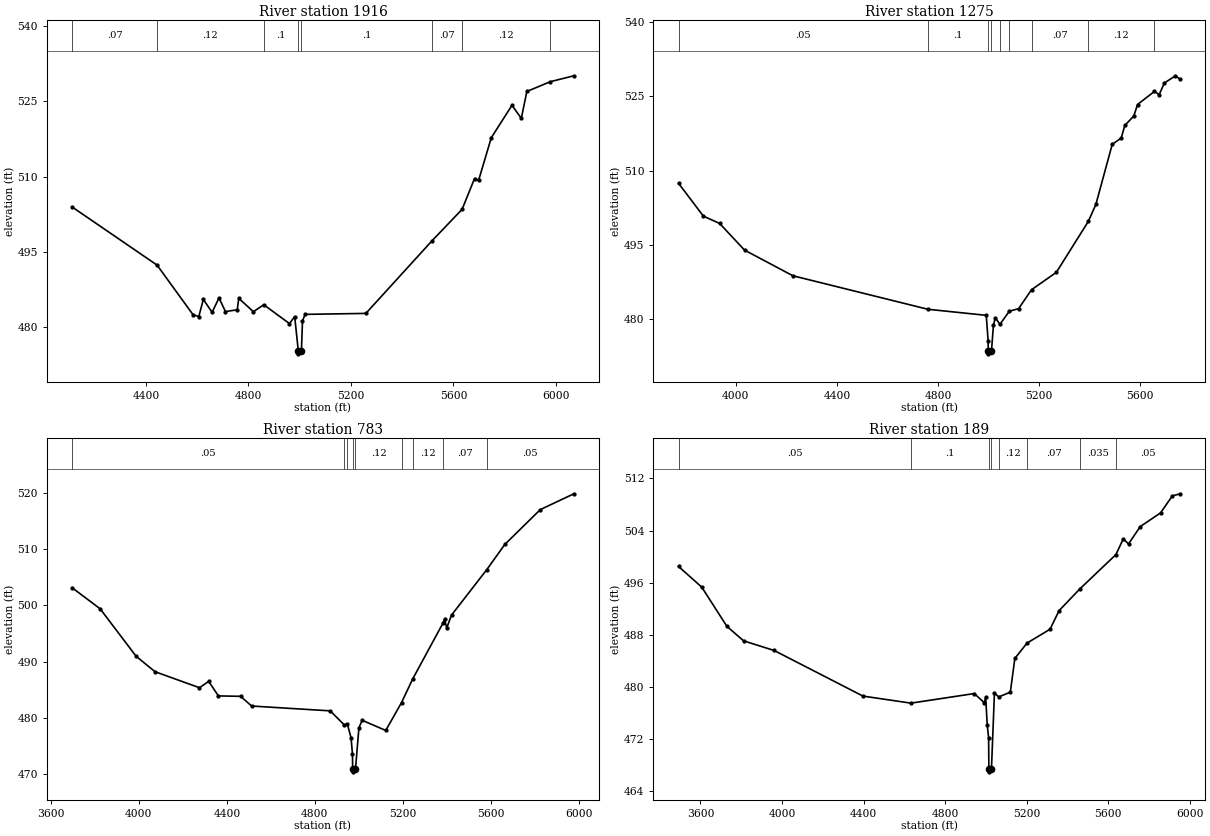
Type RM Length L Ch R = 1 ,1916    ,641,641,641
BEGIN DESCRIPTION:
B19535
END DESCRIPTION:
XS GIS Cut Line= 3
      2322392.49     13776698.12        2322205.     13775718.98
      2321725.83     13774885.65
#Sta/Elev= 30
  4111.5  503.95  4443.3  492.38    4583  482.56  4605.9  482.13  4623.8  485.56
  4657.9     483  4684.9  485.86    4710  483.15  4756.1  483.49    4762  485.78
  4819.1  483.12  4859.6   484.5  4959.8  480.76  4980.3  482.15  4994.5  475.24
    4995  474.74  5006.5  475.24  5010.7  481.26  5020.8  482.59    5258  482.78
  5516.2  497.22  5633.5  503.47  5682.1   509.6  5697.9  509.22  5747.5  517.72
  5828.2  524.16  5864.7  521.56  5886.2  526.91  5978.2  528.86  6069.7  530.03
#Mann= 8 ,-1 , 0
  4111.5     .07       0  4443.3     .12       0  4859.6      .1       0
  4994.5     .05       0  5006.5      .1       0  5516.2     .07       0
  5633.5     .12       0  5978.2     .07       0
Bank Sta=4994.5,5006.5
XS Rating Curve= 0 ,0
Exp/Cntr=0.3,0.1

Type RM Length L Ch R = 1 ,1275    ,492,492,492
BEGIN DESCRIPTION:
B19534
END DESCRIPTION:
XS GIS Cut Line= 3
      2323277.88     13776151.24      2322184.16      13775166.9
      2321772.93     13774859.78
#Sta/Elev= 30
  3773.8  507.43    3872  500.81  3936.2  499.34  4034.9  493.96  4226.2  488.79
  4760.1  482.04  4990.9  480.82  4998.3  475.67  4998.7  473.56  4999.2  473.06
  5011.4  473.56  5019.3  478.79  5026.7  480.37  5044.7  478.99  5082.2  481.65
  5118.7  482.16    5170  485.98  5268.2  489.48  5394.4  499.73  5424.5  503.17
  5489.2  515.28  5524.6  516.53  5539.2  519.11  5574.6  520.98  5589.2   523.3
  5656.3  525.95  5674.7  525.27  5695.5  527.64  5739.3  529.09  5758.5  528.35
#Mann= 9 ,-1 , 0
  3773.8     .05       0  4760.1      .1       0  4998.7     .05       0
  5011.4      .1       0  5044.7     .12       0  5082.2      .1       0
    5170     .07       0  5394.4     .12       0  5656.3     .07       0
Bank Sta=4998.7,5011.4
XS Rating Curve= 0 ,0
Exp/Cntr=0.3,0.1

Type RM Length L Ch R = 1 ,783     ,594,594,594
BEGIN DESCRIPTION:
B19533
END DESCRIPTION:
XS GIS Cut Line= 3
      2323356.05     13776010.67      2322481.04     13774776.28
       2321814.4     13774396.09
#Sta/Elev= 30
  3696.6  503.16  3824.1  499.41  3987.7  490.95  4073.8   488.2  4275.6  485.35
  4317.4  486.48  4361.7  483.89  4462.7  483.82  4512.6  482.09  4869.9  481.23
  4934.2   478.7  4947.4  478.94  4964.7  476.39  4970.8   473.6    4972  470.87
  4972.5  470.37  4984.7  470.87  5000.3  478.23  5015.1  479.55  5122.2  477.74
  5193.8   482.7  5244.8  486.92  5382.8   496.9  5389.4  497.52  5399.5  496.01
  5421.1  498.28  5581.7   506.4  5663.1  510.86  5824.5  517.07  5977.1  519.89
#Mann= 9 ,-1 , 0
  3696.6     .05       0  4934.2     .07       0  4947.4     .12       0
    4972     .05       0  4984.7     .12       0  5193.8      .1       0
  5244.8     .12       0  5382.8     .07       0  5581.7     .05       0
Bank Sta=4972,4984.7
XS Rating Curve= 0 ,0
Exp/Cntr=0.3,0.1

Type RM Length L Ch R = 1 ,189     ,0,0,0
BEGIN DESCRIPTION:
B19532
END DESCRIPTION:
XS GIS Cut Line= 4
      2323397.71     13775817.95      2323001.87     13774698.15
      2322694.58     13774333.57      2321939.73     13774078.48
#Sta/Elev= 30
  3492.4   498.5  3606.2  495.33  3729.9   489.3    3812  487.08  3961.3  485.61
  4397.1  478.61  4632.2  477.53    4943     479  4992.4  477.59    4999  478.43
  5006.7   474.1  5013.3  472.22  5014.6  467.49  5015.1  466.99  5027.4  467.49
  5041.9  479.09  5062.8  478.48  5119.9  479.22    5142  484.39  5201.6  486.74
  5314.8  488.87  5358.9  491.72  5461.7  495.08  5637.7  500.32  5673.7  502.72
  5699.6  501.96  5757.2  504.62  5856.8  506.72  5914.5  509.33  5953.7  509.65
#Mann= 8 ,-1 , 0
  3492.4     .05       0  4632.2      .1       0  5014.6     .05       0
  5027.4      .1       0  5062.8     .12       0  5201.6     .07       0
  5461.7    .035       0  5637.7     .05       0
Bank Sta=5014.6,5027.4
XS Rating Curve= 0 ,0
Exp/Cntr=0.3,0.1

Chan Stop Cuts=-1
Use User Specified Reach Order=0
Composite Channel Slope=5