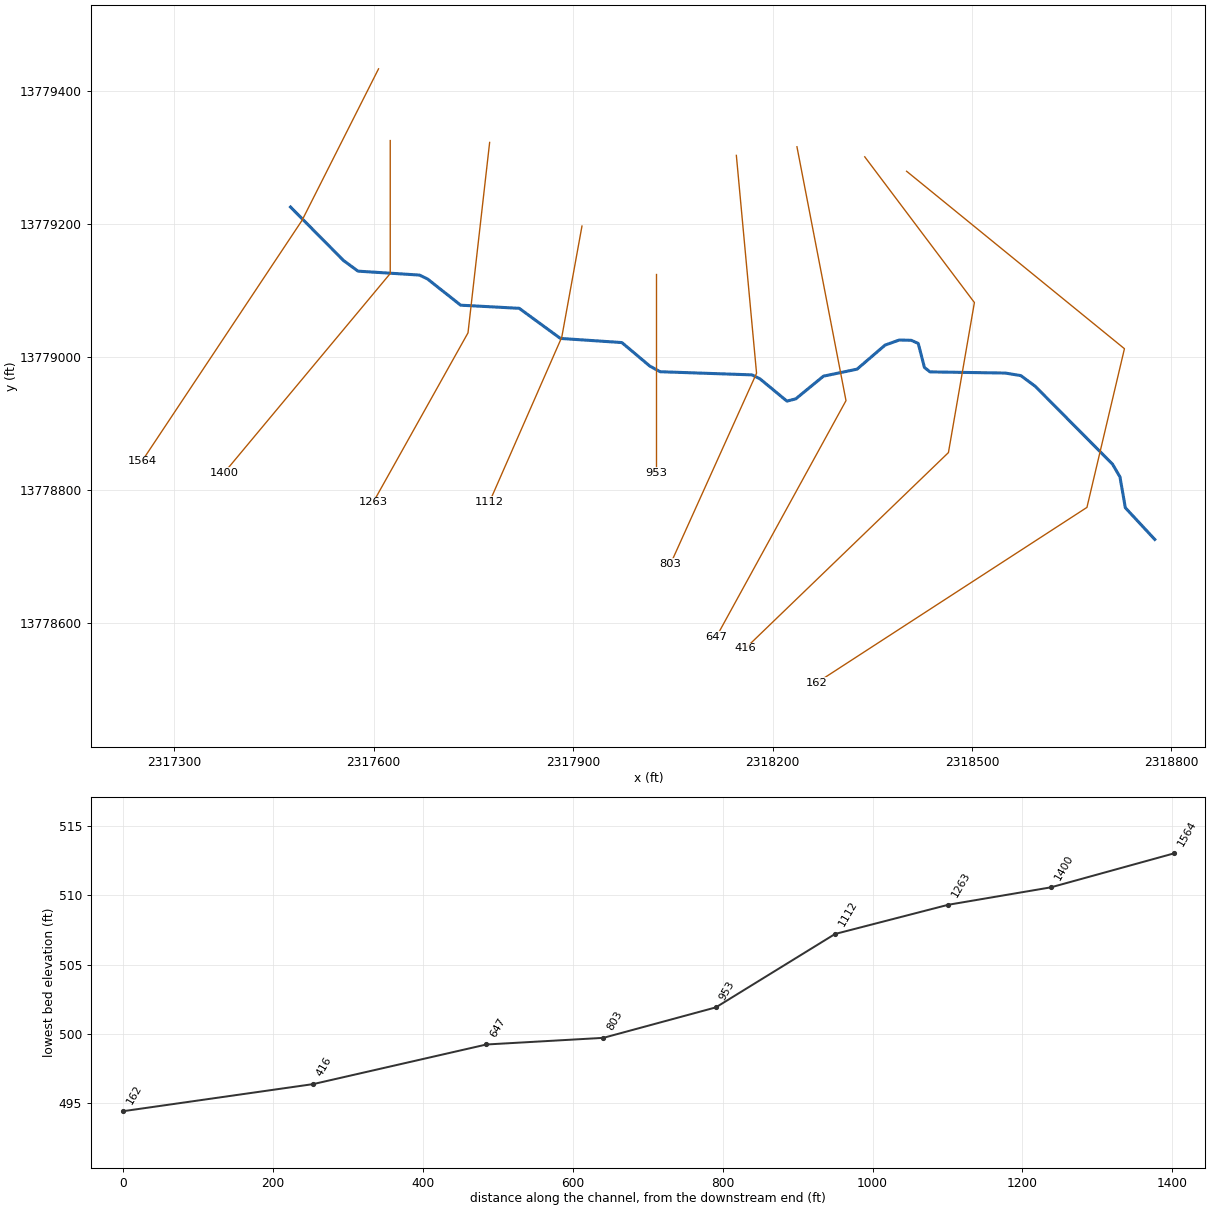
--- MILL TRIBUTARY 8B.prj (project) ---

Proj Title=MILL TRIBUTARY 8B Base Level Engineering
Current Plan=p01
Default Exp/Contr=0.3,0.1
English Units
Geom File=g01
Flow File=f01
Plan File=p01
BEGIN DESCRIPTION:
MILL TRIBUTARY 8B
END DESCRIPTION:

--- MILL TRIBUTARY 8B.p01 (plan) ---

Plan Title=Multiple Run
Short Identifier=Multiple
Geom File=g01
Flow File=f01
Subcritical Flow
K Sum by GR= 0
Std Step Tol= 0.01
Critical Tol= 0.01
Num of Std Step Trials= 20
Max Error Tol= 0.3
Flow Tol Ratio= 0.001
Split Flow NTrial= 30
Split Flow Tol= 0.02
Split Flow Ratio= 0.02
Log Output Level= 0
Friction Slope Method= 1
Unsteady Friction Slope Method= 2
Unsteady Bridges Friction Slope Method= 1
Parabolic Critical Depth
Global Vel Dist=  1 , 1 , 1
Global Log Level= 0
CheckData=True
Encroach Param= -1, 0, 0, 0
BEGIN DESCRIPTION:
Multiple Run
END DESCRIPTION:

--- MILL TRIBUTARY 8B.f01 (steady flow) ---

Flow Title=Multiple
Number of Profiles=7
Profile Names=10-year,25-year,50-year,1pct_min,100-year,1pct_plu,500-year
River Rch & RM= MILL TRIBUTARY 8,Reach-1,1564
     293     456     600     384     767    1530    1236
Boundary for River Rch & Prof#=MILL TRIBUTARY 8,Reach-1,1
Up Type=0
Dn Type=3
Dn Slope=0.005
Boundary for River Rch & Prof#=MILL TRIBUTARY 8,Reach-1,2
Up Type=0
Dn Type=3
Dn Slope=0.005
Boundary for River Rch & Prof#=MILL TRIBUTARY 8,Reach-1,3
Up Type=0
Dn Type=3
Dn Slope=0.005
Boundary for River Rch & Prof#=MILL TRIBUTARY 8,Reach-1,4
Up Type=0
Dn Type=3
Dn Slope=0.005
Boundary for River Rch & Prof#=MILL TRIBUTARY 8,Reach-1,5
Up Type=0
Dn Type=3
Dn Slope=0.005
Boundary for River Rch & Prof#=MILL TRIBUTARY 8,Reach-1,6
Up Type=0
Dn Type=3
Dn Slope=0.005
Boundary for River Rch & Prof#=MILL TRIBUTARY 8,Reach-1,7
Up Type=0
Dn Type=3
Dn Slope=0.005

--- MILL TRIBUTARY 8B.g01 (geometry) ---

Geom Title=Existing Conditions

River Reach=MILL TRIBUTARY 8,Reach-1
Reach XY= 30
      2317475.00     13779225.00      2317554.80     13779144.52
      2317576.48     13779128.56      2317669.02     13779122.65
      2317681.04     13779116.81      2317730.97     13779077.35
      2317819.03     13779072.65      2317880.97     13779027.35
      2317973.40     13779021.14      2318015.35     13778985.85
      2318030.94     13778977.27      2318169.14     13778972.53
      2318181.18     13778966.54      2318221.71     13778933.06
      2318234.93     13778936.42      2318276.64     13778970.58
      2318327.22     13778981.14      2318369.34     13779017.32
      2318390.70     13779024.98      2318408.86     13779024.48
      2318419.21     13779019.79      2318428.55     13778983.68
      2318436.95     13778977.03      2318550.09     13778975.26
      2318573.53     13778971.45      2318595.16     13778955.39
      2318711.43     13778838.23      2318722.66     13778819.03
      2318730.71     13778772.65      2318775.00     13778725.00

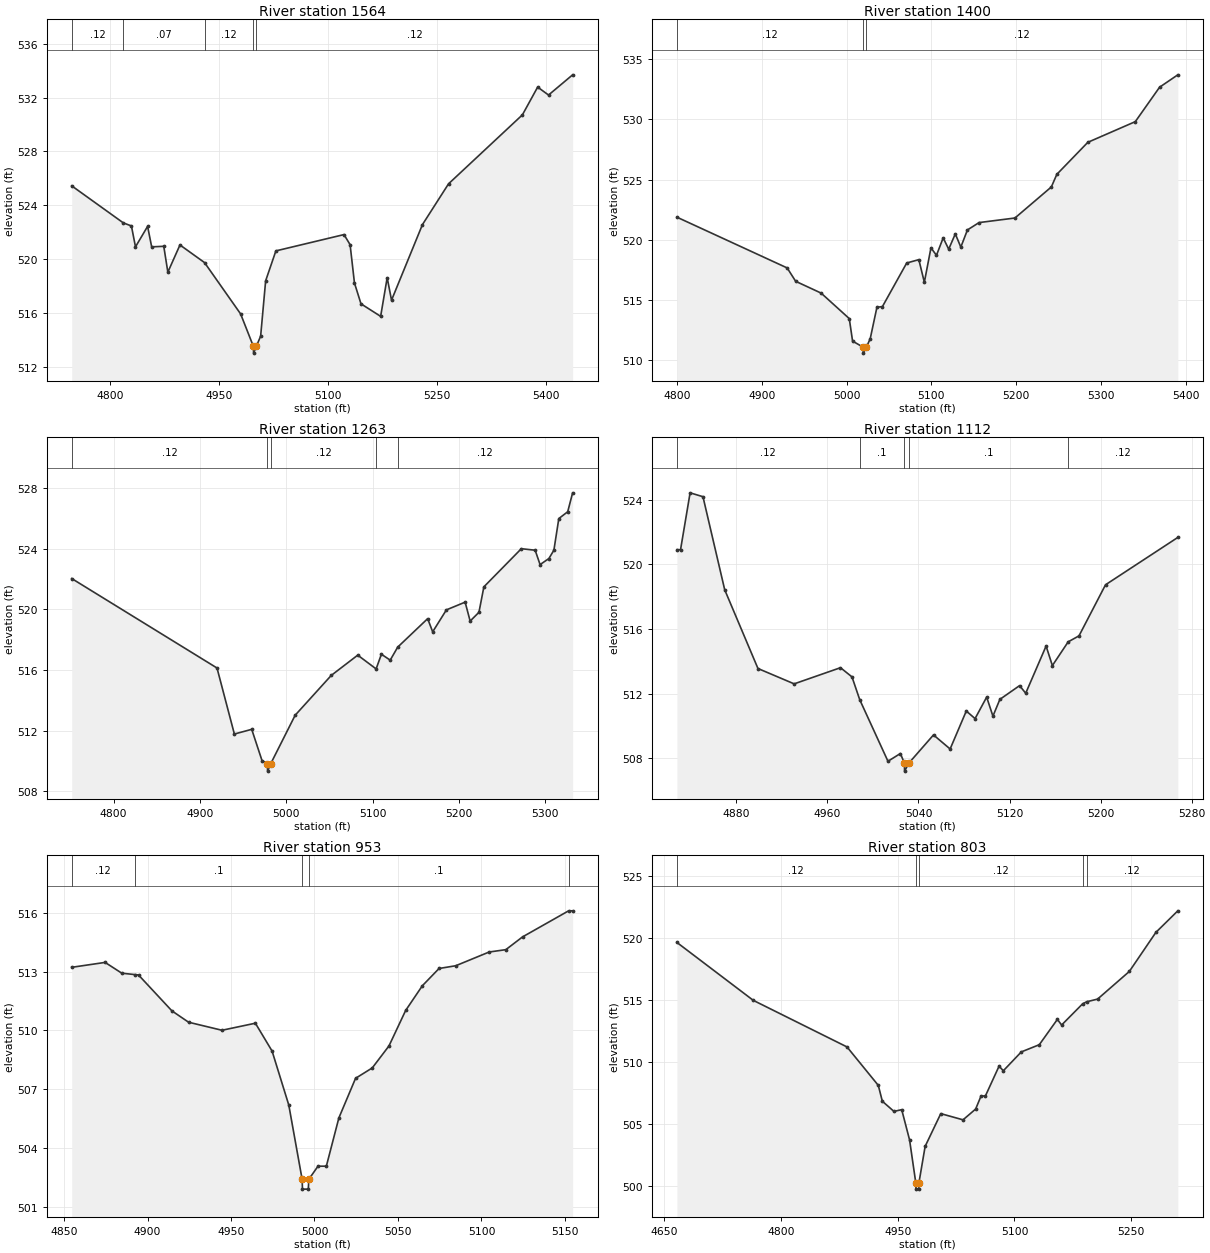
Type RM Length L Ch R = 1,1564,164,164,164
BEGIN DESCRIPTION:
B19586
END DESCRIPTION:
XS GIS Cut Line= 3
      2317607.41     13779432.87      2317492.40     13779205.03
      2317251.51     13778842.60
#Sta/Elev= 30
  4746.6  525.45  4817.7  522.70  4828.9  522.47  4834.5  520.92  4851.2  522.44
  4856.8  520.92  4873.5  520.96  4879.1  519.04  4895.8  521.06  4929.7  519.75
  4979.4  515.94  4997.0  513.53  4997.3  513.03  5001.0  513.53  5007.0  514.29
  5013.9  518.40  5028.0  520.62  5121.9  521.83  5130.3  521.08  5136.3  518.24
  5145.3  516.69  5172.4  515.76  5181.4  518.63  5187.4  516.96  5230.0  522.57
  5266.0  525.60  5367.8  530.72  5388.8  532.78  5403.8  532.19  5437.0  533.69
#Mann=5,-1,0
  4746.6    0.12       0  4817.7    0.07       0  4929.7    0.12       0
  4997.0    0.05       0  5001.0    0.12       0
Bank Sta=4997,5001
Exp/Cntr=0.3,0.1

Type RM Length L Ch R = 1,1400,137,137,137
BEGIN DESCRIPTION:
MILL TRIBUTARY 8B 3.0
END DESCRIPTION:
XS GIS Cut Line= 3
      2317625.00     13779324.96      2317625.00     13779125.00
      2317374.98     13778824.98
#Sta/Elev= 30
  4800.0  521.88  4930.0  517.66  4940.0  516.55  4970.0  515.57  5003.2  513.45
  5007.1  511.58  5019.4  511.08  5019.7  510.58  5023.4  511.08  5027.9  511.78
  5035.8  514.39  5042.3  514.45  5070.9  518.07  5085.2  518.35  5091.7  516.47
  5099.5  519.33  5106.0  518.71  5113.9  520.16  5120.4  519.22  5128.2  520.49
  5134.7  519.39  5142.5  520.82  5156.2  521.43  5198.5  521.81  5241.4  524.39
  5247.9  525.44  5284.4  528.10  5340.4  529.82  5369.0  532.68  5390.5  533.71
#Mann=3,-1,0
  4800.0    0.12       0  5019.4    0.05       0  5023.4    0.12       0
Bank Sta=5019.4,5023.4
Exp/Cntr=0.3,0.1

Type RM Length L Ch R = 1,1263,151,151,151
BEGIN DESCRIPTION:
B19585
END DESCRIPTION:
XS GIS Cut Line= 3
      2317774.52     13779322.18      2317741.97     13779035.76
      2317599.46     13778780.97
#Sta/Elev= 30
  4751.4  522.04  4919.7  516.13  4939.8  511.77  4959.9  512.08  4971.8  510.02
  4978.0  509.82  4978.3  509.32  4982.0  509.82  5010.2  513.01  5052.0  515.64
  5082.7  516.98  5104.0  516.07  5110.1  517.04  5120.3  516.65  5129.0  517.51
  5163.7  519.39  5169.5  518.52  5185.4  519.97  5207.1  520.48  5212.9  519.23
  5223.1  519.81  5228.8  521.49  5272.2  524.01  5288.2  523.91  5293.9  522.96
  5304.1  523.36  5309.9  523.91  5315.6  526.00  5325.9  526.45  5331.6  527.70
#Mann=5,-1,0
  4751.4    0.12       0  4978.0    0.05       0  4982.0    0.12       0
  5104.0     0.1       0  5129.0    0.12       0
Bank Sta=4978,4982
Exp/Cntr=0.3,0.1

Type RM Length L Ch R = 1,1112,159,159,159
BEGIN DESCRIPTION:
B19584
END DESCRIPTION:
XS GIS Cut Line= 3
      2317913.41     13779196.37      2317883.03     13779029.25
      2317774.52     13778781.86
#Sta/Elev= 30
  4827.8  520.91  4831.0  520.91  4839.4  524.43  4850.7  524.19  4869.8  518.43
  4899.0  513.56  4930.8  512.61  4971.5  513.61  4981.6  513.04  4988.4  511.63
  5013.2  507.82  5024.1  508.30  5027.6  507.71  5027.8  507.21  5031.6  507.71
  5053.2  509.45  5067.8  508.58  5082.0  510.93  5089.7  510.46  5099.9  511.79
  5105.4  510.61  5111.5  511.65  5128.8  512.50  5134.2  512.03  5152.1  514.95
  5157.6  513.74  5171.5  515.21  5181.0  515.58  5204.3  518.74  5267.8  521.67
#Mann=5,-1,0
  4827.8    0.12       0  4988.4     0.1       0  5027.6    0.05       0
  5031.6     0.1       0  5171.5    0.12       0
Bank Sta=5027.6,5031.6
Exp/Cntr=0.3,0.1

Type RM Length L Ch R = 1,953,150,150,150
BEGIN DESCRIPTION:
MILL TRIBUTARY 8B 2.0
END DESCRIPTION:
XS GIS Cut Line= 3
      2318025.00     13779124.97      2318025.00     13778975.00
      2318025.00     13778824.97
#Sta/Elev= 30
  4854.6  513.22  4874.6  513.47  4884.6  512.92  4892.3  512.85  4894.6  512.83
  4914.6  511.00  4924.6  510.42  4944.6  510.01  4964.6  510.37  4974.6  508.95
  4984.6  506.20  4992.6  502.41  4992.8  501.91  4996.3  501.91  4996.6  502.41
  5002.1  503.08  5007.1  503.08  5014.6  505.54  5024.6  507.56  5034.6  508.09
  5044.6  509.21  5054.6  511.02  5064.6  512.28  5074.6  513.16  5084.6  513.30
  5104.6  514.00  5114.6  514.12  5124.6  514.77  5152.2  516.10  5154.6  516.10
#Mann=5,-1,0
  4854.6    0.12       0  4892.3     0.1       0  4992.6    0.05       0
  4996.6     0.1       0  5152.2    0.12       0
Bank Sta=4992.6,4996.6
Exp/Cntr=0.3,0.1

Type RM Length L Ch R = 1,803,156,156,156
BEGIN DESCRIPTION:
B19583
END DESCRIPTION:
XS GIS Cut Line= 3
      2318145.62     13779302.68      2318176.00     13778975.00
      2318046.62     13778688.22
#Sta/Elev= 30
  4666.2  519.61  4764.3  514.94  4884.8  511.18  4925.0  508.08  4930.2  506.80
  4945.1  505.98  4955.1  506.12  4965.2  503.68  4973.2  500.21  4973.5  499.71
  4977.0  499.71  4977.2  500.21  4985.2  503.16  5005.3  505.80  5033.9  505.30
  5050.1  506.17  5057.1  507.23  5062.6  507.22  5080.2  509.63  5085.7  509.26
  5108.8  510.78  5131.9  511.36  5155.1  513.40  5160.6  512.95  5187.6  514.66
  5192.6  514.82  5206.8  515.04  5247.6  517.27  5281.7  520.42  5309.9  522.16
#Mann=5,-1,0
  4666.2    0.12       0  4973.2    0.05       0  4977.2    0.12       0
  5187.6     0.1       0  5192.6    0.12       0
Bank Sta=4973.2,4977.2
Exp/Cntr=0.3,0.1

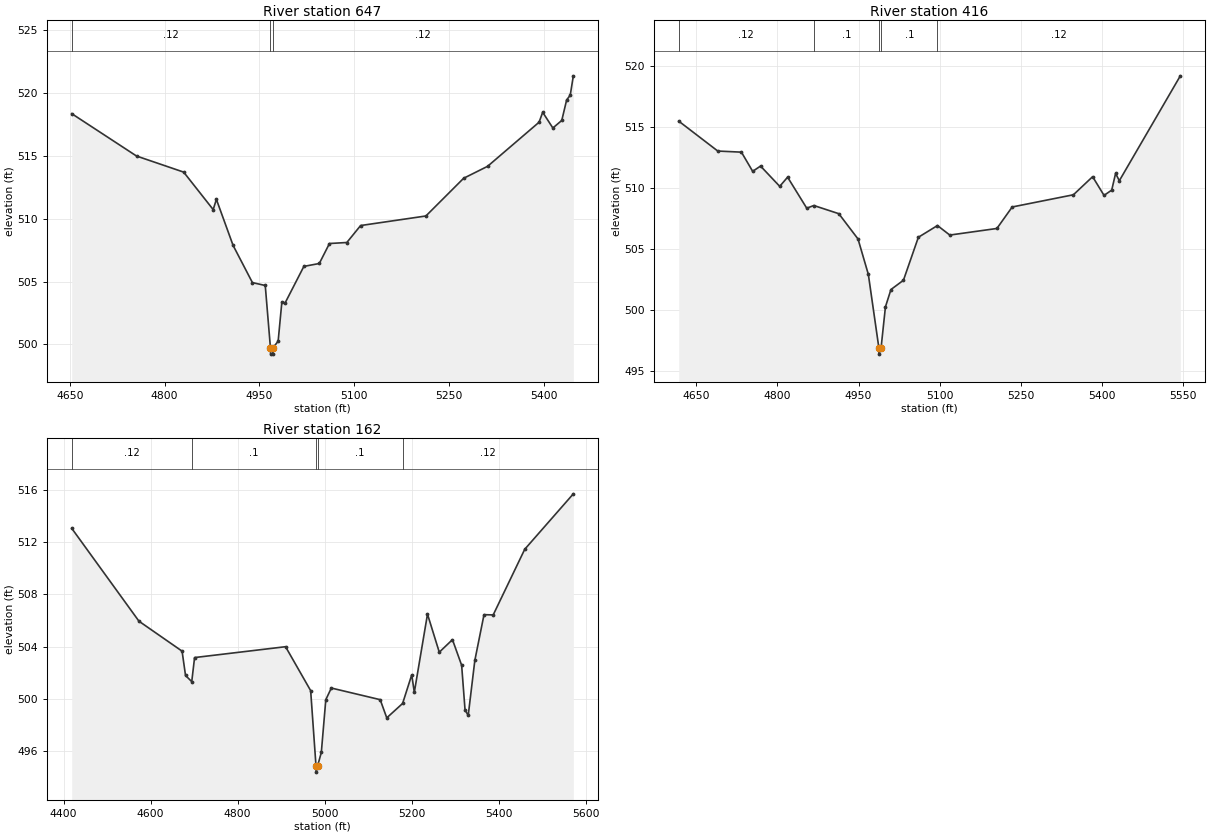
Type RM Length L Ch R = 1,647,231,231,231
BEGIN DESCRIPTION:
B19582
END DESCRIPTION:
XS GIS Cut Line= 3
      2318236.77     13779315.67      2318310.55     13778933.77
      2318115.83     13778578.94
#Sta/Elev= 30
  4653.2  518.36  4755.7  514.99  4830.3  513.71  4877.0  510.73  4882.1  511.54
  4908.5  507.88  4939.1  504.92  4959.4  504.69  4967.6  499.73  4967.9  499.23
  4971.4  499.23  4971.6  499.73  4979.8  500.26  4985.7  503.39  4990.8  503.30
  5020.5  506.21  5044.9  506.44  5061.0  508.03  5088.5  508.11  5110.3  509.46
  5213.6  510.22  5273.3  513.22  5311.2  514.17  5392.7  517.68  5398.4  518.47
  5414.5  517.22  5428.6  517.82  5436.3  519.45  5442.0  519.83  5446.9  521.37
#Mann=3,-1,0
  4653.2    0.12       0  4967.6    0.05       0  4971.6    0.12       0
Bank Sta=4967.6,4971.6
Exp/Cntr=0.3,0.1

Type RM Length L Ch R = 1,416,254,254,254
BEGIN DESCRIPTION:
B19581
END DESCRIPTION:
XS GIS Cut Line= 4
      2318338.75     13779300.53      2318503.69     13779081.34
      2318464.63     13778855.64      2318159.35     13778561.19
#Sta/Elev= 30
  4617.5  515.45  4689.7  513.00  4733.4  512.91  4754.2  511.34  4768.8  511.77
  4804.2  510.11  4818.8  510.86  4854.2  508.32  4867.3  508.54  4913.5  507.87
  4949.0  505.80  4968.1  502.90  4987.6  496.87  4987.8  496.37  4991.6  496.87
  4999.7  500.24  5009.9  501.66  5033.0  502.42  5060.6  505.94  5095.9  506.90
  5118.7  506.12  5205.8  506.66  5234.1  508.42  5347.3  509.42  5382.8  510.90
  5403.9  509.37  5418.1  509.80  5425.3  511.17  5432.2  510.57  5545.0  519.16
#Mann=5,-1,0
  4617.5    0.12       0  4867.3     0.1       0  4987.6    0.05       0
  4991.6     0.1       0  5095.9    0.12       0
Bank Sta=4987.6,4991.6
Exp/Cntr=0.3,0.1

Type RM Length L Ch R = 1,162,0,0,0
BEGIN DESCRIPTION:
B19580
END DESCRIPTION:
XS GIS Cut Line= 4
      2318401.70     13779278.82      2318729.38     13779011.89
      2318672.96     13778773.18      2318266.23     13778509.24
#Sta/Elev= 30
  4418.8  513.05  4573.3  505.95  4672.4  503.66  4680.3  501.80  4694.6  501.33
  4701.1  503.17  4910.2  504.00  4967.9  500.64  4980.1  494.91  4980.4  494.41
  4984.1  494.91  4992.4  495.92  5002.7  499.95  5015.4  500.84  5127.7  499.95
  5142.8  498.56  5179.2  499.66  5200.2  501.85  5206.1  500.51  5236.4  506.49
  5263.5  503.58  5293.8  504.54  5314.9  502.58  5322.7  499.17  5330.0  498.74
  5345.2  502.95  5366.3  506.45  5387.4  506.43  5459.9  511.45  5571.6  515.69
#Mann=5,-1,0
  4418.8    0.12       0  4694.6     0.1       0  4980.1    0.05       0
  4984.1     0.1       0  5179.2    0.12       0
Bank Sta=4980.1,4984.1
Exp/Cntr=0.3,0.1

Chan Stop Cuts=-1