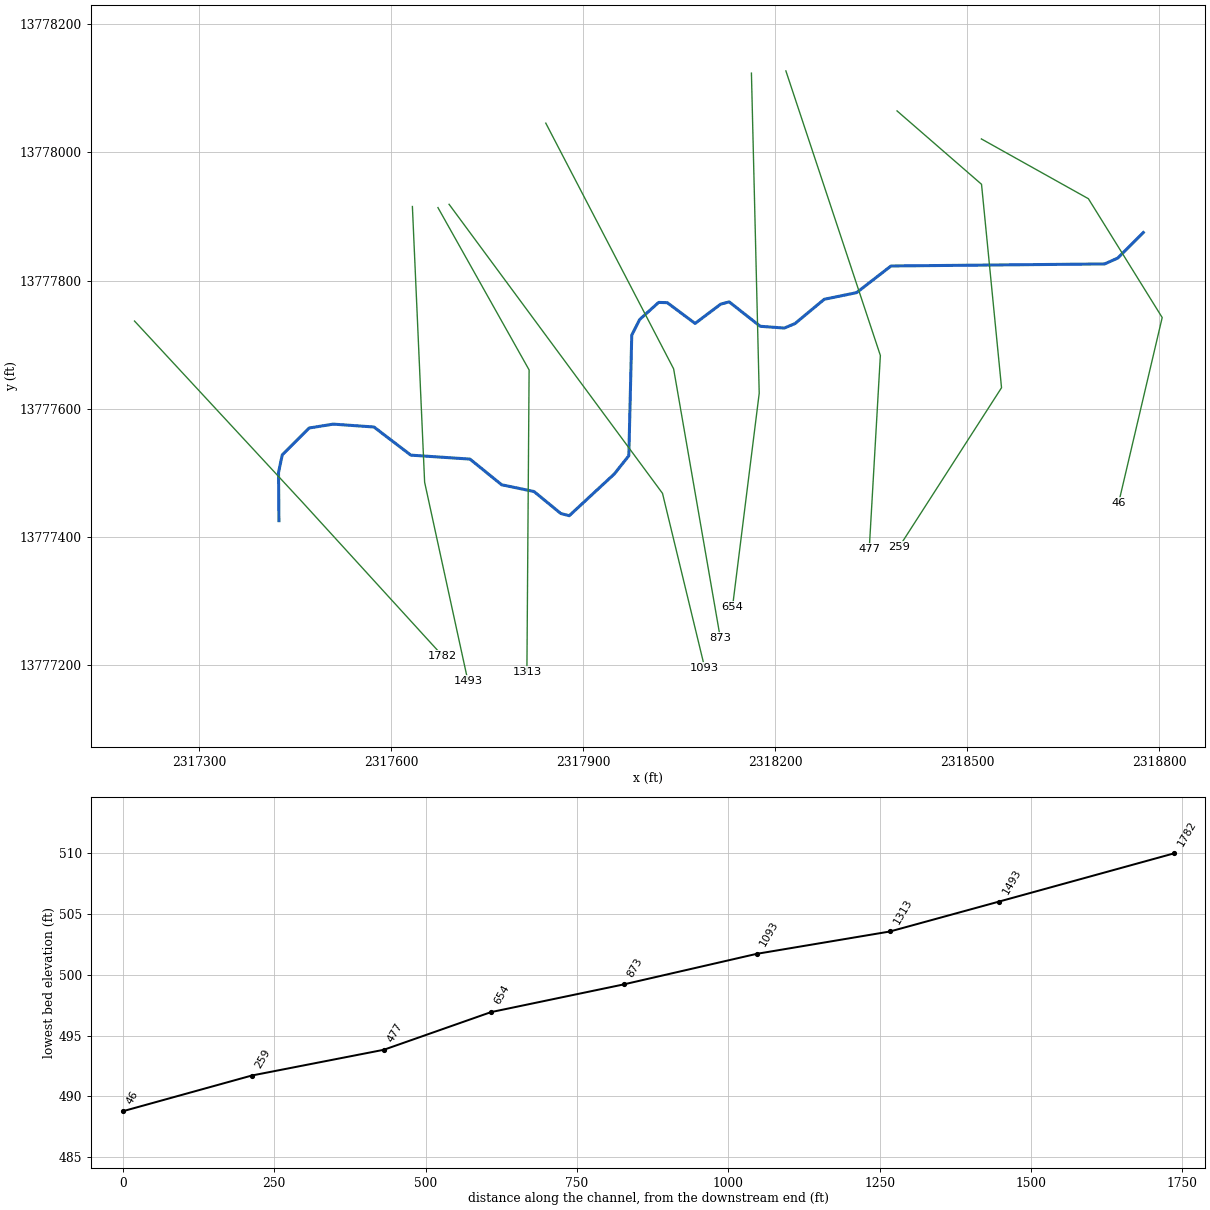
--- MILL TRIBUTARY 9.prj (project) ---

Proj Title=MILL TRIBUTARY 9 Base Level Engineering
Current Plan=p01
Default Exp/Contr=0.3,0.1
English Units
Geom File=g01
Flow File=f01
Plan File=p01
Y Axis Title=Elevation
X Axis Title(PF)=Main Channel Distance
X Axis Title(XS)=Station
BEGIN DESCRIPTION:
MILL TRIBUTARY 9
END DESCRIPTION:
DSS Export Rating Curves= 0
DSS Export Rating Curve Sorted= 0
DSS Export Volume Flow Curves= 0
DXF OffsetX= 0
DXF OffsetY= 0
DXF ScaleX= 1
DXF ScaleY= 10

--- MILL TRIBUTARY 9.p01 (plan) ---

Plan Title=Multiple Run
Short Identifier=Multiple
Geom File=g01
Flow File=f01
Subcritical Flow
K Sum by GR= 0
Std Step Tol= 0.01
Critical Tol= 0.01
Num of Std Step Trials= 20
Max Error Tol= 0.3
Flow Tol Ratio= 0.001
Split Flow NTrial= 30
Split Flow Tol= 0.02
Split Flow Ratio= 0.02
Log Output Level= 0
Friction Slope Method= 1
Unsteady Friction Slope Method= 2
Unsteady Bridges Friction Slope Method= 1
Parabolic Critical Depth
Global Vel Dist=  1 , 1 , 1
Global Log Level= 0
CheckData=True
Encroach Param= -1, 0, 0, 0
BEGIN DESCRIPTION:
Multiple Run
END DESCRIPTION:

--- MILL TRIBUTARY 9.f01 (steady flow) ---

Flow Title=Multiple
Number of Profiles=7
Profile Names=10-year,25-year,50-year,1pct_min,100-year,1pct_plu,500-year
River Rch & RM= MILL TRIBUTARY 9,Reach-1,1782
     431     687     916     593    1183    2359    1951
Boundary for River Rch & Prof#=MILL TRIBUTARY 9,Reach-1,1
Up Type=0
Dn Type=3
Dn Slope=0.005
Boundary for River Rch & Prof#=MILL TRIBUTARY 9,Reach-1,2
Up Type=0
Dn Type=3
Dn Slope=0.005
Boundary for River Rch & Prof#=MILL TRIBUTARY 9,Reach-1,3
Up Type=0
Dn Type=3
Dn Slope=0.005
Boundary for River Rch & Prof#=MILL TRIBUTARY 9,Reach-1,4
Up Type=0
Dn Type=3
Dn Slope=0.005
Boundary for River Rch & Prof#=MILL TRIBUTARY 9,Reach-1,5
Up Type=0
Dn Type=3
Dn Slope=0.005
Boundary for River Rch & Prof#=MILL TRIBUTARY 9,Reach-1,6
Up Type=0
Dn Type=3
Dn Slope=0.005
Boundary for River Rch & Prof#=MILL TRIBUTARY 9,Reach-1,7
Up Type=0
Dn Type=3
Dn Slope=0.005

--- MILL TRIBUTARY 9.g01 (geometry) ---

Geom Title=Existing Conditions

River Reach=MILL TRIBUTARY 9,Reach-1
Reach XY= 30
      2317425.00     13777425.00      2317424.35     13777500.37
      2317430.21     13777527.83      2317472.29     13777569.74
      2317509.85     13777575.80      2317573.40     13777571.30
      2317630.97     13777527.36      2317723.42     13777521.17
      2317772.83     13777481.09      2317823.37     13777470.57
      2317865.14     13777436.27      2317878.42     13777432.76
      2317948.84     13777497.99      2317971.46     13777526.44
      2317976.05     13777714.89      2317988.37     13777739.11
      2318018.00     13777765.85      2318031.49     13777765.49
      2318074.98     13777733.04      2318114.95     13777763.18
      2318128.23     13777766.69      2318176.63     13777728.59
      2318214.30     13777725.80      2318230.93     13777732.79
      2318276.72     13777770.78      2318327.18     13777781.11
      2318380.93     13777822.76      2318714.60     13777825.96
      2318734.98     13777835.05      2318775.00     13777875.00

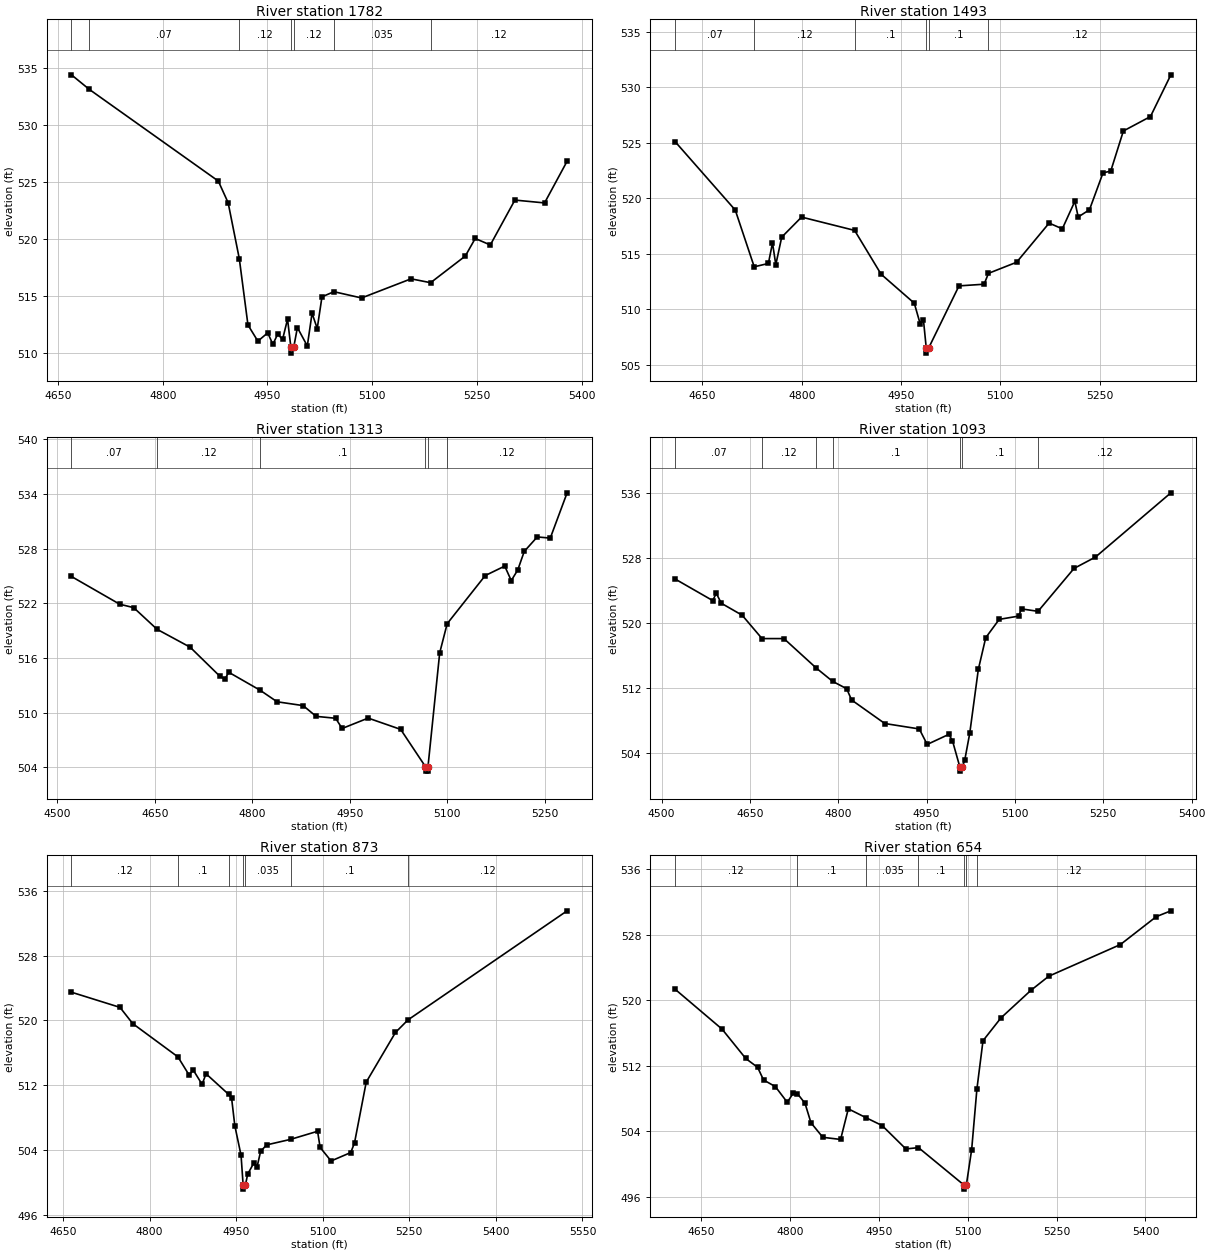
Type RM Length L Ch R = 1,1782,289,289,289
BEGIN DESCRIPTION:
B19595
END DESCRIPTION:
XS GIS Cut Line= 3
      2317199.44     13777736.77      2317463.30     13777452.08
      2317680.16     13777214.41
#Sta/Elev= 30
  4669.3  534.42  4694.7  533.15  4879.6  525.10  4893.7  523.20  4909.7  518.29
  4922.1  512.47  4936.3  511.05  4950.4  511.78  4957.8  510.77  4964.6  511.66
  4971.7  511.21  4978.8  512.98  4983.6  510.50  4983.8  510.00  4987.6  510.50
  4992.9  512.24  5007.1  510.63  5013.9  513.50  5021.3  512.16  5028.1  514.94
  5045.2  515.39  5084.8  514.84  5155.7  516.52  5183.7  516.18  5233.4  518.52
  5247.6  520.06  5269.2  519.49  5304.4  523.43  5346.9  523.18  5379.2  526.84
#Mann=7,-1,0
  4669.3    0.12       0  4694.7    0.07       0  4909.7    0.12       0
  4983.6    0.05       0  4987.6    0.12       0  5045.2   0.035       0
  5183.7    0.12       0
Bank Sta=4983.6,4987.6
Exp/Cntr=0.3,0.1

Type RM Length L Ch R = 1,1493,180,180,180
BEGIN DESCRIPTION:
B19594
END DESCRIPTION:
XS GIS Cut Line= 3
      2317633.44     13777915.61      2317652.54     13777485.07
      2317720.11     13777174.91
#Sta/Elev= 30
  4609.0  525.08  4699.7  518.92  4728.3  513.81  4749.7  514.11  4755.9  515.96
  4760.9  514.00  4769.8  516.48  4799.8  518.29  4879.9  517.09  4919.9  513.14
  4970.0  510.53  4978.8  508.69  4983.8  509.03  4988.0  506.53  4988.2  506.03
  4992.0  506.53  5037.5  512.09  5075.4  512.24  5082.0  513.22  5124.5  514.22
  5173.6  517.75  5193.5  517.23  5212.4  519.71  5217.5  518.30  5234.5  518.95
  5255.0  522.28  5266.6  522.43  5285.7  526.05  5326.6  527.35  5357.4  531.11
#Mann=6,-1,0
  4609.0    0.07       0  4728.3    0.12       0  4879.9     0.1       0
  4988.0    0.05       0  4992.0     0.1       0  5082.0    0.12       0
Bank Sta=4988,4992
Exp/Cntr=0.3,0.1

Type RM Length L Ch R = 1,1313,220,220,220
BEGIN DESCRIPTION:
B19593
END DESCRIPTION:
XS GIS Cut Line= 3
      2317673.36     13777913.91      2317815.73     13777660.42
      2317812.27     13777189.07
#Sta/Elev= 30
  4522.0  524.93  4596.1  521.89  4617.7  521.51  4653.5  519.14  4704.5  517.17
  4750.1  513.99  4758.0  513.66  4763.8  514.42  4812.0  512.45  4838.2  511.18
  4878.2  510.76  4898.2  509.58  4928.2  509.37  4938.2  508.25  4978.2  509.39
  5028.2  508.15  5066.2  504.07  5066.4  503.57  5069.9  503.57  5070.2  504.07
  5088.2  516.55  5099.7  519.75  5158.2  525.03  5188.2  526.07  5198.2  524.48
  5208.2  525.64  5218.2  527.68  5238.2  529.27  5258.2  529.14  5284.1  534.11
#Mann=6,-1,0
  4522.0    0.07       0  4653.5    0.12       0  4812.0     0.1       0
  5066.2    0.05       0  5070.2     0.1       0  5099.7    0.12       0
Bank Sta=5066.2,5070.2
Exp/Cntr=0.3,0.1

Type RM Length L Ch R = 1,1093,220,220,220
BEGIN DESCRIPTION:
B19592
END DESCRIPTION:
XS GIS Cut Line= 3
      2317690.73     13777919.10      2318024.06     13777467.71
      2318090.02     13777195.21
#Sta/Elev= 30
  4523.2  525.41  4586.8  522.76  4593.0  523.65  4601.4  522.43  4636.9  520.95
  4670.6  518.07  4707.8  518.07  4762.8  514.43  4790.4  512.80  4814.3  511.89
  4822.7  510.50  4879.0  507.60  4937.6  506.93  4951.0  505.02  4987.7  506.26
  4993.9  505.48  5006.5  502.23  5006.8  501.73  5010.5  502.23  5014.7  503.06
  5023.2  506.37  5037.8  514.26  5050.4  518.18  5073.3  520.44  5106.1  520.84
  5111.2  521.73  5139.2  521.43  5200.3  526.72  5236.7  528.12  5364.7  536.04
#Mann=7,-1,0
  4523.2    0.07       0  4670.6    0.12       0  4762.8   0.035       0
  4790.4     0.1       0  5006.5    0.05       0  5010.5     0.1       0
  5139.2    0.12       0
Bank Sta=5006.5,5010.5
Exp/Cntr=0.3,0.1

Type RM Length L Ch R = 1,873,219,219,219
BEGIN DESCRIPTION:
B19591
END DESCRIPTION:
XS GIS Cut Line= 3
      2317841.79     13778045.80      2318041.43     13777662.15
      2318114.34     13777242.02
#Sta/Elev= 30
  4664.5  523.48  4748.6  521.61  4770.7  519.61  4849.0  515.51  4868.3  513.28
  4875.6  513.88  4890.9  512.12  4897.7  513.43  4936.7  510.90  4941.9  510.49
  4947.6  507.02  4958.4  503.38  4962.0  499.71  4962.3  499.21  4966.0  499.71
  4969.8  501.04  4980.5  502.43  4986.1  501.95  4992.3  503.86  5002.6  504.66
  5044.1  505.34  5091.0  506.34  5095.4  504.35  5114.4  502.68  5148.5  503.72
  5155.0  504.91  5175.3  512.40  5226.0  518.52  5247.7  520.07  5523.4  533.51
#Mann=7,-1,0
  4664.5    0.12       0  4849.0     0.1       0  4936.7   0.035       0
  4962.0   0.035       0  4966.0   0.035       0  5044.1     0.1       0
  5247.7    0.12       0
Bank Sta=4962,4966
Exp/Cntr=0.3,0.1

Type RM Length L Ch R = 1,654,177,177,177
BEGIN DESCRIPTION:
B19590
END DESCRIPTION:
XS GIS Cut Line= 3
      2318162.95     13778123.94      2318175.11     13777623.96
      2318133.43     13777290.58
#Sta/Elev= 30
  4606.7  521.34  4685.7  516.48  4725.7  512.89  4745.7  511.81  4755.7  510.27
  4775.7  509.45  4795.7  507.54  4805.7  508.64  4812.7  508.61  4825.7  507.41
  4835.7  505.04  4855.7  503.26  4885.7  503.00  4898.7  506.74  4929.3  505.63
  4955.7  504.70  4995.8  501.84  5017.1  502.00  5093.8  497.43  5094.0  496.93
  5097.8  497.43  5106.8  501.77  5115.6  509.14  5125.9  515.06  5156.2  517.85
  5206.6  521.21  5236.8  522.94  5357.7  526.81  5418.2  530.22  5442.8  530.93
#Mann=7,-1,0
  4606.7    0.12       0  4812.7     0.1       0  4929.3   0.035       0
  5017.1     0.1       0  5093.8   0.035       0  5097.8     0.1       0
  5115.6    0.12       0
Bank Sta=5093.8,5097.8
Exp/Cntr=0.3,0.1

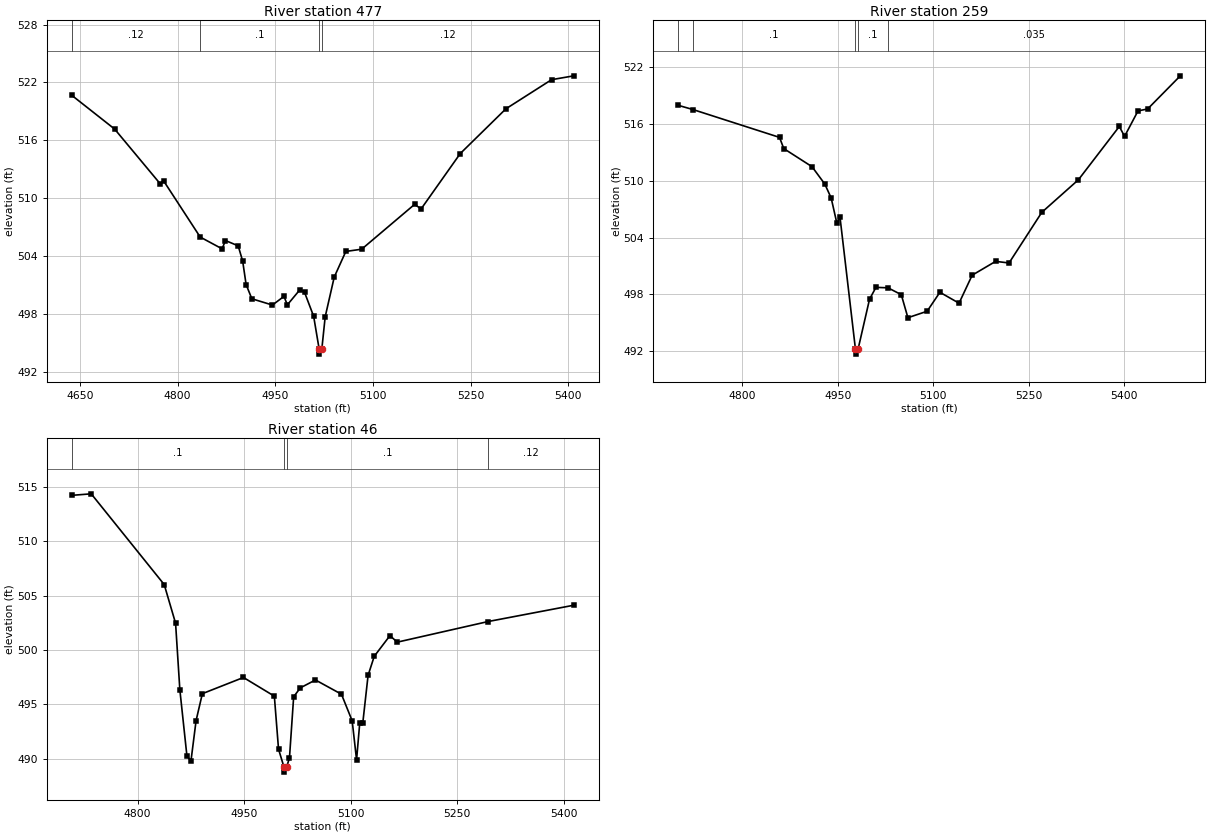
Type RM Length L Ch R = 1,477,218,218,218
BEGIN DESCRIPTION:
B19589
END DESCRIPTION:
XS GIS Cut Line= 3
      2318216.77     13778127.44      2318364.34     13777682.99
      2318346.98     13777380.90
#Sta/Elev= 30
  4637.6  520.67  4703.4  517.17  4773.3  511.50  4778.6  511.80  4834.8  505.97
  4868.4  504.75  4873.6  505.61  4893.1  505.06  4900.0  503.48  4905.3  501.04
  4914.1  499.57  4945.7  498.92  4963.4  499.82  4968.6  498.94  4987.9  500.51
  4995.0  500.24  5009.0  497.75  5017.5  494.33  5017.7  493.83  5021.5  494.33
  5026.7  497.70  5040.6  501.82  5058.4  504.48  5082.7  504.71  5164.0  509.36
  5174.0  508.89  5234.1  514.63  5304.2  519.27  5374.3  522.29  5408.5  522.69
#Mann=4,-1,0
  4637.6    0.12       0  4834.8     0.1       0  5017.5   0.035       0
  5021.5    0.12       0
Bank Sta=5017.5,5021.5
Exp/Cntr=0.3,0.1

Type RM Length L Ch R = 1,259,213,213,213
BEGIN DESCRIPTION:
B19588
END DESCRIPTION:
XS GIS Cut Line= 4
      2318390.37     13778064.94      2318522.33     13777950.35
      2318553.58     13777632.64      2318393.87     13777384.39
#Sta/Elev= 30
  4699.3  517.94  4722.2  517.50  4858.5  514.56  4865.2  513.38  4909.6  511.47
  4929.7  509.64  4939.7  508.17  4948.6  505.52  4953.6  506.13  4977.9  492.21
  4978.2  491.71  4981.9  492.21  5000.0  497.50  5010.1  498.75  5029.0  498.70
  5049.9  497.98  5060.3  495.55  5090.5  496.23  5110.6  498.23  5140.7  497.08
  5161.3  500.03  5198.2  501.49  5219.3  501.32  5270.8  506.66  5328.3  510.09
  5392.6  515.71  5400.9  514.67  5422.0  517.35  5437.2  517.56  5488.5  521.05
#Mann=5,-1,0
  4699.3    0.12       0  4722.2     0.1       0  4977.9    0.05       0
  4981.9     0.1       0  5029.0   0.035       0
Bank Sta=4977.9,4981.9
Exp/Cntr=0.3,0.1

Type RM Length L Ch R = 1,46,0,0,0
BEGIN DESCRIPTION:
B19587
END DESCRIPTION:
XS GIS Cut Line= 4
      2318522.10     13778021.17      2318689.22     13777927.82
      2318804.50     13777742.22      2318736.50     13777452.91
#Sta/Elev= 30
  4707.2  514.24  4734.6  514.38  4837.4  506.03  4853.4  502.47  4859.4  496.36
  4869.4  490.24  4875.1  489.81  4882.3  493.52  4891.1  495.99  4949.0  497.48
  4992.5  495.76  4998.4  490.88  5005.9  489.27  5006.1  488.77  5009.9  489.27
  5013.8  490.08  5019.7  495.71  5029.2  496.53  5050.4  497.25  5087.0  495.94
  5102.1  493.49  5108.3  489.90  5112.8  493.32  5117.1  493.32  5124.5  497.67
  5133.2  499.43  5155.3  501.33  5165.6  500.73  5293.7  502.63  5414.3  504.13
#Mann=4,-1,0
  4707.2     0.1       0  5005.9    0.05       0  5009.9     0.1       0
  5293.7    0.12       0
Bank Sta=5005.9,5009.9
Exp/Cntr=0.3,0.1

Chan Stop Cuts=-1