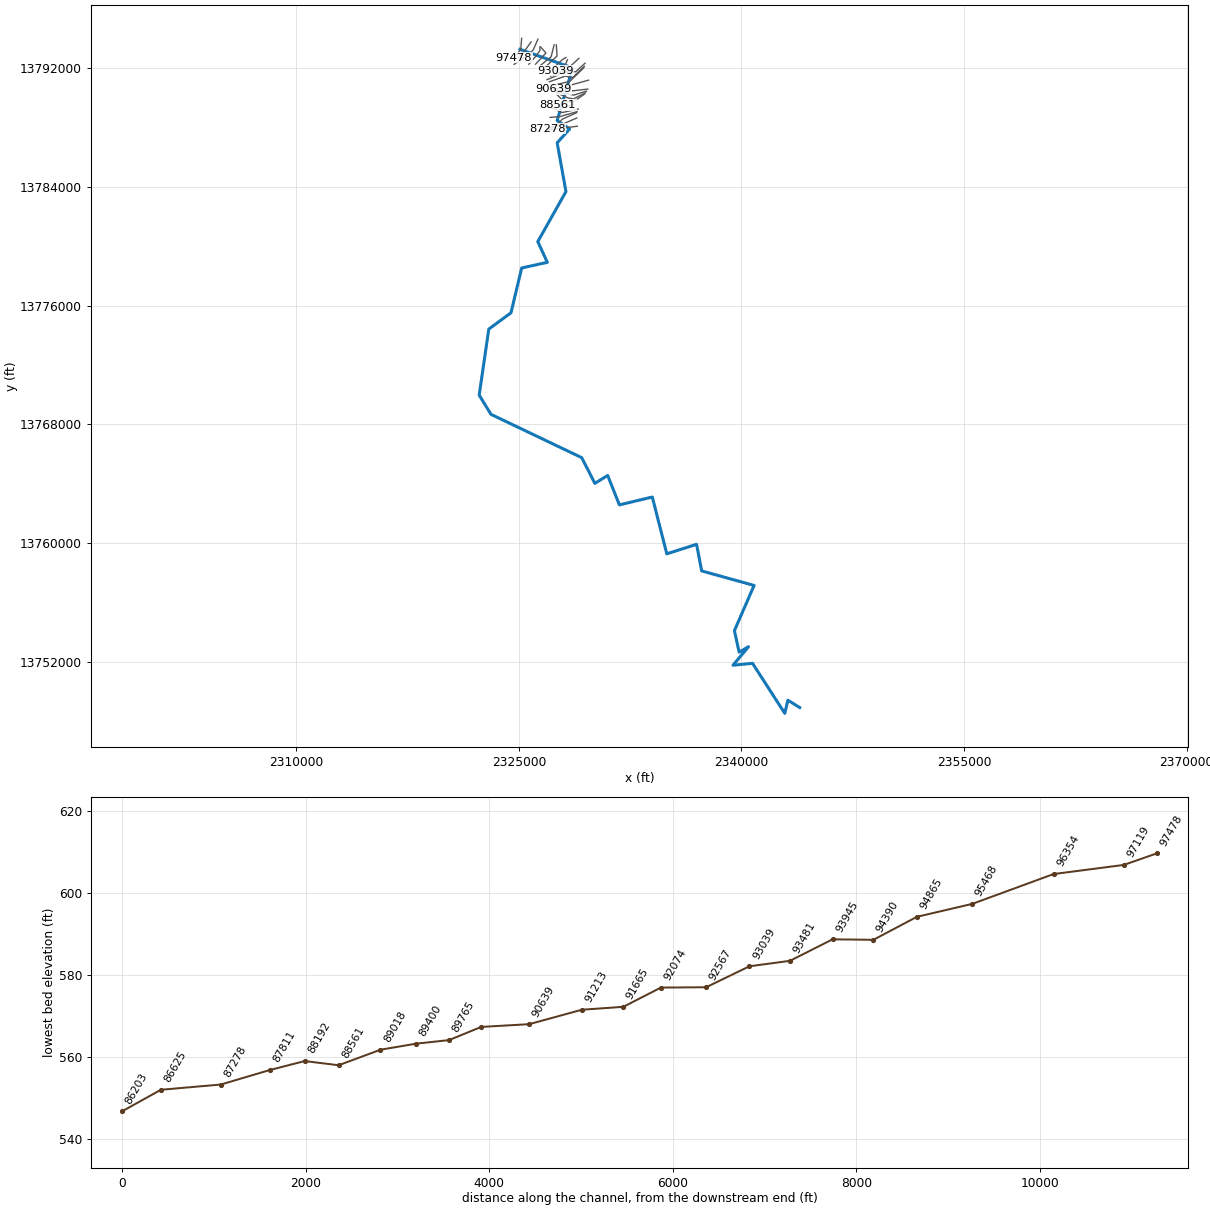
--- Mill Creek.prj (project) ---

Proj Title=Mill Creek Base Level Engineering
Current Plan=p01
Default Exp/Contr=0.3,0.1
English Units
Geom File=g01
Flow File=f01
Plan File=p01
Y Axis Title=Elevation
X Axis Title(PF)=Main Channel Distance
X Axis Title(XS)=Station
BEGIN DESCRIPTION:
Mill Creek
END DESCRIPTION:
DSS Export Rating Curves= 0
DSS Export Rating Curve Sorted= 0
DSS Export Volume Flow Curves= 0
DXF OffsetX= 0
DXF OffsetY= 0
DXF ScaleX= 1
DXF ScaleY= 10

--- Mill Creek.p01 (plan) ---

Plan Title=Multiple Run
Program Version=4.10
Short Identifier=Multiple
Geom File=g01
Flow File=f01
Subcritical Flow
K Sum by GR= 0
Std Step Tol= 0.01
Critical Tol= 0.01
Num of Std Step Trials= 20
Max Error Tol= 0.3
Flow Tol Ratio= 0.001
Split Flow NTrial= 30
Split Flow Tol= 0.02
Split Flow Ratio= 0.02
Log Output Level= 0
Friction Slope Method= 1
Unsteady Friction Slope Method= 2
Unsteady Bridges Friction Slope Method= 1
Parabolic Critical Depth
Global Vel Dist= 1 , 1 , 1
Global Log Level= 0
CheckData=True
Encroach Param=-1 ,0,0, 0
BEGIN DESCRIPTION:
Multiple Run
END DESCRIPTION:
Computation Interval=1HOUR
Output Interval=1HOUR
Run HTab= 0
Run UNet= 0
Run PostProcess= 0
Run WQNet= 0
UNET Theta= 1
UNET Theta Warmup= 1
UNET ZTol= 0.02
UNET ZSATol= 0.05
UNET MxIter= 20
UNET MaxInSteps= 0
UNET DtIC= 0
UNET DtMin= 0
UNET MaxCRTS= 20
UNET WFStab= 2
UNET SFStab= 1
UNET WFX= 1
UNET SFX= 1
UNET DSS MLevel= 4
UNET DZMax Abort= 100
UNET Convert EG Bridges= 0
UNET Use Existing IB Tables=-1
UNET Froude Reduction=False
UNET Froude Limit= 1
UNET Froude Power= 10
UNET Time Slicing=0,0, 5
UNET Junction Losses=0
Instantaneous Interval=1HOUR
Write IC File= 0
Write IC File at Sim End=0
Echo Input=False
Echo Parameters=False
Echo Output=False
Write Detailed= 0
WQ AD Non Conservative
WQ ULTIMATE=-1
WQ Max Comp Step=1HOUR
WQ Output Interval=15MIN
WQ Output Selected Increments= 0
WQ Output face flow=0
WQ Output face velocity=0
WQ Output face area=0
WQ Output face dispersion=0
WQ Output cell volume=0
WQ Output cell surface area=0
WQ Output cell continuity=0
WQ Output cumulative cell continuity=0
WQ Output face conc=0
WQ Output face dconc_dx=0
WQ Output face courant=0
WQ Output face peclet=0
WQ Output face adv mass=0
WQ Output face disp mass=0
WQ Output cell mass=0
WQ Output cell source sink temp=0
WQ Output cell source sink nsm=0
WQ Output MaxMinRange=-1
WQ Daily Max Min Mean=-1
WQ Daily Range=0
WQ Daily Time=0
WQ Create Restart=0
WQ Fixed Restart=0
WQ System Summary=0
WQ Use Fixed Temperature=0
Sorting and Armoring Iterations= 10
XS Update Threshold= 0.02
Hydraulics Update Threshold= 0.02
Energy Slope Method= 1
Volume Change Method= 0
XS Weighting Method= 0
Number of US Weighted Cross Sections= 1
Number of DS Weighted Cross Sections= 1
Upstream XS Weight=0.25
Main XS Weight=0.5
Downstream XS Weight=0.25
Number of DS XS's Weighted with US Boundary= 1
Upstream Boundary Weight= 1
Weight of XSs Associated with US Boundary= 0
Number of US XS's Weighted with DS Boundary= 1
Downstream Boundary Weight= 0.5
Weight of XSs Associated with DS Boundary= 0.5
Sediment Output Level= 4
Mass or Volume Output= 0
Output Increment Type= 1
Profile and TS Output Increment= 10
XS Output Flag= 0
XS Output Increment= 10
Disregard all LS=0
Disregard all Conn=0
Disregard all Breaches=0
Disregard all Pumps=0

--- Mill Creek.f01 (steady flow) ---

Flow Title=Multiple
Number of Profiles=7
Profile Names=10-year,25-year,50-year,1pct_min,100-year,1pct_plu,500-year
River Rch & RM= Mill Creek,Reach-1,97478
     896    1498    2061    1375    2743    5473    4813
River Rch & RM= Mill Creek,Reach-1,96354
    1306    2224    3098    2088    4166    8313    7471
River Rch & RM= Mill Creek,Reach-1,93039
    1425    2430    3389    2285    4559    9097    8183
River Rch & RM= Mill Creek,Reach-1,88561
    1482    2530    3530    2381    4751    9480    8537
River Rch & RM= Mill Creek,Reach-1,87278
    1525    2596    3614    2431    4850    9678    8666
River Rch & RM= Mill Creek,Reach-1,83718
    1614    2735    3796    2543    5073   10123    8992
River Rch & RM= Mill Creek,Reach-1,70963
    2770    4791    6740    4568    9115   18187   16542
River Rch & RM= Mill Creek,Reach-1,61991
    3880    6790    9630    6575   13119   26177   24156
River Rch & RM= Mill Creek,Reach-1,58673
    4176    7293   10328    7038   14042   28018   25751
River Rch & RM= Mill Creek,Reach-1,50416
    4455    7786   11030    7517   14998   29926   27512
River Rch & RM= Mill Creek,Reach-1,47688
    4569    7990   11325    7721   15406   30739   28281
River Rch & RM= Mill Creek,Reach-1,47116
    4745    8293   11749    8005   15972   31869   29281
River Rch & RM= Mill Creek,Reach-1,41154
    4791    8364   11839    8059   16081   32085   29426
River Rch & RM= Mill Creek,Reach-1,36942
    5542    9698   13749    9371   18697   37305   34288
River Rch & RM= Mill Creek,Reach-1,30874
    5625    9839   13947    9503   18961   37833   34756
River Rch & RM= Mill Creek,Reach-1,25265
    5548    9688   13714    9332   18620   37151   34036
River Rch & RM= Mill Creek,Reach-1,22051
    6098   10640   15056   10237   20425   40753   37272
River Rch & RM= Mill Creek,Reach-1,15263
    6169   10740   15176   10302   20555   41012   37387
River Rch & RM= Mill Creek,Reach-1,2616
    6109   10623   14997   10171   20294   40491   36845
Boundary for River Rch & Prof#=Mill Creek,Reach-1,1
Up Type=0
Dn Type=3
Dn Slope=0.0009
Boundary for River Rch & Prof#=Mill Creek,Reach-1,2
Up Type=0
Dn Type=3
Dn Slope=0.0009
Boundary for River Rch & Prof#=Mill Creek,Reach-1,3
Up Type=0
Dn Type=3
Dn Slope=0.0009
Boundary for River Rch & Prof#=Mill Creek,Reach-1,4
Up Type=0
Dn Type=3
Dn Slope=0.0009
Boundary for River Rch & Prof#=Mill Creek,Reach-1,5
Up Type=0
Dn Type=3
Dn Slope=0.0009
Boundary for River Rch & Prof#=Mill Creek,Reach-1,6
Up Type=0
Dn Type=3
Dn Slope=0.0009
Boundary for River Rch & Prof#=Mill Creek,Reach-1,7
Up Type=0
Dn Type=3
Dn Slope=0.0009

--- Mill Creek.g01 (geometry) ---

Geom Title=Existing Conditions
Program Version=4.10

River Reach=Mill Creek      ,Reach-1
Reach XY= 30
        2325075.       13793275.      2328622.95     13792019.14
      2327581.87     13788474.88      2328424.51     13787909.78
      2327582.08     13786974.99      2328174.64     13783690.16
      2326276.62     13780318.99       2326919.3     13778922.46
      2325191.48     13778542.06      2324469.61     13775522.56
        2322975.       13774425.      2322328.53     13769976.45
      2323122.57     13768680.52      2329234.69     13765764.25
      2330122.55     13764030.47       2330984.8     13764564.53
      2331772.57     13762580.52      2333991.83     13763109.47
      2334968.79      13759282.8      2336973.45     13759921.25
      2337318.95     13758132.45      2340849.48     13757152.17
      2339525.08     13754109.61      2339841.27     13752657.77
        2340475.       13753025.      2339428.46      13751776.5
      2340744.96     13751905.84      2342918.66     13748533.02
      2343126.48     13749421.55        2343925.       13748925.

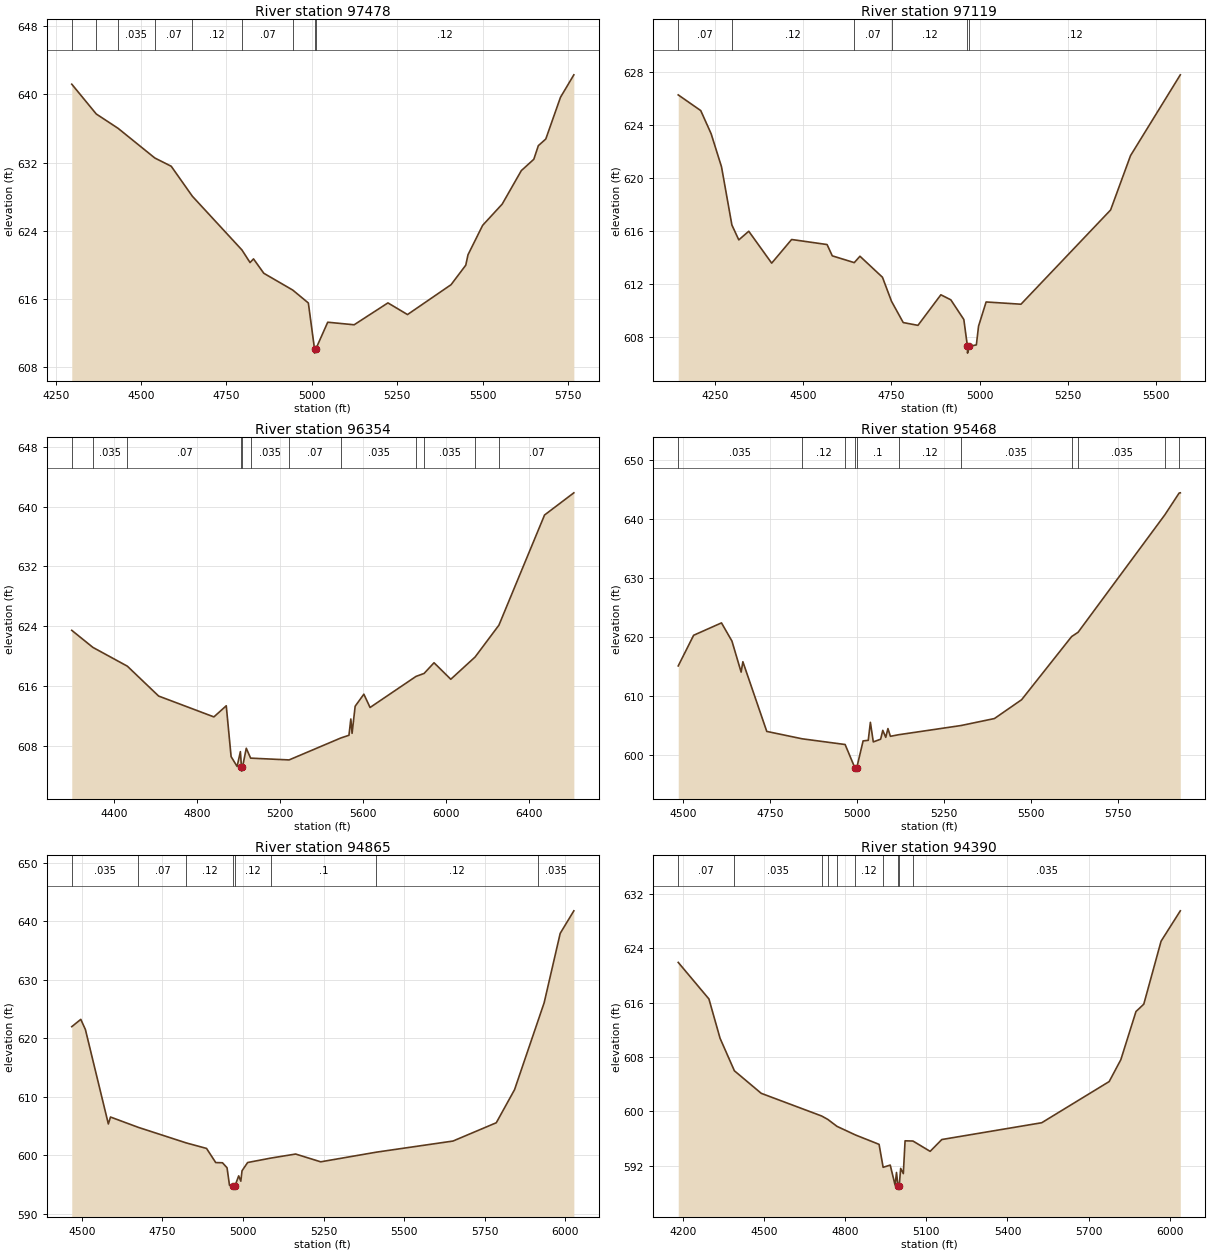
Type RM Length L Ch R = 1 ,97478   ,359,359,359
BEGIN DESCRIPTION:
B19456
END DESCRIPTION:
XS GIS Cut Line= 3
      2325188.18     13794015.25      2325129.62     13793266.95
      2324668.81     13792715.28
#Sta/Elev= 30
  4297.2  641.21  4368.9  637.71  4432.6  636.03  4540.3  632.54  4588.3  631.57
  4650.1  628.05  4795.2  621.74    4819  620.26  4829.1  620.69  4859.2     619
  4943.8  617.03  4989.6  615.51  5007.6  610.12  5007.9  609.62  5011.6  610.12
  5046.3  613.25  5123.6  612.95  5222.5  615.52  5279.8  614.15  5407.3  617.66
  5450.3  619.95  5456.8  621.17  5499.7  624.63    5557  627.13  5612.9  631.06
  5649.4  632.39  5662.7  633.99  5684.5  634.77  5727.5  639.67  5766.6  642.31
#Mann= 9 ,-1 , 0
  4297.2    .035       0  4368.9     .07       0  4432.6    .035       0
  4540.3     .07       0  4650.1     .12       0  4795.2     .07       0
  4943.8     .12       0  5007.6     .05       0  5011.6     .12       0
Bank Sta=5007.6,5011.6
XS Rating Curve= 0 ,0
Exp/Cntr=0.3,0.1

Type RM Length L Ch R = 1 ,97119   ,765,765,765
BEGIN DESCRIPTION:
Mill Creek 131.0
END DESCRIPTION:
XS GIS Cut Line= 3
        2325825.       13793775.        2325325.       13793075.
      2324925.01     13792675.01
#Sta/Elev= 30
  4144.4  626.24  4208.3  625.06  4237.8  623.32  4267.3  620.83  4296.8  616.45
  4316.4  615.33  4344.7  615.98  4409.8  613.58  4466.4  615.36  4567.1  614.98
  4581.9  614.13  4644.3  613.62  4660.5   614.1  4724.4  612.52  4750.1  610.71
  4783.4  609.11  4825.2   608.9  4890.3   611.2  4918.6  610.82  4955.5  609.34
  4965.8  607.31    4966  606.81  4969.8  607.31  4991.1  607.43  4997.3  608.84
  5018.8  610.66  5117.8  610.49  5372.3  617.58  5428.9  621.67  5570.3  627.75
#Mann= 6 ,-1 , 0
  4144.4     .07       0  4296.8     .12       0  4644.3     .07       0
  4750.1     .12       0  4965.8     .05       0  4969.8     .12       0
Bank Sta=4965.8,4969.8
XS Rating Curve= 0 ,0
Exp/Cntr=0.3,0.1

Type RM Length L Ch R = 1 ,96354   ,886,886,886
BEGIN DESCRIPTION:
B19455
END DESCRIPTION:
XS GIS Cut Line= 5
      2326287.92     13793963.26      2325963.49     13793220.03
      2325805.46     13793078.83      2325585.12     13792876.52
      2324675.32     13792259.15
#Sta/Elev= 30
  4195.4  623.44  4297.1  621.16  4463.5  618.64  4614.4  614.64  4880.9  611.85
  4940.5  613.34  4963.9  606.53  4992.8  605.22  5008.7   607.2  5013.9  605.09
  5014.2  604.59  5018.5  605.09  5037.1  607.65    5058  606.33  5243.5  606.09
  5494.2  609.04  5532.3  609.39  5541.3  611.57  5547.3  609.65  5562.2  613.28
  5604.2  614.89  5634.1  613.11  5855.5  617.27  5894.7  617.67  5942.6   619.1
  6023.4  616.89  6140.7  619.87  6255.5  624.13  6475.6  638.88  6616.9  641.85
#Mann= 12 ,-1 , 0
  4195.4     .07       0  4297.1    .035       0  4463.5     .07       0
  5013.9     .05       0  5018.5     .07       0    5058    .035       0
  5243.5     .07       0  5494.2    .035       0  5855.5     .12       0
  5894.7    .035       0  6140.7     .12       0  6255.5     .07       0
Bank Sta=5013.9,5018.5
XS Rating Curve= 0 ,0
Exp/Cntr=0.3,0.1

Type RM Length L Ch R = 1 ,95468   ,603,603,603
BEGIN DESCRIPTION:
B19454
END DESCRIPTION:
XS GIS Cut Line= 4
      2326424.55     13793449.17      2326418.04     13793188.86
      2326157.75     13792824.46      2325676.19     13792271.31
#Sta/Elev= 30
  4486.2  615.15  4530.4  620.34  4610.4  622.44  4640.4  619.36  4666.8   614.1
  4671.8  615.86  4740.4  604.05  4841.8   602.8  4965.4  601.83  4993.8  597.82
  4994.1  597.32  4998.5  597.82    5017  602.44  5031.8  602.54  5037.9  605.59
  5046.3  602.27  5067.4  602.73  5073.5  604.23  5082.1  603.05  5088.3  604.53
  5095.4  603.22  5119.3  603.49  5298.5  605.05  5394.1  606.23  5472.1  609.42
  5615.7  620.12  5634.3  620.85  5883.5  640.76  5924.5  644.45  5927.8  644.48
#Mann= 11 ,-1 , 0
  4486.2    .035       0  4841.8     .12       0  4965.4      .1       0
  4993.8     .05       0  4998.5      .1       0  5119.3     .12       0
  5298.5    .035       0  5615.7     .12       0  5634.3    .035       0
  5883.5     .12       0  5924.5    .035       0
Bank Sta=4993.8,4998.5
XS Rating Curve= 0 ,0
Exp/Cntr=0.3,0.1

Type RM Length L Ch R = 1 ,94865   ,475,475,475
BEGIN DESCRIPTION:
Mill Creek 126.0
END DESCRIPTION:
XS GIS Cut Line= 3
      2326474.97     13793425.04        2326825.       13793025.
      2326124.98     13792274.98
#Sta/Elev= 30
    4469  621.95    4497   623.2  4511.3  621.46  4582.5  605.31  4589.1   606.5
  4675.6  604.73  4824.3  602.07  4887.1  601.13  4915.6  598.71  4936.5  598.68
  4950.7  597.82  4958.3  594.83  4970.2  594.67  4970.5  594.17    4975  594.67
  4986.8  596.44  4993.4  595.53  4997.2  597.31  5014.5  598.72  5085.8  599.47
  5163.5  600.17  5241.2  598.84  5413.7  600.49  5651.5  602.39  5785.9  605.52
  5842.5  611.17  5915.5  622.98  5934.4  626.04  5984.2  637.91  6026.5  641.76
#Mann= 8 ,-1 , 0
    4469    .035       0  4675.6     .07       0  4824.3     .12       0
  4970.2     .05       0    4975     .12       0  5085.8      .1       0
  5413.7     .12       0  5915.5    .035       0
Bank Sta=4970.2,4975
XS Rating Curve= 0 ,0
Exp/Cntr=0.3,0.1

Type RM Length L Ch R = 1 ,94390   ,445,445,445
BEGIN DESCRIPTION:
Mill Creek 125.0
END DESCRIPTION:
XS GIS Cut Line= 3
        2327375.       13793575.        2327175.       13792775.
        2326375.       13792125.
#Sta/Elev= 30
  4183.3  621.93  4296.7  616.55  4337.9  610.76  4390.8  605.98    4490  602.66
  4712.9  599.33  4736.1  598.82  4769.9   597.8  4838.3  596.53  4925.5  595.15
  4940.5  591.77  4966.7   592.1  4984.7  589.15  4989.9  591.01  4995.2  589.06
  4995.6  588.56    5000  589.06  5005.3  591.61  5015.1  590.84  5021.6  595.67
  5050.7  595.64  5114.2  594.12  5157.3  595.86  5526.5  598.33  5775.8  604.39
  5818.9  607.61  5874.9   614.7  5903.7  615.78  5967.6  625.05  6038.7  629.52
#Mann= 10 ,-1 , 0
  4183.3     .07       0  4390.8    .035       0  4712.9     .07       0
  4736.1     .12       0  4769.9     .07       0  4838.3     .12       0
  4940.5      .1       0  4995.2     .05       0    5000      .1       0
  5050.7    .035       0
Bank Sta=4995.2,5000
XS Rating Curve= 0 ,0
Exp/Cntr=0.3,0.1

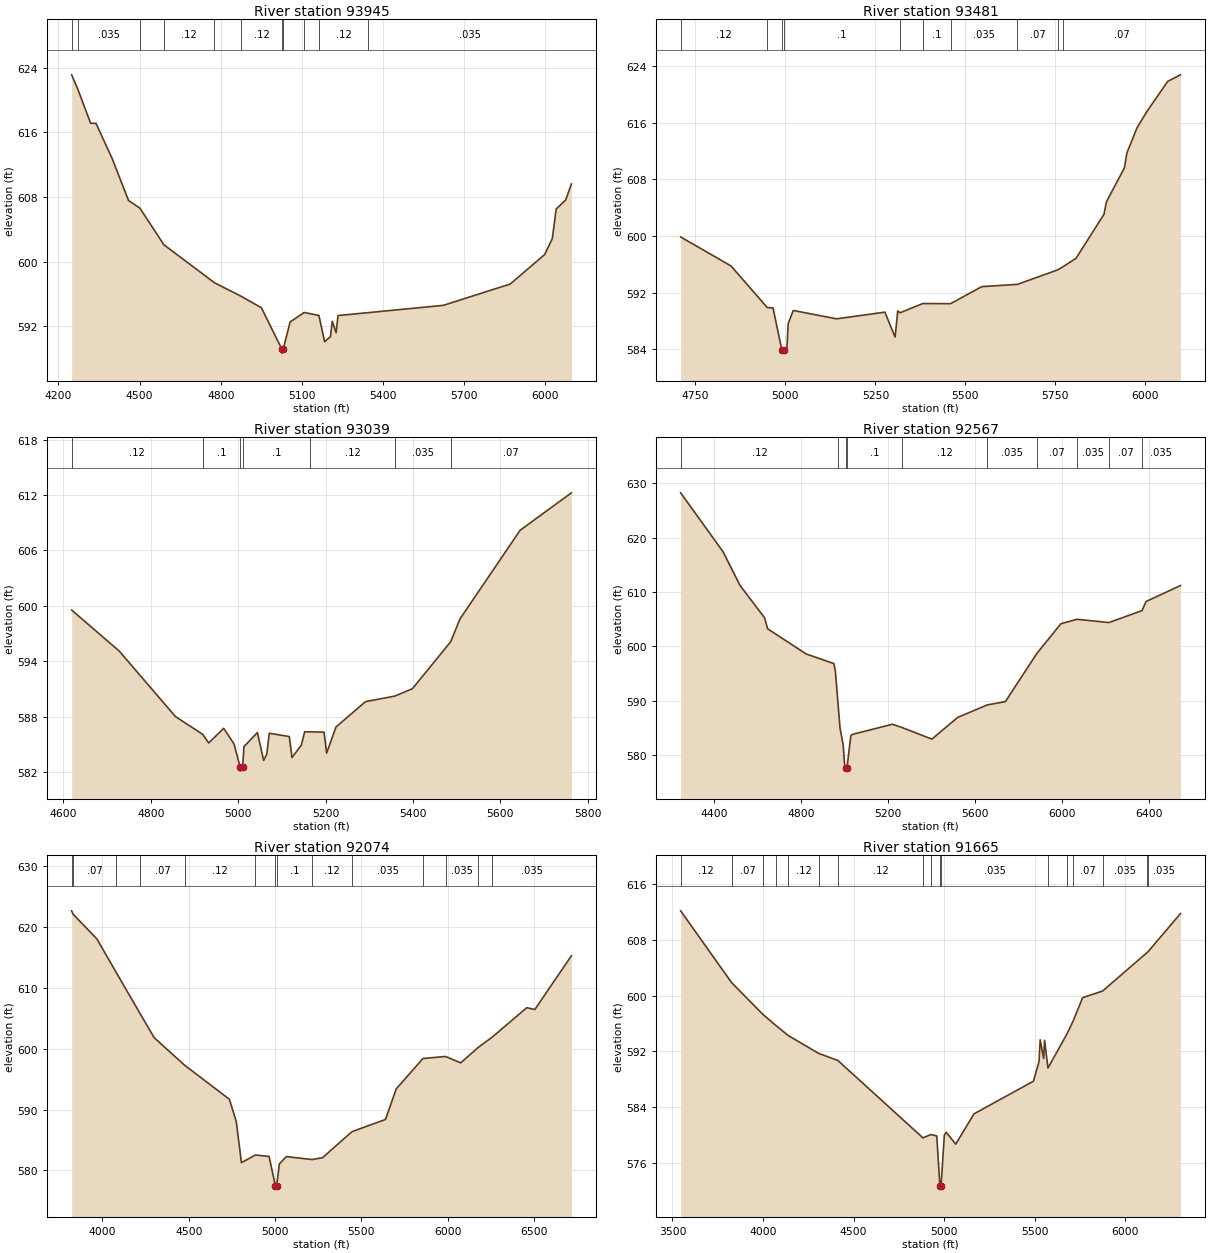
Type RM Length L Ch R = 1 ,93945   ,464,464,464
BEGIN DESCRIPTION:
Mill Creek 124.0
END DESCRIPTION:
XS GIS Cut Line= 3
        2327525.     13793575.04        2327575.       13792825.
        2326775.       13792075.
#Sta/Elev= 30
  4248.8  623.12  4271.4  621.36    4319  617.13    4339  617.11  4399.2  612.71
  4459.3  607.56    4501  606.63    4590  602.09    4777  597.39  4875.4  595.72
  4950.4   594.3  5026.2  589.18  5026.5  588.68  5031.1  589.18  5056.9  592.54
  5108.8  593.71  5163.3  593.34  5184.4  590.09  5205.9  590.72  5212.7  592.61
  5226.9   591.2  5233.8  593.33  5345.2  593.69  5623.1  594.59  5870.7  597.23
  5998.2  600.88  6026.5  602.87  6040.7  606.51  6075.8  607.63  6097.1  609.61
#Mann= 11 ,-1 , 0
  4248.8     .07       0  4271.4    .035       0    4501     .07       0
    4590     .12       0    4777     .07       0  4875.4     .12       0
  5026.2     .05       0  5031.1     .12       0  5108.8      .1       0
  5163.3     .12       0  5345.2    .035       0
Bank Sta=5026.2,5031.1
XS Rating Curve= 0 ,0
Exp/Cntr=0.3,0.1

Type RM Length L Ch R = 1 ,93481   ,442,442,442
BEGIN DESCRIPTION:
Mill Creek 123.0
END DESCRIPTION:
XS GIS Cut Line= 3
      2328175.04     13792725.02        2327925.       13792575.
      2327124.99     13791824.99
#Sta/Elev= 30
    4709  599.86    4849  595.76  4949.6  589.88  4965.6  589.84  4989.8  583.94
  4990.3  583.44  4995.8  583.94    5004  584.01  5007.7   587.6  5021.8  589.47
    5142  588.29  5276.3  589.23  5304.7  585.72    5312   589.4  5318.7  589.15
  5381.6  590.45  5458.8  590.43  5545.5  592.84  5644.4  593.16  5755.9   595.2
  5770.7  595.64  5807.3  596.85  5884.9  603.07  5891.8  604.85  5941.6  609.62
  5948.5  611.72  5976.8  615.31  6005.1  617.67  6061.8  621.85  6097.2  622.78
#Mann= 10 ,-1 , 0
    4709     .12       0  4949.6      .1       0  4989.8     .05       0
  4995.8      .1       0  5318.7     .12       0  5381.6      .1       0
  5458.8    .035       0  5644.4     .07       0  5755.9    .035       0
  5770.7     .07       0
Bank Sta=4989.8,4995.8
XS Rating Curve= 0 ,0
Exp/Cntr=0.3,0.1

Type RM Length L Ch R = 1 ,93039   ,472,472,472
BEGIN DESCRIPTION:
Mill Creek 122.0
END DESCRIPTION:
XS GIS Cut Line= 3
        2328275.     13792574.99        2328125.       13792225.
        2327475.       13791825.
#Sta/Elev= 30
  4618.7  599.54  4727.5  595.11  4856.2  588.02  4918.8  586.09  4932.4  585.16
  4966.8  586.74  4990.4  585.05  5004.1  582.61  5004.6  582.11  5010.2  582.61
  5013.1  584.76  5043.9  586.29  5058.2  583.27  5065.2  583.92    5071  586.21
  5116.9  585.85  5123.1  583.58  5144.4  584.92  5152.1  586.37  5165.4  586.36
  5196.5  586.33  5202.4  584.06  5223.7  586.88  5291.2  589.63  5358.4  590.23
  5398.7  591.03  5486.3  596.11  5507.7  598.59  5645.3  608.18  5762.7  612.23
#Mann= 7 ,-1 , 0
  4618.7     .12       0  4918.8      .1       0  5004.1     .05       0
  5010.2      .1       0  5165.4     .12       0  5358.4    .035       0
  5486.3     .07       0
Bank Sta=5004.1,5010.2
XS Rating Curve= 0 ,0
Exp/Cntr=0.3,0.1

Type RM Length L Ch R = 1 ,92567   ,493,493,493
BEGIN DESCRIPTION:
B19453
END DESCRIPTION:
XS GIS Cut Line= 3
      2329046.96     13792668.31      2328259.57     13791939.49
      2327128.69     13791471.53
#Sta/Elev= 30
  4246.2  628.23  4440.8   617.4    4519  611.19  4631.8  605.23    4646   603.2
  4822.9  598.57  4950.5   596.8  4957.4  595.35  4971.5  588.42  4978.8  584.89
    4993  581.86  4999.8  578.22  5004.1   577.5  5004.6     577  5010.3   577.5
  5028.2  583.48  5035.5  583.76  5219.2  585.63  5264.7  585.01  5400.7  582.89
  5518.9  586.88  5655.4  589.19  5738.5  589.79  5883.7  598.69  5993.7  604.13
  6067.6  604.95  6214.6  604.35  6366.8  606.55  6384.7  608.21    6543  611.16
#Mann= 10 ,-1 , 0
  4246.2     .12       0  4971.5      .1       0  5004.1     .05       0
  5010.3      .1       0  5264.7     .12       0  5655.4    .035       0
  5883.7     .07       0  6067.6    .035       0  6214.6     .07       0
  6366.8    .035       0
Bank Sta=5004.1,5010.3
XS Rating Curve= 0 ,0
Exp/Cntr=0.3,0.1

Type RM Length L Ch R = 1 ,92074   ,409,409,409
BEGIN DESCRIPTION:
B19452
END DESCRIPTION:
XS GIS Cut Line= 4
      2329463.41     13792342.94       2328832.2     13791763.79
      2328148.95     13791757.28      2326899.79     13791230.29
#Sta/Elev= 30
  3821.9  622.65  3830.1  622.11  3968.2  618.03  4078.9  612.59  4218.7  605.75
  4300.5  601.79  4477.3  597.26  4735.7  591.69  4775.7  588.02  4805.7  581.27
  4886.9  582.53  4965.8  582.29  5002.7  577.42  5003.2  576.92  5008.9  577.42
  5025.8  581.08  5065.8  582.26  5215.9  581.78  5275.8  582.09    5446  586.36
  5640.4  588.37  5702.6   593.4  5857.3  598.38    5988  598.72  6076.1  597.67
  6178.3  600.22  6258.3  601.89    6459  606.73  6505.7  606.44  6717.6  615.27
#Mann= 14 ,-1 , 0
  3821.9     .12       0  3830.1     .07       0  4078.9     .12       0
  4218.7     .07       0  4477.3     .12       0  4886.9      .1       0
  5002.7     .05       0  5008.9      .1       0  5215.9     .12       0
    5446    .035       0  5857.3     .07       0    5988    .035       0
  6178.3     .07       0  6258.3    .035       0
Bank Sta=5002.7,5008.9
XS Rating Curve= 0 ,0
Exp/Cntr=0.3,0.1

Type RM Length L Ch R = 1 ,91665   ,452,452,452
BEGIN DESCRIPTION:
B19451
END DESCRIPTION:
XS GIS Cut Line= 4
      2329411.31     13792128.17      2328584.93     13791340.82
      2328148.95     13791477.48      2327055.78     13791087.06
#Sta/Elev= 30
  3545.1   612.2  3826.7  601.88  4001.7  597.26  4073.8  595.67  4138.9  594.29
  4307.4  591.72    4413  590.71  4882.7  579.59  4926.7  580.07  4958.9  579.87
  4976.5  572.73    4977  572.23  4982.8  572.73  5000.8  579.99  5011.3  580.39
  5063.7  578.69  5164.6  583.04  5492.7  587.73  5523.5  590.53  5529.9  593.68
    5549     591  5554.3   593.6  5572.9  589.63  5677.8  594.52  5711.5  596.35
  5764.5  599.73  5874.4  600.68    6122  606.25  6126.2  606.35  6304.2   611.8
#Mann= 17 ,-1 , 0
  3545.1     .12       0  3826.7     .07       0  4001.7     .12       0
  4073.8     .07       0  4138.9     .12       0  4307.4      .1       0
    4413     .12       0  4882.7      .1       0  4926.7    .035       0
  4976.5    .035       0  4982.8    .035       0  5572.9     .07       0
  5677.8    .035       0  5711.5     .07       0  5874.4    .035       0
    6122     .07       0  6126.2    .035       0
Bank Sta=4976.5,4982.8
XS Rating Curve= 0 ,0
Exp/Cntr=0.3,0.1

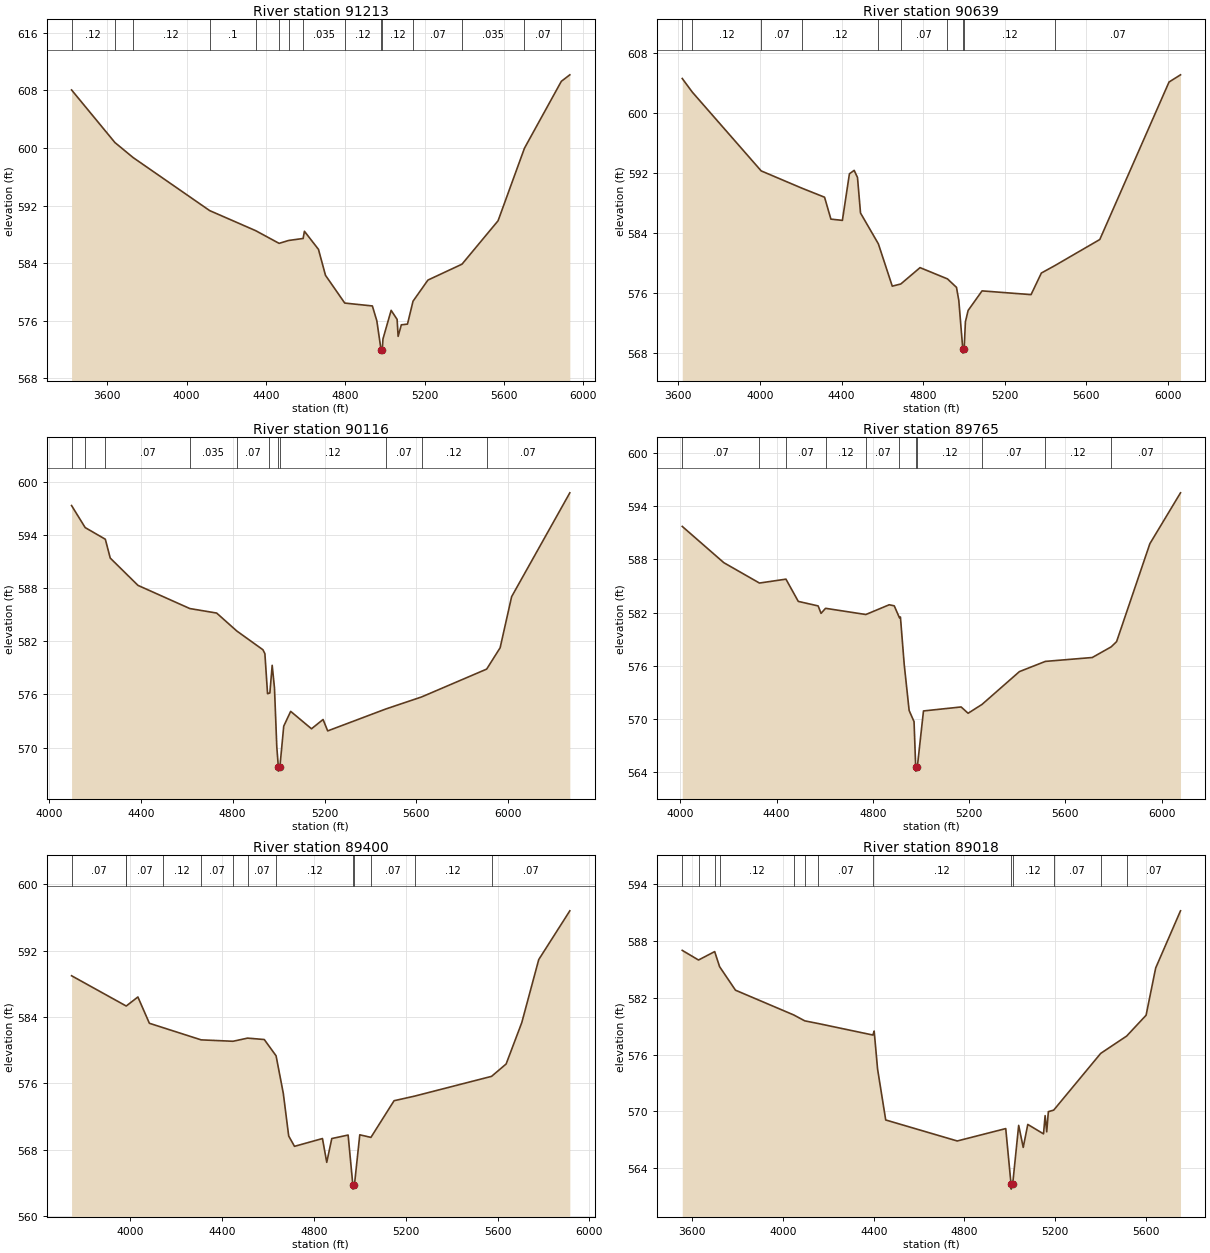
Type RM Length L Ch R = 1 ,91213   ,574,574,574
BEGIN DESCRIPTION:
B19450
END DESCRIPTION:
XS GIS Cut Line= 3
       2329378.8     13792030.58      2328435.27     13791119.58
      2327270.49     13790833.27
#Sta/Elev= 30
  3420.7  608.06  3639.1  600.76  3730.5  598.68  4116.6  591.31  4347.9  588.53
  4466.7  586.76  4514.3  587.16  4587.7  587.44  4594.1  588.44  4664.9  585.93
  4700.4  582.32  4797.4  578.47  4936.6  578.07  4959.1     576  4980.1  572.02
  4980.6  571.52  4986.5  572.02    4990  573.49  5031.2  577.46  5061.3   576.2
  5066.4  573.85  5082.6  575.45  5113.5  575.55  5141.5  578.73  5216.5  581.66
  5388.3  583.87  5570.1   589.9  5703.2  599.98  5888.9  609.26  5931.7  610.16
#Mann= 15 ,-1 , 0
  3420.7     .12       0  3639.1     .07       0  3730.5     .12       0
  4116.6      .1       0  4347.9     .12       0  4466.7      .1       0
  4514.3     .12       0  4587.7    .035       0  4797.4     .12       0
  4980.1     .05       0  4986.5     .12       0  5141.5     .07       0
  5388.3    .035       0  5703.2     .07       0  5888.9    .035       0
Bank Sta=4980.1,4986.5
XS Rating Curve= 0 ,0
Exp/Cntr=0.3,0.1

Type RM Length L Ch R = 1 ,90639   ,523,523,523
BEGIN DESCRIPTION:
B19449
END DESCRIPTION:
XS GIS Cut Line= 4
      2329697.64     13791197.66      2328441.77     13790852.79
      2328155.46     13790696.61      2327349.29     13790586.09
#Sta/Elev= 30
  3619.4  604.62  3668.8   602.8  4006.3   592.3  4206.3  589.99  4316.9  588.79
    4348  585.87  4404.3   585.7  4438.8  591.91  4462.1  592.37  4478.4  591.42
  4493.2  586.68  4580.7  582.57  4648.8  576.93  4690.6  577.22    4785   579.4
  4919.3   577.9  4963.6  576.77    4975  575.01  4994.6   568.5  4995.1     568
  5001.1   568.5  5007.3  572.18  5020.6  573.69  5088.9   576.3  5329.1   575.8
  5379.6  578.68  5446.9  579.69    5666  583.15  6005.4  604.15  6061.6  605.11
#Mann= 10 ,-1 , 0
  3619.4     .07       0  3668.8     .12       0  4006.3     .07       0
  4206.3     .12       0  4580.7    .035       0  4690.6     .07       0
  4919.3     .12       0  4994.6     .05       0  5001.1     .12       0
  5446.9     .07       0
Bank Sta=4994.6,5001.1
XS Rating Curve= 0 ,0
Exp/Cntr=0.3,0.1

Type RM Length L Ch R = 1 ,90116   ,351,351,351
BEGIN DESCRIPTION:
B19448
END DESCRIPTION:
XS GIS Cut Line= 3
      2329652.15     13790599.01      2328493.83     13790462.36
      2327491.72     13790488.38
#Sta/Elev= 30
  4098.9  597.37  4158.1  594.88  4245.8  593.56  4267.2  591.43    4388  588.34
  4613.6  585.72  4730.4  585.21  4818.1  583.18  4931.8  581.06  4940.4  580.61
  4951.9  576.09  4957.4  576.13    4962  576.17  4972.1   579.3  4982.1  576.74
  4992.2  570.07  4998.9  567.83  4999.4  567.33  5005.7  567.83  5022.4  572.42
  5052.6  574.09  5143.2  572.12  5193.6  573.17  5213.7  571.88  5466.8  574.36
  5622.4  575.72  5905.7  578.87  5964.3  581.28  6014.3  587.06  6267.7  598.81
#Mann= 11 ,-1 , 0
  4098.9     .07       0  4158.1     .12       0  4245.8     .07       0
  4613.6    .035       0  4818.1     .07       0  4957.4     .12       0
  4998.9     .05       0  5005.7     .12       0  5466.8     .07       0
  5622.4     .12       0  5905.7     .07       0
Bank Sta=4998.9,5005.7
XS Rating Curve= 0 ,0
Exp/Cntr=0.3,0.1

Type RM Length L Ch R = 1 ,89765   ,365,365,365
BEGIN DESCRIPTION:
B19447
END DESCRIPTION:
XS GIS Cut Line= 3
      2329554.53     13790462.37      2328695.55     13790189.05
      2327550.28     13790423.32
#Sta/Elev= 30
  4008.2  591.73  4180.9  587.64    4329  585.34  4439.1  585.78  4490.4  583.27
  4572.9  582.76  4584.9  581.92  4603.7  582.49  4771.1  581.79  4868.2  582.89
  4889.2  582.77  4910.9  581.41  4914.8  581.51  4930.6  576.14    4951  570.96
  4971.4   569.7  4978.2  564.62  4978.7  564.12  4985.1  564.62  5010.6  570.91
  5167.1  571.36    5196  570.65    5254  571.65  5409.3  575.35    5517   576.5
  5712.1  576.94  5790.5  578.14    5813  578.73  5951.3  589.78  6078.6  595.52
#Mann= 11 ,-1 , 0
  4008.2     .07       0    4329    .035       0  4439.1     .07       0
  4603.7     .12       0  4771.1     .07       0  4910.9     .12       0
  4978.2     .05       0  4985.1     .12       0    5254     .07       0
    5517     .12       0  5790.5     .07       0
Bank Sta=4978.2,4985.1
XS Rating Curve= 0 ,0
Exp/Cntr=0.3,0.1

Type RM Length L Ch R = 1 ,89400   ,382,382,382
BEGIN DESCRIPTION:
B19446
END DESCRIPTION:
XS GIS Cut Line= 4
      2329495.94     13790351.74      2328676.03     13789935.27
      2328279.09     13790006.85      2327512.58     13790370.62
#Sta/Elev= 30
  3743.3  588.96  3980.9  585.32  3981.4  585.31  4032.3   586.4  4082.4  583.23
  4142.1   582.7  4307.9  581.23  4446.7  581.06  4510.5  581.44  4583.1  581.27
  4634.5  579.31    4666  574.78  4689.5  569.64  4714.8  568.39  4836.7  569.33
  4855.3  566.46  4877.3  569.33  4948.5  569.75  4969.1  563.73  4969.6  563.23
    4976  563.73  4999.3  569.78  5047.9  569.47  5148.7  573.89  5238.9  574.45
  5573.7  576.83  5637.1  578.32  5705.3  583.31  5779.2  590.91  5914.7  596.79
#Mann= 13 ,-1 , 0
  3743.3     .07       0  3980.9    .035       0  3981.4     .07       0
  4142.1     .12       0  4307.9     .07       0  4446.7     .12       0
  4510.5     .07       0  4634.5     .12       0  4969.1     .05       0
    4976     .12       0  5047.9     .07       0  5238.9     .12       0
  5573.7     .07       0
Bank Sta=4969.1,4976
XS Rating Curve= 0 ,0
Exp/Cntr=0.3,0.1

Type RM Length L Ch R = 1 ,89018   ,457,457,457
BEGIN DESCRIPTION:
B19445
END DESCRIPTION:
XS GIS Cut Line= 4
      2329404.81      13790241.1      2328610.96     13789707.52
      2328038.33     13789759.58       2327563.3      13790228.1
#Sta/Elev= 30
  3555.2  587.01    3627  585.99  3698.3  586.88  3719.9  585.29  3790.1   582.8
  4047.4  580.18  4095.7  579.56  4154.6  579.28  4396.5  578.06  4402.1  578.48
  4417.1  574.47  4453.1  569.08  4768.7  566.86  4982.7  568.17  5006.2  562.27
  5006.7  561.77  5013.2  562.27  5039.8  568.51  5059.9  566.18    5080  568.61
  5149.4  567.61  5156.5  569.54  5163.6  567.83  5170.7  569.96  5194.3  570.12
  5401.8  576.12  5516.2  577.95    5602  580.15  5644.4  585.15  5753.9  591.19
#Mann= 13 ,-1 , 0
  3555.2     .07       0    3627    .035       0  3698.3     .07       0
  3719.9     .12       0  4047.4     .07       0  4095.7     .12       0
  4154.6     .07       0  4396.5     .12       0  5006.2     .05       0
  5013.2     .12       0  5194.3     .07       0  5401.8     .12       0
  5516.2     .07       0
Bank Sta=5006.2,5013.2
XS Rating Curve= 0 ,0
Exp/Cntr=0.3,0.1

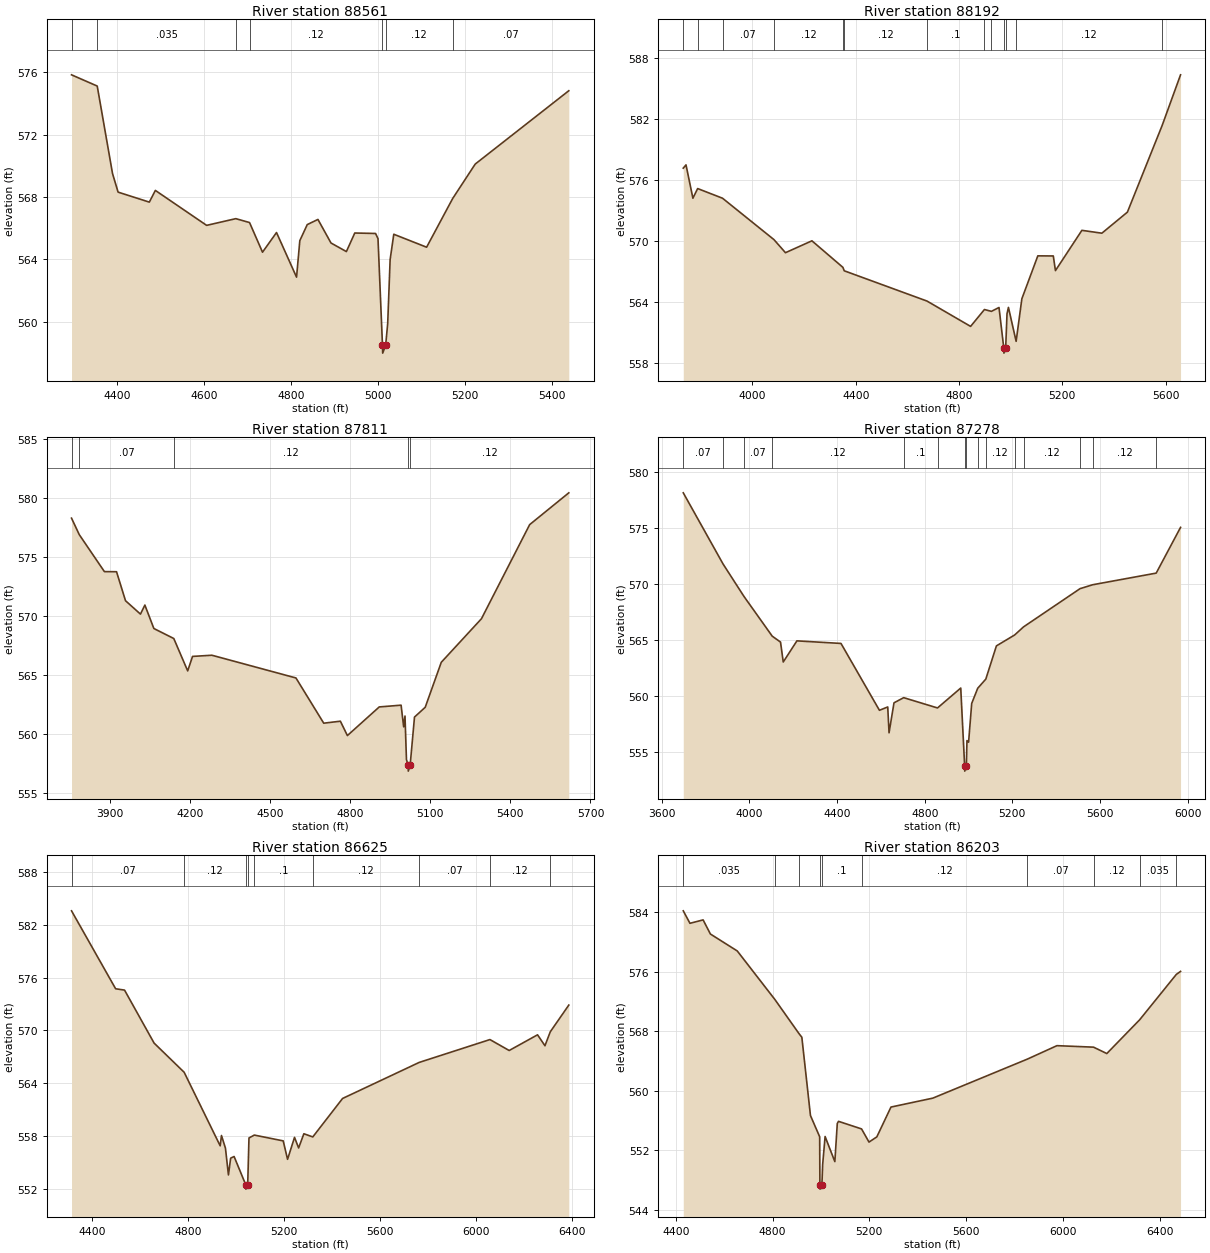
Type RM Length L Ch R = 1 ,88561   ,369,369,369
BEGIN DESCRIPTION:
Mill Creek 113.0
END DESCRIPTION:
XS GIS Cut Line= 3
      2328674.97     13789574.99        2328025.       13789325.
        2327625.       13789525.
#Sta/Elev= 30
  4295.1  575.83  4354.2  575.11  4389.4   569.5  4402.2  568.31    4474  567.67
  4487.9  568.42  4605.8  566.18  4672.9  566.61  4704.5  566.36  4734.3  564.46
  4766.5  565.72  4812.6  562.86  4820.1   565.2  4837.2  566.23  4861.8  566.56
  4891.8  565.05  4927.2   564.5  4946.5  565.69  4994.3  565.66  4999.9  565.33
  5010.2  558.49  5010.7  557.99  5017.5  558.49  5022.2  559.89  5027.8  563.99
  5036.2  565.61  5111.7  564.78  5171.6   567.9  5223.5  570.11  5438.7  574.81
#Mann= 7 ,-1 , 0
  4295.1     .12       0  4354.2    .035       0  4672.9     .07       0
  4704.5     .12       0  5010.2     .05       0  5017.5     .12       0
  5171.6     .07       0
Bank Sta=5010.2,5017.5
XS Rating Curve= 0 ,0
Exp/Cntr=0.3,0.1

Type RM Length L Ch R = 1 ,88192   ,381,381,381
BEGIN DESCRIPTION:
B19444
END DESCRIPTION:
XS GIS Cut Line= 3
      2329001.41     13789252.03      2327908.18     13789011.26
      2327179.67       13789356.
#Sta/Elev= 30
  3732.4  577.21    3743  577.53  3769.7  574.25  3788.1   575.2  3884.4  574.25
  4083.4  570.18  4128.1  568.89  4230.5  570.06  4350.4  567.45  4355.7  567.11
  4676.3  564.13  4844.9  561.64  4898.5   563.3  4925.5  563.12  4954.9   563.5
  4973.4  559.51  4973.9  559.01  4980.7  559.51  4985.9  562.89  4991.4  563.51
  5021.2  560.17  5043.4  564.36  5105.2  568.58  5165.1  568.57  5173.4  567.13
  5275.8  571.09  5353.2  570.81    5452  572.88  5586.6  581.41  5657.8  586.39
#Mann= 13 ,-1 , 0
  3732.4     .12       0  3788.1    .035       0  3884.4     .07       0
  4083.4     .12       0  4350.4     .07       0  4355.7     .12       0
  4676.3      .1       0  4898.5     .12       0  4925.5      .1       0
  4973.4     .05       0  4980.7      .1       0  5021.2     .12       0
  5586.6    .035       0
Bank Sta=4973.4,4980.7
XS Rating Curve= 0 ,0
Exp/Cntr=0.3,0.1

Type RM Length L Ch R = 1 ,87811   ,533,533,533
BEGIN DESCRIPTION:
B19443
END DESCRIPTION:
XS GIS Cut Line= 3
      2328923.35     13789076.34      2327771.53     13788744.46
      2327108.88     13788685.99
#Sta/Elev= 30
  3754.9   578.3  3783.9   576.9  3878.1  573.76  3923.6  573.75  3957.2  571.29
  4013.3  570.15  4029.8  570.92  4063.5  568.93  4138.2  568.08  4190.3  565.33
  4208.5  566.56  4281.1  566.66  4596.1  564.73  4700.2  560.89  4762.6  561.06
  4788.9  559.84  4908.3  562.27  4990.2  562.42  4999.8  560.58  5004.8   561.5
  5010.3   557.8  5016.7  557.32  5017.2  556.82  5024.1  557.32  5040.4  561.41
  5080.6  562.24  5140.8  566.06  5291.4  569.76  5472.1  577.75  5618.8  580.45
#Mann= 5 ,-1 , 0
  3754.9    .035       0  3783.9     .07       0  4138.2     .12       0
  5016.7     .05       0  5024.1     .12       0
Bank Sta=5016.7,5024.1
XS Rating Curve= 0 ,0
Exp/Cntr=0.3,0.1

Type RM Length L Ch R = 1 ,87278   ,653,653,653
BEGIN DESCRIPTION:
B19442
END DESCRIPTION:
XS GIS Cut Line= 4
       2328890.8     13789004.76      2327927.71     13788568.77
       2327556.8     13788165.32      2326932.13     13787937.58
#Sta/Elev= 30
  3697.9  578.18  3879.7  571.81  3974.8  568.92    4104  565.36  4141.9  564.83
  4154.3  563.05  4216.7  564.94  4417.9  564.71  4593.4  558.73  4631.3  559.03
  4637.3  556.72  4659.9   559.4  4704.1  559.86  4858.5  558.94  4964.6  560.72
  4982.3  553.79  4982.8  553.29  4990.2  553.79    4993  556.02  5000.4  555.88
  5014.6  559.34    5042   560.7    5079  561.52  5127.4  564.49  5210.9  565.47
  5251.2  566.19  5509.3  569.61  5567.2  569.96  5856.9     571    5968  575.09
#Mann= 15 ,-1 , 0
  3697.9     .07       0  3879.7     .12       0  3974.8     .07       0
    4104     .12       0  4704.1      .1       0  4858.5     .12       0
  4982.3     .05       0  4990.2     .12       0    5042      .1       0
    5079     .12       0  5210.9     .07       0  5251.2     .12       0
  5509.3     .07       0  5567.2     .12       0  5856.9    .035       0
Bank Sta=4982.3,4990.2
XS Rating Curve= 0 ,0
Exp/Cntr=0.3,0.1

Type RM Length L Ch R = 1 ,86625   ,422,422,422
BEGIN DESCRIPTION:
B19441
END DESCRIPTION:
XS GIS Cut Line= 3
      2328903.76     13788646.84      2327875.65     13788204.37
      2326978.79     13787885.92
#Sta/Elev= 30
  4315.5  583.57  4499.2  574.73  4536.3  574.58  4659.4  568.57  4784.6  565.26
  4934.6  556.92    4940  558.09  4956.5  556.66    4969  553.62  4978.2  555.52
  4992.5  555.71    5041  552.51  5041.5  552.01  5049.2  552.51  5054.5  557.81
  5076.7  558.14  5197.1  557.48  5215.2  555.39  5244.2  557.88  5261.3  556.68
  5283.1  558.29  5320.3  557.93  5444.3  562.29  5763.5  566.38    6058  568.97
  6138.2  567.73  6256.3  569.51  6287.2  568.27  6309.3  569.85  6386.5  572.88
#Mann= 9 ,-1 , 0
  4315.5     .07       0  4784.6     .12       0    5041     .05       0
  5049.2     .12       0  5076.7      .1       0  5320.3     .12       0
  5763.5     .07       0    6058     .12       0  6309.3    .035       0
Bank Sta=5041,5049.2
XS Rating Curve= 0 ,0
Exp/Cntr=0.3,0.1

Type RM Length L Ch R = 1 ,86203   ,589,589,589
BEGIN DESCRIPTION:
B19440
END DESCRIPTION:
XS GIS Cut Line= 3
      2328936.28     13788093.74      2327498.23     13787905.04
       2326899.8     13787813.97
#Sta/Elev= 30
  4430.9  584.22  4458.5  582.54  4512.9     583  4543.1   581.1  4654.1  578.82
  4810.1  572.27  4909.1  567.71  4921.1  567.21  4956.7  556.68  4994.8  553.82
  4995.7  547.28  4996.2  546.78  5003.9  547.28  5007.1  550.08  5017.2  553.86
  5057.5  550.48  5067.6  555.61  5072.6   555.9  5167.9  554.88  5198.7  553.11
  5231.1  553.81  5289.5  557.82  5462.4  559.02  5853.3  564.27  5975.6  566.08
  6126.8  565.88  6181.8  565.02  6317.5  569.56  6469.2  575.67  6486.6  576.07
#Mann= 10 ,-1 , 0
  4430.9    .035       0  4810.1     .07       0  4909.1      .1       0
  4995.7     .05       0  5003.9      .1       0  5167.9     .12       0
  5853.3     .07       0  6126.8     .12       0  6317.5    .035       0
  6469.2     .07       0
Bank Sta=4995.7,5003.9
XS Rating Curve= 0 ,0
Exp/Cntr=0.3,0.1