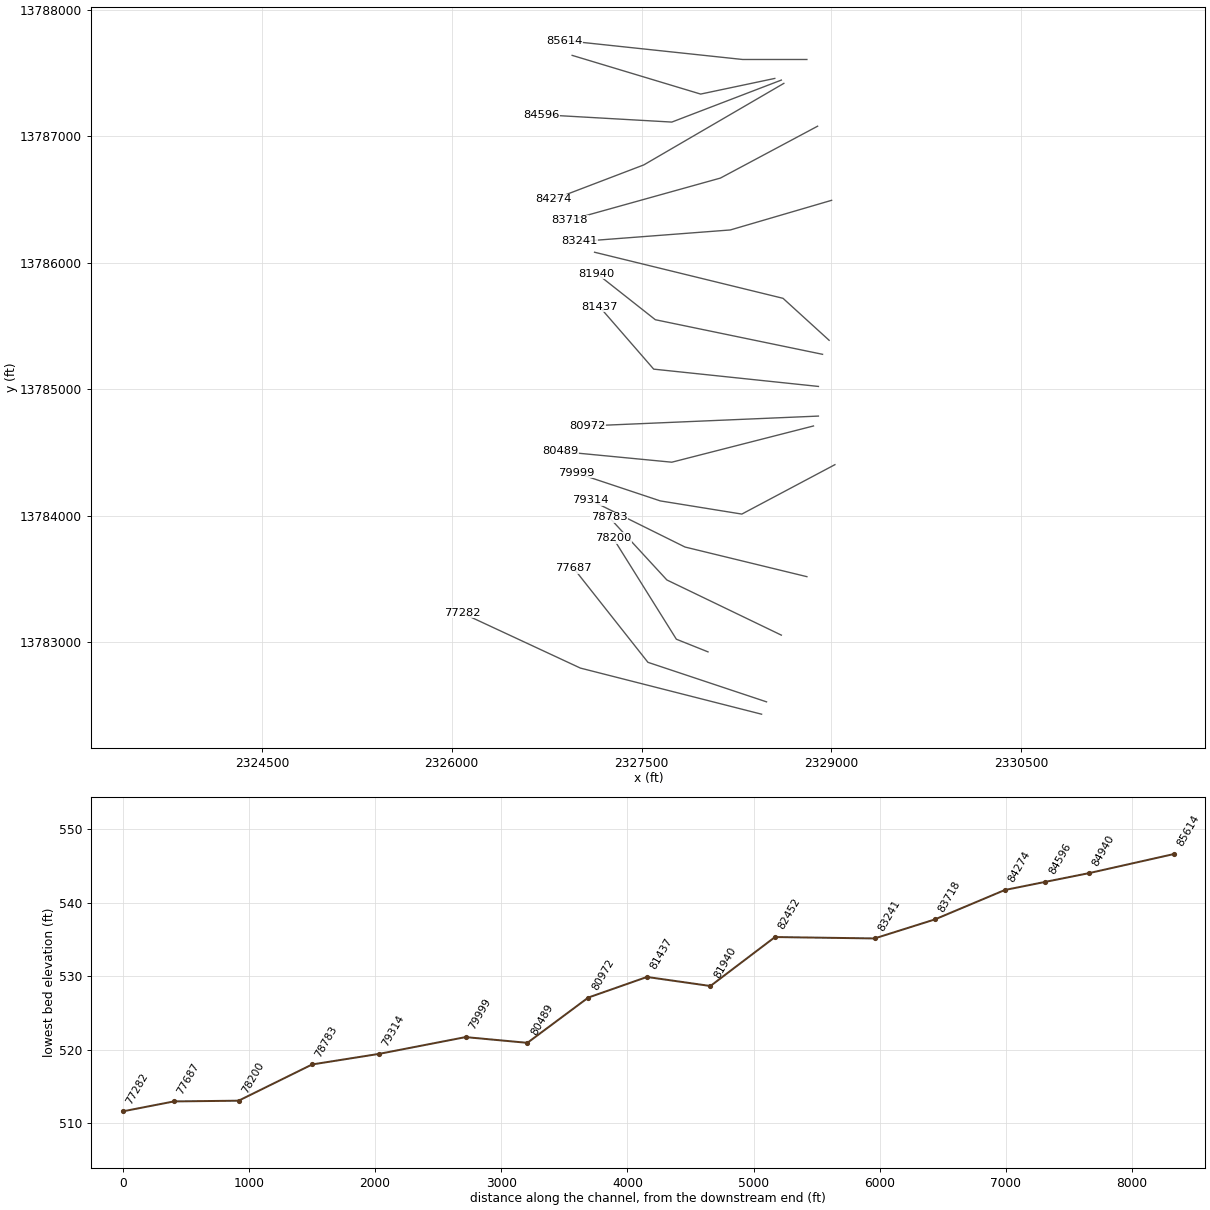
HEC-RAS study Mill Creek.prj: Mill Creek Base Level Engineering

--- Mill Creek.g01 (geometry) --- (continued)

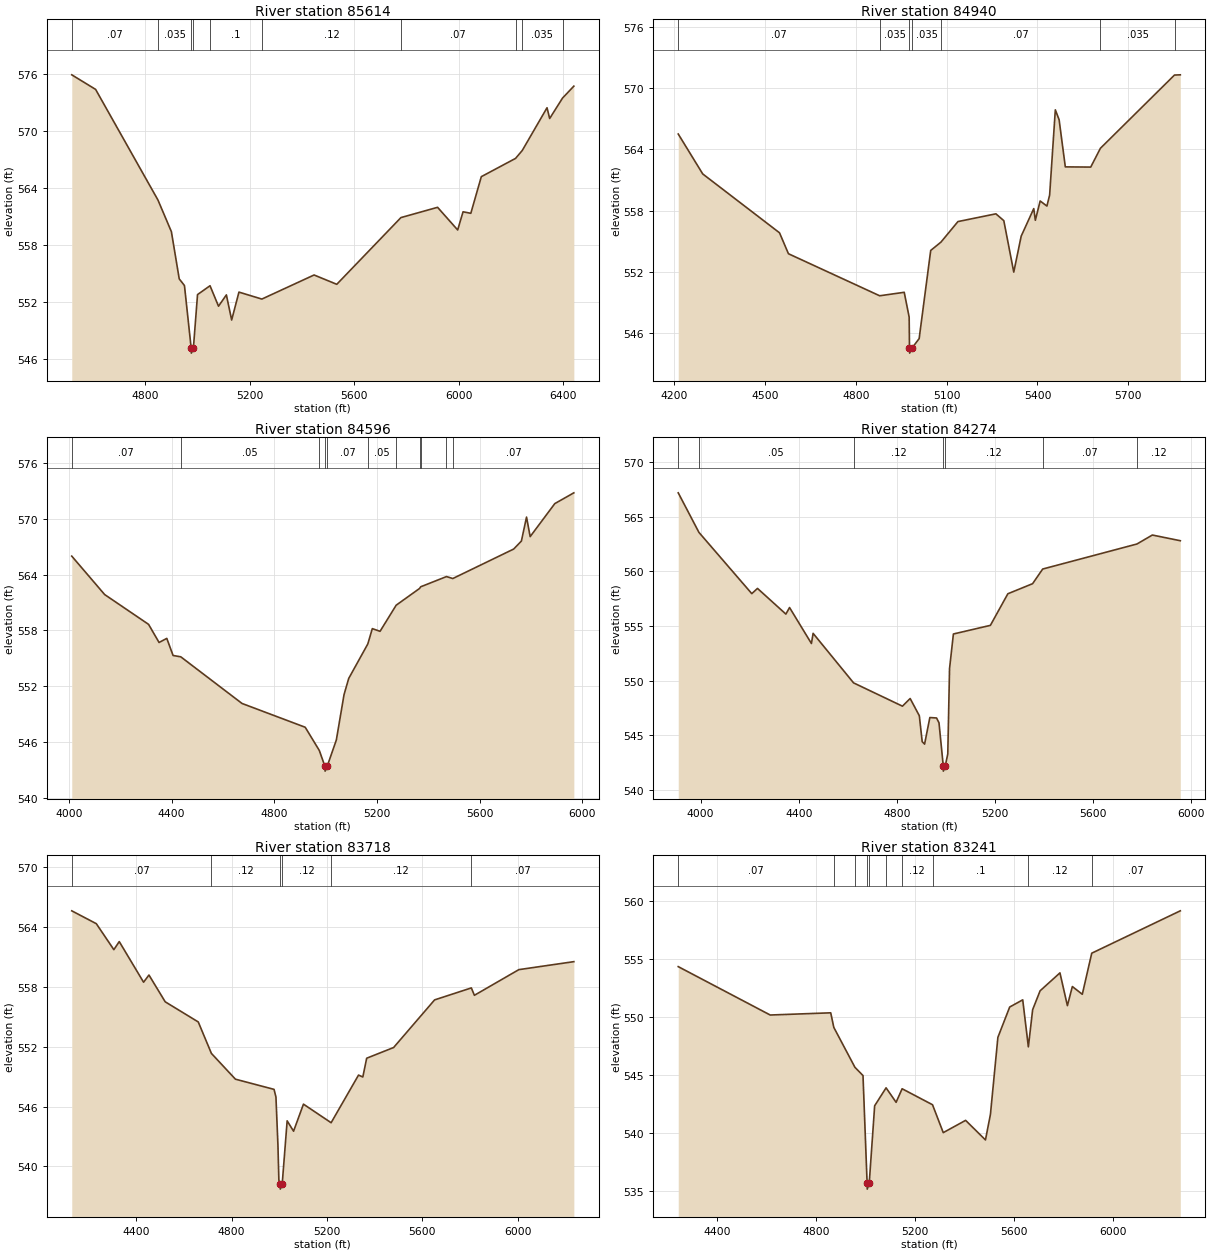
Type RM Length L Ch R = 1 ,85614   ,674,674,674
BEGIN DESCRIPTION:
B19439
END DESCRIPTION:
XS GIS Cut Line= 3
      2328806.17     13787605.71      2328298.61     13787605.71
      2326893.02     13787755.38
#Sta/Elev= 30
  4519.1  575.87  4610.3  574.34    4849  562.71  4900.3  559.39  4930.3  554.43
  4950.3  553.73  4976.1  547.13  4976.6  546.63  4984.4  547.13  5000.3  552.78
  5048.1  553.71  5080.6  551.56  5110.7  552.75  5130.9  550.11  5158.8  553.04
  5246.5  552.31  5446.3  554.84  5533.1  553.86  5778.6  560.87  5918.8  561.95
  5995.7  559.57  6016.3  561.48    6046  561.32  6086.2  565.17  6217.2  567.09
  6242.8  567.92  6337.6  572.41  6347.7  571.28    6397  573.43  6440.2  574.68
#Mann= 10 ,-1 , 0
  4519.1     .07       0    4849    .035       0  4976.1    .035       0
  4984.4    .035       0  5048.1      .1       0  5246.5     .12       0
  5778.6     .07       0  6217.2     .12       0  6242.8    .035       0
    6397     .07       0
Bank Sta=4976.1,4984.4
XS Rating Curve= 0 ,0
Exp/Cntr=0.3,0.1

Type RM Length L Ch R = 1 ,84940   ,344,344,344
BEGIN DESCRIPTION:
B19438
END DESCRIPTION:
XS GIS Cut Line= 3
      2328552.39     13787456.04      2327966.75      13787332.4
      2326951.66     13787638.23
#Sta/Elev= 30
  4213.3   565.5  4294.2  561.59  4547.9  555.82  4577.4  553.77  4878.7  549.65
  4959.9  549.99  4976.2  547.56  4977.3  544.53  4977.8  544.03  4985.6  544.53
  5009.2  545.45  5047.4  554.09  5081.3  554.91  5137.4  556.92  5262.8  557.68
  5288.9  557.01  5321.8  551.97  5346.3  555.49  5387.8  558.19  5393.1  557.05
    5409  558.94  5431.3  558.44  5440.3  559.52  5459.1  567.87  5471.6   566.9
  5492.1  562.28  5576.1  562.26    5608   564.1  5852.8  571.28    5872   571.3
#Mann= 7 ,-1 , 0
  4213.3     .07       0  4878.7    .035       0  4977.3    .035       0
  4985.6    .035       0  5081.3     .07       0    5608    .035       0
  5852.8     .07       0
Bank Sta=4977.3,4985.6
XS Rating Curve= 0 ,0
Exp/Cntr=0.3,0.1

Type RM Length L Ch R = 1 ,84596   ,322,322,322
BEGIN DESCRIPTION:
B19437
END DESCRIPTION:
XS GIS Cut Line= 3
      2328604.48     13787443.03        2327739.     13787111.16
      2326710.89     13787169.72
#Sta/Elev= 30
  4010.8  565.98  4138.8  561.85  4310.1  558.64    4351  556.69  4381.1  557.13
  4405.7  555.29  4435.5  555.15  4674.3  550.13  4920.6  547.57  4975.6  545.07
  4997.6  543.35  4998.1  542.85    5006  543.35  5041.9   546.2  5071.9  551.08
  5090.1  552.82  5164.5  556.53  5182.1  558.18  5212.2  557.89  5275.1   560.7
  5366.2   562.5  5370.6  562.68  5471.2  563.78  5495.8  563.57    5733  566.74
  5763.1   567.6  5783.1  570.18  5797.3  568.08  5893.3  571.63  5967.5  572.79
#Mann= 11 ,-1 , 0
  4010.8     .07       0  4435.5     .05       0  4975.6     .07       0
  4997.6     .05       0    5006     .07       0  5164.5     .05       0
  5275.1     .07       0  5366.2     .12       0  5370.6     .07       0
  5471.2     .05       0  5495.8     .07       0
Bank Sta=4997.6,5006
XS Rating Curve= 0 ,0
Exp/Cntr=0.3,0.1

Type RM Length L Ch R = 1 ,84274   ,556,556,556
BEGIN DESCRIPTION:
B19436
END DESCRIPTION:
XS GIS Cut Line= 3
        2328624.     13787417.01      2327517.75     13786772.79
      2326802.67     13786499.75
#Sta/Elev= 30
  3909.2  567.19  3993.6  563.57  4208.9  557.97  4232.1  558.45  4347.8   556.1
  4362.7   556.7  4451.9  553.41  4458.7  554.34  4623.6  549.81  4822.7  547.68
  4854.1  548.38  4891.4  546.81  4903.2  544.43  4912.9  544.21  4934.4  546.64
  4961.7   546.6  4971.6  546.16  4988.9  542.24  4989.4  541.74  4997.3  542.24
  5007.4  543.31  5014.6  551.12  5030.3  554.28    5181  555.07  5252.2  557.96
  5352.9  558.88  5394.1  560.22  5778.1  562.51  5840.9  563.33  5954.8  562.81
#Mann= 7 ,-1 , 0
  3909.2     .07       0  3993.6     .05       0  4623.6     .12       0
  4988.9     .05       0  4997.3     .12       0  5394.1     .07       0
  5778.1     .12       0
Bank Sta=4988.9,4997.3
XS Rating Curve= 0 ,0
Exp/Cntr=0.3,0.1

Type RM Length L Ch R = 1 ,83718   ,477,477,477
BEGIN DESCRIPTION:
B19435
END DESCRIPTION:
XS GIS Cut Line= 3
      2328890.77     13787078.62      2328122.92     13786668.67
      2326932.13     13786336.81
#Sta/Elev= 30
  4129.7   565.6  4232.8  564.31  4306.3  561.71  4328.9  562.52    4431  558.45
  4453.6  559.17  4521.7  556.49  4660.5  554.47  4715.6  551.32  4816.4  548.74
  4978.4  547.72  4986.4  546.95  4994.7  542.17  4998.7  538.62  5004.1  538.23
  5004.6  537.73  5012.6  538.23  5033.4  544.57  5060.3  543.53  5101.8  546.24
  5217.9  544.38  5332.9  549.15  5350.9  548.96  5367.1  550.84  5480.1  551.91
    5652  556.68  5806.3  557.88    5819  557.14  6005.5  559.71  6236.3  560.51
#Mann= 6 ,-1 , 0
  4129.7     .07       0  4715.6     .12       0  5004.1     .05       0
  5012.6     .12       0  5217.9     .12       0  5806.3     .07       0
Bank Sta=5004.1,5012.6
XS Rating Curve= 0 ,0
Exp/Cntr=0.3,0.1

Type RM Length L Ch R = 1 ,83241   ,789,789,789
BEGIN DESCRIPTION:
B19434
END DESCRIPTION:
XS GIS Cut Line= 3
      2329001.36     13786492.97      2328201.01     13786258.72
      2327010.21     13786167.62
#Sta/Elev= 30
  4243.8  554.37  4615.3  550.19  4859.8  550.38  4872.3  549.12  4957.7  545.67
  4990.2  544.96  5006.8  535.65  5007.3  535.15  5015.3  535.65  5037.3  542.35
  5083.4   543.9  5123.9  542.65  5148.2  543.82    5271  542.44  5314.4  540.03
  5404.7  541.09  5484.9   539.4    5505  541.61  5535.1  548.26  5582.8  550.88
  5635.4   551.5  5658.2  547.44  5675.5  550.65  5705.6  552.28  5785.8  553.83
  5815.9     551  5835.9  552.65  5876.1  551.98  5914.2  555.53    6272  559.19
#Mann= 10 ,-1 , 0
  4243.8     .07       0  4872.3    .035       0  4957.7     .12       0
  5006.8     .05       0  5015.3     .12       0  5083.4      .1       0
  5148.2     .12       0    5271      .1       0  5658.2     .12       0
  5914.2     .07       0
Bank Sta=5006.8,5015.3
XS Rating Curve= 0 ,0
Exp/Cntr=0.3,0.1

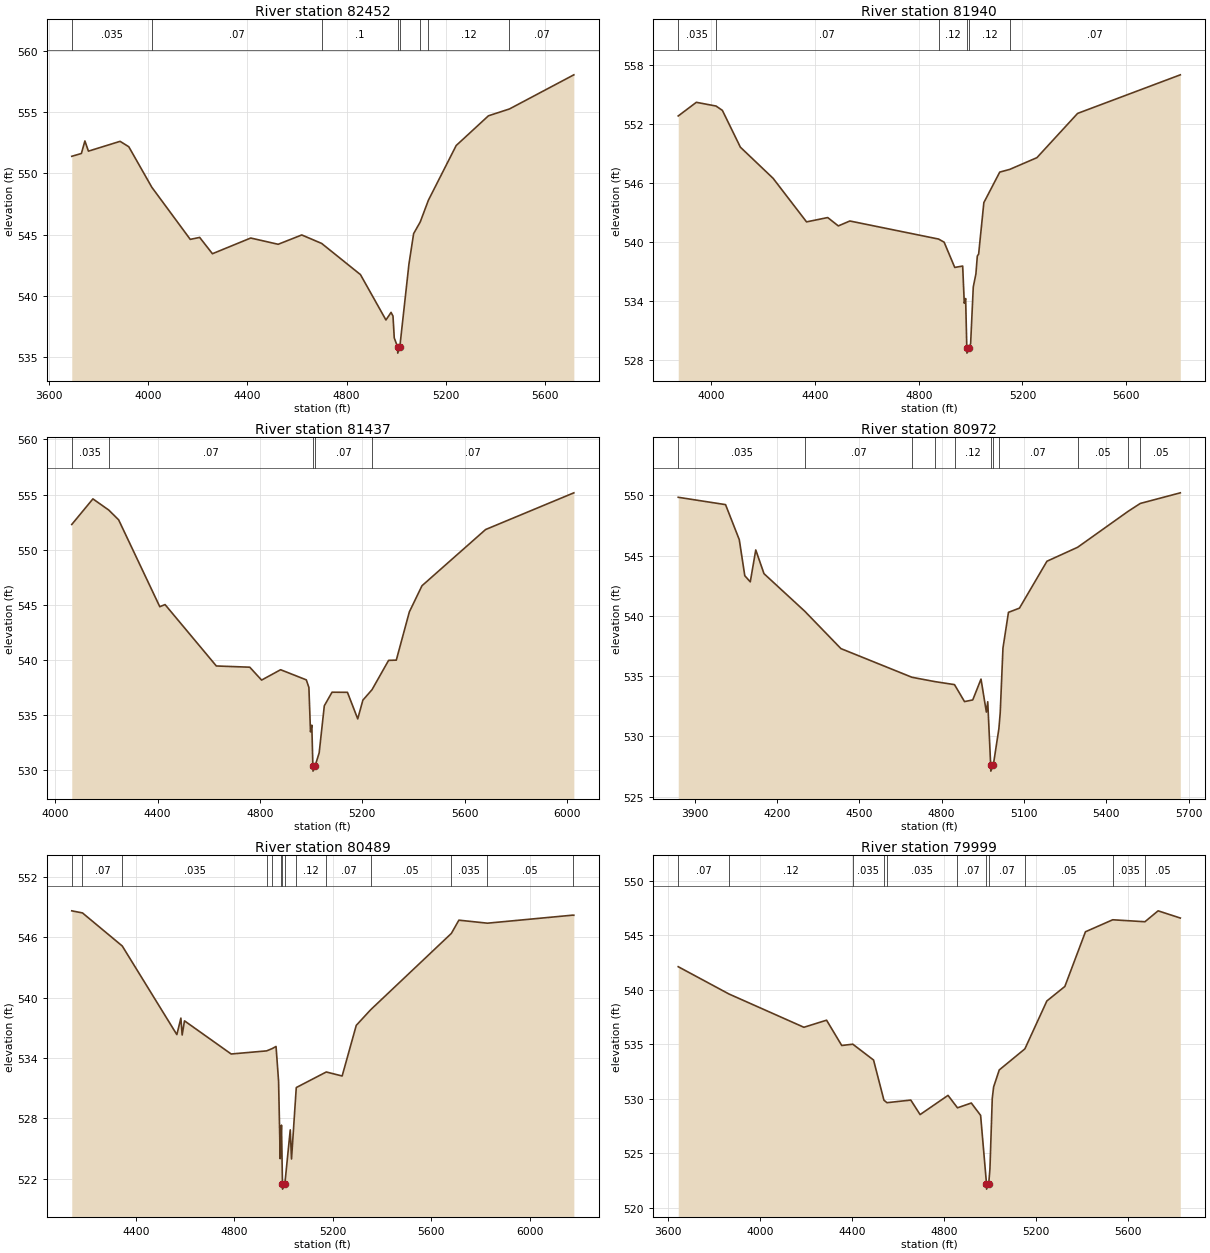
Type RM Length L Ch R = 1 ,82452   ,512,512,512
BEGIN DESCRIPTION:
B19433
END DESCRIPTION:
XS GIS Cut Line= 3
      2328981.87     13785386.76      2328617.47     13785718.62
      2327128.71     13786082.69
#Sta/Elev= 30
  3691.5  551.38  3730.3  551.61  3744.5  552.63  3758.7   551.8  3886.4   552.6
  3921.5  552.16  4014.4  548.86  4169.5  544.61  4207.5  544.77    4259  543.44
  4413.4  544.72  4524.2  544.21  4619.3  544.97  4699.6  544.28  4856.1  541.74
    4959  538.04  4979.6  538.66  4987.4  538.36  4992.5  536.58  5006.1  535.84
  5006.6  535.34  5014.9  535.84  5051.7  542.59  5070.7  545.08  5097.3  546.03
  5130.2   547.8  5242.4  552.26  5372.4  554.68  5457.4  555.24    5717  558.02
#Mann= 8 ,-1 , 0
  3691.5    .035       0  4014.4     .07       0  4699.6      .1       0
  5006.1     .05       0  5014.9      .1       0  5097.3     .07       0
  5130.2     .12       0  5457.4     .07       0
Bank Sta=5006.1,5014.9
XS Rating Curve= 0 ,0
Exp/Cntr=0.3,0.1

Type RM Length L Ch R = 1 ,81940   ,503,503,503
BEGIN DESCRIPTION:
B19432
END DESCRIPTION:
XS GIS Cut Line= 3
      2328929.86     13785276.13      2327608.85     13785549.44
      2327146.85     13785913.84
#Sta/Elev= 30
    3872  552.84  3941.9  554.23  4017.9  553.85  4042.3  553.41  4111.8  549.66
    4238  546.49  4367.1  542.05  4448.8  542.49  4489.7  541.64  4534.2  542.14
  4876.5   540.3  4898.1  539.98    4939  537.41  4969.6  537.55  4975.8  533.76
    4981  534.24  4985.6  529.18  4986.1  528.68  4994.5  529.18  5000.3  529.67
  5010.5  535.42  5020.7  536.76  5026.1  538.57  5031.2  538.77  5051.3  544.01
  5112.6  547.12  5151.5   547.4    5256  548.59  5413.1   553.1  5809.4  557.03
#Mann= 6 ,-1 , 0
    3872    .035       0  4017.9     .07       0  4876.5     .12       0
  4985.6     .05       0  4994.5     .12       0  5151.5     .07       0
Bank Sta=4985.6,4994.5
XS Rating Curve= 0 ,0
Exp/Cntr=0.3,0.1

Type RM Length L Ch R = 1 ,81437   ,465,465,465
BEGIN DESCRIPTION:
B19431
END DESCRIPTION:
XS GIS Cut Line= 3
      2328897.29     13785022.35      2327595.84     13785159.01
      2327166.37     13785653.55
#Sta/Elev= 30
    4064  552.29  4146.7  554.61  4208.5   553.6  4247.3  552.71  4408.2  544.83
  4428.9  545.02  4629.4  539.45  4760.1  539.34  4806.4  538.17  4880.8  539.11
  4981.3  538.19  4991.4   537.5  4997.7  533.47  5002.8  534.08  5006.9  530.41
  5007.4  529.91    5016  530.41  5031.6  531.57  5051.7  535.84  5081.9  537.07
  5142.2  537.06  5182.4  534.65  5202.5  536.35  5238.3   537.3  5303.1  539.96
  5333.2  539.98  5384.3  544.36  5433.7  546.73  5682.5  551.83  6027.6  555.16
#Mann= 5 ,-1 , 0
    4064    .035       0  4208.5     .07       0  5006.9     .05       0
    5016     .07       0  5238.3     .07       0
Bank Sta=5006.9,5016
XS Rating Curve= 0 ,0
Exp/Cntr=0.3,0.1

Type RM Length L Ch R = 1 ,80972   ,483,483,483
BEGIN DESCRIPTION:
B19430
END DESCRIPTION:
XS GIS Cut Line= 2
      2328897.25      13784788.1      2327069.42     13784710.04
#Sta/Elev= 30
  3840.2  549.84  4012.6  549.23  4062.7  546.32  4082.7  543.33  4102.7  542.82
  4122.7  545.47  4152.7   543.5  4301.3  540.38    4433  537.28  4691.8   534.9
  4775.4  534.54  4846.9  534.29  4883.4  532.88  4913.4  533.02  4943.5  534.75
    4963  532.01    4968  532.87  4978.7  527.61  4979.2  527.11  4988.3  527.61
  5008.6  530.63  5013.5  531.96  5023.5  537.33  5043.5  540.29  5083.6  540.64
  5183.7  544.53  5295.5  545.69  5479.9  548.68    5524  549.33  5669.7  550.21
#Mann= 11 ,-1 , 0
  3840.2    .035       0  4301.3     .07       0  4691.8     .12       0
  4775.4     .07       0  4846.9     .12       0  4978.7     .05       0
  4988.3     .12       0  5008.6     .07       0  5295.5     .05       0
  5479.9     .07       0    5524     .05       0
Bank Sta=4978.7,4988.3
XS Rating Curve= 0 ,0
Exp/Cntr=0.3,0.1

Type RM Length L Ch R = 1 ,80489   ,490,490,490
BEGIN DESCRIPTION:
B19429
END DESCRIPTION:
XS GIS Cut Line= 3
       2328858.2       13784710.        2327739.      13784423.7
      2326860.51     13784508.29
#Sta/Elev= 30
  4140.5  548.65    4184  548.44  4345.4  545.15    4567  536.33  4583.4  537.97
  4588.6  536.29    4598   537.7  4787.5   534.4  4931.5  534.71  4954.1  534.94
  4969.6  535.15  4979.9   531.7  4986.5  523.98  4990.6  526.67  4991.6  527.32
  4995.7  521.45  4996.2  520.95  5005.3  521.45  5027.3  526.85  5032.4  523.95
  5051.7  531.06  5173.5  532.61  5237.9  532.21  5295.2  537.25  5353.5   538.8
  5681.1   546.4  5711.7  547.72  5827.6  547.42  6173.9  548.22  6178.3  548.21
#Mann= 14 ,-1 , 0
  4140.5    .035       0    4184     .07       0  4345.4    .035       0
  4931.5     .07       0  4954.1     .12       0  4990.6     .07       0
  4995.7     .05       0  5005.3     .07       0  5051.7     .12       0
  5173.5     .07       0  5353.5     .05       0  5681.1    .035       0
  5827.6     .05       0  6173.9     .07       0
Bank Sta=4995.7,5005.3
XS Rating Curve= 0 ,0
Exp/Cntr=0.3,0.1

Type RM Length L Ch R = 1 ,79999   ,685,685,685
BEGIN DESCRIPTION:
B19428
END DESCRIPTION:
XS GIS Cut Line= 4
      2329027.43     13784404.18      2328292.11     13784013.74
       2327647.9     13784117.86      2326984.12     13784339.12
#Sta/Elev= 30
  3643.1  542.11  3863.8  539.61    4190  536.56  4288.6  537.21  4354.6  534.89
  4402.7  535.01    4493  533.56  4538.2  529.88  4551.5  529.65  4655.1  529.89
  4695.6  528.56  4817.1  530.32  4858.3  529.18  4918.4  529.62  4958.9  528.49
  4984.5  522.23    4985  521.73  4994.2  522.23  4999.5  523.58  5009.6  530.04
  5015.5  531.09    5040  532.65  5151.5  534.58  5247.2  538.97  5325.5   540.3
  5415.1  545.31  5533.7  546.41  5673.9  546.23  5731.3  547.23  5827.9  546.57
#Mann= 11 ,-1 , 0
  3643.1     .07       0  3863.8     .12       0  4402.7    .035       0
  4538.2     .07       0  4551.5    .035       0  4858.3     .07       0
  4984.5     .05       0  4994.2     .07       0  5151.5     .05       0
  5533.7    .035       0  5673.9     .05       0
Bank Sta=4984.5,4994.2
XS Rating Curve= 0 ,0
Exp/Cntr=0.3,0.1

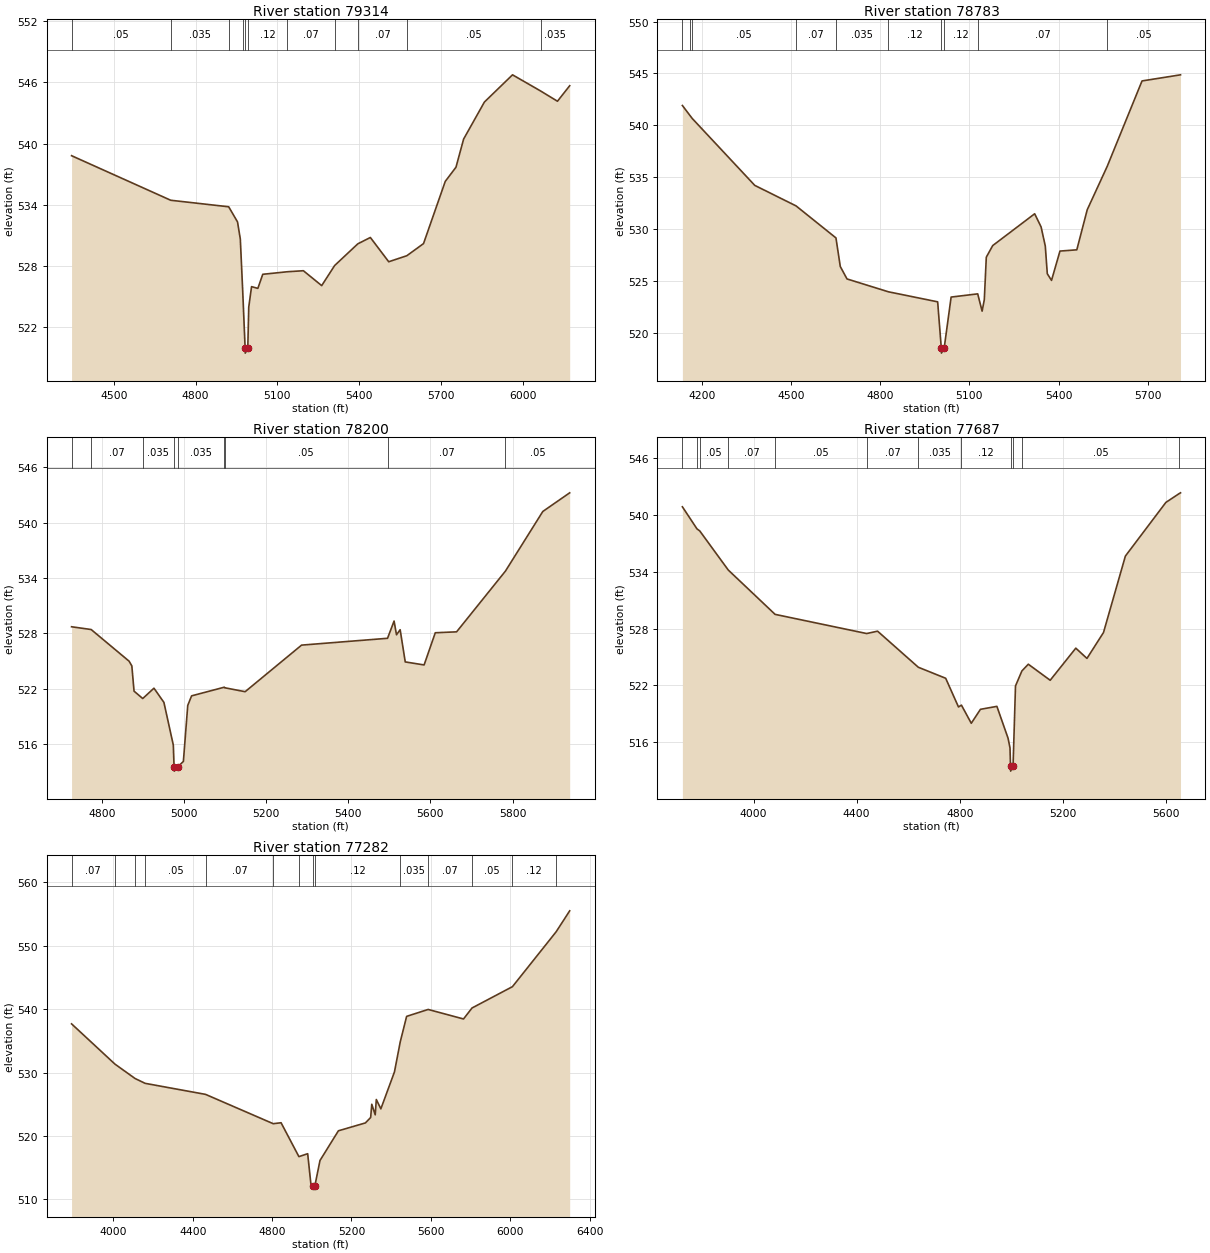
Type RM Length L Ch R = 1 ,79314   ,531,531,531
BEGIN DESCRIPTION:
B19427
END DESCRIPTION:
XS GIS Cut Line= 3
      2328806.16      13783519.2      2327843.11     13783753.46
      2327094.82     13784124.35
#Sta/Elev= 30
  4345.5  538.81  4709.1  534.44  4921.6   533.8  4953.9  532.32  4964.2  530.64
  4973.1  525.46  4981.8  519.95  4982.3  519.45  4991.6  519.95  4995.1  523.96
  5005.4  525.97  5028.5   525.8  5046.5  527.18  5136.7  527.43  5195.4  527.53
  5262.6  526.07    5310  528.04  5395.1  530.17    5441  530.79  5508.3  528.41
  5574.6     529  5635.9  530.19  5715.6  536.29  5754.9  537.68  5782.9  540.44
  5859.1  544.07  5962.2  546.74  6064.9  545.16    6127  544.15  6171.8  545.67
#Mann= 11 ,-1 , 0
  4345.5     .05       0  4709.1    .035       0  4921.6     .07       0
  4973.1     .12       0  4981.8     .05       0  4991.6     .12       0
  5136.7     .07       0    5310     .05       0  5395.1     .07       0
  5574.6     .05       0  6064.9    .035       0
Bank Sta=4981.8,4991.6
XS Rating Curve= 0 ,0
Exp/Cntr=0.3,0.1

Type RM Length L Ch R = 1 ,78783   ,583,583,583
BEGIN DESCRIPTION:
B19426
END DESCRIPTION:
XS GIS Cut Line= 3
      2328604.43      13783057.2      2327699.95     13783493.17
      2327244.46      13783987.7
#Sta/Elev= 30
  4134.2  541.91  4160.6  540.91  4167.9  540.64  4377.8   534.2  4516.7  532.22
    4651  529.13  4665.6  526.37  4688.2  525.17  4827.5  523.93  4993.3  522.96
  5005.5  518.51    5006  518.01  5015.3  518.51  5038.6  523.42  5128.1  523.73
  5142.9  522.06  5150.3  523.17    5157  527.27  5178.6  528.39  5319.8  531.46
  5341.4  530.19  5355.5  528.35  5362.3  525.67  5376.5  525.03  5404.9  527.86
  5461.6  527.98  5496.7  531.85    5564  536.04  5681.1  544.28  5810.6  544.87
#Mann= 10 ,-1 , 0
  4134.2     .05       0  4160.6     .07       0  4167.9     .05       0
  4516.7     .07       0    4651    .035       0  4827.5     .12       0
  5005.5     .05       0  5015.3     .12       0  5128.1     .07       0
    5564     .05       0
Bank Sta=5005.5,5015.3
XS Rating Curve= 0 ,0
Exp/Cntr=0.3,0.1

Type RM Length L Ch R = 1 ,78200   ,513,513,513
BEGIN DESCRIPTION:
Mill Creek 96.0
END DESCRIPTION:
XS GIS Cut Line= 3
      2328024.96     13782925.02        2327775.       13783025.
      2327275.01     13783824.99
#Sta/Elev= 30
  4726.4  528.73  4774.1  528.43  4866.4     525  4873.1  524.49  4878.5  521.75
  4899.6  520.95    4927  522.07  4951.2  520.53  4974.1   515.9  4975.9  513.58
  4976.4  513.08  4985.7  513.58  4998.6  514.13  5009.2   520.2  5018.6  521.24
  5098.4  522.18    5099  522.12  5148.9  521.69  5286.3  526.74  5495.6  527.48
  5511.5  529.35  5517.4  527.86  5526.3  528.41  5538.7  524.92  5584.6  524.59
  5611.8  528.08  5663.7  528.18  5782.5  534.76  5873.6  541.23    5939  543.25
#Mann= 9 ,-1 , 0
  4726.4     .05       0  4774.1     .07       0  4899.6    .035       0
  4975.9    .035       0  4985.7    .035       0  5098.4     .07       0
    5099     .05       0  5495.6     .07       0  5782.5     .05       0
Bank Sta=4975.9,4985.7
XS Rating Curve= 0 ,0
Exp/Cntr=0.3,0.1

Type RM Length L Ch R = 1 ,77687   ,405,405,405
BEGIN DESCRIPTION:
B19425
END DESCRIPTION:
XS GIS Cut Line= 3
      2328487.34      13782530.1      2327550.29     13782842.45
      2326964.63     13783584.29
#Sta/Elev= 30
  3723.7  540.82  3780.4  538.49    3791  538.28  3901.7  534.16  4083.4  529.49
  4438.8  527.47  4481.1  527.72  4639.2  523.92  4745.4  522.76    4795  519.74
  4806.5  519.93  4844.7  518.02  4880.3  519.49  4944.1   519.8  4987.4  516.45
    4995  515.42  4996.9  513.48  4997.4  512.98  5006.8  513.48  5016.3  521.95
  5041.1  523.53    5066  524.24  5150.9  522.55  5250.3  525.93  5293.6  524.85
  5357.8  527.58  5442.7  535.63  5599.8  541.28  5651.5  542.21  5656.6  542.29
#Mann= 12 ,-1 , 0
  3723.7     .05       0  3780.4     .07       0    3791     .05       0
  3901.7     .07       0  4083.4     .05       0  4438.8     .07       0
  4639.2    .035       0  4806.5     .12       0  4996.9     .05       0
  5006.8     .12       0  5041.1     .05       0  5651.5    .035       0
Bank Sta=4996.9,5006.8
XS Rating Curve= 0 ,0
Exp/Cntr=0.3,0.1

Type RM Length L Ch R = 1 ,77282   ,477,477,477
BEGIN DESCRIPTION:
B19424
END DESCRIPTION:
XS GIS Cut Line= 3
      2328448.27      13782432.5       2327016.7      13782796.9
      2326079.86     13783232.79
#Sta/Elev= 30
  3789.4  537.67  4008.4  531.32  4109.5  529.06    4160   528.3  4464.6  526.56
  4805.7  521.94  4845.3  522.09  4935.2  516.75  4979.4  517.21  4995.2  512.55
  5005.4  512.13  5005.9  511.63  5015.5  512.13  5041.4  516.14  5134.2  520.82
  5270.3  522.06  5296.9  522.92  5302.4     525  5319.8  523.34  5325.3  525.75
  5348.2  524.28  5416.8   530.1  5446.1  534.86  5478.1  538.85  5586.6  539.94
  5764.8  538.44  5807.7  540.17  6011.4  543.53  6231.7  552.18  6299.9  555.48
#Mann= 14 ,-1 , 0
  3789.4     .07       0  4008.4     .05       0  4109.5     .07       0
    4160     .05       0  4464.6     .07       0  4805.7    .035       0
  4935.2     .12       0  5005.4     .05       0  5015.5     .12       0
  5446.1    .035       0  5586.6     .07       0  5807.7     .05       0
  6011.4     .12       0  6231.7     .07       0
Bank Sta=5005.4,5015.5
XS Rating Curve= 0 ,0
Exp/Cntr=0.3,0.1