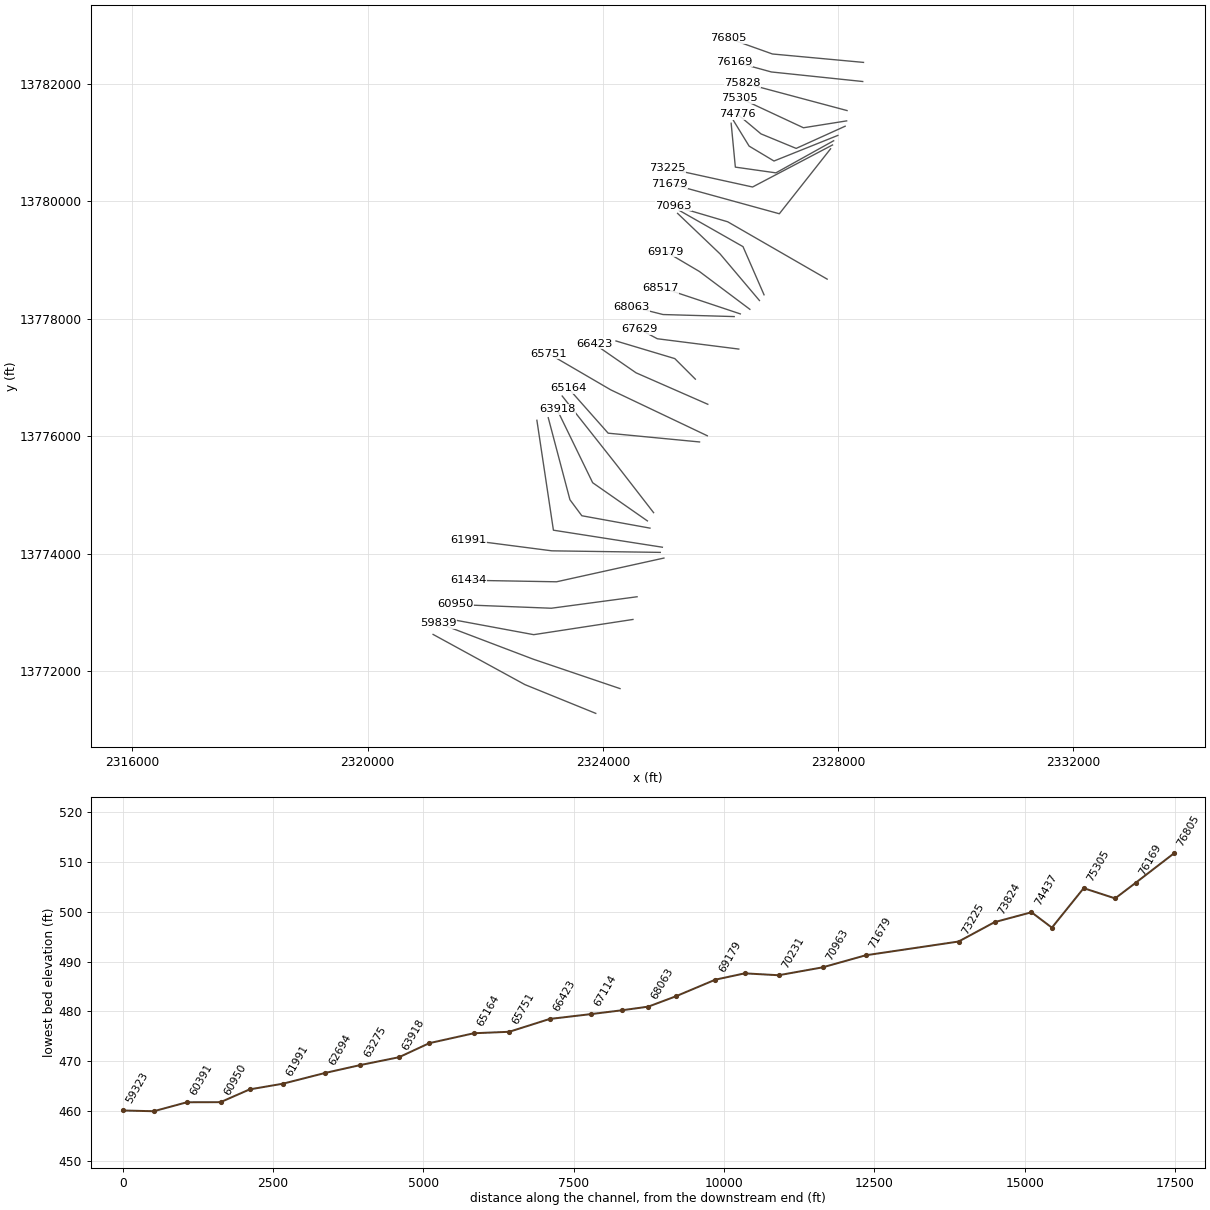
HEC-RAS study Mill Creek.prj: Mill Creek Base Level Engineering

--- Mill Creek.g01 (geometry) --- (continued)

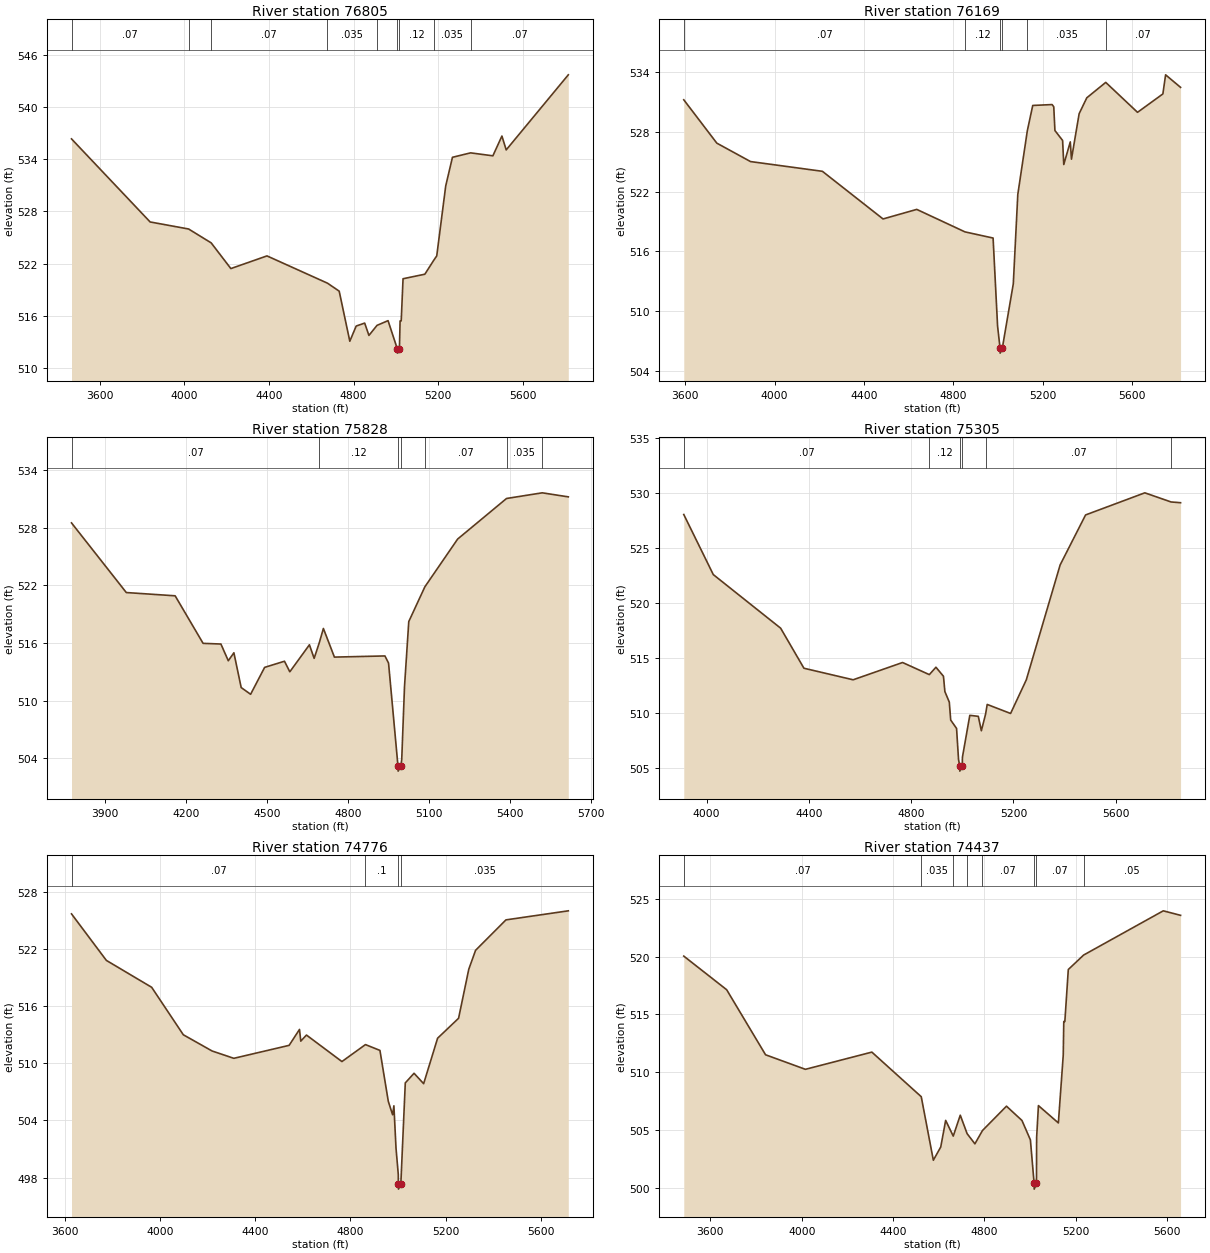
Type RM Length L Ch R = 1 ,76805   ,636,636,636
BEGIN DESCRIPTION:
B19423
END DESCRIPTION:
XS GIS Cut Line= 3
      2328435.23     13782367.43      2326886.56     13782510.59
      2326139.12     13782777.06
#Sta/Elev= 30
    3466  536.36  3837.8  526.79  4019.6  525.98  4126.4  524.38  4219.4  521.42
  4390.2  522.88    4676  519.74  4731.6  518.82  4781.8  513.05  4811.9   514.8
  4852.1  515.14  4872.2  513.72  4910.6  514.88  4962.6  515.42  5006.3  512.18
  5006.8  511.68  5016.4  512.18  5019.5  515.39  5024.8  515.39  5033.5  520.25
  5136.5  520.77  5179.1  522.39  5192.8  522.88  5235.3  530.95  5267.1  534.24
  5352.8  534.75  5458.2  534.41    5501  536.69  5521.2  535.09  5814.8  543.74
#Mann= 9 ,-1 , 0
    3466     .07       0  4019.6     .05       0  4126.4     .07       0
    4676    .035       0  4910.6     .12       0  5006.3     .05       0
  5016.4     .12       0  5179.1    .035       0  5352.8     .07       0
Bank Sta=5006.3,5016.4
XS Rating Curve= 0 ,0
Exp/Cntr=0.3,0.1

Type RM Length L Ch R = 1 ,76169   ,341,341,341
BEGIN DESCRIPTION:
B19422
END DESCRIPTION:
XS GIS Cut Line= 3
      2328422.22     13782042.07      2326867.04     13782204.75
      2326230.42     13782380.14
#Sta/Elev= 30
  3593.8  531.25  3741.8  526.89  3892.6  525.04  4214.4  524.06  4485.9  519.27
  4636.7  520.23  4852.6  517.97  4978.5  517.35  4998.6   508.5  5009.7  506.28
  5010.2  505.78  5019.8  506.28    5069  512.75  5089.1  521.73  5131.7  528.13
    5156  530.68  5242.6  530.77  5250.1  530.55  5255.3  528.16  5289.7  527.16
  5294.9  524.74  5324.1  527.02  5329.3  525.28  5363.7  529.85    5398  531.45
  5482.8     533  5625.1  529.99  5738.6  531.84  5750.8  533.76  5817.8   532.5
#Mann= 6 ,-1 , 0
  3593.8     .07       0  4852.6     .12       0  5009.7     .05       0
  5019.8     .12       0  5131.7    .035       0  5482.8     .07       0
Bank Sta=5009.7,5019.8
XS Rating Curve= 0 ,0
Exp/Cntr=0.3,0.1

Type RM Length L Ch R = 1 ,75828   ,523,523,523
BEGIN DESCRIPTION:
B19421
END DESCRIPTION:
XS GIS Cut Line= 2
      2328155.48     13781547.52      2326379.47     13782022.42
#Sta/Elev= 30
  3777.6   528.5  3980.4  521.25  4161.1  520.91  4264.6  515.96  4330.5  515.89
  4357.8  514.15  4378.5  514.98  4405.5  511.36  4440.4  510.66  4492.3  513.46
  4565.7   514.1  4585.5     513    4658  515.81  4675.5   514.4  4694.7  516.04
  4709.7  517.51  4750.5  514.53  4937.4  514.65  4950.8  513.91  4985.8  503.16
  4986.3  502.66  4995.9  503.16  4999.6  503.87  5009.9  511.47  5025.7  518.23
  5085.3  521.85  5206.6  526.82  5387.4  531.04  5519.6  531.63    5616  531.21
#Mann= 7 ,-1 , 0
  3777.6     .07       0  4694.7     .12       0  4985.8     .05       0
  4995.9     .12       0  5085.3     .07       0  5387.4    .035       0
  5519.6     .07       0
Bank Sta=4985.8,4995.9
XS Rating Curve= 0 ,0
Exp/Cntr=0.3,0.1

Type RM Length L Ch R = 1 ,75305   ,529,529,529
BEGIN DESCRIPTION:
B19420
END DESCRIPTION:
XS GIS Cut Line= 3
      2328148.96     13781371.83      2327413.64      13781254.7
      2326328.46     13781761.55
#Sta/Elev= 30
    3911  528.03  4026.4  522.57  4289.7   517.7  4380.8  514.06  4573.2  513.01
  4766.3  514.58    4871  513.48  4896.9  514.15  4926.3  513.33  4931.8  511.94
  4949.1  510.98  4954.6  509.35  4977.5  508.59  4985.2  505.77  4989.7  505.21
  4990.2  504.71    5000  505.21  5000.4  505.97  5029.3  509.78  5062.5  509.69
  5074.4  508.38    5091  509.89  5097.3  510.77  5188.7  509.95  5250.1     513
  5382.5  523.45  5481.9  527.99  5713.6     530  5816.1  529.17  5853.3   529.1
#Mann= 6 ,-1 , 0
    3911     .07       0    4871     .12       0  4989.7     .05       0
    5000     .12       0    5091     .07       0  5816.1    .035       0
Bank Sta=4989.7,5000
XS Rating Curve= 0 ,0
Exp/Cntr=0.3,0.1

Type RM Length L Ch R = 1 ,74776   ,339,339,339
BEGIN DESCRIPTION:
B19419
END DESCRIPTION:
XS GIS Cut Line= 4
      2328122.91     13781280.72        2327290.     13780903.31
      2326691.34     13781150.59      2326288.97     13781488.06
#Sta/Elev= 30
  3628.1  525.66  3774.6  520.78  3964.9  517.96  4097.9  512.98  4218.7  511.28
  4310.1  510.51  4542.5  511.87    4586  513.54  4591.4  512.31  4615.3  512.95
  4764.3  510.17  4863.2  511.95    4924  511.34  4959.1     506  4977.2  504.59
  4982.6  505.53  4991.5   501.1  5001.1  498.32  5001.4  497.29  5001.9  496.79
  5011.7  497.29  5030.5  507.93  5067.3  508.94  5107.6  507.85  5166.3  512.62
  5254.4  514.71  5297.3  519.86  5325.9  521.84  5453.4  525.03  5715.4  525.98
#Mann= 4 ,-1 , 0
  3628.1     .07       0  4863.2      .1       0  5001.4     .05       0
  5011.7    .035       0
Bank Sta=5001.4,5011.7
XS Rating Curve= 0 ,0
Exp/Cntr=0.3,0.1

Type RM Length L Ch R = 1 ,74437   ,613,613,613
BEGIN DESCRIPTION:
B19418
END DESCRIPTION:
XS GIS Cut Line= 4
      2327999.26     13781124.55      2326912.59     13780688.58
      2326489.62     13780942.36      2326222.81     13781378.37
#Sta/Elev= 30
  3483.6  520.05  3671.4  517.14  3841.7  511.51  4016.2  510.25  4307.1  511.74
  4523.4  507.88  4576.4  502.38  4608.8  503.53  4630.3  505.83  4663.5  504.47
  4694.3  506.28  4724.3  504.68  4758.4   503.8  4791.4  504.95  4896.6  507.06
  4964.5  505.82  5001.4  504.14  5017.6  500.38  5018.1  499.88  5027.9  500.38
  5028.6  504.34  5036.5  507.11  5123.8  505.61  5145.2  511.49  5147.5  514.39
  5152.2  514.39  5167.3  518.89  5234.3  520.14  5583.2  523.97  5658.9  523.58
#Mann= 8 ,-1 , 0
  3483.6     .07       0  4523.4    .035       0  4663.5      .1       0
  4724.3    .035       0  4791.4     .07       0  5017.6     .05       0
  5027.9     .07       0  5234.3     .05       0
Bank Sta=5017.6,5027.9
XS Rating Curve= 0 ,0
Exp/Cntr=0.3,0.1

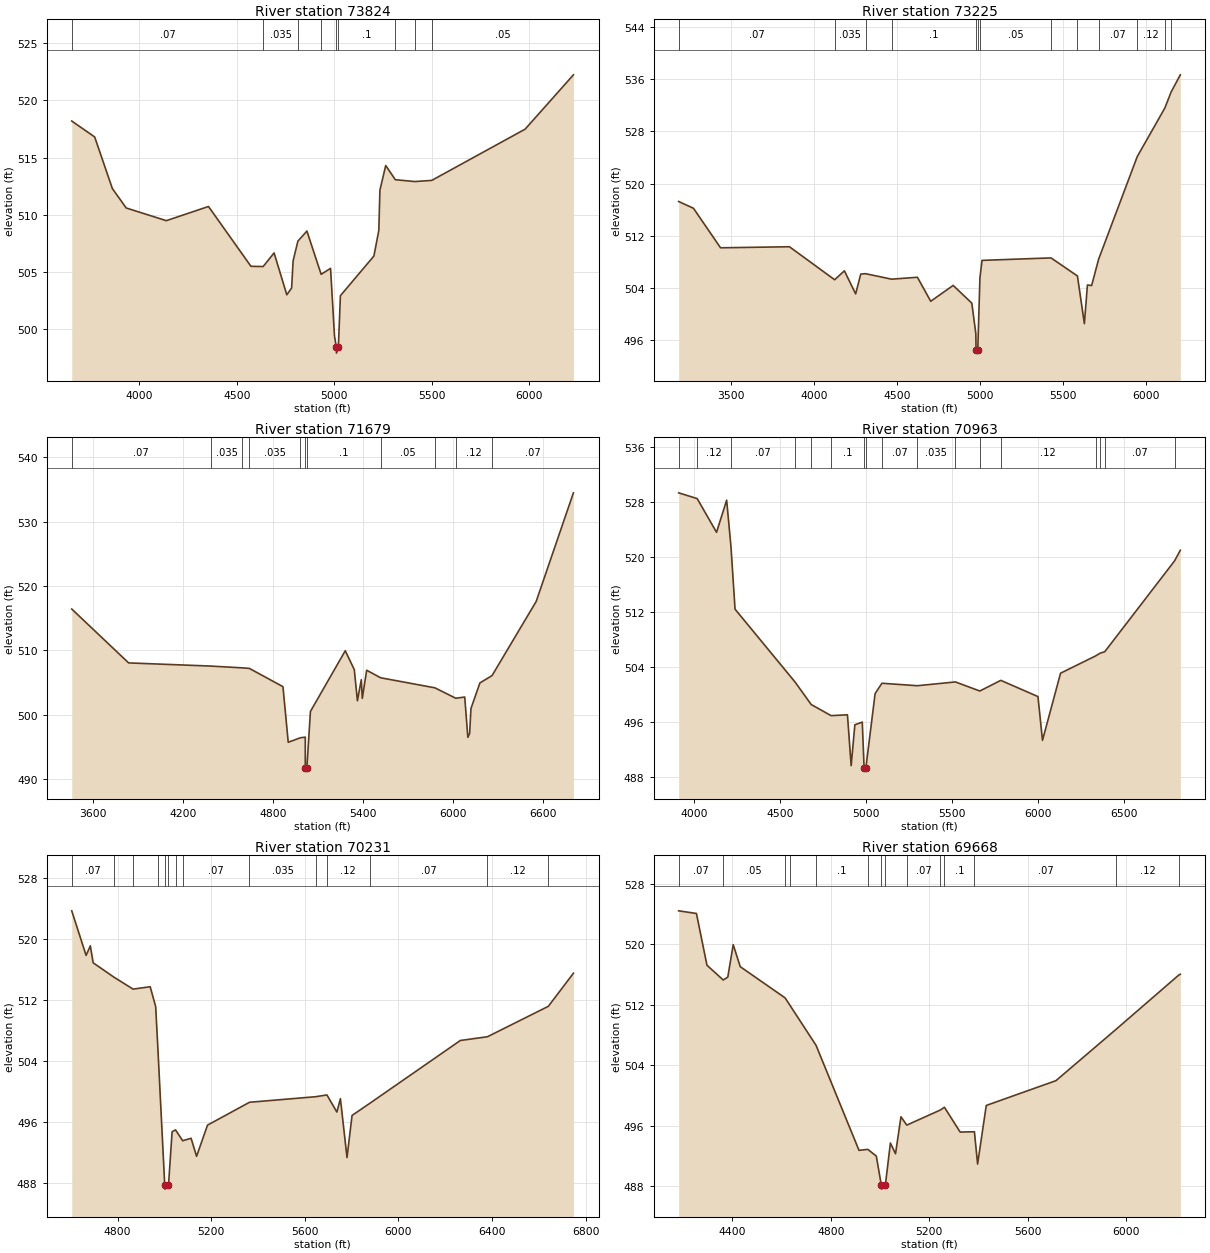
Type RM Length L Ch R = 1 ,73824   ,599,599,599
BEGIN DESCRIPTION:
B19417
END DESCRIPTION:
XS GIS Cut Line= 4
      2327927.68     13781033.44      2326945.12     13780486.85
      2326255.36     13780584.46      2326183.92     13781331.36
#Sta/Elev= 30
  3654.2  518.19  3771.7   516.8  3862.3  512.29  3933.2  510.59    4139  509.48
  4355.1  510.72  4572.7  505.49  4635.2  505.47  4691.3  506.66  4756.5     503
  4781.1  503.59  4788.8  505.97  4813.3  507.69  4859.5  508.57  4932.5  504.79
  4980.7  505.31  5000.9   499.4  5010.4   498.4  5010.9   497.9  5020.7   498.4
  5031.2  502.92  5202.9  506.39  5228.1  508.63  5233.7  512.15  5263.5   514.3
  5312.7  513.06  5412.5   512.9  5499.3     513    5978  517.48  6225.5  522.23
#Mann= 9 ,-1 , 0
  3654.2     .07       0  4635.2    .035       0  4813.3     .07       0
  4932.5      .1       0  5010.4     .05       0  5020.7      .1       0
  5312.7     .05       0  5412.5     .07       0  5499.3     .05       0
Bank Sta=5010.4,5020.7
XS Rating Curve= 0 ,0
Exp/Cntr=0.3,0.1

Type RM Length L Ch R = 1 ,73225   ,1546,1546,1546
BEGIN DESCRIPTION:
Mill Creek 90.0
END DESCRIPTION:
XS GIS Cut Line= 3
       2327908.2     13780961.89      2326548.18     13780246.09
      2325098.55     13780564.62
#Sta/Elev= 30
  3183.1  517.26  3272.3  516.22  3435.3  510.16  3850.3  510.32  4122.5  505.26
  4181.2  506.63    4249  503.09  4279.7  506.13  4308.5  506.19  4465.5  505.35
    4621  505.64    4701  501.96  4836.2  504.39  4948.5  501.67  4972.6  497.03
    4974  494.51  4974.5  494.01  4984.4  494.51  4997.4  505.55  5009.9  508.23
  5425.5  508.61  5584.6  505.84  5626.4  498.53  5644.7  504.45  5670.2  504.38
    5712   508.4  5944.7  524.14    6111  531.59  6148.8  534.05  6204.2  536.68
#Mann= 13 ,-1 , 0
  3183.1     .07       0  4122.5    .035       0  4308.5     .07       0
  4465.5      .1       0    4974     .05       0  4984.4      .1       0
  4997.4     .05       0  5425.5     .07       0  5584.6     .12       0
    5712     .07       0  5944.7     .12       0    6111     .07       0
  6148.8     .12       0
Bank Sta=4974,4984.4
XS Rating Curve= 0 ,0
Exp/Cntr=0.3,0.1

Type RM Length L Ch R = 1 ,71679   ,716,716,716
BEGIN DESCRIPTION:
Mill Creek 89.0
END DESCRIPTION:
XS GIS Cut Line= 3
      2327875.63     13780896.78      2327003.69     13779790.59
      2325136.17     13780304.64
#Sta/Elev= 30
  3457.5  516.43  3836.8  508.06  4383.2  507.57  4595.8  507.29  4641.8  507.21
    4866  504.37  4901.2  495.73  4982.1  496.43  5014.8  496.53    5015  491.75
  5015.5  491.25  5025.4  491.75  5049.2  500.52  5281.5  509.95  5341.8  507.01
  5362.5  502.19  5388.4  505.45  5395.1  502.56  5424.3  506.92  5517.6  505.75
  5879.4  504.19  6018.6  502.57  6078.2  502.76  6098.9   496.5  6110.9   497.1
  6119.7  500.98  6179.7  504.96  6260.4  506.09  6554.8  517.61    6803  534.48
#Mann= 11 ,-1 , 0
  3457.5     .07       0  4383.2    .035       0  4595.8     .07       0
  4641.8    .035       0  4982.1      .1       0    5015     .05       0
  5025.4      .1       0  5517.6     .05       0  5879.4     .07       0
  6018.6     .12       0  6260.4     .07       0
Bank Sta=5015,5025.4
XS Rating Curve= 0 ,0
Exp/Cntr=0.3,0.1

Type RM Length L Ch R = 1 ,70963   ,732,732,732
BEGIN DESCRIPTION:
Mill Creek 88.0
END DESCRIPTION:
XS GIS Cut Line= 3
      2327817.08     13778677.86      2326125.22     13779653.93
      2325201.22     13779927.23
#Sta/Elev= 30
  3912.4   529.3  4020.2  528.46  4132.6  523.56  4191.5  528.23  4216.4  521.52
  4240.3  512.38  4589.4  501.78  4682.9  498.52  4798.6   496.9  4893.8  497.02
  4915.3  489.63  4936.9  495.57    4980  495.96  4990.5  489.33    4991  488.83
    5001  489.33  5054.6   500.1  5094.2  501.61  5300.2  501.25  5521.5   501.8
  5663.3  500.48  5785.5  502.03  6001.4  499.67  6027.8   493.3  6132.8  503.07
  6337.2  505.59  6362.6  505.98  6389.7  506.19  6795.6   519.4  6829.2  520.95
#Mann= 17 ,-1 , 0
  3912.4     .05       0  4020.2     .12       0  4216.4     .07       0
  4589.4     .12       0  4682.9     .07       0  4798.6      .1       0
  4990.5     .05       0    5001      .1       0  5094.2     .07       0
  5300.2    .035       0  5521.5     .07       0  5663.3     .05       0
  5785.5     .12       0  6337.2     .07       0  6362.6     .12       0
  6389.7     .07       0  6795.6     .12       0
Bank Sta=4990.5,5001
XS Rating Curve= 0 ,0
Exp/Cntr=0.3,0.1

Type RM Length L Ch R = 1 ,70231   ,563,563,563
BEGIN DESCRIPTION:
Mill Creek 87.0
END DESCRIPTION:
XS GIS Cut Line= 3
      2326743.41     13778411.03       2326385.5     13779230.97
      2325299.39     13779848.82
#Sta/Elev= 30
  4603.7  523.65  4665.1  517.82  4683.1  519.07  4695.3  516.85  4783.2  514.99
  4865.8  513.41    4939  513.72  4962.4  511.13  4971.9   505.6  5001.2  487.75
  5001.7  487.25  5017.2  487.75  5032.6  494.75  5047.2     495  5077.9  493.58
  5113.8   493.9  5137.2  491.54    5184  495.62  5363.4  498.61  5647.1  499.34
  5694.3  499.57  5736.9  497.33    5752  499.08  5780.2  491.38  5801.8  496.89
  5877.5  498.47  6264.5  506.69  6380.3  507.18  6640.7  511.16  6747.9  515.49
#Mann= 14 ,-1 , 0
  4603.7     .07       0  4783.2     .05       0  4865.8     .12       0
  4971.9      .1       0  5001.2     .05       0  5017.2      .1       0
  5047.2     .12       0  5077.9     .07       0  5363.4    .035       0
  5647.1     .07       0  5694.3     .12       0  5877.5     .07       0
  6380.3     .12       0  6640.7     .07       0
Bank Sta=5001.2,5017.2
XS Rating Curve= 0 ,0
Exp/Cntr=0.3,0.1

Type RM Length L Ch R = 1 ,69668   ,489,489,489
BEGIN DESCRIPTION:
Mill Creek 86.0
END DESCRIPTION:
XS GIS Cut Line= 3
      2326665.34     13778313.43      2325995.07     13779107.33
      2325272.74     13779797.13
#Sta/Elev= 30
  4181.8  524.45    4254   524.1  4296.8  517.25  4362.9   515.3  4381.4  515.68
  4403.4  519.97    4432  517.06  4614.3  512.93  4633.9  511.95    4740  506.65
  4914.4  492.76  4950.2  492.89  4984.7     492  5005.2  488.13  5005.7  487.63
  5021.3  488.13  5041.9  493.73  5062.7  492.31  5084.8   497.2  5108.4   496.1
    5245   498.1  5261.3  498.46  5325.3  495.18  5383.2  495.22  5396.1  490.95
  5431.3   498.7  5714.4  501.98  5960.3  508.82  6212.8  515.94  6219.6  516.06
#Mann= 14 ,-1 , 0
  4181.8     .07       0  4362.9     .05       0  4614.3      .1       0
  4633.9     .05       0    4740      .1       0  4950.2    .035       0
  5005.2    .035       0  5021.3    .035       0  5108.4     .07       0
    5245     .12       0  5261.3      .1       0  5383.2     .07       0
  5960.3     .12       0  6212.8     .07       0
Bank Sta=5005.2,5021.3
XS Rating Curve= 0 ,0
Exp/Cntr=0.3,0.1

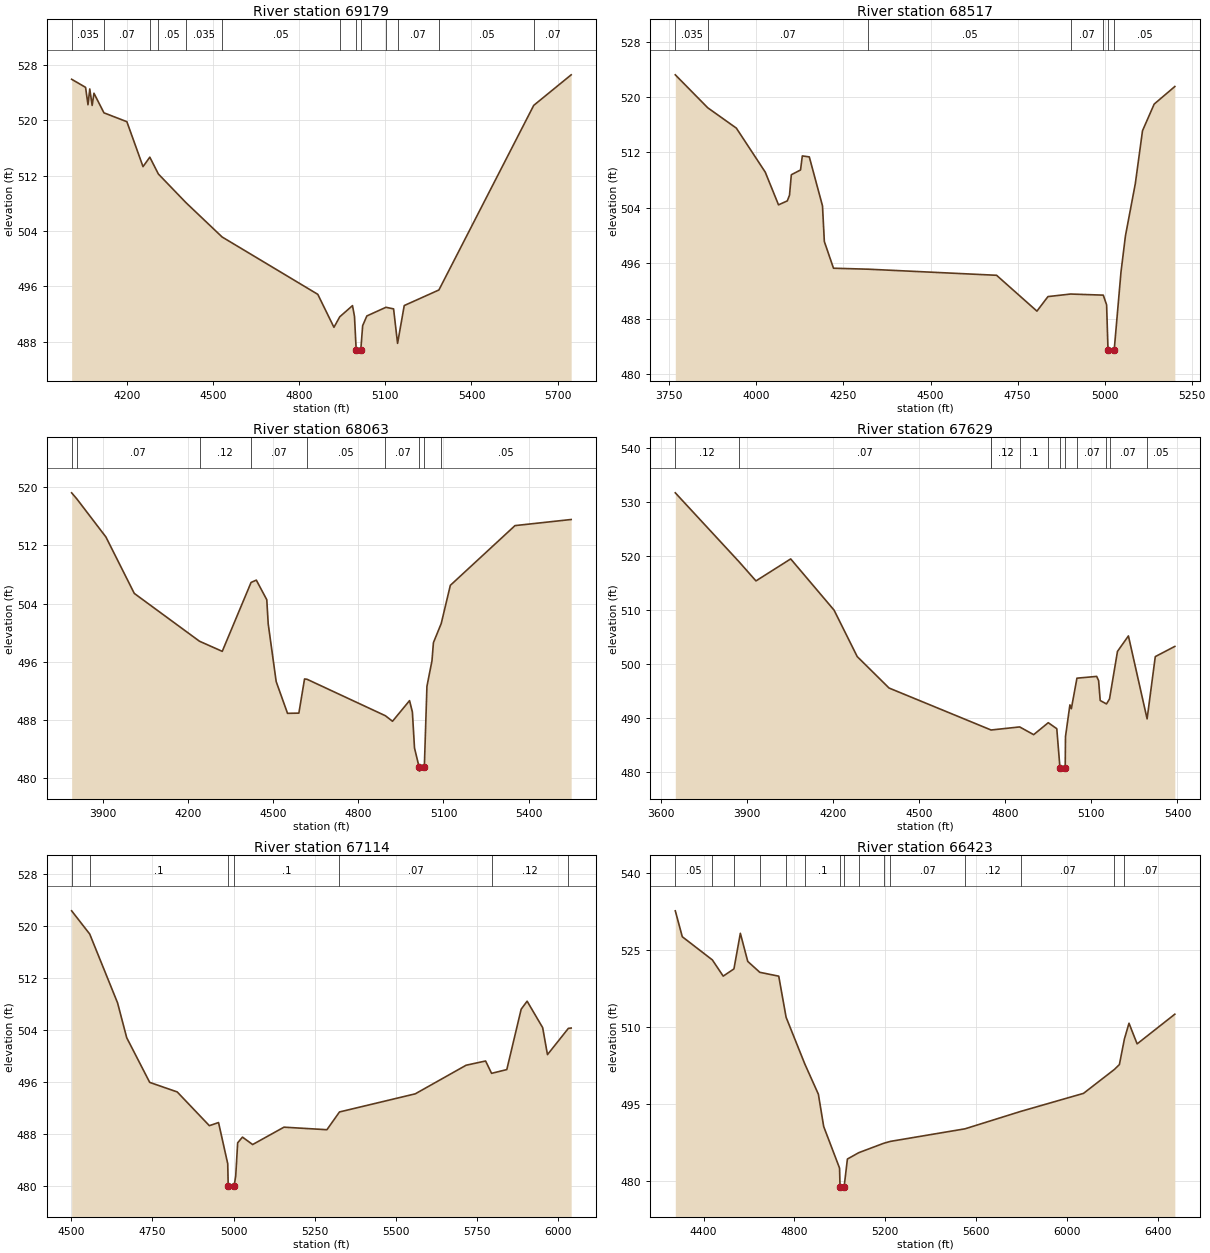
Type RM Length L Ch R = 1 ,69179   ,662,662,662
BEGIN DESCRIPTION:
Mill Creek 84.0
END DESCRIPTION:
XS GIS Cut Line= 3
      2326502.66     13778163.77      2325643.69       13778808.
      2325071.01      13779146.4
#Sta/Elev= 30
  4008.2  525.91  4056.7  524.74  4065.1  522.23  4071.3  524.51  4079.6  522.13
  4085.9  523.89  4120.7  521.06  4200.5  519.78  4256.7  513.29  4280.3  514.66
  4310.1  512.23  4406.2  508.09  4532.1  503.13  4865.1  494.85  4921.3  490.09
  4941.6  491.61  4985.9  493.22  4992.8  491.67  4998.7  486.86  4999.2  486.36
  5014.8  486.86  5021.3  490.33  5035.9  491.73  5102.4  492.98  5128.9  492.75
  5142.8  487.77    5166  493.23  5286.7  495.48  5616.8  522.14  5747.1  526.55
#Mann= 13 ,-1 , 0
  4008.2    .035       0  4120.7     .07       0  4280.3    .035       0
  4310.1     .05       0  4406.2    .035       0  4532.1     .05       0
  4941.6    .035       0  4998.7    .035       0  5014.8    .035       0
  5102.4      .1       0  5142.8     .07       0  5286.7     .05       0
  5616.8     .07       0
Bank Sta=4998.7,5014.8
XS Rating Curve= 0 ,0
Exp/Cntr=0.3,0.1

Type RM Length L Ch R = 1 ,68517   ,454,454,454
BEGIN DESCRIPTION:
Mill Creek 83.0
END DESCRIPTION:
XS GIS Cut Line= 3
      2326339.99     13778085.69        2325175.       13778475.
      2324974.97     13778525.01
#Sta/Elev= 30
    3767  523.22  3860.1  518.46  3942.3  515.52  4025.3  509.16  4063.4  504.43
  4088.6     505    4095  505.83  4100.2  508.78  4126.6  509.47  4131.8   511.5
  4151.8  511.36  4189.7  504.28    4195  499.13  4221.3  495.27  4320.8  495.13
  4689.6  494.25  4805.5  489.07  4837.2  491.17  4902.3  491.54    4996  491.38
  5005.6  489.98  5009.6   483.5  5010.1     483  5027.5   483.5  5046.9  494.72
  5059.7  499.95  5088.1  507.51  5108.7  515.14  5142.2  518.99  5201.5  521.53
#Mann= 7 ,-1 , 0
    3767    .035       0  3860.1     .07       0  4320.8     .05       0
  4902.3     .07       0    4996     .05       0  5009.6     .05       0
  5027.5     .05       0
Bank Sta=5009.6,5027.5
XS Rating Curve= 0 ,0
Exp/Cntr=0.3,0.1

Type RM Length L Ch R = 1 ,68063   ,434,434,434
BEGIN DESCRIPTION:
Mill Creek 82.0
END DESCRIPTION:
XS GIS Cut Line= 3
      2326235.81     13778040.16        2325025.       13778075.
      2324491.88     13778209.35
#Sta/Elev= 30
    3789  519.24  3806.8  518.43  3909.9  513.16  4009.9   505.4  4239.8  498.82
    4320  497.43  4421.6  506.91  4440.1  507.23    4477  504.53    4482  501.22
  4510.1  493.27  4550.1   488.9  4590.1  488.93  4610.1  493.63  4618.8  493.59
  4895.2  488.57  4920.3  487.81  4980.3  490.65  4990.3  489.09  4997.8  484.13
  5014.4  481.45  5014.9  480.95  5032.4  481.45  5041.6  492.61  5059.4  496.14
  5064.5  498.63    5092  501.26  5124.1  506.51  5352.1  514.73  5550.1  515.57
#Mann= 9 ,-1 , 0
    3789    .035       0  3806.8     .07       0  4239.8     .12       0
  4421.6     .07       0  4618.8     .05       0  4895.2     .07       0
  5014.4     .05       0  5032.4     .07       0    5092     .05       0
Bank Sta=5014.4,5032.4
XS Rating Curve= 0 ,0
Exp/Cntr=0.3,0.1

Type RM Length L Ch R = 1 ,67629   ,515,515,515
BEGIN DESCRIPTION:
Mill Creek 81.0
END DESCRIPTION:
XS GIS Cut Line= 3
      2326313.89     13777487.05       2324927.9     13777662.74
      2324625.01       13777825.
#Sta/Elev= 30
  3650.2  531.73  3871.9     519  3931.3  515.43  4052.3   519.5  4203.5  510.02
  4284.1  501.43    4395  495.61  4750.6  487.84  4750.7  487.84  4850.2  488.41
    4899  486.98  4949.9  489.19  4979.6  488.08  4990.8  480.73  4991.3  480.23
  5008.9  480.73  5009.9  486.62  5025.3  492.49  5030.3  491.78  5049.8  497.43
  5118.6  497.76  5125.3  496.98  5130.9   493.3  5152.7  492.66  5163.3  493.59
  5191.1  502.39  5229.2  505.25  5294.3   489.9  5322.8  501.42  5390.9  503.31
#Mann= 12 ,-1 , 0
  3650.2     .12       0  3871.9     .07       0  4750.6      .1       0
  4750.7     .12       0  4850.2      .1       0  4949.9     .12       0
  4990.8     .05       0  5008.9     .12       0  5049.8     .07       0
  5152.7     .12       0  5163.3     .07       0  5294.3     .05       0
Bank Sta=4990.8,5008.9
XS Rating Curve= 0 ,0
Exp/Cntr=0.3,0.1

Type RM Length L Ch R = 1 ,67114   ,691,691,691
BEGIN DESCRIPTION:
Mill Creek 80.0
END DESCRIPTION:
XS GIS Cut Line= 3
      2325575.03     13776974.97        2325225.       13777325.
      2324225.04     13777624.99
#Sta/Elev= 30
  4501.3  522.27    4557   518.7  4642.8  508.11    4671  502.75  4741.8  495.88
  4826.6  494.41  4925.6  489.22  4953.9   489.7  4982.2  483.37  4983.7  479.96
  4984.2  479.46  5001.9  479.96  5006.8  481.47  5012.8  486.58  5027.6  487.46
    5059  486.32  5155.5  488.99  5287.8   488.6  5326.5  491.33  5560.1  494.12
  5716.7  498.52  5776.7  499.17  5795.1  497.27    5842  497.85  5886.3  507.14
  5904.6  508.37  5952.5   504.3  5967.3  500.15  6031.7  504.19  6040.3  504.24
#Mann= 7 ,-1 , 0
  4501.3     .12       0    4557      .1       0  4983.7     .05       0
  5001.9      .1       0  5326.5     .07       0  5795.1     .12       0
  6031.7     .07       0
Bank Sta=4983.7,5001.9
XS Rating Curve= 0 ,0
Exp/Cntr=0.3,0.1

Type RM Length L Ch R = 1 ,66423   ,672,672,672
BEGIN DESCRIPTION:
B19416
END DESCRIPTION:
XS GIS Cut Line= 3
      2325787.02     13776547.08      2324565.94     13777082.95
      2323854.34     13777574.92
#Sta/Elev= 30
  4275.8  532.57  4306.6  527.53  4438.9  523.03  4486.6  519.88  4533.9  521.28
  4562.1   528.2  4594.7  522.74  4647.7  520.62  4731.1  519.87  4763.5  511.88
  4845.8  502.81  4905.6  496.92  4928.9  490.65  4998.8  482.56  5000.8  478.98
  5001.3  478.48    5019  478.98  5033.3  484.33  5083.1  485.56  5192.4  487.38
  5222.6  487.76  5550.8   490.2  5797.2   493.6  6072.4  497.09  6208.7  501.75
  6230.4  502.69  6252.5  507.66  6272.7  510.72  6308.5  506.71  6474.4  512.48
#Mann= 15 ,-1 , 0
  4275.8     .05       0  4438.9     .07       0  4533.9     .05       0
  4647.7     .07       0  4763.5     .12       0  4845.8      .1       0
  5000.8     .05       0    5019      .1       0  5083.1     .07       0
  5192.4     .12       0  5222.6     .07       0  5550.8     .12       0
  5797.2     .07       0  6208.7     .12       0  6252.5     .07       0
Bank Sta=5000.8,5019
XS Rating Curve= 0 ,0
Exp/Cntr=0.3,0.1

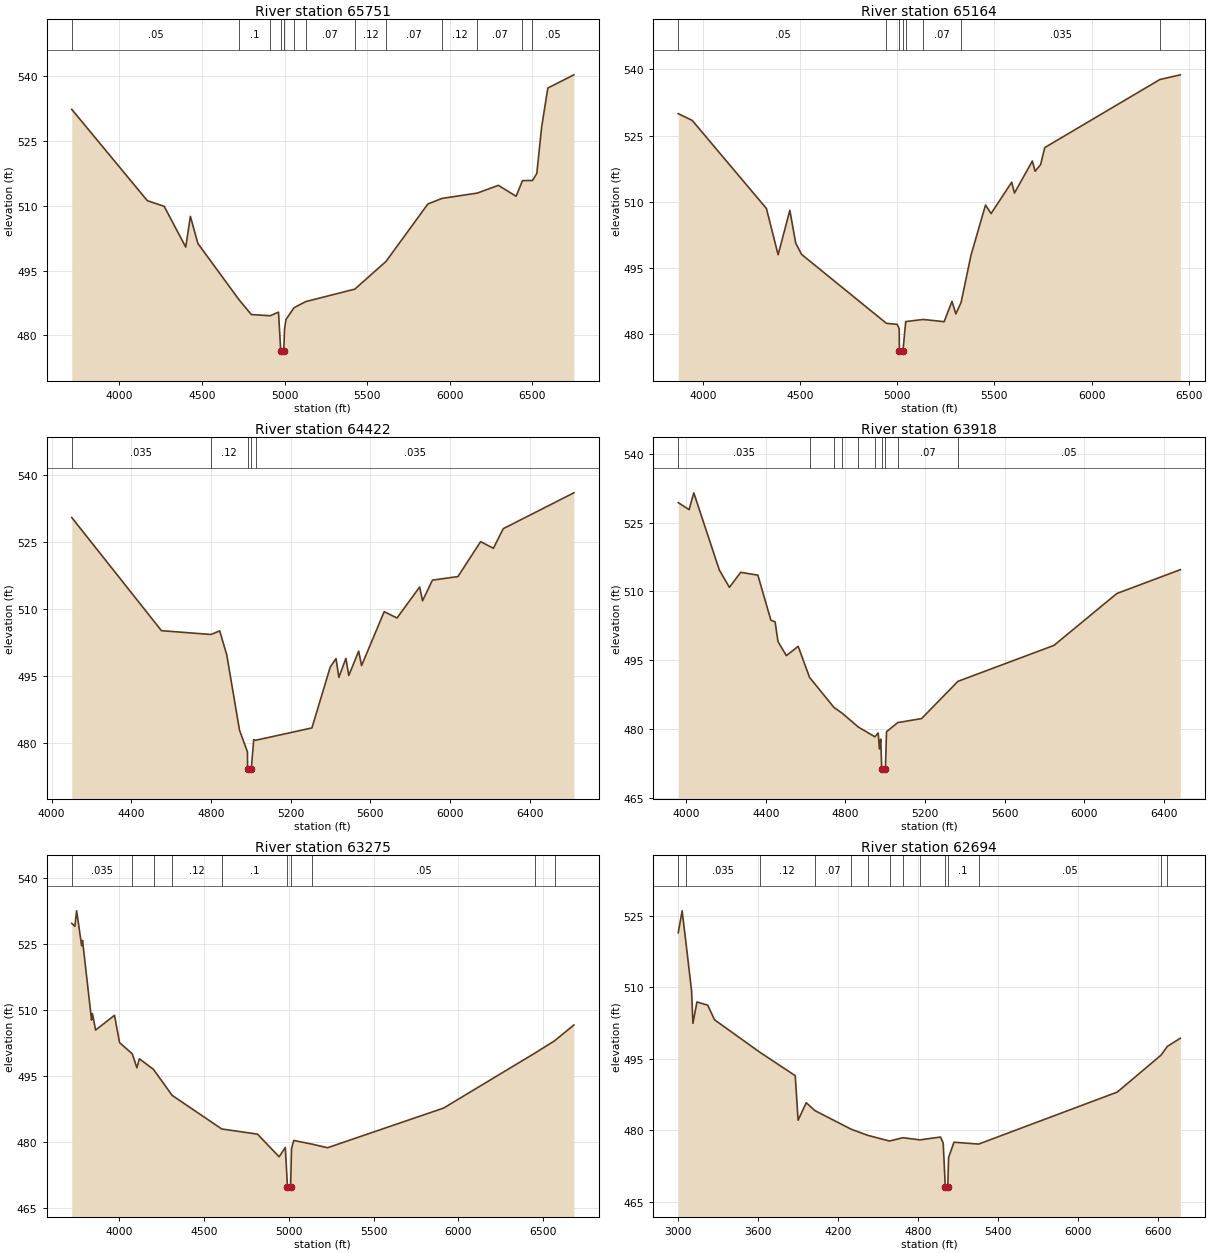
Type RM Length L Ch R = 1 ,65751   ,587,587,587
BEGIN DESCRIPTION:
B19415
END DESCRIPTION:
XS GIS Cut Line= 3
      2325778.23     13776011.21      2324135.49     13776793.05
      2323081.34     13777407.97
#Sta/Elev= 30
  3711.7  532.29    4169  511.18    4271  509.87  4401.7  500.44  4429.9  507.54
  4475.3  501.27  4725.4  488.21  4798.8  484.84  4912.4  484.55  4963.3  485.39
  4976.9  476.41  4977.4  475.91  4995.1  476.41    5000  481.53  5008.7   483.7
  5057.2  486.41  5128.2  487.83  5425.3  490.71  5614.2  497.12  5867.7  510.41
  5953.5   511.7  6167.4  512.93  6294.4  514.72  6401.9  512.19  6440.4  515.81
  6500.7  515.84  6527.2  517.46  6556.6  528.26  6593.8  537.22  6751.4  540.28
#Mann= 13 ,-1 , 0
  3711.7     .05       0  4725.4      .1       0  4912.4     .12       0
  4976.9     .05       0  4995.1     .12       0  5057.2      .1       0
  5128.2     .07       0  5425.3     .12       0  5614.2     .07       0
  5953.5     .12       0  6167.4     .07       0  6440.4    .035       0
  6500.7     .05       0
Bank Sta=4976.9,4995.1
XS Rating Curve= 0 ,0
Exp/Cntr=0.3,0.1

Type RM Length L Ch R = 1 ,65164   ,742,742,742
BEGIN DESCRIPTION:
B19414
END DESCRIPTION:
XS GIS Cut Line= 3
      2325646.47      13775905.8      2324091.56     13776055.14
      2323415.13     13776819.42
#Sta/Elev= 30
  3873.5  529.97  3945.3  528.44  4327.1  508.45  4387.3  497.94  4447.6  508.04
  4477.7  500.61  4507.9  498.03  4944.5  482.38  5000.1  482.15  5010.2  481.11
  5011.1  476.12  5011.6  475.62  5029.4  476.12  5043.7  482.78  5133.2  483.26
  5241.2  482.76  5281.8  487.37  5301.5  484.52  5328.8  487.16  5379.3  497.82
  5454.2  509.23  5482.7  507.29  5588.9  514.41  5603.1  511.95  5695.1  519.22
  5709.3  516.89  5737.8  518.43  5758.7  522.26  6351.3  537.72  6456.2  538.78
#Mann= 8 ,-1 , 0
  3873.5     .05       0  4944.5      .1       0  5011.1     .05       0
  5029.4      .1       0  5043.7     .05       0  5133.2     .07       0
  5328.8    .035       0  6351.3     .07       0
Bank Sta=5011.1,5029.4
XS Rating Curve= 0 ,0
Exp/Cntr=0.3,0.1

Type RM Length L Ch R = 1 ,64422   ,504,504,504
BEGIN DESCRIPTION:
B19413
END DESCRIPTION:
XS GIS Cut Line= 3
      2324864.59     13774702.33      2324232.12     13775519.27
      2323309.88     13776687.45
#Sta/Elev= 30
  4100.9  530.38  4551.3  505.06  4800.2  504.21  4843.8  505.01  4879.1  499.68
  4943.4  482.79  4983.2  477.94  4983.9  474.13  4984.4  473.63  5002.4  474.13
  5014.8  480.68  5024.8  480.54    5307   483.3  5399.1  496.94    5428  498.82
  5442.4  494.61  5477.7  498.87  5492.1  495.03  5541.8  500.48  5556.3  497.24
  5670.1  509.32  5734.2   507.9    5848  514.83  5862.5  511.74  5912.1  516.37
  6040.4  517.17  6154.2  524.99  6218.3   523.5    6268  527.89  6622.4  535.91
#Mann= 5 ,-1 , 0
  4100.9    .035       0  4800.2     .12       0  4983.9     .05       0
  5002.4     .12       0  5024.8    .035       0
Bank Sta=4983.9,5002.4
XS Rating Curve= 0 ,0
Exp/Cntr=0.3,0.1

Type RM Length L Ch R = 1 ,63918   ,643,643,643
BEGIN DESCRIPTION:
B19412
END DESCRIPTION:
XS GIS Cut Line= 3
      2324759.19     13774561.75      2323828.02     13775211.81
      2323221.89     13776459.21
#Sta/Elev= 30
  3960.1  529.36  4014.8  527.82  4038.3  531.49  4166.6  514.65  4217.2  510.88
  4273.9  514.16  4360.2  513.54  4425.6  503.71  4446.6  503.37  4461.4  499.06
  4503.3  495.99  4562.6  498.02    4620  491.24  4742.9  484.68  4783.2  483.46
  4865.6   480.4  4948.2   478.3  4964.7  479.13  4970.8  475.64  4977.5  477.78
  4982.5  471.31    4983  470.81    5001  471.31  5006.6  479.41  5062.9  481.39
  5182.7  482.27  5365.1  490.38    5848  498.23  6163.8  509.54  6482.6  514.73
#Mann= 10 ,-1 , 0
  3960.1    .035       0    4620     .12       0  4742.9      .1       0
  4783.2     .12       0  4865.6      .1       0  4948.2     .12       0
  4982.5     .05       0    5001     .12       0  5062.9     .07       0
  5365.1     .05       0
Bank Sta=4982.5,5001
XS Rating Curve= 0 ,0
Exp/Cntr=0.3,0.1

Type RM Length L Ch R = 1 ,63275   ,581,581,581
BEGIN DESCRIPTION:
B19411
END DESCRIPTION:
XS GIS Cut Line= 4
      2324803.09     13774438.76      2323643.54     13774649.59
       2323441.5     13774921.92      2323072.55     13776318.65
#Sta/Elev= 30
  3718.7  529.71  3737.1  529.03  3747.3  532.56  3777.1   524.6  3782.2  525.84
  3835.5  507.69  3840.6  509.19  3859.1  505.43  3970.9  508.79  4000.7  502.58
  4075.7  500.03    4103  496.84  4117.6   498.9  4201.1  496.47  4311.1  490.57
  4603.6  482.93  4814.5  481.75  4942.2   476.6  4978.7  478.72  4991.4  469.74
  4991.9  469.24  5009.9  469.74  5015.3  478.46  5028.5  480.31  5134.5  479.49
    5228  478.66  5912.4  487.68    6454  500.25  6567.2  502.99    6681  506.58
#Mann= 10 ,-1 , 0
  3718.7    .035       0  4075.7     .12       0  4201.1     .07       0
  4311.1     .12       0  4603.6      .1       0  4991.4     .05       0
  5009.9      .1       0  5134.5     .05       0    6454     .07       0
  6567.2     .05       0
Bank Sta=4991.4,5009.9
XS Rating Curve= 0 ,0
Exp/Cntr=0.3,0.1

Type RM Length L Ch R = 1 ,62694   ,703,703,703
BEGIN DESCRIPTION:
Mill Creek 72.0
END DESCRIPTION:
XS GIS Cut Line= 3
      2325013.92     13774113.73      2323160.39     13774403.62
      2322879.28     13776274.76
#Sta/Elev= 30
  3001.4  521.44  3030.7  526.05  3058.8  519.49  3101.5  509.26  3111.7  502.45
    3142  506.94    3223  506.25  3273.6   503.2  3613.1   496.4  3879.6  491.47
  3901.1  482.12  3961.9   485.8  4026.8  484.15  4299.1  480.24  4424.2  478.95
  4587.3  477.76  4687.4  478.45  4815.4     478  4969.9   478.6  4990.1  477.31
  5005.8  468.17  5006.3  467.67  5024.3  468.17  5030.5  474.31    5071  477.51
  5256.1  477.12  6296.6  488.03  6624.6  495.77  6671.8   497.6  6769.6  499.32
#Mann= 14 ,-1 , 0
  3001.4     .05       0  3058.8    .035       0  3613.1     .12       0
  4026.8     .07       0  4299.1     .12       0  4424.2     .07       0
  4587.3      .1       0  4687.4     .12       0  4815.4      .1       0
  5005.8     .05       0  5024.3      .1       0  5256.1     .05       0
  6624.6     .07       0  6671.8     .05       0
Bank Sta=5005.8,5024.3
XS Rating Curve= 0 ,0
Exp/Cntr=0.3,0.1

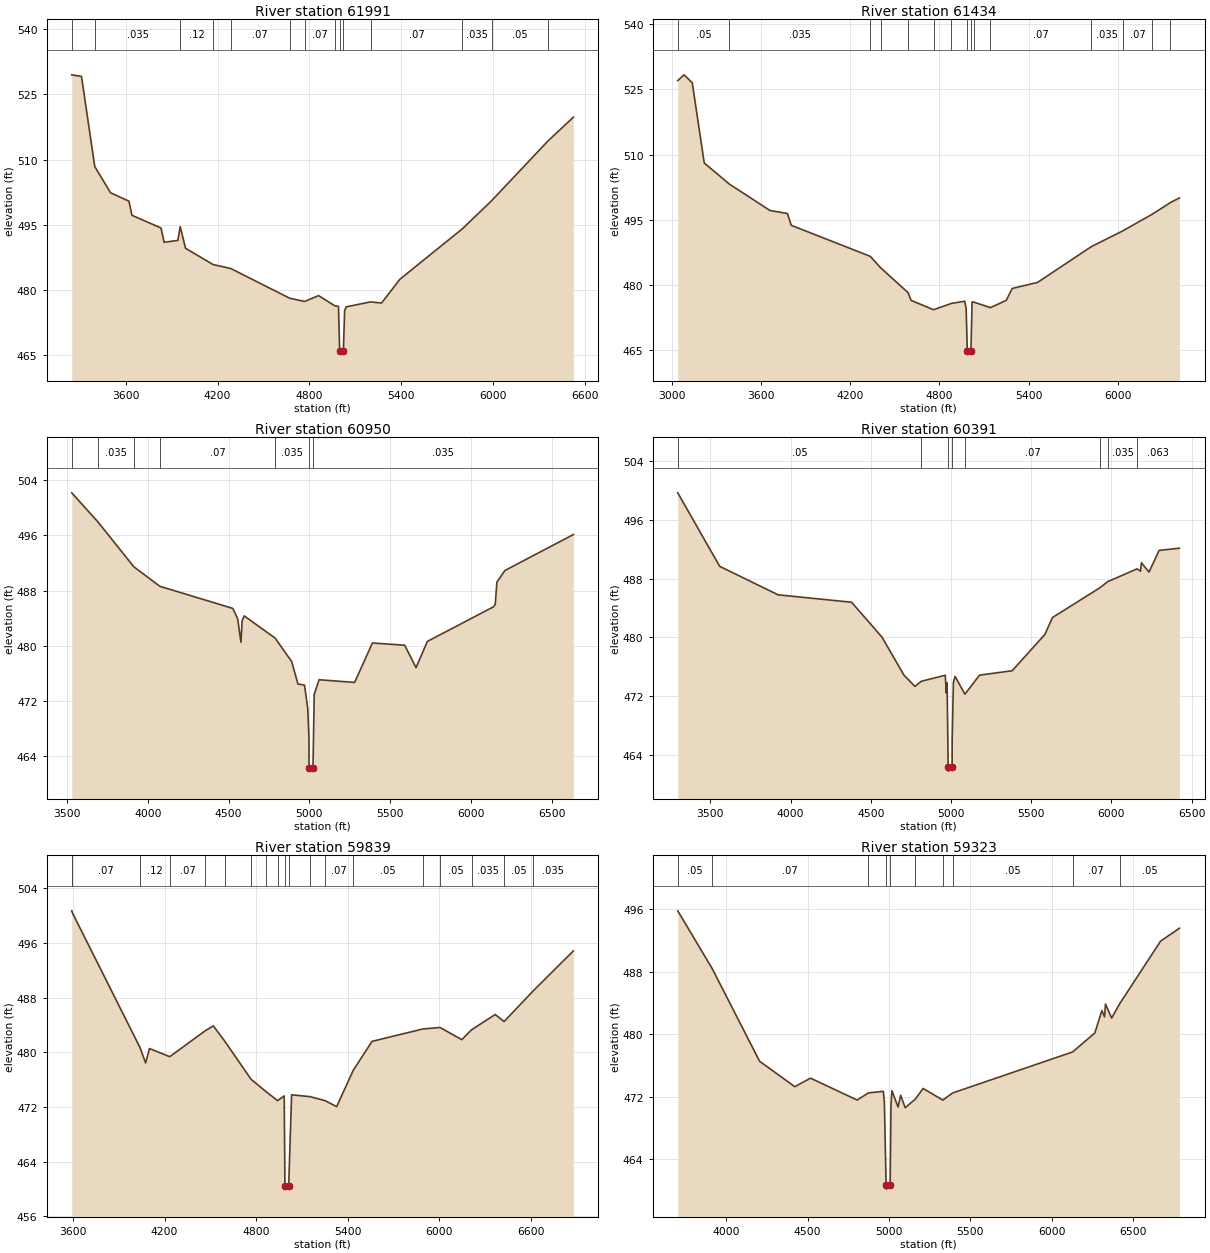
Type RM Length L Ch R = 1 ,61991   ,557,557,557
BEGIN DESCRIPTION:
Mill Creek 71.0
END DESCRIPTION:
XS GIS Cut Line= 3
      2324978.81     13774025.88      2323134.03     13774052.23
       2321710.9     13774236.71
#Sta/Elev= 30
  3246.5  529.52  3310.3  529.15    3397  508.42  3500.3  502.39  3620.3  500.47
  3640.3  497.21  3830.4  494.29  3850.4     491  3940.4  491.44  3955.6   494.6
  3990.4  489.63  4170.6  485.88  4285.7  484.98  4670.7  478.15  4769.3  477.39
  4860.5  478.74  4966.3   476.4  4990.5  476.26  4998.3  466.01  4998.8  465.51
  5022.6  466.01  5030.5  475.25  5040.5  476.15  5199.9  477.29    5272  477.03
    5393  482.53    5801  494.12  5991.6  500.56  6360.1  514.31  6526.5  519.78
#Mann= 14 ,-1 , 0
  3246.5     .05       0    3397    .035       0  3955.6     .12       0
  4170.6    .035       0  4285.7     .07       0  4670.7    .035       0
  4769.3     .07       0  4966.3      .1       0  4998.3     .05       0
  5022.6      .1       0  5199.9     .07       0    5801    .035       0
  5991.6     .05       0  6360.1    .035       0
Bank Sta=4998.3,5022.6
XS Rating Curve= 0 ,0
Exp/Cntr=0.3,0.1

Type RM Length L Ch R = 1 ,61434   ,484,484,484
BEGIN DESCRIPTION:
Mill Creek 70.0
END DESCRIPTION:
XS GIS Cut Line= 3
      2325040.34     13773929.25      2323213.09     13773525.15
      2321710.92      13773551.5
#Sta/Elev= 30
  3040.1  527.03  3082.2  528.35  3137.7  526.52  3218.2  508.08  3387.8  503.21
  3660.1  497.16  3777.7  496.46  3803.4  493.75  4334.9  486.61  4403.6  484.02
  4588.4  478.29  4609.3  476.49  4760.2  474.34  4880.9  475.79  4969.6   476.3
  4979.6  474.66  4987.5  464.86    4988  464.36  5011.8  464.86  5019.6  476.15
  5033.5  476.06  5143.3  474.82  5249.6   476.5  5289.6  479.23  5459.7  480.62
  5822.2  488.86  6032.5  492.46  6229.6  496.27  6353.6  498.98  6413.9  500.05
#Mann= 15 ,-1 , 0
  3040.1     .05       0  3387.8    .035       0  4334.9     .07       0
  4403.6    .035       0  4588.4     .07       0  4760.2      .1       0
  4880.9    .035       0  4987.5    .035       0  5011.8    .035       0
  5033.5      .1       0  5143.3     .07       0  5822.2    .035       0
  6032.5     .07       0  6229.6     .05       0  6353.6     .07       0
Bank Sta=4987.5,5011.8
XS Rating Curve= 0 ,0
Exp/Cntr=0.3,0.1

Type RM Length L Ch R = 1 ,60950   ,559,559,559
BEGIN DESCRIPTION:
Mill Creek 69.0
END DESCRIPTION:
XS GIS Cut Line= 3
      2324583.49     13773270.39        2323125.       13773075.
      2321491.26     13773138.62
#Sta/Elev= 30
  3528.8  502.18    3691  497.96  3913.3  491.45  4074.2  488.62  4526.1  485.41
  4556.4  483.89  4576.6   480.5  4583.9  483.63  4596.7  484.33  4788.3   481.1
  4890.9  477.69  4929.7  474.43  4970.1  474.28  4990.2  470.89  4997.8  466.54
  4998.1   462.3  4998.6   461.8  5022.6   462.3  5030.3  472.94  5060.4  475.06
  5280.5  474.67  5390.7  480.39  5590.8  480.07  5660.8  476.81  5730.9  480.62
  6141.2  485.65  6151.2  486.01  6161.5  489.22  6211.2  490.91  6635.3  496.13
#Mann= 7 ,-1 , 0
  3528.8     .07       0    3691    .035       0  3913.3     .05       0
  4074.2     .07       0  4788.3    .035       0  4998.1    .035       0
  5022.6    .035       0
Bank Sta=4998.1,5022.6
XS Rating Curve= 0 ,0
Exp/Cntr=0.3,0.1

Type RM Length L Ch R = 1 ,60391   ,552,552,552
BEGIN DESCRIPTION:
Mill Creek 68.0
END DESCRIPTION:
XS GIS Cut Line= 3
      2324513.25     13772883.87        2322825.       13772625.
      2321429.89     13772883.85
#Sta/Elev= 30
  3297.2  499.68  3558.5  489.67  3922.7  485.79  4380.7  484.78  4570.2  480.03
  4707.5  474.84  4775.9  473.32  4814.9  474.01  4964.7  474.84    4971   472.4
    4976  473.81  4982.8  462.28  4983.3  461.78  5007.4  462.28  5007.7  466.08
  5015.3  473.85  5025.5  474.68  5087.2  472.26  5178.1  474.85  5381.5  475.45
  5585.4  480.39  5633.1   482.7  5928.3  486.75  5977.5  487.59  6160.5  489.33
  6181.8  489.01  6186.9  490.16  6234.6  488.89  6297.6  491.84  6424.1  492.14
#Mann= 8 ,-1 , 0
  3297.2     .05       0  4814.9      .1       0  4982.8     .05       0
  5007.4      .1       0  5087.2     .07       0  5928.3     .05       0
  5977.5    .035       0  6160.5    .063       0
Bank Sta=4982.8,5007.4
XS Rating Curve= 0 ,0
Exp/Cntr=0.3,0.1

Type RM Length L Ch R = 1 ,59839   ,516,516,516
BEGIN DESCRIPTION:
Mill Creek 67.0
END DESCRIPTION:
XS GIS Cut Line= 3
      2324293.57     13771706.73      2322817.78     13772207.45
      2321201.41     13772822.37
#Sta/Elev= 30
  3591.7  500.68  3596.3  500.37  4037.8  480.74  4075.9  478.44  4101.1  480.54
  4234.1  479.35    4466  483.13  4519.5  483.86    4594  481.63  4766.8  476.05
  4865.6  474.23  4940.9  472.92  4984.1  473.61  4988.9  460.48  4989.4  459.98
  5013.5  460.48  5032.6  473.77  5152.1  473.51  5253.3  472.91  5327.8  472.04
  5436.6  477.36  5559.7  481.59  5892.6   483.4  6005.2  483.62  6148.1  481.84
  6212.3  483.29    6367  485.52  6425.4  484.49  6615.9  488.97  6879.5  494.83
#Mann= 19 ,-1 , 0
  3591.7     .05       0  3596.3     .07       0  4037.8     .12       0
  4234.1     .07       0    4466     .12       0    4594     .07       0
  4766.8     .05       0  4865.6     .07       0  4940.9      .1       0
  4988.9     .05       0  5013.5      .1       0  5152.1     .12       0
  5253.3     .07       0  5436.6     .05       0  5892.6     .07       0
  6005.2     .05       0  6212.3    .035       0  6425.4     .05       0
  6615.9    .035       0
Bank Sta=4988.9,5013.5
XS Rating Curve= 0 ,0
Exp/Cntr=0.3,0.1

Type RM Length L Ch R = 1 ,59323   ,650,650,650
BEGIN DESCRIPTION:
Mill Creek 66.0
END DESCRIPTION:
XS GIS Cut Line= 3
      2323880.75     13771285.04        2322675.       13771775.
      2321113.54     13772629.12
#Sta/Elev= 30
  3702.6  495.82  3914.4   488.4  4205.3  476.53  4421.2  473.27  4518.4  474.36
  4804.6  471.55  4873.4  472.47  4965.3  472.67  4971.7  471.32  4982.4  460.63
  4982.9  460.13  5007.1  460.63  5012.2  470.74  5017.9  472.76  5055.8  470.66
  5071.9  472.17  5099.4  470.57  5162.6  471.69  5209.3  473.04  5330.8  471.55
  5390.8  472.46  6127.6  477.72  6264.2  480.15  6307.8  483.02    6324  482.23
  6329.7  483.87  6367.6  482.07  6417.5  483.92  6668.2  491.93  6783.9  493.59
#Mann= 10 ,-1 , 0
  3702.6     .05       0  3914.4     .07       0  4873.4      .1       0
  4982.4     .05       0  5007.1      .1       0  5162.6     .12       0
  5330.8     .07       0  5390.8     .05       0  6127.6     .07       0
  6417.5     .05       0
Bank Sta=4982.4,5007.1
XS Rating Curve= 0 ,0
Exp/Cntr=0.3,0.1