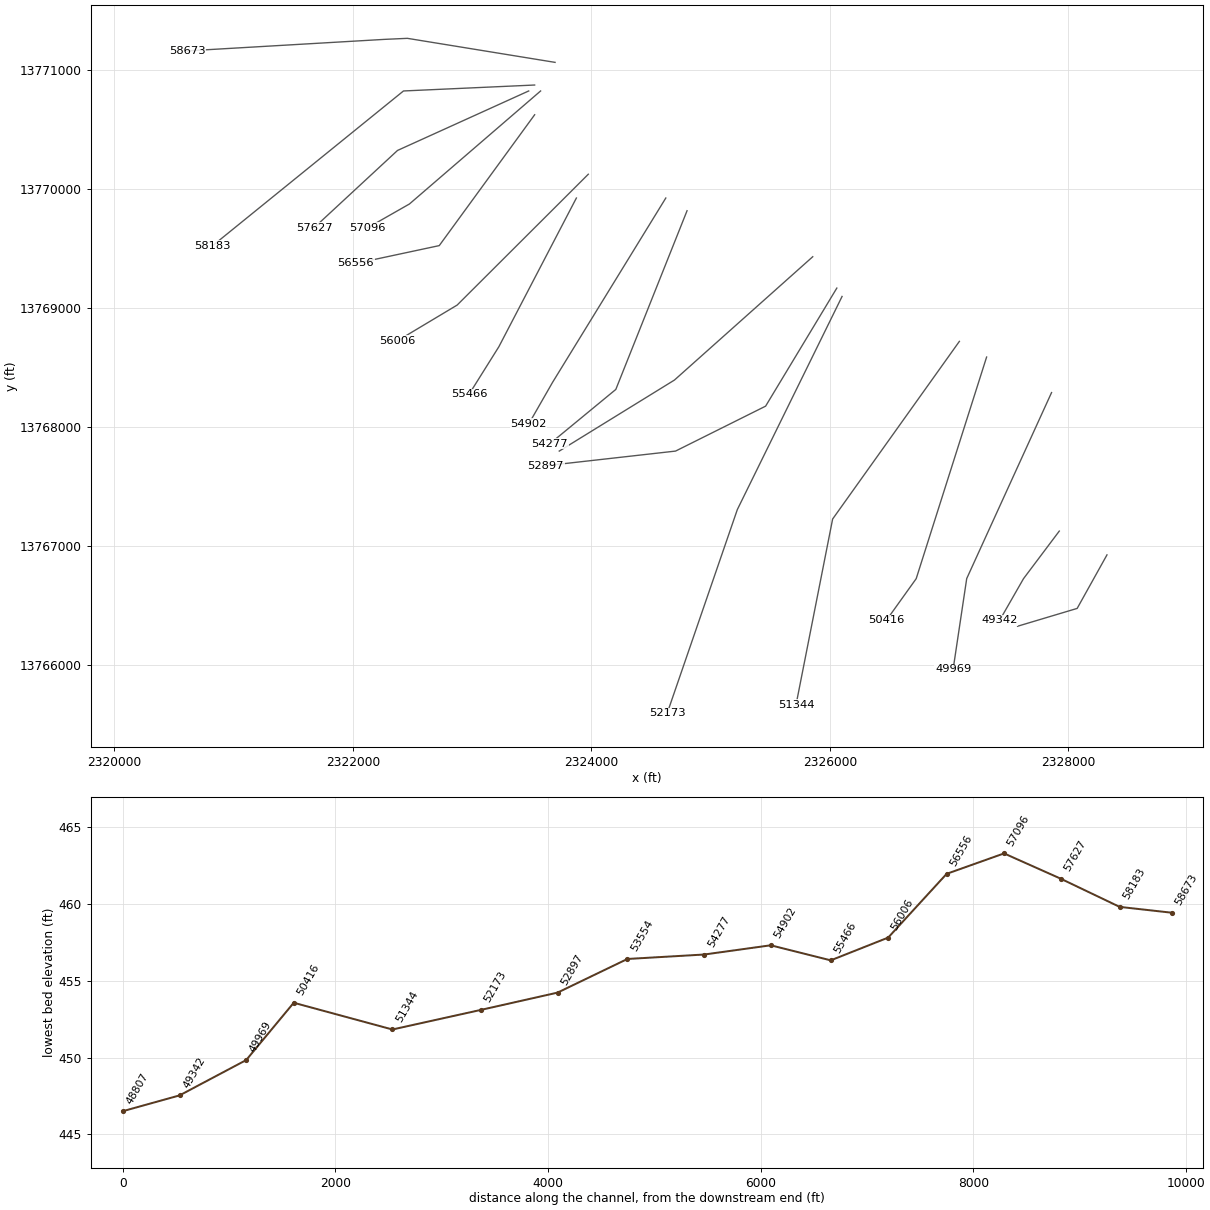
HEC-RAS study Mill Creek.prj: Mill Creek Base Level Engineering

--- Mill Creek.g01 (geometry) --- (continued)

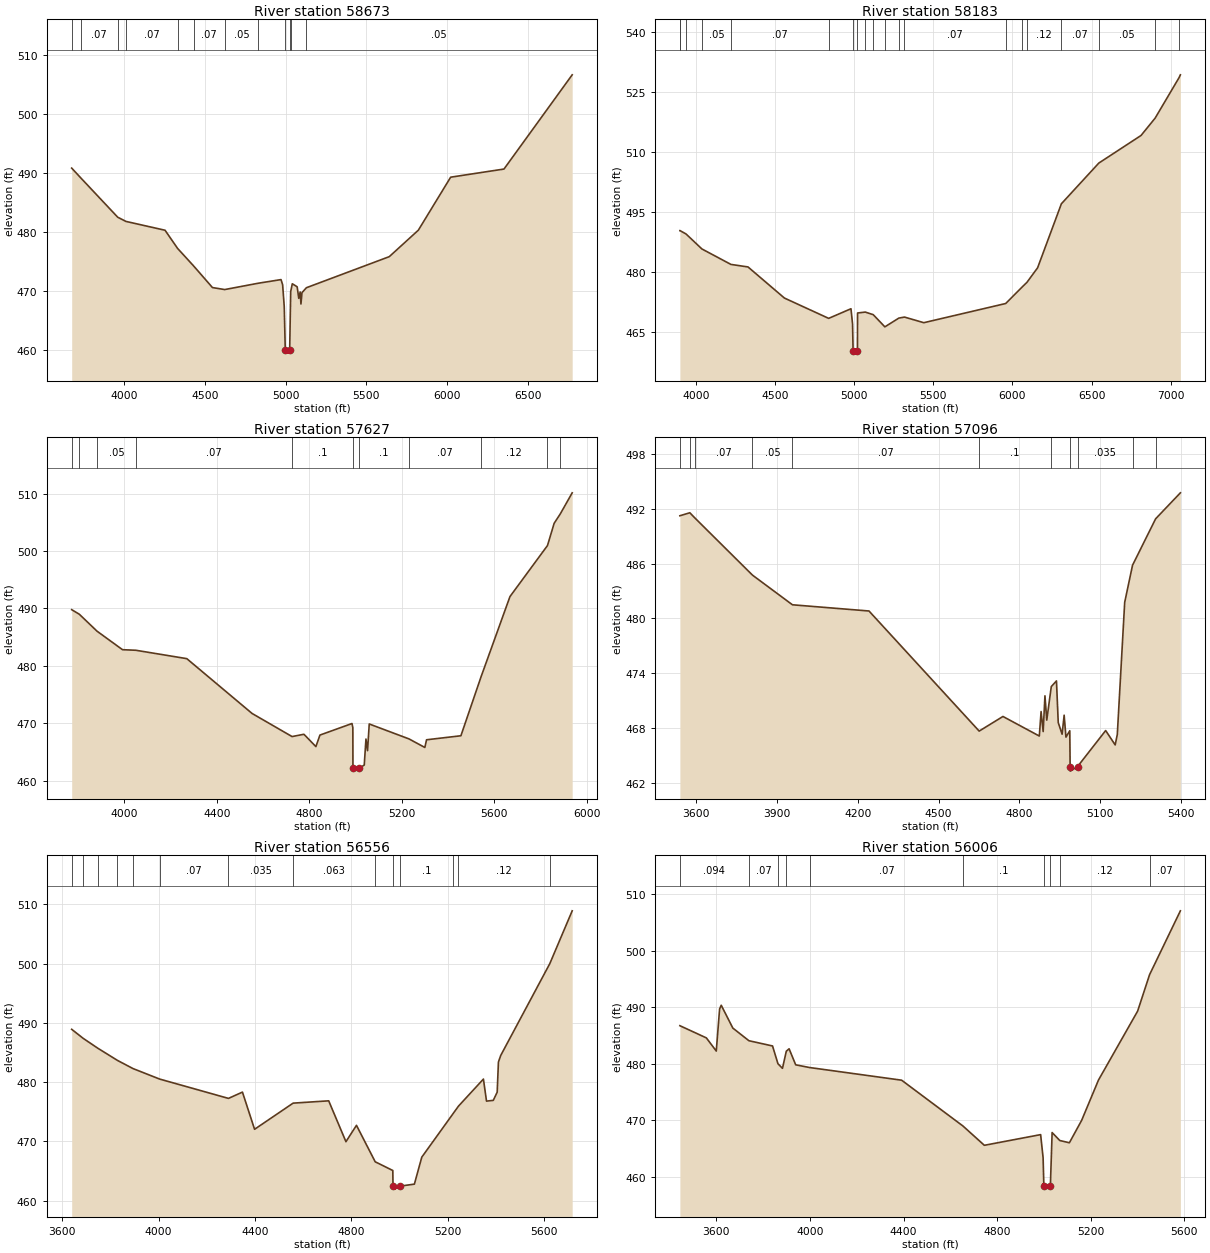
Type RM Length L Ch R = 1 ,58673   ,490,490,490
BEGIN DESCRIPTION:
B19410
END DESCRIPTION:
XS GIS Cut Line= 4
      2323696.26     13771065.44      2322457.61     13771267.48
      2322264.35      13771258.7      2320612.85     13771162.07
#Sta/Elev= 30
  3673.8  490.81  3728.7  489.19  3959.2  482.48    4010  481.77  4252.6  480.27
  4330.3  477.19  4430.6  474.19  4546.4  470.55  4622.3  470.21  4831.6  471.29
  4971.5   471.9  4981.5  471.03  4991.5  467.33  4997.9  459.93  4998.4  459.43
  5025.2  459.93  5030.3  467.98  5031.5  469.88  5041.5  471.19  5071.6  470.68
  5081.6  468.72  5090.1   469.8  5095.1  467.76  5101.6  469.69  5128.7  470.52
  5642.5  475.79  5822.8  480.28  6023.2  489.27  6353.7  490.65  6776.6  506.63
#Mann= 12 ,-1 , 0
  3673.8     .05       0  3728.7     .07       0  3959.2     .05       0
    4010     .07       0  4330.3     .05       0  4430.6     .07       0
  4622.3     .05       0  4831.6      .1       0  4997.9     .05       0
  5025.2      .1       0  5030.3     .07       0  5128.7     .05       0
Bank Sta=4997.9,5025.2
XS Rating Curve= 0 ,0
Exp/Cntr=0.3,0.1

Type RM Length L Ch R = 1 ,58183   ,556,556,556
BEGIN DESCRIPTION:
Mill Creek 65.0
END DESCRIPTION:
XS GIS Cut Line= 3
      2323524.97       13770875.        2322425.       13770825.
      2320824.97     13769524.97
#Sta/Elev= 30
  3898.9   490.4    3900   490.4  3937.8  489.56  4038.1  485.82  4221.5  481.96
  4329.3  481.33  4559.5  473.56  4839.1  468.49    4980  470.89    4990  467.11
  4993.5  460.31    4994  459.81  5020.8  460.31  5021.6  469.83  5070.3  470.06
  5120.7  469.41  5194.2  466.37  5282.6  468.56  5318.2  468.81  5440.3  467.41
  5957.8   472.2  6061.7  476.32  6092.3   477.5  6159.4  481.12  6309.6   497.1
    6546  507.26    6813  514.16  6902.1  518.49  7053.1  528.59  7061.6   529.3
#Mann= 20 ,-1 , 0
  3898.9     .07       0    3900     .05       0  3937.8     .07       0
  4038.1     .05       0  4221.5     .07       0  4839.1      .1       0
  4993.5     .05       0  5020.8      .1       0  5070.3     .07       0
  5120.7      .1       0  5194.2     .05       0  5282.6      .1       0
  5318.2     .07       0  5957.8     .12       0  6061.7     .07       0
  6092.3     .12       0  6309.6     .07       0    6546     .05       0
  6902.1     .07       0  7053.1     .05       0
Bank Sta=4993.5,5020.8
XS Rating Curve= 0 ,0
Exp/Cntr=0.3,0.1

Type RM Length L Ch R = 1 ,57627   ,531,531,531
BEGIN DESCRIPTION:
Mill Creek 64.0
END DESCRIPTION:
XS GIS Cut Line= 3
      2323475.01       13770825.        2322375.       13770325.
      2321674.97     13769674.98
#Sta/Elev= 30
  3772.8  489.77  3805.6  488.98  3882.2  486.03  3992.5   482.8  4050.2   482.7
  4270.4  481.24  4552.7  471.69  4725.4  467.67  4776.8  468.07  4828.4  465.92
    4846  467.93  4984.5  469.94  4988.2  469.24  4988.6  462.15  4989.1  461.65
  5016.1  462.15  5037.5  462.71  5044.9  467.24  5051.7  465.21  5059.1  469.86
    5231  467.26  5299.4  465.77  5306.8  467.11  5455.3  467.81  5542.6   478.1
  5667.4  492.05  5829.6  500.94  5858.4  504.81  5885.1  506.46  5936.4  510.12
#Mann= 11 ,-1 , 0
  3772.8     .05       0  3805.6     .07       0  3882.2     .05       0
  4050.2     .07       0  4725.4      .1       0  4988.6     .05       0
  5016.1      .1       0    5231     .07       0  5542.6     .12       0
  5829.6    .035       0  5885.1     .07       0
Bank Sta=4988.6,5016.1
XS Rating Curve= 0 ,0
Exp/Cntr=0.3,0.1

Type RM Length L Ch R = 1 ,57096   ,540,540,540
BEGIN DESCRIPTION:
Mill Creek 63.0
END DESCRIPTION:
XS GIS Cut Line= 3
        2323575.       13770825.        2322475.       13769875.
      2322124.96     13769674.98
#Sta/Elev= 30
  3540.5  491.23  3577.4  491.56  3595.1  491.02  3809.6  484.74    3958  481.49
    4242  480.81  4650.7  467.67  4738.9  469.27  4873.8  467.13  4880.4  469.81
  4888.1  467.62  4894.7  471.53  4901.4  468.87  4918.2  472.54  4937.4  473.16
    4944   468.6  4958.3  467.33  4965.9  469.41  4972.6  467.01  4986.8  467.71
  4988.1  463.79  4988.6  463.29  5015.7  463.79  5119.9  467.73  5155.2  466.16
  5163.1   467.3  5190.5  481.76  5219.6  485.82  5305.3   490.9  5397.1  493.74
#Mann= 11 ,-1 , 0
  3540.5     .07       0  3577.4     .05       0  3595.1     .07       0
  3809.6     .05       0    3958     .07       0  4650.7      .1       0
  4918.2    .035       0  4988.1    .035       0  5015.7    .035       0
  5219.6    .063       0  5305.3    .035       0
Bank Sta=4988.1,5015.7
XS Rating Curve= 0 ,0
Exp/Cntr=0.3,0.1

Type RM Length L Ch R = 1 ,56556   ,550,550,550
BEGIN DESCRIPTION:
Mill Creek 62.0
END DESCRIPTION:
XS GIS Cut Line= 3
      2323525.02     13770625.03        2322725.       13769525.
      2322024.98       13769375.
#Sta/Elev= 30
  3639.4  488.91  3687.3  487.38  3748.5   485.7  3829.2  483.67  3893.7  482.29
  4004.2  480.52  4289.7  477.26  4347.7  478.32    4398  472.05  4557.9  476.46
  4705.5  476.85    4777  469.96  4820.7  472.72  4898.4  466.57  4971.4   465.1
  4972.2  462.46  4972.7  461.96    5000  462.46  5060.9   462.8  5091.6  467.35
  5222.3  474.74  5243.7  475.95  5347.3  480.52  5360.1   476.8  5388.2  476.93
  5404.4  478.31  5409.5  483.39  5418.9  484.49  5622.7  499.99  5715.5  508.89
#Mann= 14 ,-1 , 0
  3639.4     .05       0  3687.3     .07       0  3748.5     .05       0
  3829.2     .07       0  3893.7     .05       0  4004.2     .07       0
  4289.7    .035       0  4557.9    .063       0  4898.4      .1       0
  4972.2     .05       0    5000      .1       0  5222.3    .035       0
  5243.7     .12       0  5622.7    .035       0
Bank Sta=4972.2,5000
XS Rating Curve= 0 ,0
Exp/Cntr=0.3,0.1

Type RM Length L Ch R = 1 ,56006   ,540,540,540
BEGIN DESCRIPTION:
Mill Creek 61.0
END DESCRIPTION:
XS GIS Cut Line= 3
      2323974.98     13770124.98        2322875.       13769025.
        2322375.       13768725.
#Sta/Elev= 30
  3444.4  486.75  3557.5  484.59  3599.9  482.26  3614.1  489.71  3621.1  490.37
  3670.6  486.33  3739.3  484.09  3840.3  483.16  3863.5  480.01  3882.8   479.2
  3899.1  482.23  3911.1  482.66  3939.3  479.82  3998.8  479.34  4391.9   477.1
  4654.5  468.97  4745.4  465.57  4985.9  467.46  4996.5  463.36  4999.7  458.31
  5000.2  457.81  5027.5  458.31    5035  467.83  5067.7  466.42  5108.8  466.02
  5161.3     470  5233.2  477.13  5400.4  489.33  5451.3  495.77  5583.1  507.09
#Mann= 10 ,-1 , 0
  3444.4    .094       0  3739.3     .07       0  3863.5    .035       0
  3899.1     .05       0  3998.8     .07       0  4654.5      .1       0
  4999.7     .05       0  5027.5      .1       0  5067.7     .12       0
  5451.3     .07       0
Bank Sta=4999.7,5027.5
XS Rating Curve= 0 ,0
Exp/Cntr=0.3,0.1

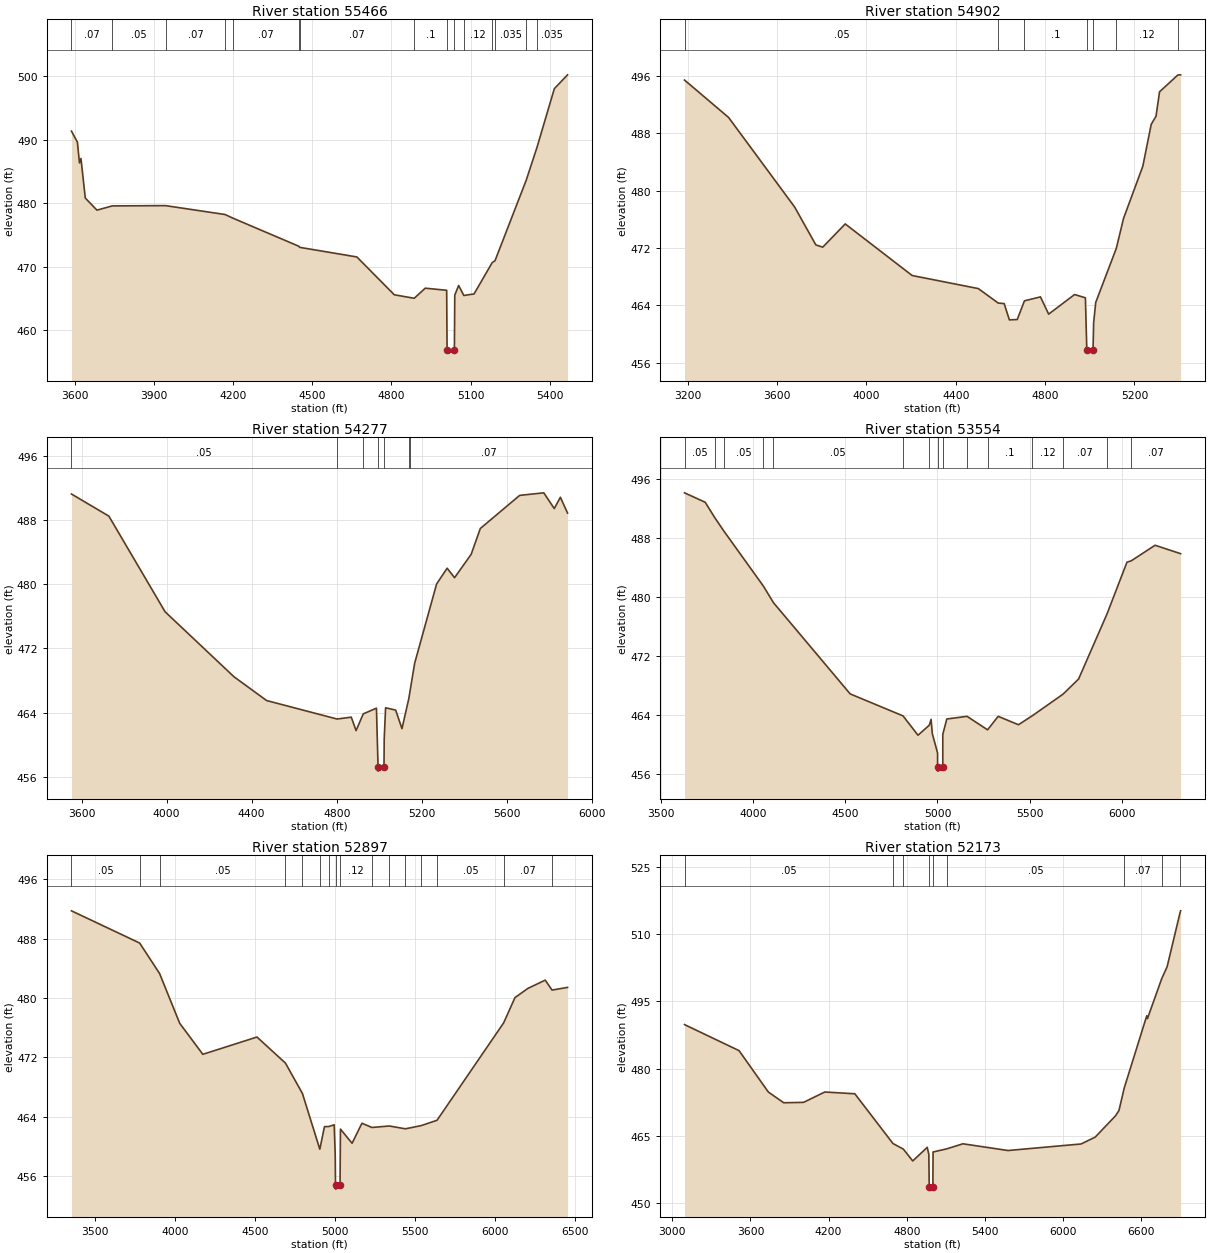
Type RM Length L Ch R = 1 ,55466   ,564,564,564
BEGIN DESCRIPTION:
Mill Creek 60.0
END DESCRIPTION:
XS GIS Cut Line= 3
      2323874.99     13769924.98        2323225.       13768675.
      2322974.99     13768274.98
#Sta/Elev= 30
  3587.1  491.37  3609.6  489.64  3617.4  486.36  3623.1  487.05  3639.5  480.81
  3683.7   478.9    3742  479.57  3944.1  479.61  4169.4  478.21  4197.8  477.66
  4449.6  473.19  4452.1  473.03  4669.1  471.51  4810.9  465.54  4886.5  464.99
  4928.3  466.58  5009.5  466.25    5011  456.83  5011.5  456.33  5038.8  456.83
  5040.2  465.49  5054.9  467.01  5074.5  465.43  5113.3  465.67  5182.2  470.63
  5192.7  470.91    5311  483.62  5351.9  488.81  5417.6  498.07  5467.7  500.26
#Mann= 15 ,-1 , 0
  3587.1     .07       0    3742     .05       0  3944.1     .07       0
  4169.4     .12       0  4197.8     .07       0  4449.6     .12       0
  4452.1     .07       0  4886.5      .1       0    5011     .05       0
  5038.8      .1       0  5074.5     .12       0  5182.2     .07       0
  5192.7    .035       0    5311     .07       0  5351.9    .035       0
Bank Sta=5011,5038.8
XS Rating Curve= 0 ,0
Exp/Cntr=0.3,0.1

Type RM Length L Ch R = 1 ,54902   ,625,625,625
BEGIN DESCRIPTION:
Mill Creek 59.0
END DESCRIPTION:
XS GIS Cut Line= 3
      2324625.01     13769925.02        2323675.       13768375.
        2323475.       13768025.
#Sta/Elev= 30
  3185.6  495.42  3382.9   490.2  3678.8  477.69  3773.6  472.41  3804.5   472.1
  3905.1  475.34  4204.8  468.14  4500.8  466.32    4590   464.3  4616.8  464.22
    4640  461.95  4675.2     462  4707.5  464.61  4779.2  465.16  4815.9  462.75
    4932  465.49  4980.4  465.03  4986.7  457.81  4987.2  457.31  5014.6  457.81
  5017.3  461.54  5026.6  464.38  5118.9  471.94  5151.2  476.11  5237.5  483.39
    5275  489.23  5296.6  490.37  5312.4  493.78  5394.4  496.13  5406.7  496.15
#Mann= 7 ,-1 , 0
  3185.6     .05       0    4590     .12       0  4707.5      .1       0
  4986.7     .05       0  5014.6      .1       0  5118.9     .12       0
  5394.4     .07       0
Bank Sta=4986.7,5014.6
XS Rating Curve= 0 ,0
Exp/Cntr=0.3,0.1

Type RM Length L Ch R = 1 ,54277   ,723,723,723
BEGIN DESCRIPTION:
B19409
END DESCRIPTION:
XS GIS Cut Line= 3
      2324803.14     13769818.05      2324205.76     13768315.83
      2323652.91      13767859.5
#Sta/Elev= 30
  3552.4  491.22  3728.3  488.47  3992.7  476.56  4316.5  468.47  4470.4   465.5
  4801.5   463.2  4868.6  463.43  4891.2  461.76  4924.9  463.84    4987  464.55
  4994.6  457.21  4995.1  456.71  5022.5  457.21  5023.5   460.7    5030   464.6
  5077.4  464.31  5107.1     462  5139.3  465.75  5142.6  466.29  5166.8  470.15
  5269.9  480.01  5319.4  481.98  5354.5   480.8  5432.7  483.72  5475.7  486.93
  5660.7  491.05  5774.1  491.37  5823.6  489.41  5852.2  490.82  5885.9  488.85
#Mann= 7 ,-1 , 0
  3552.4     .05       0  4801.5     .07       0  4924.9      .1       0
  4994.6     .05       0  5022.5      .1       0  5139.3     .12       0
  5142.6     .07       0
Bank Sta=4994.6,5022.5
XS Rating Curve= 0 ,0
Exp/Cntr=0.3,0.1

Type RM Length L Ch R = 1 ,53554   ,657,657,657
BEGIN DESCRIPTION:
B19408
END DESCRIPTION:
XS GIS Cut Line= 3
       2325857.3      13769431.5      2324697.71     13768394.89
      2323731.41     13767797.55
#Sta/Elev= 30
  3627.8  494.16    3740  492.88  3792.2  490.78  3839.4  489.04  4055.6  481.51
  4110.1  479.27  4526.6  466.89  4813.2  463.91  4894.4  461.29  4955.8  462.65
  4965.5  463.44  4972.2  461.49  5000.6  458.88  5000.8  456.92  5001.3  456.42
  5028.9  456.92    5029  461.41  5050.7  463.49  5160.7  463.85  5271.8  462.02
  5329.5  463.85  5439.4  462.71  5515.3  463.94  5681.4  466.86  5765.7  468.91
  5920.2  477.75  6028.1  484.75  6051.4  484.94  6180.6  487.05  6319.2  485.91
#Mann= 15 ,-1 , 0
  3627.8     .05       0  3792.2     .07       0  3839.4     .05       0
  4055.6     .07       0  4110.1     .05       0  4813.2     .12       0
  4955.8      .1       0  5000.8     .05       0  5028.9      .1       0
  5160.7     .12       0  5271.8      .1       0  5515.3     .12       0
  5681.4     .07       0  5920.2     .05       0  6051.4     .07       0
Bank Sta=5000.8,5028.9
XS Rating Curve= 0 ,0
Exp/Cntr=0.3,0.1

Type RM Length L Ch R = 1 ,52897   ,724,724,724
BEGIN DESCRIPTION:
B19407
END DESCRIPTION:
XS GIS Cut Line= 4
      2326059.35     13769167.96      2325461.97     13768175.27
      2324706.49     13767797.53      2323618.63     13767674.71
#Sta/Elev= 30
  3353.1  491.74  3778.8   487.4  3903.2   483.3  4029.1  476.58  4173.5   472.4
  4511.7  474.73  4689.7  471.21  4795.5  467.12    4904  459.61  4933.1  462.65
  4960.6  462.67  4993.8   462.9  5000.2  458.87  5002.1  454.73  5002.6  454.23
  5030.3  454.73    5033  462.32  5105.6  460.41  5167.1  463.11  5229.5  462.54
    5338  462.74  5438.5  462.36  5537.2  462.79    5636  463.51  6052.2  476.64
  6122.7  480.04  6203.2  481.28  6311.8   482.4  6354.3  481.06  6451.1  481.42
#Mann= 16 ,-1 , 0
  3353.1     .05       0  3778.8     .07       0  3903.2     .05       0
  4689.7     .07       0  4795.5     .12       0    4904      .1       0
  4960.6     .12       0  5002.1     .05       0  5030.3     .12       0
  5229.5     .07       0    5338     .05       0  5438.5     .07       0
  5537.2     .12       0    5636     .05       0  6052.2     .07       0
  6354.3    .035       0
Bank Sta=5002.1,5030.3
XS Rating Curve= 0 ,0
Exp/Cntr=0.3,0.1

Type RM Length L Ch R = 1 ,52173   ,829,829,829
BEGIN DESCRIPTION:
Mill Creek 58.0
END DESCRIPTION:
XS GIS Cut Line= 3
      2326103.23     13769097.62      2325224.79     13767305.59
       2324636.2     13765592.54
#Sta/Elev= 30
  3094.3  489.83  3512.7  484.02  3737.7  474.77  3855.7  472.38  4007.6  472.47
  4170.7  474.78  4401.2  474.39    4694  463.28  4773.7  462.03  4845.6  459.39
  4957.1  462.43  4969.2  460.83    4972   453.6  4972.5   453.1  5000.2   453.6
  5001.6  461.39  5106.4  462.09  5230.7  463.22  5577.1  461.72  6137.5  463.18
    6246  464.71  6402.2  469.48  6428.2  470.64  6468.7  475.67  6641.6   491.8
  6646.9  491.17  6756.6   500.1  6797.9  502.75  6893.8  514.41  6901.4  515.23
#Mann= 9 ,-1 , 0
  3094.3     .05       0    4694     .07       0  4773.7      .1       0
    4972     .05       0  5000.2      .1       0  5106.4     .05       0
  6468.7     .07       0  6756.6     .12       0  6893.8    .035       0
Bank Sta=4972,5000.2
XS Rating Curve= 0 ,0
Exp/Cntr=0.3,0.1

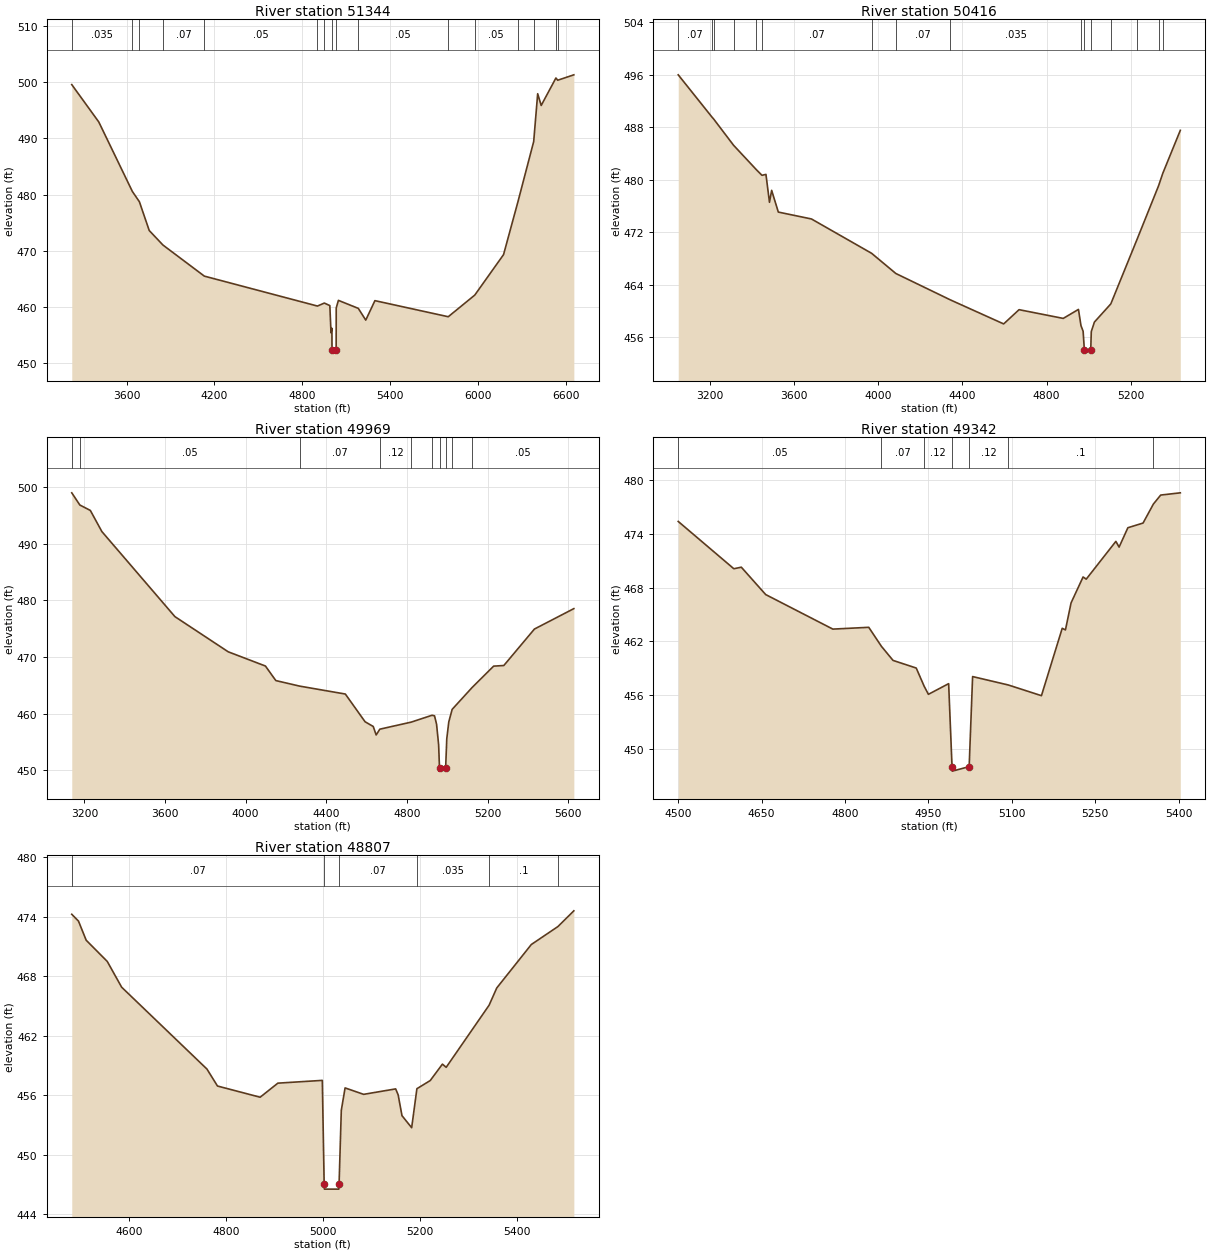
Type RM Length L Ch R = 1 ,51344   ,928,928,928
BEGIN DESCRIPTION:
Mill Creek 57.0
END DESCRIPTION:
XS GIS Cut Line= 3
      2327087.15     13768719.94      2326024.19     13767226.53
      2325716.73     13765662.85
#Sta/Elev= 30
  3226.1  499.57  3410.5  492.93  3639.8  480.57  3687.6  478.75  3754.8  473.63
  3848.3  471.05    4131  465.52  4902.9   460.2  4949.8  460.73  4987.4  460.28
  4995.5  455.45  5001.6  456.25  5002.3  452.33  5002.8  451.83  5030.5  452.33
  5031.1  459.86  5045.9  461.21  5181.6  459.79  5232.6   457.7  5295.1  461.16
  5795.7   458.3  5976.7  462.15    6173  469.34  6270.1  478.63  6378.8  489.45
    6406  497.95    6430  495.86  6530.5  500.75  6542.7  500.35  6652.8  501.31
#Mann= 16 ,-1 , 0
  3226.1    .035       0  3639.8     .12       0  3687.6    .035       0
  3848.3     .07       0    4131     .05       0  4902.9     .07       0
  4949.8     .12       0  5002.3     .05       0  5030.5     .12       0
  5181.6     .05       0  5795.7     .07       0  5976.7     .05       0
  6270.1     .07       0  6378.8     .12       0  6530.5     .07       0
  6542.7     .12       0
Bank Sta=5002.3,5030.5
XS Rating Curve= 0 ,0
Exp/Cntr=0.3,0.1

Type RM Length L Ch R = 1 ,50416   ,447,447,447
BEGIN DESCRIPTION:
Mill Creek 56.0
END DESCRIPTION:
XS GIS Cut Line= 3
      2327315.55     13768588.19        2326725.       13766725.
      2326474.98     13766374.97
#Sta/Elev= 30
    3050  495.97  3210.8  489.51  3217.5  489.27  3312.8  485.24  3421.3  481.51
  3447.8  480.66  3466.6   480.8  3483.4  476.55  3493.7  478.37  3525.4  475.06
  3682.8  474.01  3968.4  468.78  4083.7   465.7  4342.7  461.68  4595.7  458.02
  4668.9  460.19  4878.7  458.86  4950.9  460.23    4963  457.75  4973.1   456.9
  4978.9  454.07  4979.4  453.57  5009.3  454.07  5011.9  456.86  5026.7   458.3
  5104.6  461.07  5228.1  470.81  5331.5  479.07  5351.7  480.98  5434.7  487.51
#Mann= 16 ,-1 , 0
    3050     .07       0  3210.8     .05       0  3217.5     .12       0
  3312.8    .035       0  3421.3     .05       0  3447.8     .07       0
  3968.4     .05       0  4083.7     .07       0  4342.7    .035       0
    4963     .05       0  4978.9     .05       0  5009.3     .05       0
  5104.6     .12       0  5228.1     .07       0  5331.5     .12       0
  5351.7     .07       0
Bank Sta=4978.9,5009.3
XS Rating Curve= 0 ,0
Exp/Cntr=0.3,0.1

Type RM Length L Ch R = 1 ,49969   ,627,627,627
BEGIN DESCRIPTION:
Mill Creek 55.0
END DESCRIPTION:
XS GIS Cut Line= 3
      2327860.18     13768289.45      2327148.63      13766725.8
      2327034.43     13765961.52
#Sta/Elev= 30
  3137.3  499.01  3177.3  496.86  3229.4   495.9  3286.6  492.17  3648.9  477.14
  3913.5  470.92    4098  468.41  4149.6  465.84  4267.7  464.86  4494.4  463.46
  4592.4  458.56  4632.8  457.73  4647.4  456.23  4665.5  457.25  4821.4   458.5
  4924.4  459.71  4936.9  459.61    4947  458.13  4957.2  454.51  4961.6  450.34
  4962.1  449.84    4992  450.34  4997.6  455.55  5007.7  458.55  5024.3  460.75
  5124.3  464.65  5230.1  468.39  5280.7   468.5  5432.4  474.94    5628  478.55
#Mann= 10 ,-1 , 0
  3137.3    .035       0  3177.3     .05       0  4267.7     .07       0
  4665.5     .12       0  4821.4     .07       0  4924.4     .12       0
  4961.6     .05       0    4992     .12       0  5024.3     .07       0
  5124.3     .05       0
Bank Sta=4961.6,4992
XS Rating Curve= 0 ,0
Exp/Cntr=0.3,0.1

Type RM Length L Ch R = 1 ,49342   ,535,535,535
BEGIN DESCRIPTION:
Mill Creek 54.0
END DESCRIPTION:
XS GIS Cut Line= 3
      2327924.99     13767124.99        2327625.       13766725.
        2327425.     13766374.99
#Sta/Elev= 30
    4500  475.37    4600   470.1  4613.5  470.27  4657.3  467.22  4778.1  463.37
  4842.7  463.57  4865.5  461.45  4886.4  459.88  4928.1  459.03  4942.3  457.01
    4950   456.1  4986.4  457.29  4992.5  448.04    4993  447.54  5023.3  448.04
  5029.5  458.08  5093.8  457.14  5153.3  455.95  5190.7  463.46  5196.5  463.28
  5206.6  466.29  5228.2  469.18  5233.9  468.94  5287.2  473.15    5293  472.51
  5308.8  474.67  5336.1  475.19  5354.6   477.3  5367.8  478.31  5403.1  478.56
#Mann= 7 ,-1 , 0
    4500     .05       0  4865.5     .07       0  4942.3     .12       0
  4992.5     .05       0  5023.3     .12       0  5093.8      .1       0
  5354.6     .05       0
Bank Sta=4992.5,5023.3
XS Rating Curve= 0 ,0
Exp/Cntr=0.3,0.1

Type RM Length L Ch R = 1 ,48807   ,544,544,544
BEGIN DESCRIPTION:
Mill Creek 53.0
END DESCRIPTION:
XS GIS Cut Line= 3
      2328325.02     13766925.04        2328075.       13766475.
      2327575.04     13766325.01
#Sta/Elev= 30
    4481  474.26  4494.8  473.58  4510.8  471.64  4554.3   469.5    4584   466.9
  4760.2  458.63  4781.9  456.92    4870  455.79  4906.6  457.21  4998.4  457.49
  5002.2  447.01  5002.7  446.51  5032.5  446.51    5033  447.01  5037.6  454.46
  5045.4  456.73  5083.7  456.08  5149.8  456.63    5155  456.03  5162.9  453.93
  5182.9  452.71  5193.7  456.65  5221.2  457.47  5246.4  459.13  5254.2  458.81
  5342.8  465.08  5358.6  466.82    5430  471.21  5484.9  473.02  5517.8  474.61
#Mann= 6 ,-1 , 0
    4481     .07       0  5002.2     .05       0    5033     .07       0
  5193.7    .035       0  5342.8      .1       0  5484.9     .05       0
Bank Sta=5002.2,5033
XS Rating Curve= 0 ,0
Exp/Cntr=0.3,0.1