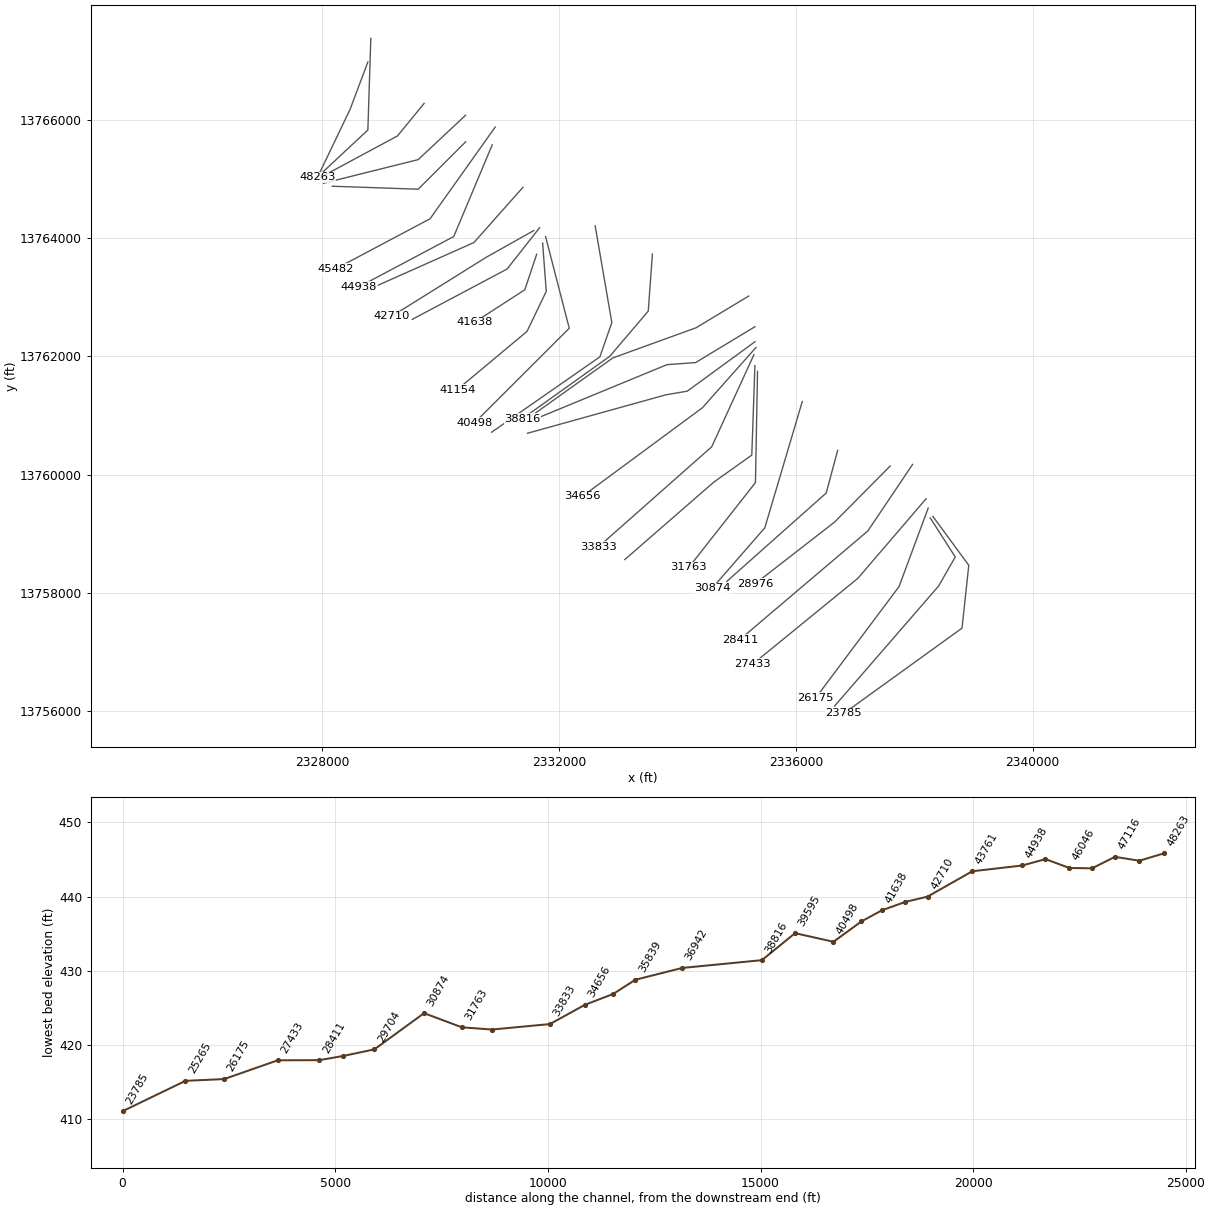
HEC-RAS study Mill Creek.prj: Mill Creek Base Level Engineering

--- Mill Creek.g01 (geometry) --- (continued)

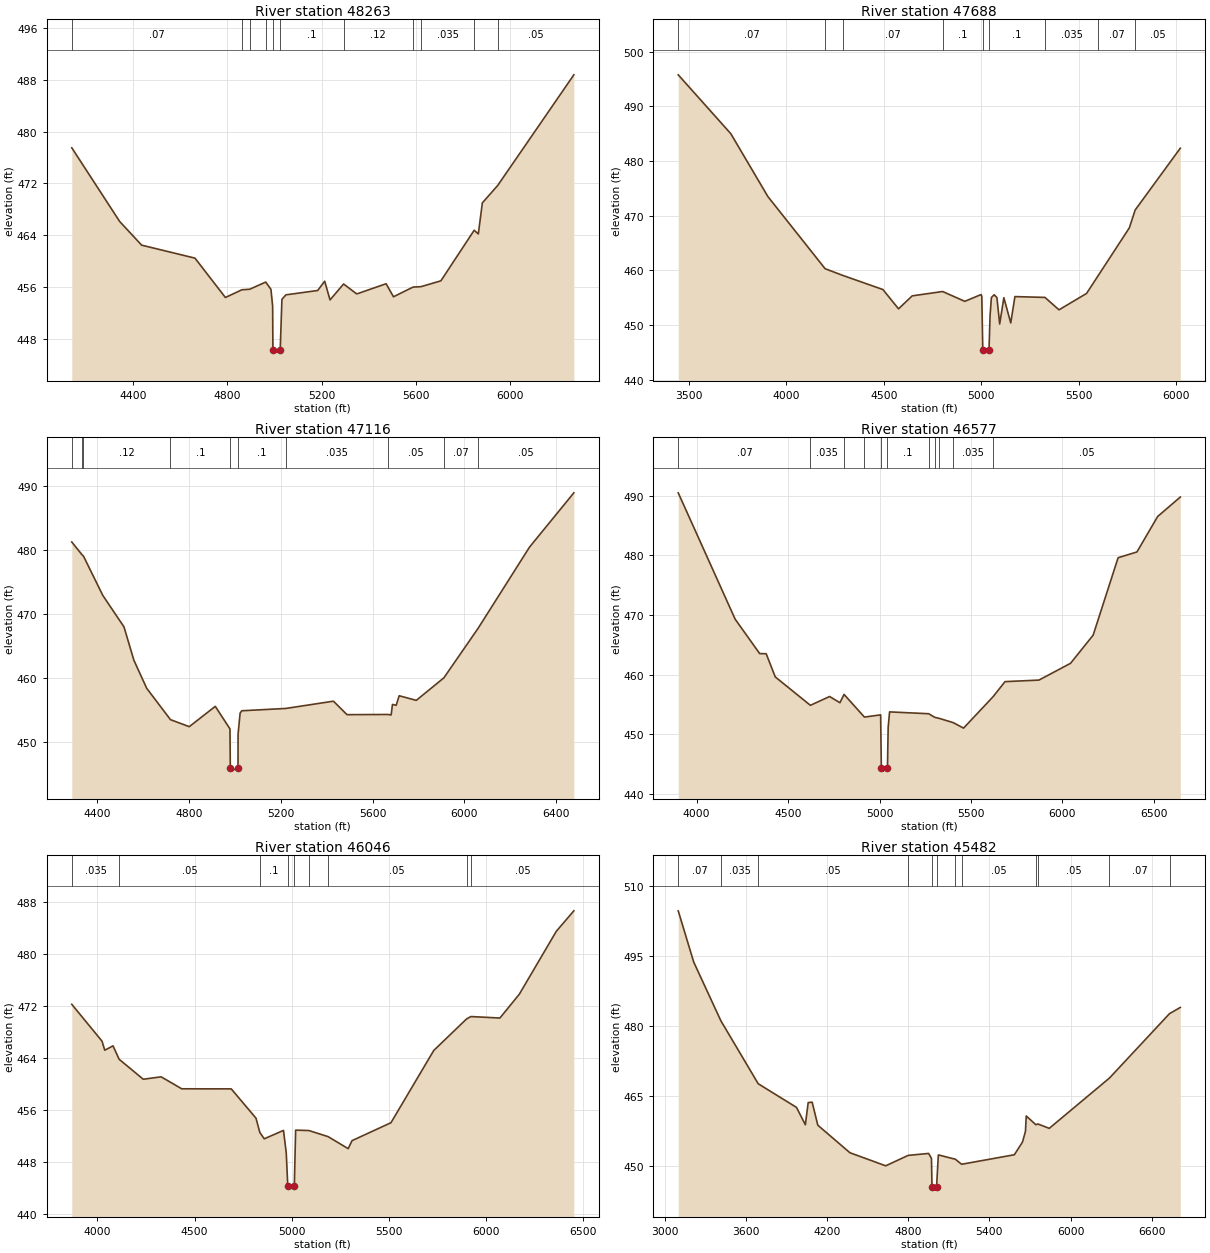
Type RM Length L Ch R = 1 ,48263   ,575,575,575
BEGIN DESCRIPTION:
Mill Creek 52.0
END DESCRIPTION:
XS GIS Cut Line= 3
      2328775.01     13766975.03        2328475.       13766175.
      2327924.99     13765024.99
#Sta/Elev= 30
  4140.1   477.5  4343.1  466.14  4436.5  462.48  4662.6  460.48  4791.6  454.41
  4861.7   455.6  4894.6  455.68  4962.7  456.79  4984.7  455.67  4991.9  453.12
  4993.2  446.33  4993.7  445.83  5024.1  446.33  5031.3  454.13  5048.4  454.82
    5183  455.49  5212.7  456.92  5235.4  454.04  5292.8  456.49  5348.7  454.96
  5473.2  456.53  5504.4  454.52  5587.8  456.02  5621.2  456.08  5705.5  456.98
  5846.7  464.78  5864.2  464.21  5881.3     469  5946.7   471.7  6269.3  488.75
#Mann= 11 ,-1 , 0
  4140.1     .07       0  4861.7      .1       0  4894.6     .07       0
  4962.7      .1       0  4993.2     .05       0  5024.1      .1       0
  5292.8     .12       0  5587.8     .07       0  5621.2    .035       0
  5846.7     .07       0  5946.7     .05       0
Bank Sta=4993.2,5024.1
XS Rating Curve= 0 ,0
Exp/Cntr=0.3,0.1

Type RM Length L Ch R = 1 ,47688   ,572,572,572
BEGIN DESCRIPTION:
Mill Creek 51.0
END DESCRIPTION:
XS GIS Cut Line= 3
        2328825.     13767374.97        2328775.       13765825.
        2328025.       13765125.
#Sta/Elev= 30
  3444.5  495.74  3714.6  484.96  3904.7  473.47  4198.3  460.28  4288.4  459.06
    4495  456.47  4575.1  452.94  4645.1  455.31  4801.3  456.11  4915.2  454.31
  4998.7  455.55  5002.4  455.26  5007.5  445.34    5008  444.84  5039.3  445.34
  5044.9  451.75  5051.7  455.01  5065.9  455.52    5080     455  5094.2  450.17
  5115.7  454.98  5150.9  450.37  5172.4  455.18  5326.7  455.03  5398.6  452.76
  5540.2  455.76  5599.3  458.99  5759.6  467.75  5789.4  471.01  6021.2  482.32
#Mann= 9 ,-1 , 0
  3444.5     .07       0  4198.3     .12       0  4288.4     .07       0
  4801.3      .1       0  5007.5     .05       0  5039.3      .1       0
  5326.7    .035       0  5599.3     .07       0  5789.4     .05       0
Bank Sta=5007.5,5039.3
XS Rating Curve= 0 ,0
Exp/Cntr=0.3,0.1

Type RM Length L Ch R = 1 ,47116   ,539,539,539
BEGIN DESCRIPTION:
Mill Creek 50.0
END DESCRIPTION:
XS GIS Cut Line= 3
        2329725.       13766275.        2329275.       13765725.
      2327975.01     13765025.01
#Sta/Elev= 30
  4289.6  481.24  4334.4  479.24  4340.5  479.04  4424.5   472.9  4517.1  467.95
  4560.2  462.73  4616.2  458.33  4719.6  453.43  4801.4  452.33  4914.8  455.51
  4978.7  451.98  4980.3  445.87  4980.9  445.37  5013.8  445.87    5014  451.15
  5022.9  454.45  5030.2  454.82  5221.3  455.18  5429.4  456.32  5488.6  454.21
  5665.5  454.24  5680.9  454.17  5686.6  455.81  5702.8  455.68  5715.8  457.17
  5790.4  456.45  5910.4  459.97  6060.6  467.78  6283.6  480.44  6476.7  488.94
#Mann= 10 ,-1 , 0
  4289.6     .12       0  4334.4     .07       0  4340.5     .12       0
  4719.6      .1       0  4980.3     .05       0  5013.8      .1       0
  5221.3    .035       0  5665.5     .05       0  5910.4     .07       0
  6060.6     .05       0
Bank Sta=4980.3,5013.8
XS Rating Curve= 0 ,0
Exp/Cntr=0.3,0.1

Type RM Length L Ch R = 1 ,46577   ,531,531,531
BEGIN DESCRIPTION:
Mill Creek 49.0
END DESCRIPTION:
XS GIS Cut Line= 3
      2330424.97     13766074.97        2329625.       13765325.
      2328024.99       13764925.
#Sta/Elev= 30
  3899.1  490.47  4210.4  469.29  4344.6  463.52    4380   463.5  4429.8  459.61
  4621.9  454.85  4726.8  456.33  4783.4  455.29  4805.9  456.68  4917.3  452.88
    5006  453.25  5009.8  444.32  5010.4  443.82  5043.4  444.32  5047.2  451.14
  5054.9  453.75  5268.9  453.44    5302  452.84  5327.9  452.65  5402.8  451.95
  5459.5  451.03  5620.2  456.27  5686.3  458.82  5871.8  459.08  6044.5  461.89
  6168.2  466.61  6304.7  479.59  6407.8  480.56  6521.2  486.51  6644.9  489.76
#Mann= 11 ,-1 , 0
  3899.1     .07       0  4621.9    .035       0  4805.9     .07       0
  4917.3      .1       0  5009.8     .05       0  5043.4      .1       0
  5268.9     .07       0    5302    .035       0  5327.9     .07       0
  5402.8    .035       0  5620.2     .05       0
Bank Sta=5009.8,5043.4
XS Rating Curve= 0 ,0
Exp/Cntr=0.3,0.1

Type RM Length L Ch R = 1 ,46046   ,564,564,564
BEGIN DESCRIPTION:
Mill Creek 48.0
END DESCRIPTION:
XS GIS Cut Line= 3
      2330425.02     13765625.02        2329625.       13764825.
      2328174.96       13764875.
#Sta/Elev= 30
  3868.2  472.25  4023.8  466.59  4037.9   465.2  4080.4  465.87  4111.8  463.81
  4235.9  460.74  4327.8  461.11  4433.9  459.27  4688.5  459.26  4815.7  454.76
  4835.4  452.57  4858.2  451.59  4957.2  452.88  4971.3  449.43  4979.2  444.36
  4979.9  443.86  5012.9  444.36  5019.6  452.92  5087.5  452.86  5186.2  451.93
  5289.8  450.08  5309.8  451.31  5509.9  454.06    5730  465.16  5898.7     470
    5921  470.37  6070.2  470.14  6170.3  473.81  6360.4  483.47  6450.5  486.61
#Mann= 9 ,-1 , 0
  3868.2    .035       0  4111.8     .05       0  4835.4      .1       0
  4979.2     .05       0  5012.9      .1       0  5087.5     .12       0
  5186.2     .05       0  5898.7    .035       0    5921     .05       0
Bank Sta=4979.2,5012.9
XS Rating Curve= 0 ,0
Exp/Cntr=0.3,0.1

Type RM Length L Ch R = 1 ,45482   ,544,544,544
BEGIN DESCRIPTION:
Mill Creek 47.0
END DESCRIPTION:
XS GIS Cut Line= 3
      2330924.99     13765874.99        2329825.       13764325.
      2328225.01       13763475.
#Sta/Elev= 30
  3099.3  504.63  3213.7  493.67  3414.5   481.1  3690.6  467.62  3973.9  462.55
  4039.2  458.84  4060.1  463.58  4089.6  463.67  4131.4  458.74  4368.8  452.85
  4633.3  450.05  4799.6  452.28  4950.8   452.7  4971.7  451.64  4975.7  445.56
  4976.4  445.06  5009.4  445.56  5022.6  452.38  5148.4  451.46  5194.7  450.38
  5584.6  452.42  5644.9  455.14  5666.9  457.46  5672.5  460.72  5743.7  458.84
  5758.3  459.01  5842.7  458.07  6287.9  468.84  6731.8  482.62  6811.7  483.95
#Mann= 12 ,-1 , 0
  3099.3     .07       0  3414.5    .035       0  3690.6     .05       0
  4799.6      .1       0  4975.7     .05       0  5009.4      .1       0
  5148.4     .07       0  5194.7     .05       0  5743.7     .07       0
  5758.3     .05       0  6287.9     .07       0  6731.8    .035       0
Bank Sta=4975.7,5009.4
XS Rating Curve= 0 ,0
Exp/Cntr=0.3,0.1

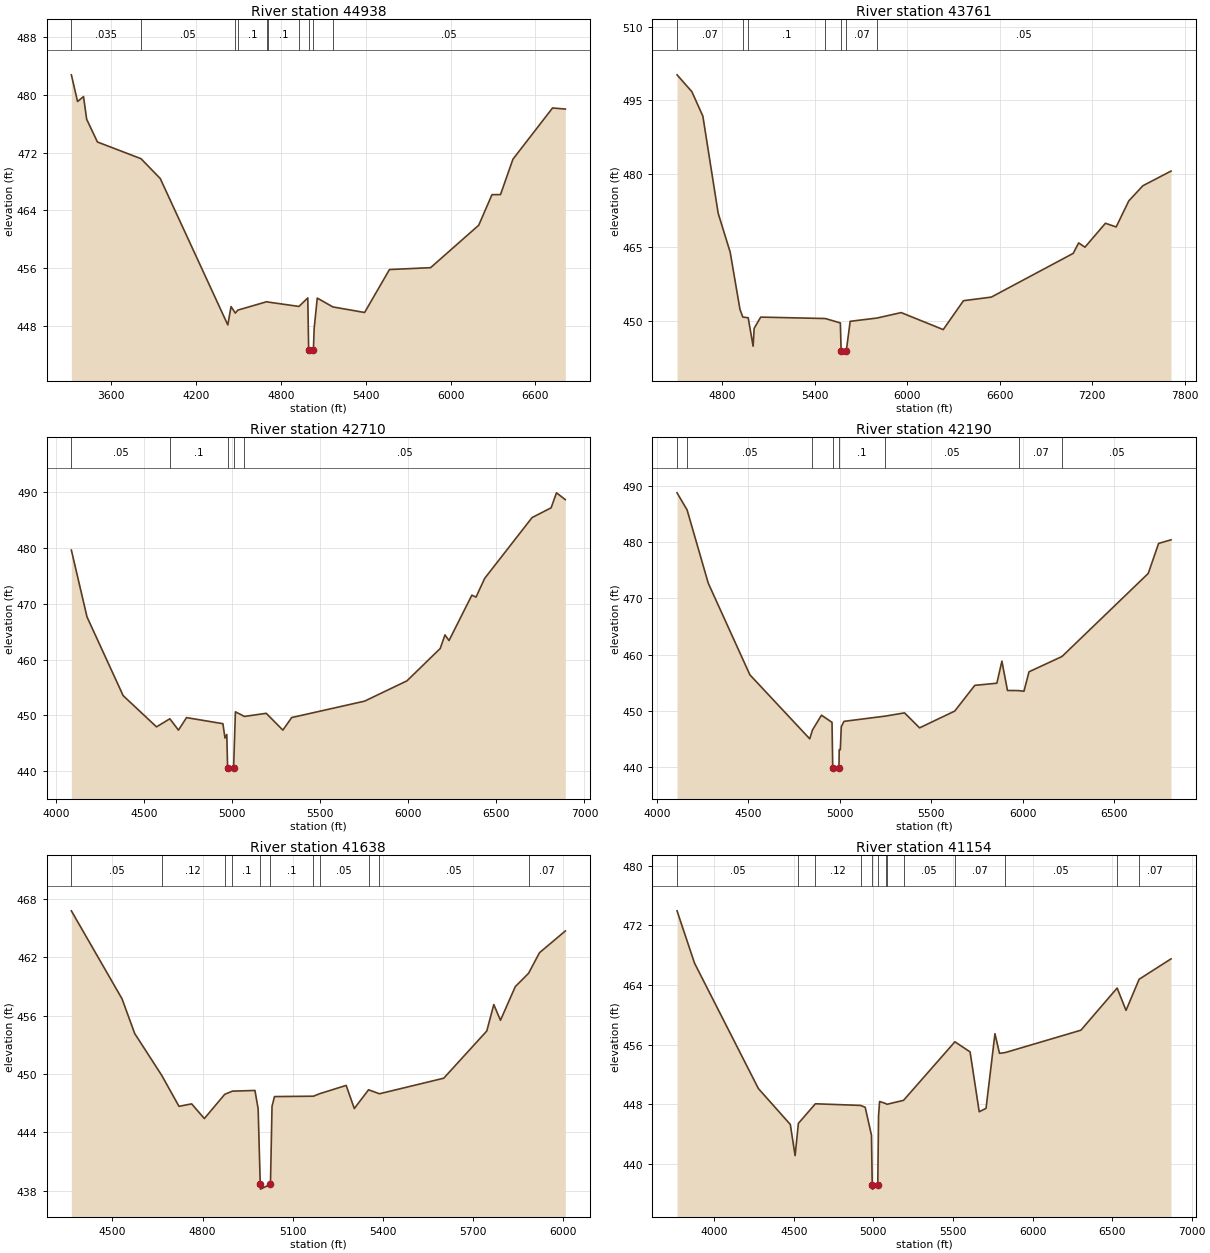
Type RM Length L Ch R = 1 ,44938   ,1177,1177,1177
BEGIN DESCRIPTION:
Mill Creek 46.0
END DESCRIPTION:
XS GIS Cut Line= 3
        2330875.       13765575.        2330225.       13764025.
      2328625.04     13763175.02
#Sta/Elev= 30
    3319  482.82  3362.8  479.12  3404.9   479.8  3427.4  476.65  3503.3   473.5
  3811.6  471.18  3947.5  468.43  4425.1  448.12    4448  450.66  4478.4  449.75
  4495.9  450.17  4701.4  451.34    4712  451.28  4928.2  450.68  4990.6  451.86
  4996.7   444.7  4997.4   444.2  5030.4   444.7  5035.6   447.6  5057.6  451.84
  5168.1  450.61  5392.3  449.84  5568.1   455.8  5858.9  456.06  6199.2  461.95
  6292.8  466.19  6353.1   466.2    6441  471.11  6721.1  478.22  6811.5  478.07
#Mann= 10 ,-1 , 0
    3319    .035       0  3811.6     .05       0  4478.4     .07       0
  4495.9      .1       0  4701.4     .12       0    4712      .1       0
  4928.2     .07       0  4996.7     .05       0  5030.4     .07       0
  5168.1     .05       0
Bank Sta=4996.7,5030.4
XS Rating Curve= 0 ,0
Exp/Cntr=0.3,0.1

Type RM Length L Ch R = 1 ,43761   ,1051,1051,1051
BEGIN DESCRIPTION:
Mill Creek 45.0
END DESCRIPTION:
XS GIS Cut Line= 3
      2331391.65     13764854.67      2330565.88     13763923.48
      2328775.01       13763125.
#Sta/Elev= 30
  4506.8  500.21  4603.2  496.76  4674.2  491.79  4773.7  471.96  4851.6  464.03
  4915.1  452.35  4933.7  450.78  4968.5  450.64  5000.4  444.83  5007.1  448.48
  5049.8  450.77  5468.6  450.48  5566.6  449.58  5571.4  443.92  5572.1  443.42
  5605.3  443.92  5630.2  449.91  5804.3  450.58  5961.1  451.69  6234.1  448.22
  6365.5  454.12    6546  454.85  7077.2  463.77    7113  465.91  7153.8  465.04
  7286.6  469.92  7356.3  469.17  7438.5   474.5  7529.8  477.58  7712.2  480.57
#Mann= 7 ,-1 , 0
  4506.8     .07       0  4933.7     .12       0  4968.5      .1       0
  5468.6     .07       0  5571.4     .05       0  5605.3     .07       0
  5804.3     .05       0
Bank Sta=5571.4,5605.3
XS Rating Curve= 0 ,0
Exp/Cntr=0.3,0.1

Type RM Length L Ch R = 1 ,42710   ,520,520,520
BEGIN DESCRIPTION:
Mill Creek 44.0
END DESCRIPTION:
XS GIS Cut Line= 3
      2331574.98     13764124.99        2330775.       13763675.
      2329174.96     13762674.97
#Sta/Elev= 30
    4087  479.61  4175.9  467.63  4381.1  453.53  4570.5  447.93  4646.2  449.38
  4695.1  447.35    4741  449.59  4947.5   448.5  4959.3  445.93  4969.5  446.57
  4974.2   440.5  4974.9     440  5008.1   440.5  5018.4  450.63  5069.5   449.8
  5193.5  450.36  5287.9  447.35    5338   449.6  5751.9  452.54  5992.5  456.18
  6181.2  461.97  6208.3  464.41  6231.3   463.4    6361  471.53  6384.6  471.18
  6433.5  474.53    6703  485.44  6810.9  487.18  6841.5  489.87  6891.7  488.65
#Mann= 5 ,-1 , 0
    4087     .05       0  4646.2      .1       0  4974.2     .05       0
  5008.1      .1       0  5069.5     .05       0
Bank Sta=4974.2,5008.1
XS Rating Curve= 0 ,0
Exp/Cntr=0.3,0.1

Type RM Length L Ch R = 1 ,42190   ,552,552,552
BEGIN DESCRIPTION:
Mill Creek 43.0
END DESCRIPTION:
XS GIS Cut Line= 3
      2331674.97     13764174.96        2331125.       13763475.
      2329525.04     13762625.02
#Sta/Elev= 30
  4109.8  488.74  4164.8   485.7  4280.6  472.68  4508.3   456.4  4835.5  445.03
  4850.3  446.58  4899.7  449.23  4957.5  447.96  4961.4  439.79    4962  439.29
  4995.3  439.79  4996.8  443.09  5002.8  443.09  5008.1  447.16  5022.6  448.13
  5249.5  449.07  5354.2  449.64  5436.4  446.98  5628.6  449.96  5738.5  454.53
  5859.1  454.91  5886.7  458.83  5917.2  453.62    5979   453.6  6007.3  453.48
  6034.9  456.94  6215.5  459.66  6687.2  474.42  6743.8  479.75  6811.7  480.39
#Mann= 8 ,-1 , 0
  4109.8     .07       0  4164.8     .05       0  4850.3      .1       0
  4961.4     .05       0  4995.3      .1       0  5249.5     .05       0
    5979     .07       0  6215.5     .05       0
Bank Sta=4961.4,4995.3
XS Rating Curve= 0 ,0
Exp/Cntr=0.3,0.1

Type RM Length L Ch R = 1 ,41638   ,484,484,484
BEGIN DESCRIPTION:
Mill Creek 42.0
END DESCRIPTION:
XS GIS Cut Line= 3
      2331625.01     13763725.04        2331425.       13763125.
      2330575.02     13762575.01
#Sta/Elev= 30
  4363.3  466.79    4532  457.74  4574.2  454.17  4664.3  449.86  4721.7  446.68
  4763.9  446.93  4806.1  445.42  4873.9  447.91  4899.6  448.24  4974.7  448.31
  4985.3  446.42  4992.3  438.66    4993  438.16  5026.3  438.66  5031.5  446.68
  5039.7  447.68  5169.5  447.72  5190.4  447.98  5278.4  448.83  5305.5  446.45
  5352.9  448.38  5389.2  447.97  5603.3  449.57  5746.7  454.43    5770  457.15
  5792.2  455.53  5841.5  458.99  5885.7  460.36  5922.1  462.48  6008.2  464.72
#Mann= 11 ,-1 , 0
  4363.3     .05       0  4664.3     .12       0  4873.9     .05       0
  4899.6      .1       0  4992.3     .05       0  5026.3      .1       0
  5169.5     .07       0  5190.4     .05       0  5352.9     .07       0
  5389.2     .05       0  5885.7     .07       0
Bank Sta=4992.3,5026.3
XS Rating Curve= 0 ,0
Exp/Cntr=0.3,0.1

Type RM Length L Ch R = 1 ,41154   ,656,656,656
BEGIN DESCRIPTION:
B19406
END DESCRIPTION:
XS GIS Cut Line= 4
      2331725.46      13763914.7      2331786.95     13763097.72
      2331461.92      13762421.3      2330284.79     13761437.44
#Sta/Elev= 30
  3766.4  473.95  3876.4  466.93  4277.5  450.13  4478.1  445.32  4508.2  441.14
  4528.8  445.46  4635.7  448.09  4919.2  447.87  4948.7  447.62  4988.1  443.87
  4992.9  437.15  4993.7  436.65  5027.7  437.15  5032.5  446.43  5039.2   448.4
  5076.5  448.13  5085.3  448.02  5189.6  448.55  5512.4   456.4  5607.8  455.04
  5665.1  447.02    5708  447.48    5764  457.48  5792.6  454.85  5828.1  454.95
    6304  457.95  6531.7   463.6  6587.7  460.61    6670  464.78  6870.3  467.51
#Mann= 13 ,-1 , 0
  3766.4     .05       0  4528.8     .07       0  4635.7     .12       0
  4919.2      .1       0  4992.9     .05       0  5027.7      .1       0
  5076.5     .12       0  5085.3     .07       0  5189.6     .05       0
  5512.4     .07       0  5828.1     .05       0  6531.7     .12       0
    6670     .07       0
Bank Sta=4992.9,5027.7
XS Rating Curve= 0 ,0
Exp/Cntr=0.3,0.1

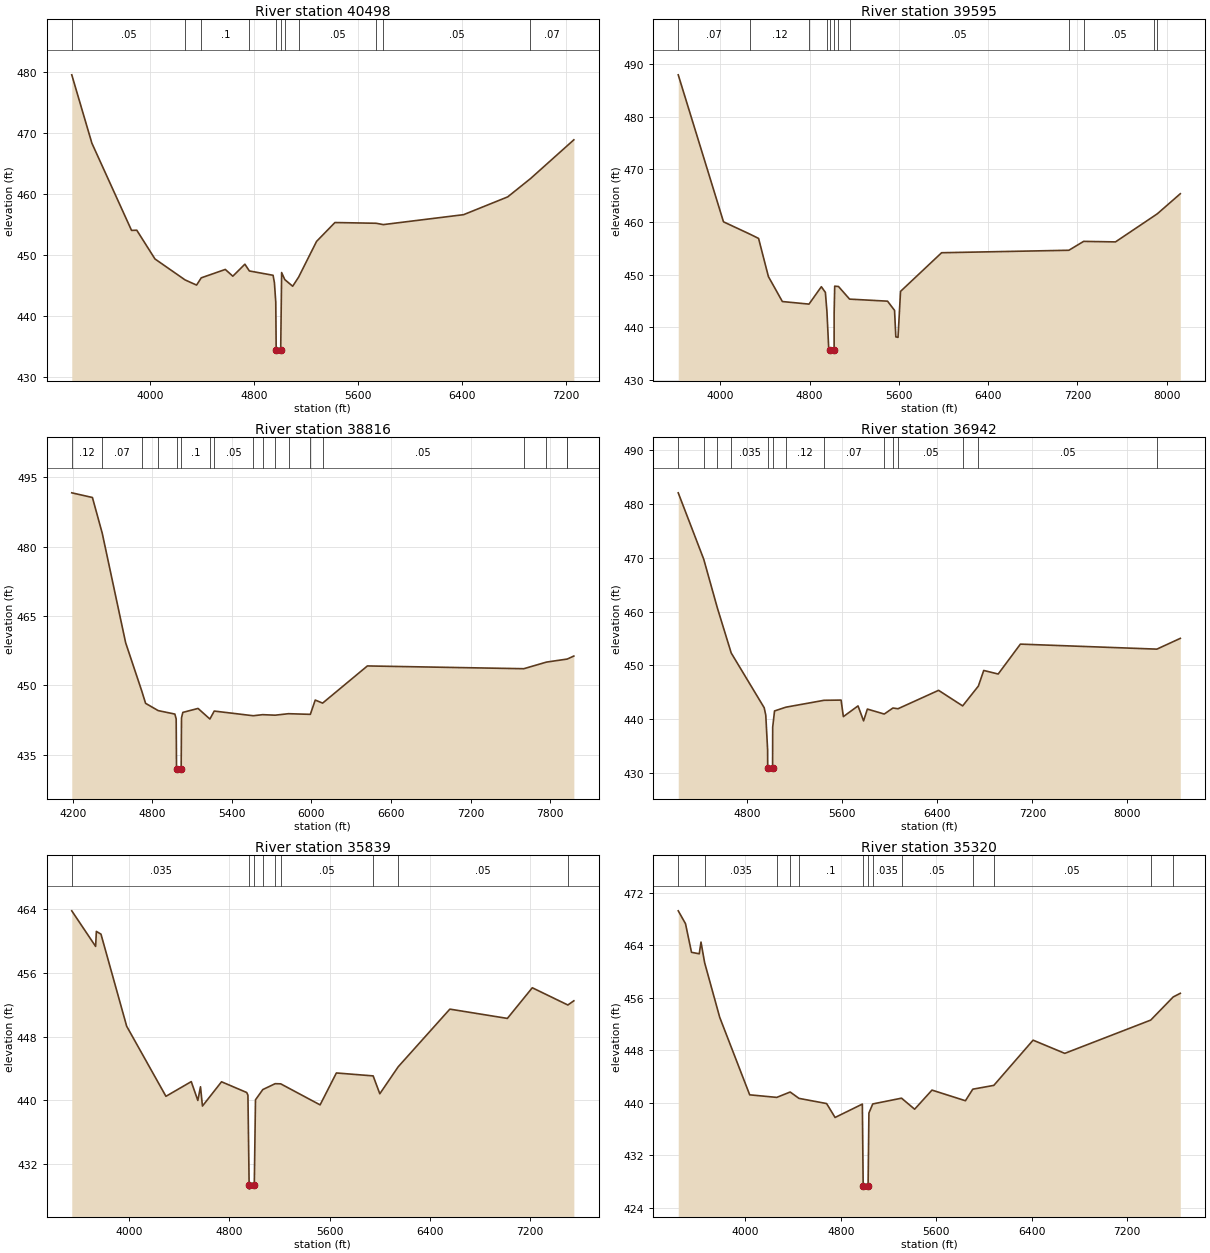
Type RM Length L Ch R = 1 ,40498   ,903,903,903
BEGIN DESCRIPTION:
Mill Creek 41.0
END DESCRIPTION:
XS GIS Cut Line= 3
      2331775.01     13764024.98        2332175.       13762475.
        2330575.       13760875.
#Sta/Elev= 30
  3398.7   479.6  3553.6  468.37  3858.6  454.06  3898.9  454.09    4039  449.37
  4270.6  445.93  4359.1  445.08  4395.1  446.27  4580.2  447.65    4638  446.54
  4730.9  448.51  4765.2   447.4  4947.8  446.69  4958.1  445.47  4968.5  442.29
  4971.7  434.41  4972.5  433.91  5006.5  434.41  5013.6  447.14  5037.7  445.99
  5098.5  444.89  5144.1  446.38  5282.3  452.25  5423.7  455.35  5741.3  455.23
  5795.7  455.01  6413.7  456.64  6753.1  459.56  6928.6  462.56  7262.2  468.93
#Mann= 11 ,-1 , 0
  3398.7     .05       0  4270.6     .07       0  4395.1      .1       0
  4765.2     .12       0  4971.7     .05       0  5006.5     .12       0
  5037.7     .07       0  5144.1     .05       0  5741.3    .035       0
  5795.7     .05       0  6928.6     .07       0
Bank Sta=4971.7,5006.5
XS Rating Curve= 0 ,0
Exp/Cntr=0.3,0.1

Type RM Length L Ch R = 1 ,39595   ,779,779,779
BEGIN DESCRIPTION:
B19405
END DESCRIPTION:
XS GIS Cut Line= 4
      2332612.71     13764204.59      2332893.82     13762570.64
      2332691.77     13761990.85      2330864.57     13760717.08
#Sta/Elev= 30
  3622.2  487.99  4027.7  460.04  4263.3  457.71  4342.2  456.88  4430.2  449.63
  4555.3  444.88    4794  444.39  4904.6   447.7  4940.9  446.62    4955   442.9
  4971.3  435.72  4984.4  435.57  4985.1  435.07  5019.2  435.57  5019.3  442.61
  5024.4   447.8  5058.3  447.74  5157.7  445.34  5497.9  444.95  5560.7   443.2
  5572.1  438.16  5591.8  438.07  5614.4  446.81  5982.3  454.16  7122.8  454.63
  7255.1  456.32  7540.7  456.22  7881.7  461.08  7916.3  461.58  8121.5  465.38
#Mann= 12 ,-1 , 0
  3622.2     .07       0  4263.3     .12       0    4794     .07       0
    4955     .12       0  4984.4     .05       0  5019.2     .12       0
  5058.3     .07       0  5157.7     .05       0  7122.8    .035       0
  7255.1     .05       0  7881.7     .07       0  7916.3     .05       0
Bank Sta=4984.4,5019.2
XS Rating Curve= 0 ,0
Exp/Cntr=0.3,0.1

Type RM Length L Ch R = 1 ,38816   ,1874,1874,1874
BEGIN DESCRIPTION:
B19404
END DESCRIPTION:
XS GIS Cut Line= 4
      2333579.03     13763730.24      2333508.75     13762763.91
      2332858.68     13761999.64      2331382.84     13760945.46
#Sta/Elev= 30
  4192.7  491.62  4348.4  490.61  4422.4  482.89    4599  459.19  4721.3  448.69
  4749.4  446.09  4844.4  444.52    4970  443.77    4980  442.72  4982.6  431.93
  4983.3  431.43  5017.6  431.93  5020.1  442.94  5030.1  444.13  5144.9  444.99
  5234.2   442.7  5266.9  444.42  5560.8  443.41  5631.8  443.64  5726.1  443.53
    5827  443.85  5991.6  443.71  6028.6   446.8  6084.2  446.14  6421.9  454.18
  7601.1  453.58    7772  455.01    7927  455.66  7929.6  455.68  7978.6  456.32
#Mann= 18 ,-1 , 0
  4192.7     .12       0  4422.4     .07       0  4721.3     .12       0
  4844.4      .1       0  4982.6     .05       0  5017.6      .1       0
  5234.2     .12       0  5266.9     .05       0  5560.8     .12       0
  5631.8     .05       0  5726.1     .12       0    5827     .05       0
  5991.6    .035       0  6084.2     .05       0  7601.1    .035       0
    7772     .05       0    7927     .07       0  7929.6     .05       0
Bank Sta=4982.6,5017.6
XS Rating Curve= 0 ,0
Exp/Cntr=0.3,0.1

Type RM Length L Ch R = 1 ,36942   ,1103,1103,1103
BEGIN DESCRIPTION:
B19403
END DESCRIPTION:
XS GIS Cut Line= 4
      2335204.23     13763018.68      2334316.94      13762482.8
      2332911.39     13761973.28      2331532.59     13760989.68
#Sta/Elev= 30
  4219.3  482.05  4433.8  469.73  4548.7  460.67  4665.2  452.31  4942.7  442.15
    4956  440.77  4971.5  434.33  4972.3  430.88  4973.3  430.38  5013.4  430.88
  5014.2  438.53  5029.7  441.55  5124.8  442.25  5446.6  443.53  5589.9  443.57
  5608.9   440.5  5732.4  442.49  5779.1  439.71    5811   441.9  5953.1  440.98
  6026.3   442.1  6068.5  441.96  6410.2  445.38  6612.9  442.49  6745.1  446.17
  6790.2  449.07  6911.9  448.41  7098.8  453.96  8247.4  453.03  8444.6  455.03
#Mann= 14 ,-1 , 0
  4219.3     .12       0  4433.8    .035       0  4548.7     .07       0
  4665.2    .035       0  4972.3    .035       0  5013.4    .035       0
  5124.8     .12       0  5446.6     .07       0  5953.1     .12       0
  6026.3     .07       0  6068.5     .05       0  6612.9    .035       0
  6745.1     .05       0  8247.4    .035       0
Bank Sta=4972.3,5013.4
XS Rating Curve= 0 ,0
Exp/Cntr=0.3,0.1

Type RM Length L Ch R = 1 ,35839   ,519,519,519
BEGIN DESCRIPTION:
B19402
END DESCRIPTION:
XS GIS Cut Line= 4
      2335309.65     13762500.39      2334308.16     13761894.22
        2333825.     13761859.08      2331655.22     13760963.06
#Sta/Elev= 30
    3545  463.83  3735.2  459.35  3741.1  461.24  3777.9  460.89  3982.9  449.29
  4295.8  440.47  4497.6  442.32  4549.9  439.95  4571.3  441.67  4586.8  439.24
  4738.9   442.3  4939.4  440.95  4949.4  440.62    4959  429.28    4960  428.78
  5000.1  429.28  5009.6  440.03    5068  441.32  5166.5  442.06  5210.7  442.04
  5524.7  439.39  5654.5  443.41  5947.7  443.04  6000.7  440.79  6146.9  444.18
    6559  451.45  7017.7  450.28  7216.4  454.14  7499.9  451.97  7547.6   452.5
#Mann= 9 ,-1 , 0
    3545    .035       0    4959     .05       0  5000.1    .035       0
    5068    .035       0  5166.5     .07       0  5210.7     .05       0
  5947.7    .035       0  6146.9     .05       0  7499.9    .035       0
Bank Sta=4959,5000.1
XS Rating Curve= 0 ,0
Exp/Cntr=0.3,0.1

Type RM Length L Ch R = 1 ,35320   ,664,664,664
BEGIN DESCRIPTION:
B19401
END DESCRIPTION:
XS GIS Cut Line= 4
      2335309.62     13762245.62       2334167.6     13761411.06
      2333807.43     13761349.57      2331471.58     13760699.75
#Sta/Elev= 30
  3439.3  469.28  3500.2  467.32  3550.4  462.96  3615.3  462.73  3629.9  464.52
  3660.3  461.38  3786.7  453.05  4037.7  441.24  4264.3  440.85  4376.7  441.67
  4450.3   440.7  4681.7  439.91  4752.8  437.79  4981.1  439.83    4988  427.37
    4989  426.87  5029.1  427.37  5036.1  438.47  5068.1  439.85  5309.3  440.73
  5418.9  439.05  5564.2  441.96  5844.4  440.34  5905.8   442.1  6082.1  442.68
  6410.8  449.57  6676.3  447.56  7396.1  452.63  7584.4  456.16  7643.7  456.71
#Mann= 13 ,-1 , 0
  3439.3     .07       0  3660.3    .035       0  4264.3     .07       0
  4376.7    .035       0  4450.3      .1       0    4988     .05       0
  5029.1      .1       0  5068.1    .035       0  5309.3     .05       0
  5905.8    .035       0  6082.1     .05       0  7396.1    .035       0
  7584.4     .05       0
Bank Sta=4988,5029.1
XS Rating Curve= 0 ,0
Exp/Cntr=0.3,0.1

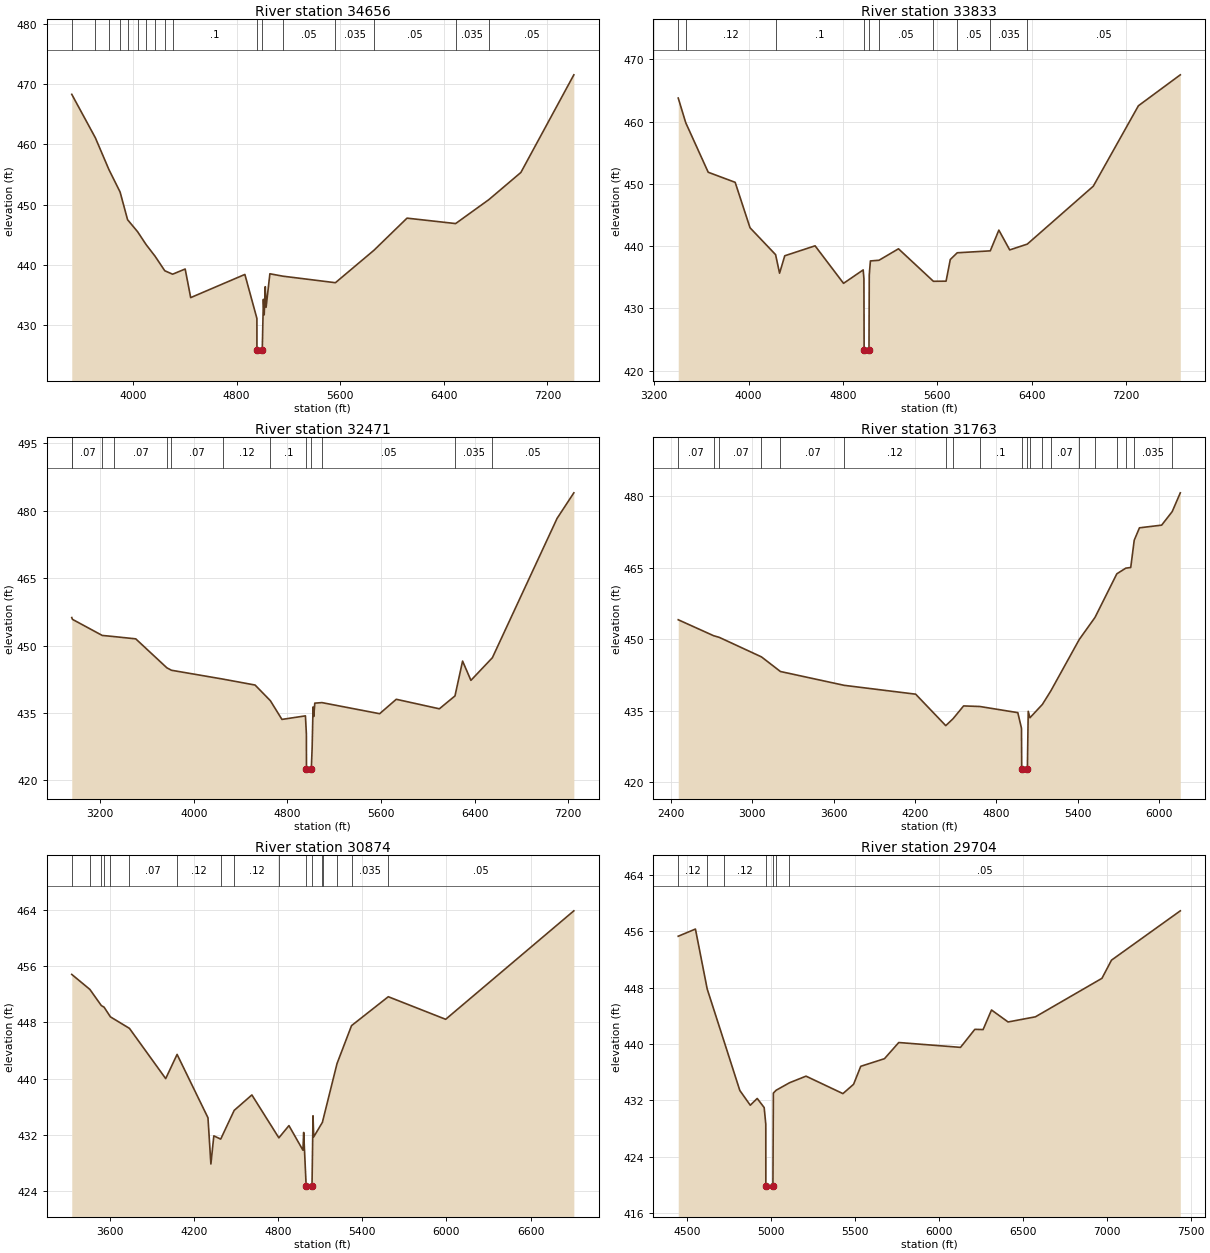
Type RM Length L Ch R = 1 ,34656   ,823,823,823
BEGIN DESCRIPTION:
B19400
END DESCRIPTION:
XS GIS Cut Line= 3
      2335327.17     13762148.97      2334422.36     13761129.95
       2332401.9     13759636.57
#Sta/Elev= 30
  3528.4   468.3  3710.4   461.1  3815.6  455.81  3901.4  452.11  3959.1  447.52
  4036.5  445.53  4102.7  443.38  4171.7  441.46  4246.3  439.06  4306.9  438.49
  4403.7  439.35  4446.3  434.61  4864.5  438.45  4957.3  431.16  4957.6  425.91
  4958.6  425.41  4998.7  425.91  5007.4  434.33  5013.6  431.75    5022  436.42
  5028.3     433  5057.5  438.56  5158.5  438.16  5563.3  437.08  5860.5  442.45
    6116  447.78  6491.1  446.88  6747.8  450.85  6994.8  455.35  7403.6  471.53
#Mann= 17 ,-1 , 0
  3528.4     .07       0  3710.4     .12       0  3815.6    .035       0
  3901.4     .07       0  3959.1    .035       0  4036.5     .07       0
  4102.7    .035       0  4171.7     .07       0  4246.3     .12       0
  4306.9      .1       0  4957.6     .05       0  4998.7      .1       0
  5158.5     .05       0  5563.3    .035       0  5860.5     .05       0
  6491.1    .035       0  6747.8     .05       0
Bank Sta=4957.6,4998.7
XS Rating Curve= 0 ,0
Exp/Cntr=0.3,0.1

Type RM Length L Ch R = 1 ,33833   ,1362,1362,1362
BEGIN DESCRIPTION:
B19399
END DESCRIPTION:
XS GIS Cut Line= 3
      2335292.03     13762025.97      2334580.48      13760471.1
      2332674.18     13758784.42
#Sta/Elev= 30
  3403.4  463.79  3466.9  459.83  3657.4  451.87  3885.9  450.25  4011.9  442.95
  4228.6  438.63  4262.3  435.65  4306.2  438.45  4563.2  440.05  4804.4  434.02
  4970.9  436.18  4977.1  434.78  4978.9  423.31  4979.9  422.81  5020.1  423.31
  5022.5   435.4  5032.1  437.62  5105.1  437.73  5270.1  439.57  5566.1  434.35
  5673.4  434.37  5709.2  437.85  5767.9  438.93  6048.1  439.24  6120.8  442.57
  6212.8  439.39  6362.2  440.33  6921.2  449.63  7303.5  462.55  7658.7  467.52
#Mann= 10 ,-1 , 0
  3403.4     .07       0  3466.9     .12       0  4228.6      .1       0
  4978.9     .05       0  5020.1      .1       0  5105.1     .05       0
  5566.1     .07       0  5767.9     .05       0  6048.1    .035       0
  6362.2     .05       0
Bank Sta=4978.9,5020.1
XS Rating Curve= 0 ,0
Exp/Cntr=0.3,0.1

Type RM Length L Ch R = 1 ,32471   ,708,708,708
BEGIN DESCRIPTION:
B19398
END DESCRIPTION:
XS GIS Cut Line= 4
      2335309.61     13761841.54       2335256.9     13760330.55
      2334615.62     13759873.74      2333113.44     13758564.82
#Sta/Elev= 30
  2956.8  456.25  2962.7  455.85  3217.3  452.27  3315.9  452.02  3503.7  451.51
  3769.8  445.06  3808.9  444.52  4247.1  442.56  4523.8  441.23  4654.2  437.75
  4753.4  433.58  4954.1  434.37  4962.2  430.37  4963.1  422.57  4964.1  422.07
  5004.3  422.57  5011.3  427.11  5019.3  436.35  5025.4  434.24  5034.1   437.2
  5095.4  437.32  5588.5  434.85  5730.7  438.06    6099  435.94  6232.5  438.81
  6297.5  446.56  6368.7  442.27  6552.1  447.31  7105.4  478.33  7248.5  484.01
#Mann= 13 ,-1 , 0
  2956.8     .12       0  2962.7     .07       0  3217.3     .12       0
  3315.9     .07       0  3769.8     .12       0  3808.9     .07       0
  4247.1     .12       0  4654.2      .1       0  4963.1     .05       0
  5004.3      .1       0  5095.4     .05       0  6232.5    .035       0
  6552.1     .05       0
Bank Sta=4963.1,5004.3
XS Rating Curve= 0 ,0
Exp/Cntr=0.3,0.1

Type RM Length L Ch R = 1 ,31763   ,889,889,889
BEGIN DESCRIPTION:
B19397
END DESCRIPTION:
XS GIS Cut Line= 3
      2335353.53     13761744.84       2335318.4     13759864.96
      2334193.98     13758433.09
#Sta/Elev= 30
  2454.5  454.08  2715.2  450.74  2757.1  450.39  3068.1   446.3  3207.7  443.24
  3678.2  440.34  4204.6  438.49  4426.4   431.9  4479.9  433.34    4558  436.03
  4677.6  435.91  4957.5  434.62  4984.6  431.35  4986.3  422.87  4987.3  422.37
  5028.1  422.87  5034.3   434.9  5046.9  433.55  5138.8  436.35  5201.5  439.21
    5410  449.93  5526.2  454.56  5687.5  463.71  5753.6  464.89  5789.9  465.03
  5815.6  470.74  5854.1  473.34  6017.7   473.9  6095.4  476.73  6155.3  480.67
#Mann= 20 ,-1 , 0
  2454.5     .07       0  2715.2     .12       0  2757.1     .07       0
  3068.1     .12       0  3207.7     .07       0  3678.2     .12       0
  4426.4      .1       0  4479.9     .12       0  4677.6      .1       0
  4986.3     .05       0  5028.1      .1       0  5046.9     .07       0
  5138.8     .05       0  5201.5     .07       0    5410     .05       0
  5526.2     .07       0  5687.5    .035       0  5753.6     .07       0
  5815.6    .035       0  6095.4     .05       0
Bank Sta=4986.3,5028.1
XS Rating Curve= 0 ,0
Exp/Cntr=0.3,0.1

Type RM Length L Ch R = 1 ,30874   ,1170,1170,1170
BEGIN DESCRIPTION:
Mill Creek 38.0
END DESCRIPTION:
XS GIS Cut Line= 3
      2336109.02     13761235.37      2335476.52     13759100.69
      2334589.64      13758082.1
#Sta/Elev= 30
  3330.6   454.8  3459.6  452.67  3541.3  450.37  3560.7  450.15  3605.9  448.77
  3741.6  447.13  3999.8  439.99    4081  443.43    4301  434.42  4321.8  427.85
  4342.7  431.85  4391.7  431.39  4487.6  435.47  4613.8  437.67    4806  431.57
  4877.9  433.31  4977.6  429.81  4982.8  432.34  5000.4  424.78  5001.4  424.28
  5042.2  424.78  5049.3   434.7  5054.5  431.71  5116.7  433.79  5118.4  433.96
  5220.3  442.12  5323.8  447.52  5585.6  451.63  5994.4  448.42  6907.6  463.84
#Mann= 17 ,-1 , 0
  3330.6     .12       0  3459.6     .07       0  3541.3     .12       0
  3560.7     .07       0  3605.9     .12       0  3741.6     .07       0
    4081     .12       0  4391.7      .1       0  4487.6     .12       0
    4806      .1       0  5000.4     .05       0  5042.2      .1       0
  5116.7     .07       0  5118.4      .1       0  5220.3     .07       0
  5323.8    .035       0  5585.6     .05       0
Bank Sta=5000.4,5042.2
XS Rating Curve= 0 ,0
Exp/Cntr=0.3,0.1

Type RM Length L Ch R = 1 ,29704   ,728,728,728
BEGIN DESCRIPTION:
B19396
END DESCRIPTION:
XS GIS Cut Line= 3
      2336706.39     13760409.65      2336513.11     13759689.26
      2334835.23     13758195.86
#Sta/Elev= 30
  4446.3  455.32  4548.8  456.34  4618.9  447.83  4721.6  440.22  4813.3  433.41
  4875.6  431.31    4917  432.27  4958.4  430.98  4968.1  428.62  4968.4  419.89
  4969.4  419.39  5010.6  419.89  5013.3  433.04  5029.8  433.44  5109.2   434.5
  5207.9  435.44  5427.8  432.96  5491.4  434.29    5534  436.84  5675.3  437.92
  5760.6  440.22  6128.5  439.53  6213.8  442.09  6263.1  442.06  6313.3  444.84
    6412  443.14    6575  443.87  6971.4  449.34  7028.2  451.92  7438.4  458.93
#Mann= 7 ,-1 , 0
  4446.3     .12       0  4618.9     .07       0  4721.6     .12       0
  4968.4     .05       0  5010.6     .12       0  5029.8      .1       0
  5109.2     .05       0
Bank Sta=4968.4,5010.6
XS Rating Curve= 0 ,0
Exp/Cntr=0.3,0.1

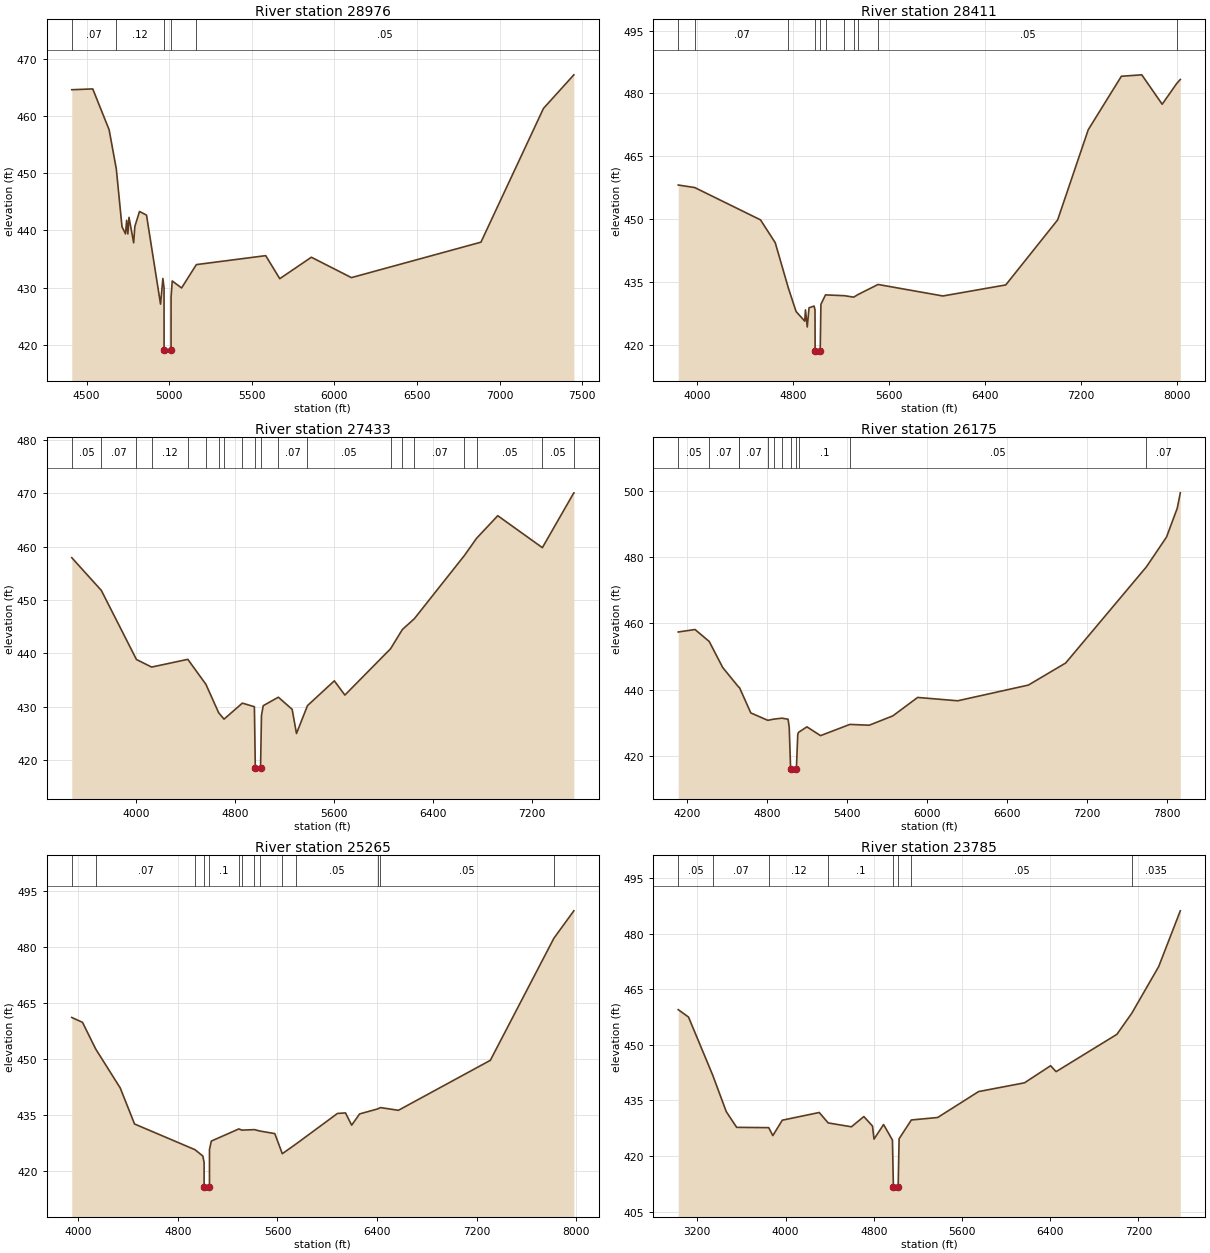
Type RM Length L Ch R = 1 ,28976   ,565,565,565
BEGIN DESCRIPTION:
B19395
END DESCRIPTION:
XS GIS Cut Line= 3
      2337593.64     13760146.08      2336653.67     13759197.32
      2335309.84     13758152.12
#Sta/Elev= 30
  4410.8  464.66  4537.9   464.8  4636.9  457.64  4680.4  450.77  4714.7  440.66
  4735.9  439.41  4742.9  441.79  4750.1   439.4  4757.1   442.3  4785.4  437.84
  4792.4   440.7  4820.7  443.33  4863.1  442.69    4948  427.09  4962.1  431.59
  4969.2  429.93  4969.3  419.01  4970.3  418.51  5011.5  419.01  5011.7  428.34
  5018.7  431.15  5075.3  429.93  5164.7  434.02  5584.4  435.59  5669.3  431.55
  5860.5  435.31    6103  431.74  6886.7  437.95  7264.9  461.38  7448.8  467.27
#Mann= 5 ,-1 , 0
  4410.8     .07       0  4680.4     .12       0  4969.3     .05       0
  5011.5     .12       0  5164.7     .05       0
Bank Sta=4969.3,5011.5
XS Rating Curve= 0 ,0
Exp/Cntr=0.3,0.1

Type RM Length L Ch R = 1 ,28411   ,978,978,978
BEGIN DESCRIPTION:
B19394
END DESCRIPTION:
XS GIS Cut Line= 3
      2337971.39     13760172.45      2337215.89     13759047.98
      2335054.82     13757211.95
#Sta/Elev= 30
  3840.7  458.12  3978.1  457.52  4527.5  449.79  4650.5  444.32  4759.2  433.56
  4824.4  427.88  4896.5  425.59  4902.5  428.28  4917.5  424.19  4932.5  428.78
  4974.5  429.19  4982.1  428.28  4983.3  418.44  4984.3  417.94  5025.6  418.44
  5031.5   429.6  5069.8  431.86  5227.9  431.67  5304.9  431.32  5342.3  431.96
  5508.5  434.35  6049.5   431.6  6574.3  434.24  7007.4  449.79  7262.6  471.33
  7539.3  484.12  7709.6  484.46  7879.8  477.43  8001.5  482.41  8031.1  483.34
#Mann= 11 ,-1 , 0
  3840.7     .05       0  3978.1     .07       0  4759.2      .1       0
  4983.3     .05       0  5025.6      .1       0  5069.8     .12       0
  5227.9      .1       0  5304.9     .12       0  5342.3      .1       0
  5508.5     .05       0  8001.5     .07       0
Bank Sta=4983.3,5025.6
XS Rating Curve= 0 ,0
Exp/Cntr=0.3,0.1

Type RM Length L Ch R = 1 ,27433   ,1258,1258,1258
BEGIN DESCRIPTION:
B19393
END DESCRIPTION:
XS GIS Cut Line= 3
      2338199.75     13759592.61      2337048.98     13758248.57
      2335275.04     13756799.56
#Sta/Elev= 30
  3480.9  457.94    3720   451.8    4004  438.85  4126.6  437.43  4419.4  438.88
  4565.8  434.19  4668.6  428.87  4712.2  427.67  4860.6  430.67  4957.7  429.99
  4965.1  418.42  4966.1  417.92  5007.4  418.42  5014.8  428.34    5029  430.19
  5151.4  431.78  5262.9  429.51    5298  424.97  5386.8   430.2    5604  434.85
  5689.3  432.18  6058.9  440.87  6154.5  444.48  6250.8  446.49  6656.5  458.37
  6754.1  461.57  6925.6  465.81  7286.4  459.82  7540.6   470.1  7540.8   470.1
#Mann= 20 ,-1 , 0
  3480.9     .05       0    3720     .07       0    4004     .07       0
  4126.6     .12       0  4419.4     .07       0  4565.8     .12       0
  4668.6     .07       0  4712.2     .12       0  4860.6      .1       0
  4965.1     .05       0  5007.4      .1       0  5151.4     .07       0
  5386.8     .05       0  6058.9     .07       0  6154.5     .05       0
  6250.8     .07       0  6656.5     .07       0  6754.1     .05       0
  7286.4     .05       0  7540.6     .07       0
Bank Sta=4965.1,5007.4
XS Rating Curve= 0 ,0
Exp/Cntr=0.3,0.1

Type RM Length L Ch R = 1 ,26175   ,910,910,910
BEGIN DESCRIPTION:
B19392
END DESCRIPTION:
XS GIS Cut Line= 3
      2338234.93     13759434.54      2337742.97     13758108.02
      2336338.13     13756229.04
#Sta/Elev= 30
  4137.1   457.4  4262.8  458.15  4369.2  454.54  4470.1  446.69  4588.8  440.81
  4595.6  440.65  4680.6  432.97  4807.9  430.73  4851.3  431.08    4914  431.38
  4959.9  431.06  4968.5   428.6  4979.1  415.89  4980.1  415.39    5022  415.89
  5032.5  426.51  5038.8  427.12  5101.1  428.76  5203.2  426.11    5423   429.5
  5567.7  429.25  5744.9  432.08  5930.4  437.64  6230.5  436.63  6759.9  441.37
  7039.2  448.03  7644.6   477.1  7794.7  486.06    7875  494.76    7898  499.42
#Mann= 12 ,-1 , 0
  4137.1     .05       0  4369.2     .07       0  4588.8     .12       0
  4595.6     .07       0  4807.9     .12       0  4851.3     .07       0
    4914     .12       0  4979.1     .05       0    5022     .12       0
  5038.8      .1       0    5423     .05       0  7644.6     .07       0
Bank Sta=4979.1,5022
XS Rating Curve= 0 ,0
Exp/Cntr=0.3,0.1

Type RM Length L Ch R = 1 ,25265   ,1480,1480,1480
BEGIN DESCRIPTION:
B19391
END DESCRIPTION:
XS GIS Cut Line= 4
      2338270.06     13759267.59      2338691.72     13758608.75
      2338410.61      13758116.8       2336654.7     13756088.74
#Sta/Elev= 30
  3948.6  461.17  4034.8  459.87  4140.7  452.72  4337.8  442.27  4452.8  432.61
  4937.7  425.73  5001.1  424.02  5011.1   422.3  5011.3  415.65  5012.3  415.15
  5054.2  415.65  5054.3  425.75  5069.1  428.03  5290.4  431.29  5313.9  430.97
  5415.1   431.1  5459.4  430.72  5578.8  430.04  5639.1  424.65  5745.2  427.15
  6082.2  435.44  6146.3  435.58  6196.2   432.3  6259.8  435.31  6404.4  436.65
  6427.5  437.01  6571.3  436.28  7309.4  449.68  7819.8  482.41    7980  489.76
#Mann= 14 ,-1 , 0
  3948.6     .05       0  4140.7     .07       0  4937.7      .1       0
  5011.3     .05       0  5054.2      .1       0  5290.4     .07       0
  5313.9     .05       0  5415.1     .07       0  5459.4     .05       0
  5639.1     .07       0  5745.2     .05       0  6404.4     .07       0
  6427.5     .05       0  7819.8    .035       0
Bank Sta=5011.3,5054.2
XS Rating Curve= 0 ,0
Exp/Cntr=0.3,0.1

Type RM Length L Ch R = 1 ,23785   ,1734,1734,1734
BEGIN DESCRIPTION:
B19390
END DESCRIPTION:
XS GIS Cut Line= 4
        2338314.     13759293.92      2338920.12     13758468.19
      2338805.92     13757405.24      2336811.78     13755964.54
#Sta/Elev= 30
  3026.6  459.48  3119.8  457.49  3338.6  441.86  3462.4  431.95  3556.5  427.72
  3847.5  427.64  3884.6  425.49  3970.2  429.65  4305.6  431.73  4386.3  428.92
  4597.2  427.87  4710.1  430.63  4788.3  428.08  4802.2  424.55  4888.9  428.48
  4969.4  424.28    4978  411.55    4979  411.05  5021.1  411.55  5029.7  424.64
  5140.6  429.71  5379.5  430.38  5750.3  437.37  6167.1  439.74  6403.8  444.35
  6453.5  442.75  7004.9  452.82  7140.8  458.55  7383.9   471.1  7580.1  486.15
#Mann= 8 ,-1 , 0
  3026.6     .05       0  3338.6     .07       0  3847.5     .12       0
  4386.3      .1       0    4978     .05       0  5021.1      .1       0
  5140.6     .05       0  7140.8    .035       0
Bank Sta=4978,5021.1
XS Rating Curve= 0 ,0
Exp/Cntr=0.3,0.1