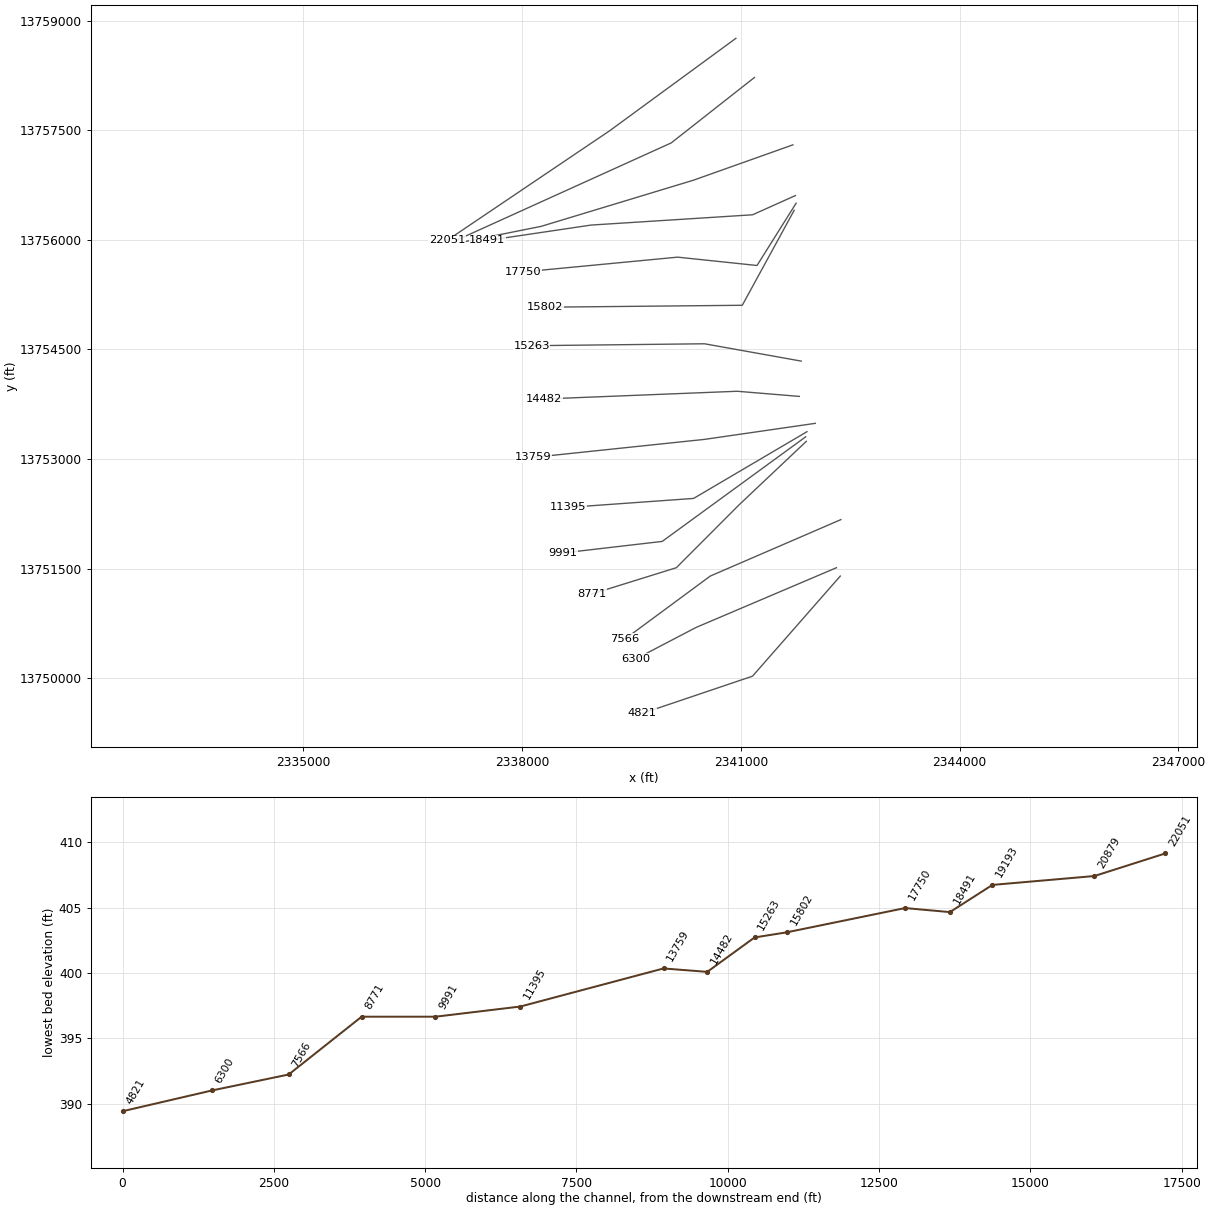
HEC-RAS study Mill Creek.prj: Mill Creek Base Level Engineering

--- Mill Creek.g01 (geometry) --- (continued)

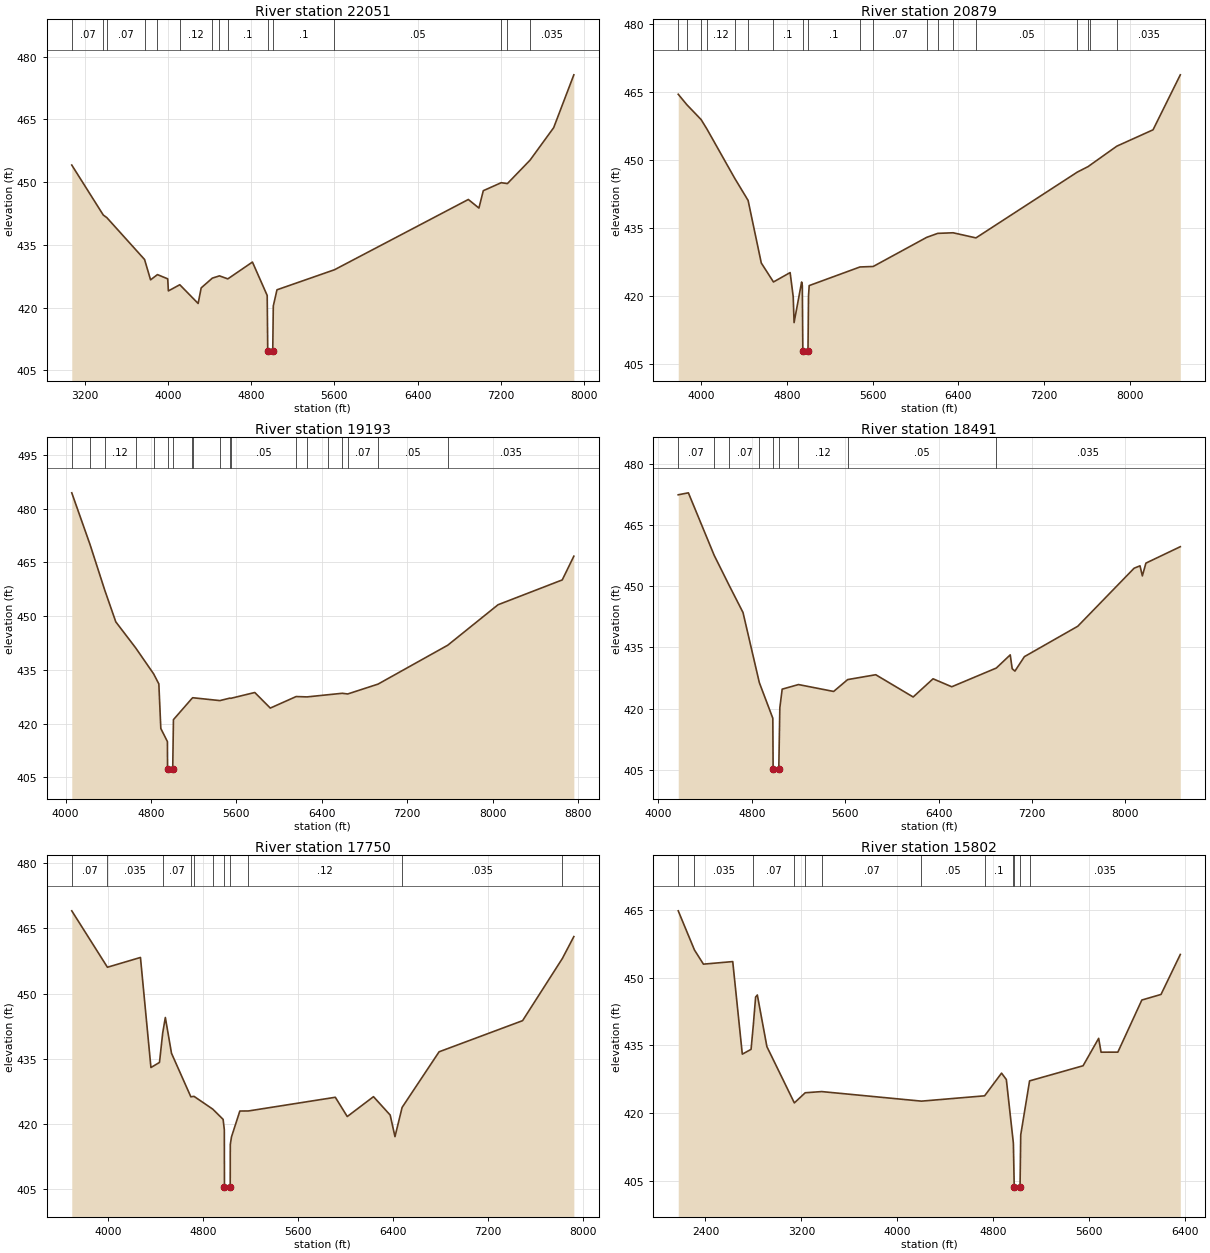
Type RM Length L Ch R = 1 ,22051   ,1172,1172,1172
BEGIN DESCRIPTION:
B19389
END DESCRIPTION:
XS GIS Cut Line= 3
      2340931.82     13758758.09      2339201.23     13757493.09
      2336969.99     13755990.96
#Sta/Elev= 30
  3071.6   454.1  3375.3  442.14  3408.9  441.54  3772.5  431.52  3830.2  426.66
  3896.5  427.91  3995.4   426.9  4001.6  424.01  4111.5  425.49  4288.1  421.01
  4317.4  424.73  4424.8  427.07  4493.6  427.61    4574  426.89  4810.9  430.91
    4953  422.92  4958.2  409.64  4959.2  409.14  5006.4  409.64  5011.7  420.41
  5047.2  424.28  5600.6  429.07  6889.2  445.87  6991.2  443.82  7033.2  447.97
  7205.8  449.88  7265.5  449.67  7483.7  455.28  7710.9  463.04    7905  475.67
#Mann= 15 ,-1 , 0
  3071.6     .07       0  3375.3     .12       0  3408.9     .07       0
  3772.5     .12       0  3896.5     .07       0  4111.5     .12       0
  4424.8      .1       0  4493.6     .12       0    4574      .1       0
  4958.2     .05       0  5006.4      .1       0  5600.6     .05       0
  7205.8     .07       0  7265.5     .05       0  7483.7    .035       0
Bank Sta=4958.2,5006.4
XS Rating Curve= 0 ,0
Exp/Cntr=0.3,0.1

Type RM Length L Ch R = 1 ,20879   ,1686,1686,1686
BEGIN DESCRIPTION:
B19388
END DESCRIPTION:
XS GIS Cut Line= 3
      2341186.54      13758222.2      2340044.56     13757326.18
      2337092.88      13755990.9
#Sta/Elev= 30
  3783.5  464.56  3863.3  462.27  3997.3  458.97  4052.2  456.86  4310.5  446.04
  4436.3  441.12  4559.6   427.3  4673.3  423.12    4829  425.19  4857.9  419.84
  4865.9  414.15  4936.5  423.11  4942.9  422.34  4947.7  407.91  4948.7  407.41
  4995.9  407.91  5000.7  420.02  5007.1  422.32  5481.5  426.43  5605.3  426.54
  6104.2  432.96  6208.4  433.85    6352  433.98  6565.3  432.85  7512.7  447.38
  7613.9   448.6  7631.9  448.91  7881.4   453.1  8219.9  456.71  8474.7  468.85
#Mann= 19 ,-1 , 0
  3783.5     .07       0  3863.3     .12       0  3997.3     .07       0
  4052.2     .12       0  4310.5     .07       0  4436.3     .12       0
  4673.3      .1       0  4947.7     .05       0  4995.9      .1       0
  5481.5     .12       0  5605.3     .07       0  6104.2    .035       0
  6208.4     .05       0    6352    .035       0  6565.3     .05       0
  7512.7     .07       0  7613.9     .05       0  7631.9     .07       0
  7881.4    .035       0
Bank Sta=4947.7,4995.9
XS Rating Curve= 0 ,0
Exp/Cntr=0.3,0.1

Type RM Length L Ch R = 1 ,19193   ,702,702,702
BEGIN DESCRIPTION:
B19387
END DESCRIPTION:
XS GIS Cut Line= 4
      2341713.64     13757299.83      2340352.02     13756816.67
      2338261.27     13756184.17      2337208.55     13755973.63
#Sta/Elev= 30
  4058.4  484.38  4230.2  469.89  4367.1  457.25  4470.8  448.38  4657.1  441.11
  4825.1  433.87    4874  431.07  4892.5  418.63  4954.3  414.97  4955.6  407.23
  4956.6  406.73    5004  407.23  5010.7  421.09  5181.9  426.94  5190.9  427.21
  5445.5  426.41  5539.3   427.1  5548.3  427.04  5772.5  428.67    5918  424.32
  6160.2  427.54  6262.1  427.44    6457  428.04  6592.1  428.45  6643.3  428.26
  6927.3  431.01    7580  441.86  8050.9  453.15  8652.5  460.08  8761.1   466.7
#Mann= 19 ,-1 , 0
  4058.4    .035       0  4230.2     .07       0  4367.1     .12       0
  4657.1     .07       0  4825.1     .12       0  4955.6     .05       0
    5004     .12       0  5181.9     .12       0  5190.9      .1       0
  5445.5     .12       0  5539.3      .1       0  5548.3     .05       0
  6160.2    .035       0  6262.1     .05       0    6457     .07       0
  6592.1     .05       0  6643.3     .07       0  6927.3     .05       0
    7580    .035       0
Bank Sta=4955.6,5004
XS Rating Curve= 0 ,0
Exp/Cntr=0.3,0.1

Type RM Length L Ch R = 1 ,18491   ,741,741,741
BEGIN DESCRIPTION:
B19386
END DESCRIPTION:
XS GIS Cut Line= 4
      2341748.78     13756605.83      2341160.21      13756342.3
      2338946.47     13756201.74      2337523.38     13755990.91
#Sta/Elev= 30
  4169.6  472.42  4256.6   472.9  4477.2   457.6  4608.3  450.07  4724.6  443.55
  4864.6  426.34    4980  417.62  4982.6  405.15  4983.6  404.65  5031.1  405.15
  5040.1  420.19  5060.2  424.75  5199.9  425.88  5501.1  424.19  5621.2   427.1
  5861.8  428.29  6182.4  422.83  6352.8  427.29  6513.1  425.34  6894.8  429.93
  7014.1  433.16  7030.9  429.76  7054.4  429.18  7135.3  432.72  7592.8  440.18
  8075.4  454.41  8125.9     455  8146.2  452.53  8176.5  455.66  8471.3  459.69
#Mann= 9 ,-1 , 0
  4169.6     .07       0  4477.2    .035       0  4608.3     .07       0
  4864.6      .1       0  4982.6     .05       0  5031.1      .1       0
  5199.9     .12       0  5621.2     .05       0  6894.8    .035       0
Bank Sta=4982.6,5031.1
XS Rating Curve= 0 ,0
Exp/Cntr=0.3,0.1

Type RM Length L Ch R = 1 ,17750   ,1948,1948,1948
BEGIN DESCRIPTION:
B19385
END DESCRIPTION:
XS GIS Cut Line= 4
      2341757.56     13756500.39      2341221.71     13755648.31
       2340132.4     13755762.51      2338015.27     13755560.46
#Sta/Elev= 30
  3691.9  469.04  3992.3  456.05  4270.4   458.3  4358.7  432.96  4430.7  434.13
  4457.8  440.93    4480  444.48  4531.9  436.24  4694.8  426.22  4721.6  426.32
  4879.3  423.38  4966.6  421.02  4976.7  418.64  4977.9  405.46  4978.9  404.96
  5026.4  405.46    5027  415.22    5037  416.98  5107.4  422.94  5180.3  422.96
  5911.7  426.11  6012.1  421.67  6233.1  426.25  6373.8  422.01    6414  417.04
  6474.2  423.78  6785.6  436.58  7488.8  443.75  7824.3  458.09  7920.5  463.11
#Mann= 11 ,-1 , 0
  3691.9     .07       0  3992.3    .035       0  4457.8     .07       0
  4694.8     .12       0  4721.6     .07       0  4879.3      .1       0
  4977.9     .05       0  5026.4      .1       0  5180.3     .12       0
  6474.2    .035       0  7824.3     .07       0
Bank Sta=4977.9,5026.4
XS Rating Curve= 0 ,0
Exp/Cntr=0.3,0.1

Type RM Length L Ch R = 1 ,15802   ,539,539,539
BEGIN DESCRIPTION:
B19384
END DESCRIPTION:
XS GIS Cut Line= 3
      2341731.21     13756403.78      2341019.66     13755103.66
      2338313.99      13755077.3
#Sta/Elev= 30
    2173  464.85  2308.4  456.16  2383.2  453.02  2627.6  453.59  2707.4  433.05
  2780.5  434.12  2799.3  439.51  2818.5  445.73  2832.8  446.18  2912.6  434.72
  3141.4  422.24  3232.3  424.49  3369.5  424.75  4201.6  422.63  4728.6  423.81
  4869.8  428.84  4909.8  427.42  4968.6  413.27  4975.5  403.61  4976.5  403.11
  5024.1  403.61  5029.8  415.14  5103.6  427.12  5549.9  430.48  5679.9  436.56
  5699.9  433.49  5839.9   433.5  6039.9  445.06  6199.9   446.3  6360.9  455.17
#Mann= 12 ,-1 , 0
    2173     .07       0  2308.4    .035       0  2799.3     .07       0
  3141.4      .1       0  3232.3     .12       0  3369.5     .07       0
  4201.6     .05       0  4728.6      .1       0  4968.6     .12       0
  4975.5     .05       0  5024.1     .12       0  5103.6    .035       0
Bank Sta=4975.5,5024.1
XS Rating Curve= 0 ,0
Exp/Cntr=0.3,0.1

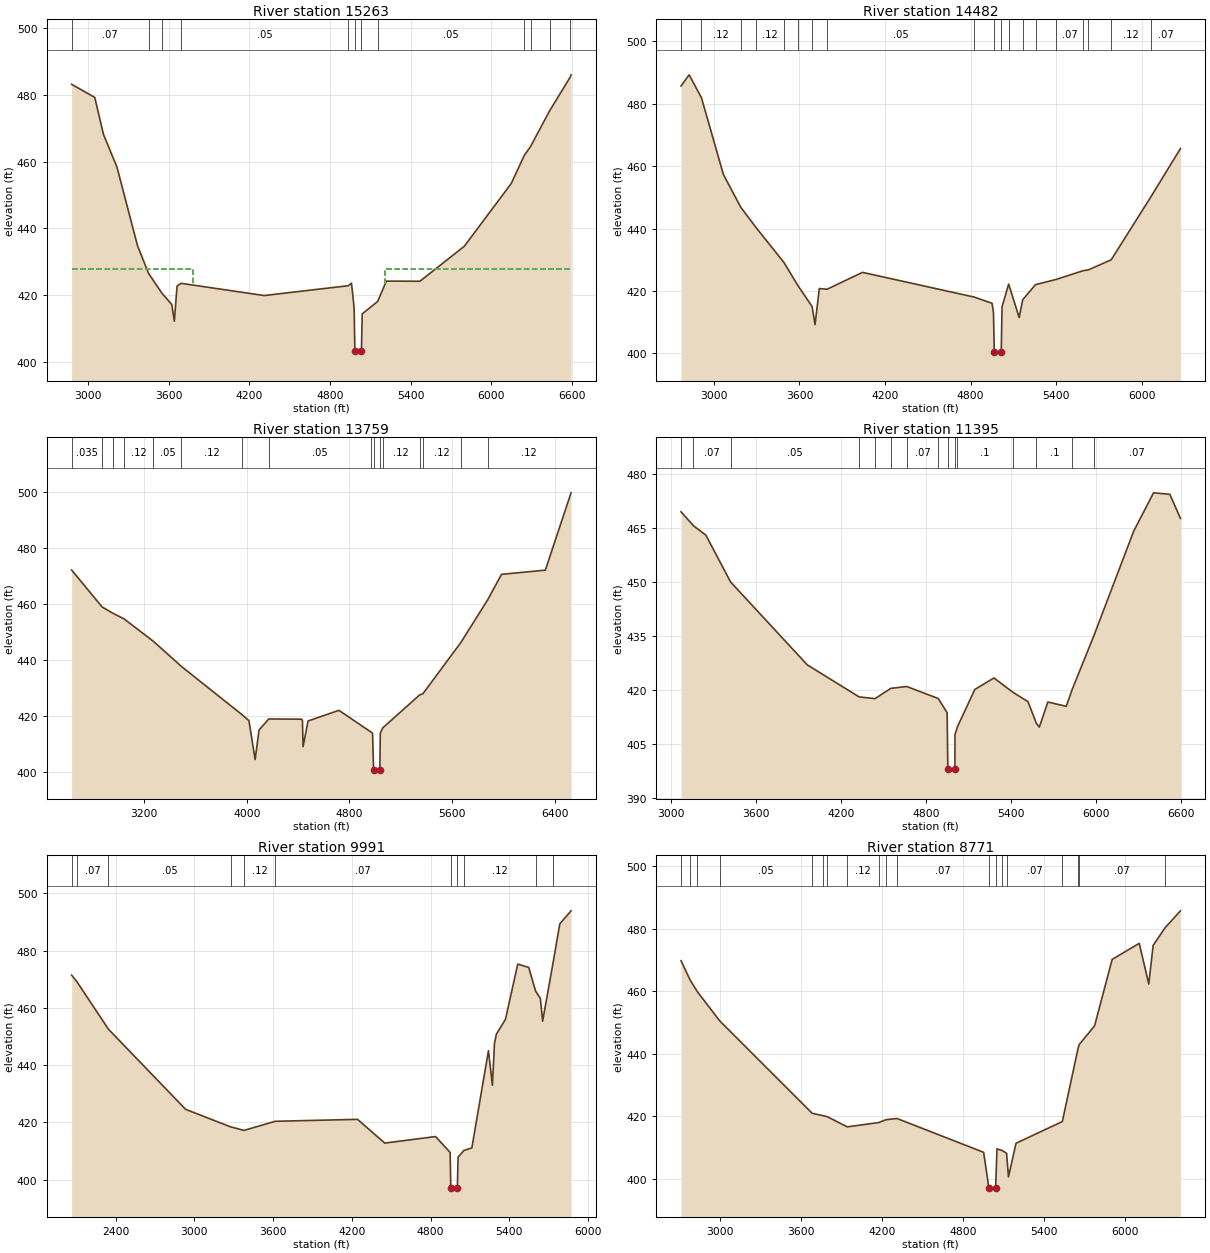
Type RM Length L Ch R = 1 ,15263   ,781,781,781
BEGIN DESCRIPTION:
Mill Creek 21.0
END DESCRIPTION:
XS GIS Cut Line= 3
      2341827.83     13754339.39      2340501.36     13754576.57
      2338129.72     13754550.22
#Sta/Elev= 30
  2876.2  483.15  3048.4  479.23  3112.7  468.24  3214.3  458.31  3366.7  434.88
  3448.7   426.6  3549.3  420.61    3622  417.26    3641  412.27  3661.3  422.74
  3690.5   423.6  4310.1  419.94  4936.4  422.88  4960.1  423.62  4970.1   420.2
  4980.1  416.03  4985.8  403.21  4986.8  402.71  5034.5  403.21  5040.1  414.46
  5155.1  418.16  5220.1  424.26  5470.1  424.22  5800.2  434.67  6150.2  453.46
  6247.1  461.87  6293.8  464.52  6435.6  475.19    6590  485.34  6595.5  485.98
#Mann= 12 ,-1 , 0
  2876.2     .07       0  3448.7     .12       0  3549.3      .1       0
  3690.5     .05       0  4936.4      .1       0  4985.8     .05       0
  5034.5      .1       0  5155.1     .05       0  6247.1     .07       0
  6293.8     .05       0  6435.6    .035       0    6590     .05       0
#XS Ineff= 2 , 0
       0    3780     428    5210       0   427.9
Permanent Ineff=
       F       F
Bank Sta=4985.8,5034.5
XS Rating Curve= 0 ,0
Exp/Cntr=0.3,0.1

Type RM Length L Ch R = 1 ,14482   ,723,723,723
BEGIN DESCRIPTION:
Mill Creek 20.0
END DESCRIPTION:
XS GIS Cut Line= 3
      2341801.53     13753856.23      2340949.38     13753926.51
      2338305.23     13753821.09
#Sta/Elev= 30
  2769.5  485.73  2826.2   489.3  2912.5  481.99    3067   457.3  3189.2  446.79
  3297.4  440.23  3490.8  429.15  3589.8  421.68  3688.5  415.01    3709  409.21
    3739  420.79  3793.7  420.56  4041.6  425.97  4825.7  418.04    4950  416.06
    4960  413.16  4965.7  400.58  4966.7  400.08  5014.4  400.58    5020  414.91
  5066.5  422.21  5140.1  411.52    5165  417.21  5254.8  422.04  5397.8  423.69
  5590.5  426.53  5624.2  426.75  5785.4     430  6064.8  450.27  6270.8  465.67
#Mann= 19 ,-1 , 0
  2769.5     .07       0  2912.5     .12       0  3189.2     .07       0
  3297.4     .12       0  3490.8      .1       0  3589.8     .12       0
  3688.5      .1       0  3793.7     .05       0  4825.7      .1       0
  4965.7     .05       0  5014.4      .1       0  5066.5     .12       0
    5165     .07       0  5254.8     .12       0  5397.8     .07       0
  5590.5     .05       0  5624.2     .07       0  5785.4     .12       0
  6064.8     .07       0
Bank Sta=4965.7,5014.4
XS Rating Curve= 0 ,0
Exp/Cntr=0.3,0.1

Type RM Length L Ch R = 1 ,13759   ,2364,2364,2364
BEGIN DESCRIPTION:
Mill Creek 19.0
END DESCRIPTION:
XS GIS Cut Line= 3
      2342021.16     13753487.28      2340501.36     13753267.66
      2338155.81     13753021.68
#Sta/Elev= 30
  2633.9  472.23    2872  459.02  2953.4  456.84  3041.4  454.81  3270.7  446.78
  3489.8  437.78  3961.8  420.55  4016.3  418.39  4064.8  404.51  4095.1  415.02
  4170.7  418.99  4427.3  418.91  4433.5   418.4  4438.5  409.13  4477.5  418.28
  4718.1  422.07  4969.2  414.28  4980.3  413.82  4988.2  400.84  4989.2  400.34
  5037.1  400.84  5040.6  413.93  5059.9  415.81  5347.2  427.58  5372.6     428
  5667.4  446.24  5877.6  461.57  5985.8   470.7  6327.6   472.2  6527.9  499.84
#Mann= 16 ,-1 , 0
  2633.9    .035       0    2872     .12       0  2953.4     .07       0
  3041.4     .12       0  3270.7     .05       0  3489.8     .12       0
  3961.8      .1       0  4170.7     .05       0  4969.2      .1       0
  4988.2     .05       0  5037.1      .1       0  5059.9     .12       0
  5347.2      .1       0  5372.6     .12       0  5667.4     .07       0
  5877.6     .12       0
Bank Sta=4988.2,5037.1
XS Rating Curve= 0 ,0
Exp/Cntr=0.3,0.1

Type RM Length L Ch R = 1 ,11395   ,1404,1404,1404
BEGIN DESCRIPTION:
B19383
END DESCRIPTION:
XS GIS Cut Line= 3
      2341906.94     13753373.09      2340352.02     13752459.46
      2338630.27     13752336.48
#Sta/Elev= 30
  3069.5  469.54  3157.5  465.67  3245.7  463.02  3419.9  450.02  3961.5  426.99
  4328.1  418.07  4440.4  417.59  4552.6  420.45  4664.9  420.96  4887.4  417.62
  4950.2  413.68  4955.2  397.93  4956.2  397.43  5005.3  397.93  5005.6  407.58
  5023.1  409.77  5145.9  420.14    5281  423.34  5414.2  419.39  5521.6  416.75
  5580.9  410.72  5601.8  409.68    5662  416.65  5792.3  415.45  5833.9  420.14
  5987.9  435.14  6268.8  464.17  6409.1  474.82  6524.2  474.41  6599.1  467.72
#Mann= 15 ,-1 , 0
  3069.5    .035       0  3157.5     .07       0  3419.9     .05       0
  4328.1     .12       0  4440.4     .05       0  4552.6     .12       0
  4664.9     .07       0  4887.4     .12       0  4955.2     .05       0
  5005.3     .12       0  5023.1      .1       0  5414.2     .07       0
  5580.9      .1       0  5833.9     .12       0  5987.9     .07       0
Bank Sta=4955.2,5005.3
XS Rating Curve= 0 ,0
Exp/Cntr=0.3,0.1

Type RM Length L Ch R = 1 ,9991    ,1220,1220,1220
BEGIN DESCRIPTION:
B19382
END DESCRIPTION:
XS GIS Cut Line= 3
      2341889.32     13753302.78      2339921.57     13751870.89
      2338560.01     13751712.77
#Sta/Elev= 30
  2065.7  471.42  2103.1  469.34  2346.2  452.54  2933.9  424.54    3276  418.43
  3378.5  417.18    3617  420.36  4243.7  421.04  4450.8  412.74  4838.1  415.03
  4948.9  409.47    4954  397.15    4955  396.65  5004.2  397.15  5009.3  407.82
  5054.5  410.18  5114.4  411.06  5240.8  445.03    5271  432.97  5286.7  447.59
  5301.2  450.81  5370.3  455.97    5464   475.3  5547.6  474.14  5599.7   465.9
  5636.2  463.32  5653.6  455.38  5736.2  476.57  5784.4  489.37    5870  493.92
#Mann= 11 ,-1 , 0
  2065.7    .035       0  2103.1     .07       0  2346.2     .05       0
    3276     .07       0  3378.5     .12       0    3617     .07       0
    4954     .05       0  5004.2     .07       0  5054.5     .12       0
  5599.7     .07       0  5736.2     .12       0
Bank Sta=4954,5004.2
XS Rating Curve= 0 ,0
Exp/Cntr=0.3,0.1

Type RM Length L Ch R = 1 ,8771    ,1205,1205,1205
BEGIN DESCRIPTION:
B19381
END DESCRIPTION:
XS GIS Cut Line= 4
      2341898.09     13753241.27      2340975.73     13752371.62
      2340114.84     13751510.72      2338955.27     13751150.55
#Sta/Elev= 30
  2708.5  469.77  2775.5  463.62  2829.3  459.85  2995.3  450.49  3679.9  420.93
  3762.5  420.13  3791.9  419.84    3940  416.58  4173.1  417.96    4228  418.88
  4308.3  419.26  4950.1  408.43  4988.7  397.15  4989.7  396.65  5038.9  397.15
  5049.1  409.55  5088.5  408.98  5120.1  408.13    5134  400.58    5190  411.33
    5533  418.28    5649   441.6  5657.7   442.9  5771.9  448.91  5902.2  470.18
  6102.8  475.31  6173.2  462.31  6205.7  474.65  6293.7  480.28  6407.9  485.72
#Mann= 19 ,-1 , 0
  2708.5     .07       0  2775.5     .05       0  2829.3     .07       0
  2995.3     .05       0  3679.9     .07       0  3762.5     .05       0
  3791.9     .07       0    3940     .12       0  4173.1     .07       0
    4228     .12       0  4308.3     .07       0  4988.7     .05       0
  5038.9     .07       0  5088.5      .1       0  5120.1     .07       0
    5533      .1       0    5649     .12       0  5657.7     .07       0
  6293.7    .035       0
Bank Sta=4988.7,5038.9
XS Rating Curve= 0 ,0
Exp/Cntr=0.3,0.1

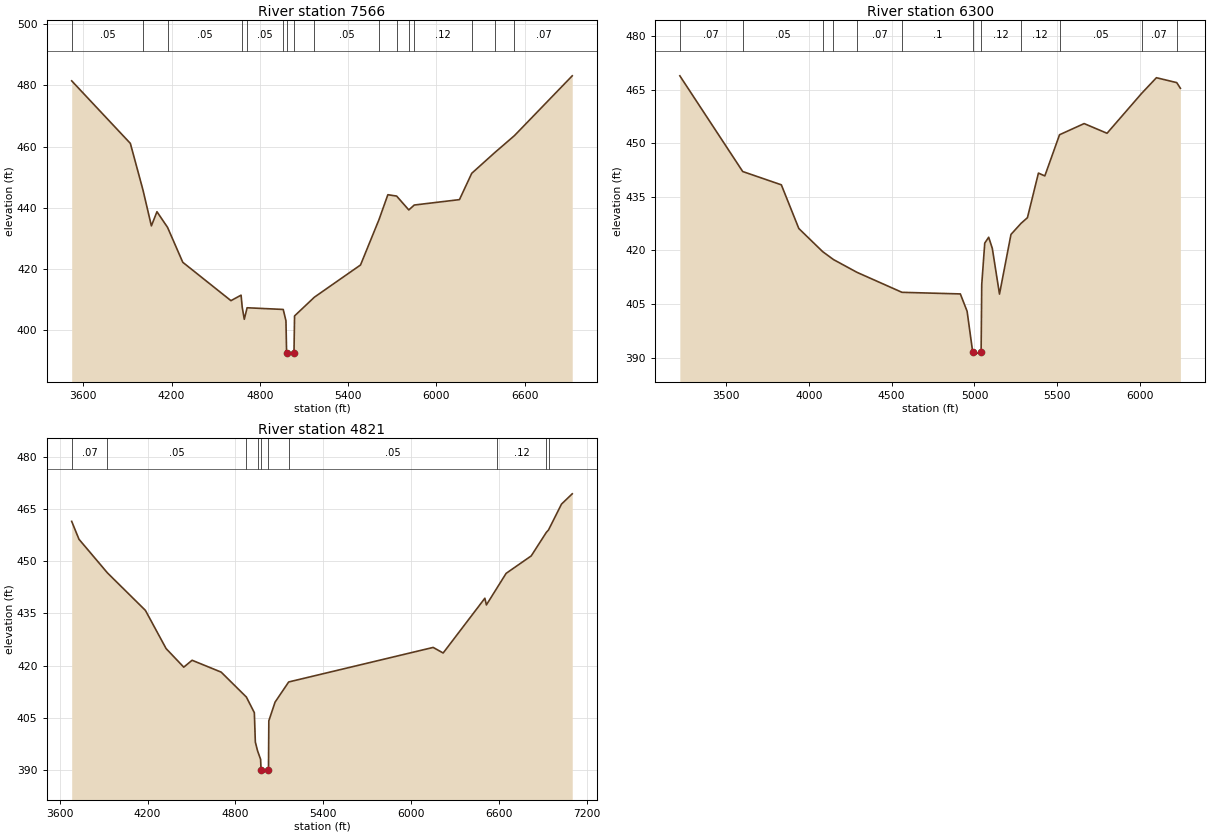
Type RM Length L Ch R = 1 ,7566    ,1266,1266,1266
BEGIN DESCRIPTION:
B19380
END DESCRIPTION:
XS GIS Cut Line= 3
      2342372.46     13752169.55      2340580.42     13751396.52
      2339412.09     13750535.64
#Sta/Elev= 30
  3521.4  481.46  3920.2  461.04  4006.4  445.75  4063.2  434.11  4101.1  438.73
  4173.2  433.61  4276.6  422.22  4604.1  409.69    4673  411.48  4680.8  407.53
  4694.8  403.61  4713.9  407.37  4959.5  406.82    4978  403.13  4982.4  392.73
  4983.4  392.23  5032.7  392.73  5036.5   404.7  5171.3  410.82    5485  421.34
  5610.8  436.18  5670.9  444.28  5730.5  443.84  5813.2  439.31  5850.3  440.91
  6157.6  442.68  6240.9  451.26  6398.7  458.08  6531.5  463.58  6924.3   483.1
#Mann= 16 ,-1 , 0
  3521.4     .05       0  4006.4     .12       0  4173.2     .05       0
  4680.8      .1       0  4713.9     .05       0  4959.5      .1       0
  4982.4     .05       0  5032.7      .1       0  5171.3     .05       0
  5610.8     .07       0  5730.5     .12       0  5813.2     .07       0
  5850.3     .12       0  6240.9    .035       0  6398.7     .05       0
  6531.5     .07       0
Bank Sta=4982.4,5032.7
XS Rating Curve= 0 ,0
Exp/Cntr=0.3,0.1

Type RM Length L Ch R = 1 ,6300    ,1479,1479,1479
BEGIN DESCRIPTION:
B19379
END DESCRIPTION:
XS GIS Cut Line= 3
      2342311.02     13751510.73      2340387.16     13750693.74
      2339561.37     13750263.28
#Sta/Elev= 30
  3221.7  468.86  3601.2  442.09  3834.4  438.37  3939.9  426.15  4083.4   419.7
  4149.1  417.46  4291.4  413.88  4562.6   408.3  4914.9  407.85  4955.7     403
  4989.7  391.51  4990.7  391.01  5040.2  391.51    5044  410.47  5062.2  422.06
  5085.9  423.71  5107.8   420.6  5151.2  407.81  5220.5  424.49  5281.2  427.59
  5319.9  429.18  5386.2  441.65  5424.8  440.86  5513.6  452.38  5662.2   455.5
  5800.4  452.79  6009.6  463.97  6098.4  468.33  6221.1  466.96  6243.1  465.38
#Mann= 12 ,-1 , 0
  3221.7     .07       0  3601.2     .05       0  4083.4     .07       0
  4149.1      .1       0  4291.4     .07       0  4562.6      .1       0
  4989.7     .05       0  5040.2     .12       0  5281.2     .12       0
  5513.6     .05       0  6009.6     .07       0  6221.1     .12       0
Bank Sta=4989.7,5040.2
XS Rating Curve= 0 ,0
Exp/Cntr=0.3,0.1

Type RM Length L Ch R = 1 ,4821    ,756,756,756
BEGIN DESCRIPTION:
B19378
END DESCRIPTION:
XS GIS Cut Line= 3
      2342363.71     13751396.51      2341160.21     13750026.11
      2339649.64     13749516.73
#Sta/Elev= 30
  3681.7  461.45  3731.5  456.31  3925.8  446.65  4185.1  435.88  4326.5   424.9
    4447  419.57  4503.9  421.55  4702.3  418.15  4874.7  410.98    4929  406.49
  4935.7  398.08  4950.8  395.55  4971.7  393.09  4974.9  389.92  4975.9  389.42
  5025.5  389.92  5027.9  404.17  5070.4  409.52  5163.5  415.32    6150  425.24
  6218.3  423.64  6503.1  439.37  6513.6  437.45  6582.9  442.12  6648.4  446.52
  6819.7  451.53  6922.9  458.29  6937.7  458.98  7026.2   466.4  7099.7  469.36
#Mann= 10 ,-1 , 0
  3681.7     .07       0  3925.8     .05       0  4874.7     .07       0
  4950.8     .12       0  4974.9     .05       0  5025.5     .12       0
  5163.5     .05       0  6582.9     .12       0  6922.9     .07       0
  6937.7     .12       0
Bank Sta=4974.9,5025.5
XS Rating Curve= 0 ,0
Exp/Cntr=0.3,0.1