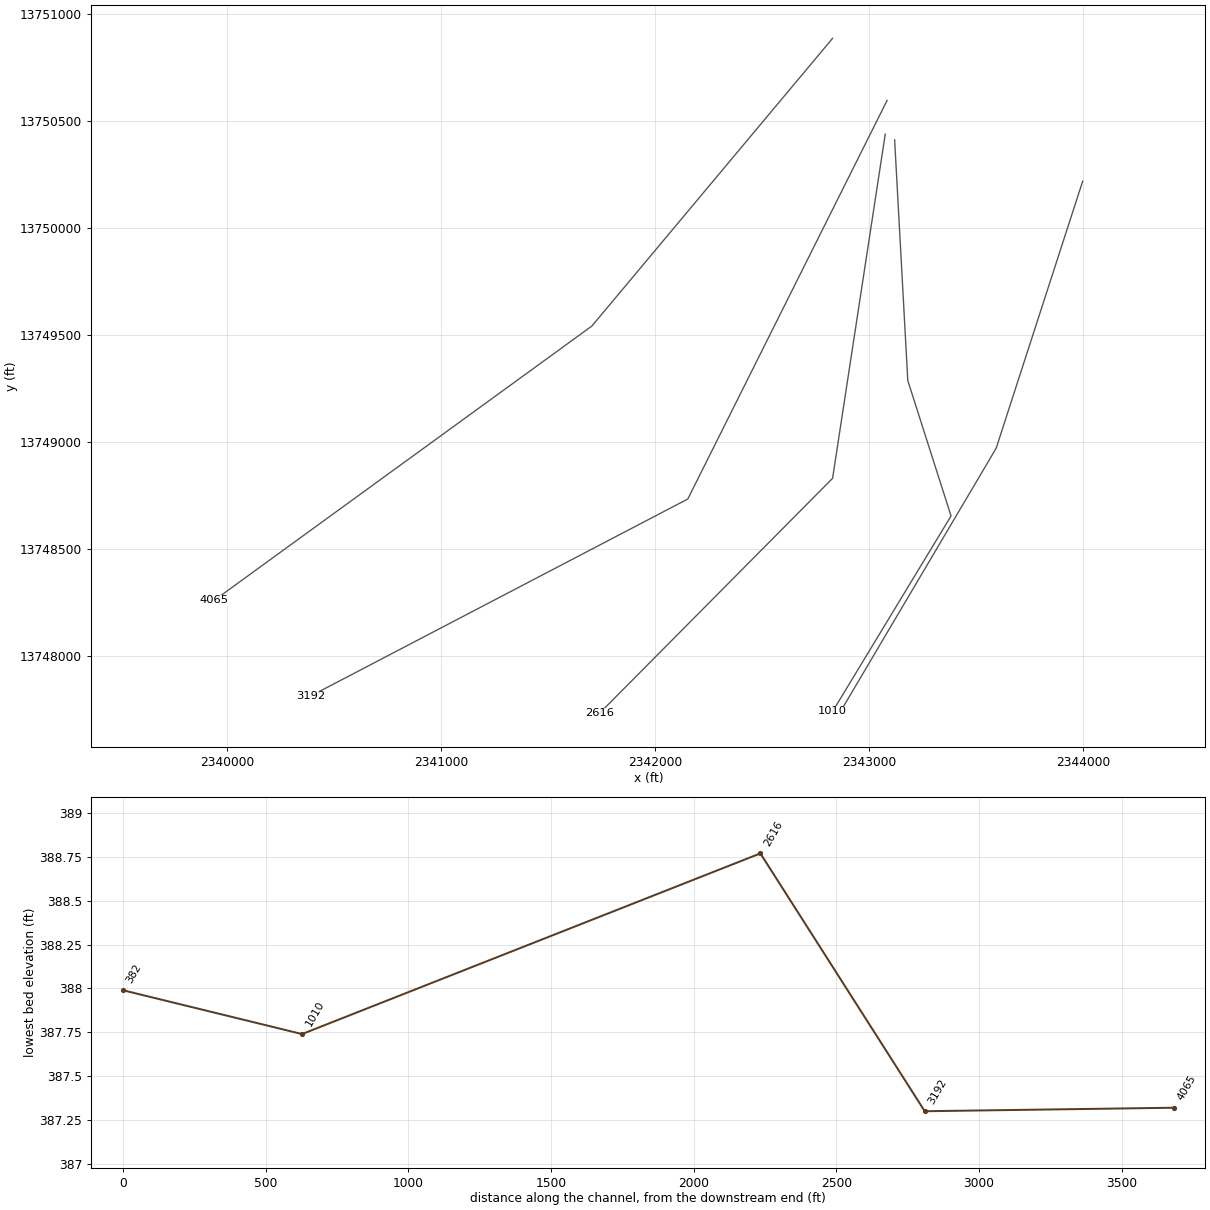
HEC-RAS study Mill Creek.prj: Mill Creek Base Level Engineering

--- Mill Creek.g01 (geometry) --- (continued)

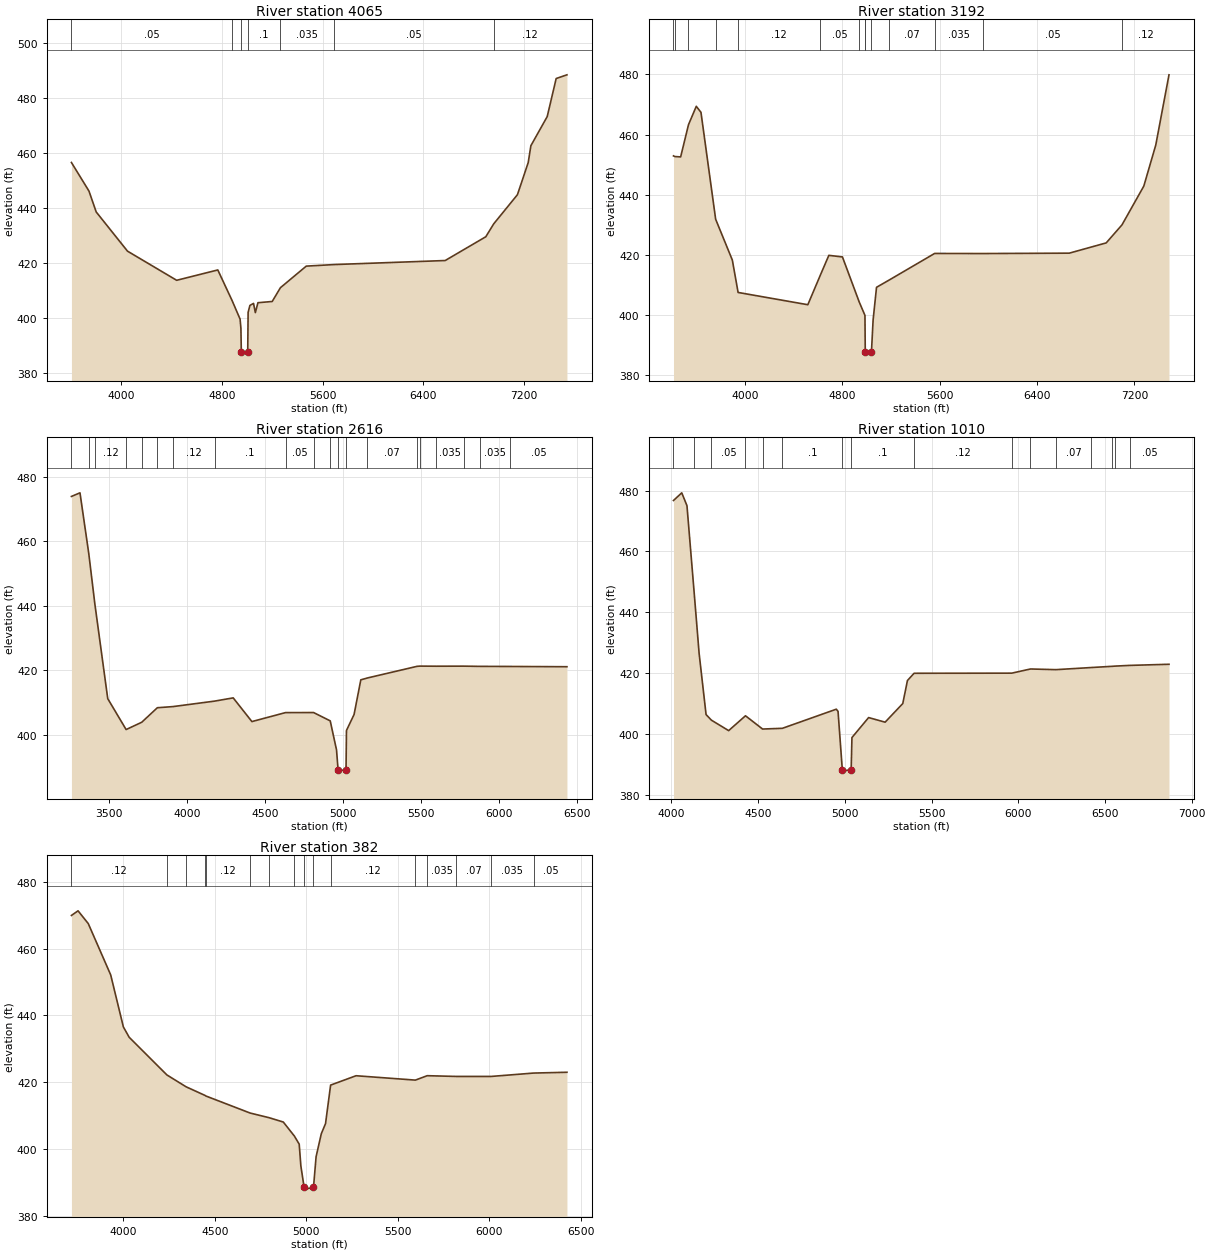
Type RM Length L Ch R = 1 ,4065    ,873,873,873
BEGIN DESCRIPTION:
B19377
END DESCRIPTION:
XS GIS Cut Line= 3
      2342829.28     13750886.98      2341704.86     13749542.95
      2339939.57     13748260.69
#Sta/Elev= 30
  3605.7  456.58    3745  446.19  3802.3  438.61  4050.8  424.37  4441.2  413.78
  4767.8  417.54  4880.8  406.47  4944.8  399.67  4951.3   396.3  4954.5  387.82
  4955.5  387.32  5005.4  387.82  5008.5  402.14  5022.8  404.66  5051.5  405.38
  5065.8  402.04  5086.6  405.64  5199.8  406.08  5264.8  411.08  5470.2  418.93
  5693.6   419.5  6573.2  420.96  6895.6   429.6  6958.7   434.3  7146.8  444.88
  7232.6  456.58  7253.5  462.67  7383.3  473.26  7454.4  487.09  7539.9  488.43
#Mann= 7 ,-1 , 0
  3605.7     .05       0  4880.8      .1       0  4954.5     .05       0
  5005.4      .1       0  5264.8    .035       0  5693.6     .05       0
  6958.7     .12       0
Bank Sta=4954.5,5005.4
XS Rating Curve= 0 ,0
Exp/Cntr=0.3,0.1

Type RM Length L Ch R = 1 ,3192    ,576,576,576
BEGIN DESCRIPTION:
B19376
END DESCRIPTION:
XS GIS Cut Line= 3
      2343084.04     13750597.07      2342152.88     13748734.76
      2340388.55     13747813.09
#Sta/Elev= 30
  3411.6   452.9  3423.1  452.68  3470.4  452.56  3534.8  463.26    3599  469.39
  3637.5  467.38  3758.2  431.82  3895.2  418.26  3942.7  407.48  4515.7   403.4
  4619.5  413.32  4688.5  419.82  4800.3  419.29  4938.2  404.31  4985.3  399.85
  4986.9  392.14  4987.8   387.8  4988.8   387.3  5038.8   387.8  5052.4  398.37
  5080.4  409.19    5184   411.6  5557.9  420.45  5956.1  420.42  6664.7  420.55
  6968.2  423.96  7097.8  429.95  7277.3  442.85  7375.5  456.49  7484.3  479.86
#Mann= 14 ,-1 , 0
  3411.6     .05       0  3423.1     .12       0  3534.8     .07       0
  3758.2     .05       0  3942.7     .12       0  4619.5     .05       0
  4938.2      .1       0  4986.9    .035       0  4987.8    .035       0
  5038.8    .035       0    5184     .07       0  5557.9    .035       0
  5956.1     .05       0  7097.8     .12       0
Bank Sta=4987.8,5038.8
XS Rating Curve= 0 ,0
Exp/Cntr=0.3,0.1

Type RM Length L Ch R = 1 ,2616    ,1606,1606,1606
BEGIN DESCRIPTION:
B19375
END DESCRIPTION:
XS GIS Cut Line= 3
      2343075.28     13750439.03       2342829.3     13748831.39
      2341739.99     13747733.29
#Sta/Elev= 30
  3259.7  473.86  3314.4  474.98  3370.8  456.14  3409.8  440.51  3492.2  411.22
  3609.9  401.65  3709.9  403.91  3809.9  408.41    3910  408.76  4176.8  410.46
  4295.6  411.46  4415.3  404.12  4630.6   406.9  4810.3  406.92  4916.9  404.34
  4957.2  395.37  4967.1  389.27  4968.1  388.77  5018.1  389.27  5020.9  401.36
  5069.7  406.32  5112.8  417.05  5155.5  417.63  5472.8  421.23  5491.9   421.3
    5596  421.27  5771.5  421.29  5877.4  421.22    6069  421.19  6432.8  421.11
#Mann= 20 ,-1 , 0
  3259.7     .12       0  3370.8     .07       0  3409.8     .12       0
  3609.9     .05       0  3709.9     .12       0  3809.9      .1       0
    3910     .12       0  4176.8      .1       0  4630.6     .05       0
  4810.3     .12       0  4916.9      .1       0  4967.1     .05       0
  5018.1      .1       0  5155.5     .07       0  5472.8    .035       0
  5491.9     .07       0    5596    .035       0  5771.5     .07       0
  5877.4    .035       0    6069     .05       0
Bank Sta=4967.1,5018.1
XS Rating Curve= 0 ,0
Exp/Cntr=0.3,0.1

Type RM Length L Ch R = 1 ,1010    ,628,628,628
BEGIN DESCRIPTION:
B19374
END DESCRIPTION:
XS GIS Cut Line= 4
       2343119.2     13750412.59      2343180.69     13749288.19
      2343382.74     13748655.69      2342829.68      13747742.7
#Sta/Elev= 30
  4011.8  476.74  4059.5  479.26  4089.5  475.03  4131.7  445.97  4159.6  426.44
  4199.7  406.34  4230.2  404.51  4329.9  401.06    4427  405.94  4525.5  401.58
  4639.9  401.82  4950.8  408.11  4960.8  407.37  4985.3  388.24  4986.3  387.74
  5036.4  388.24  5040.9  398.78    5137  405.35  5232.3  403.84  5334.1  409.97
    5361  417.54  5399.3  419.92  5962.6  419.96  6070.6  421.33  6217.6  421.11
  6422.1  421.81  6542.1  422.21  6559.9  422.28  6643.1  422.51  6869.3  422.88
#Mann= 16 ,-1 , 0
  4011.8     .12       0  4131.7     .07       0  4230.2     .05       0
    4427      .1       0  4525.5     .12       0  4639.9      .1       0
  4985.3     .05       0  5036.4      .1       0  5399.3     .12       0
  5962.6      .1       0  6070.6    .035       0  6217.6     .07       0
  6422.1    .035       0  6542.1     .07       0  6559.9    .035       0
  6643.1     .05       0
Bank Sta=4985.3,5036.4
XS Rating Curve= 0 ,0
Exp/Cntr=0.3,0.1

Type RM Length L Ch R = 1 ,382     ,0,0,0
BEGIN DESCRIPTION:
B19373
END DESCRIPTION:
XS GIS Cut Line= 3
      2343997.67     13750219.37      2343593.57     13748971.94
      2342882.45     13747769.19
#Sta/Elev= 30
    3716  469.91  3752.1  471.29  3807.9  467.48  3930.6  452.11  3999.8  436.55
  4031.8  433.43  4237.8  422.17  4342.3  418.63  4447.3  416.01  4451.1  415.86
    4693  410.76  4796.5  409.37  4874.1  408.07  4934.6  403.88    4961  401.45
  4970.1  394.92    4988  388.49    4989  387.99  5039.1  388.49  5053.3  397.69
  5081.8  404.57    5105  407.62  5132.7  419.13  5271.8  421.93  5596.1  420.62
  5660.7  421.94  5820.1  421.72  6009.9  421.72  6242.8  422.73  6424.5  422.97
#Mann= 16 ,-1 , 0
    3716     .12       0  4237.8     .07       0  4342.3     .12       0
  4447.3      .1       0  4451.1     .12       0    4693      .1       0
  4796.5     .12       0  4934.6      .1       0    4988     .05       0
  5039.1      .1       0  5132.7     .12       0  5596.1      .1       0
  5660.7    .035       0  5820.1     .07       0  6009.9    .035       0
  6242.8     .05       0
Bank Sta=4988,5039.1
XS Rating Curve= 0 ,0
Exp/Cntr=0.3,0.1

Chan Stop Cuts=-1
Use User Specified Reach Order=0
Composite Channel Slope=5