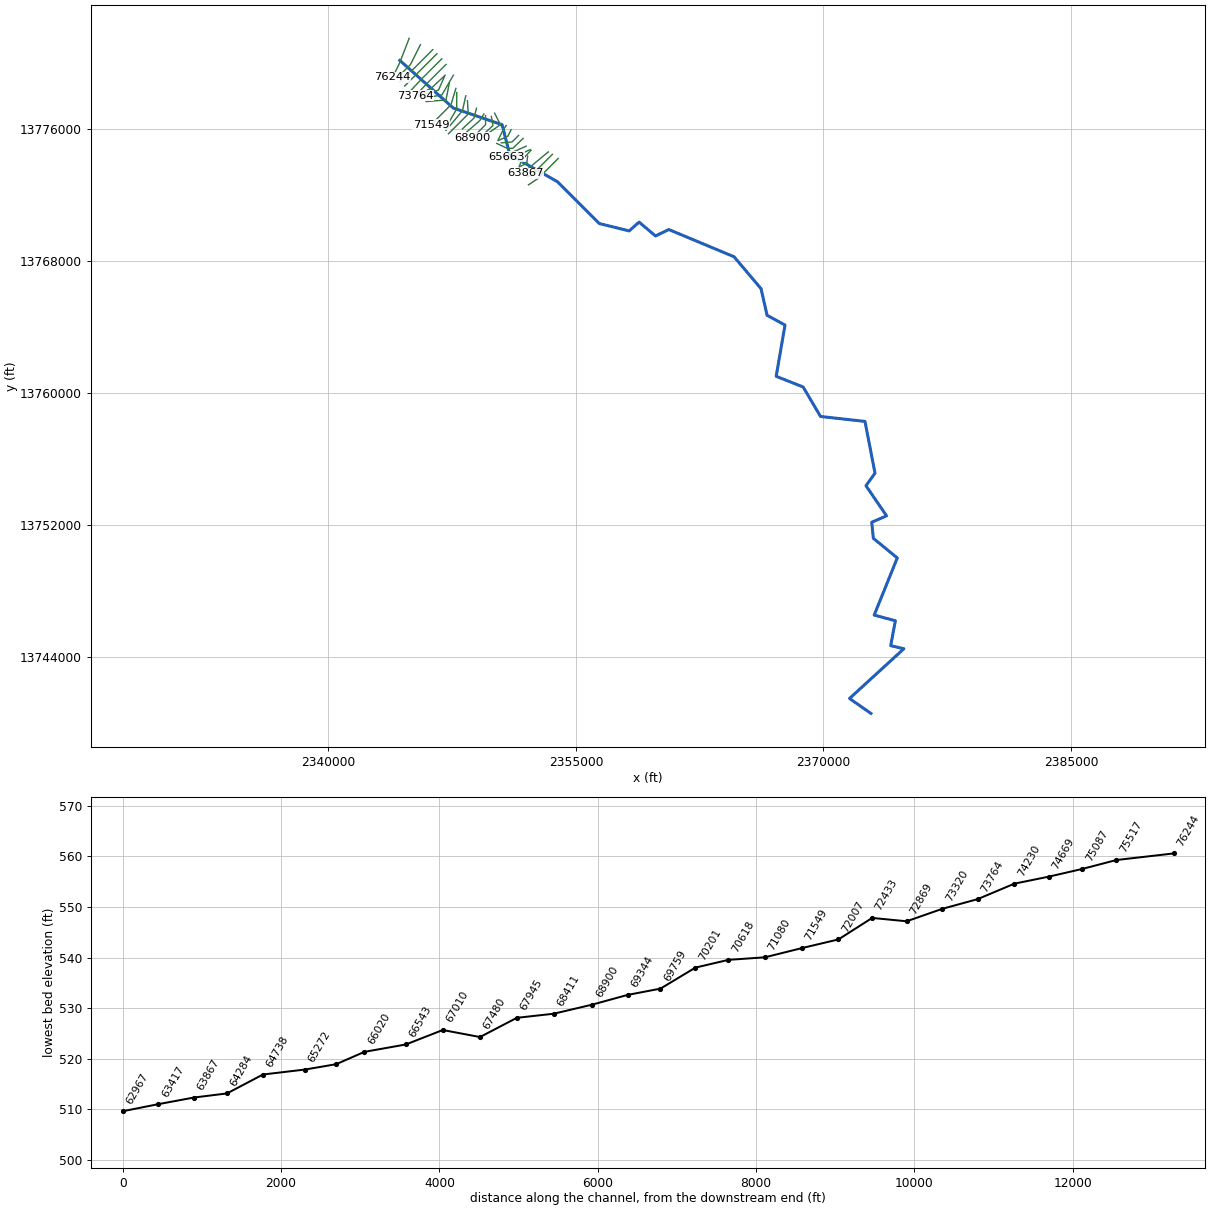
--- NASH CREEK.prj (project) ---

Proj Title=NASH CREEK Base Level Engineering
Current Plan=p01
Default Exp/Contr=0.3,0.1
English Units
Geom File=g01
Flow File=f01
Plan File=p01
Y Axis Title=Elevation
X Axis Title(PF)=Main Channel Distance
X Axis Title(XS)=Station
BEGIN DESCRIPTION:
NASH CREEK
END DESCRIPTION:
DSS Export Rating Curves= 0
DSS Export Rating Curve Sorted= 0
DSS Export Volume Flow Curves= 0
DXF OffsetX= 0
DXF OffsetY= 0
DXF ScaleX= 1
DXF ScaleY= 10

--- NASH CREEK.p01 (plan) ---

Plan Title=Multiple Run
Short Identifier=Multiple
Geom File=g01
Flow File=f01
Subcritical Flow
K Sum by GR= 0
Std Step Tol= 0.01
Critical Tol= 0.01
Num of Std Step Trials= 20
Max Error Tol= 0.3
Flow Tol Ratio= 0.001
Split Flow NTrial= 30
Split Flow Tol= 0.02
Split Flow Ratio= 0.02
Log Output Level= 0
Friction Slope Method= 1
Unsteady Friction Slope Method= 2
Unsteady Bridges Friction Slope Method= 1
Parabolic Critical Depth
Global Vel Dist=  1 , 1 , 1
Global Log Level= 0
CheckData=True
Encroach Param= -1, 0, 0, 0
BEGIN DESCRIPTION:
Multiple Run
END DESCRIPTION:

--- NASH CREEK.f01 (steady flow) ---

Flow Title=Multiple
Number of Profiles=7
Profile Names=10-year,25-year,50-year,1pct_min,100-year,1pct_plu,500-year
River Rch & RM= NASH CREEK,Reach-1,76244
     622     999    1336     865    1726    3445    2855
River Rch & RM= NASH CREEK,Reach-1,74669
     731    1181    1587    1032    2059    4107    3431
River Rch & RM= NASH CREEK,Reach-1,71080
    1018    1674    2276    1495    2983    5952    5081
River Rch & RM= NASH CREEK,Reach-1,67480
    1697    2866    3966    2648    5283   10542    9301
River Rch & RM= NASH CREEK,Reach-1,65663
    1906    3236    4496    3011    6009   11989   10649
River Rch & RM= NASH CREEK,Reach-1,63417
    1967    3343    4648    3116    6217   12404   11034
River Rch & RM= NASH CREEK,Reach-1,60326
    2195    3747    5224    3511    7005   13977   12497
River Rch & RM= NASH CREEK,Reach-1,58956
    2344    4008    5595    3763    7508   14981   13416
River Rch & RM= NASH CREEK,Reach-1,52664
    2519    4314    6028    4058    8097   16155   14492
River Rch & RM= NASH CREEK,Reach-1,50916
    2683    4602    6436    4336    8650   17260   15505
River Rch & RM= NASH CREEK,Reach-1,44886
    2825    4849    6784    4571    9120   18196   16351
River Rch & RM= NASH CREEK,Reach-1,39753
    2884    4955    6938    4678    9334   18624   16760
River Rch & RM= NASH CREEK,Reach-1,35822
    3229    5574    7829    5293   10562   21074   19073
River Rch & RM= NASH CREEK,Reach-1,33687
    3353    5791    8137    5502   10979   21906   19831
River Rch & RM= NASH CREEK,Reach-1,29182
    4398    7641   10784    7321   14608   29147   26578
River Rch & RM= NASH CREEK,Reach-1,23915
    4355    7586   10722    7289   14544   29019   26547
River Rch & RM= NASH CREEK,Reach-1,20602
    4839    8458   11984    8166   16294   32510   29874
River Rch & RM= NASH CREEK,Reach-1,17058
    5095    8887   12577    8560   17079   34078   31223
River Rch & RM= NASH CREEK,Reach-1,13274
    5183    9070   12859    8767   17492   34900   32098
River Rch & RM= NASH CREEK,Reach-1,7224
    5268    9214   13060    8901   17759   35434   32567
River Rch & RM= NASH CREEK,Reach-1,2951
    5322    9305   13184    8981   17920   35755   32832
Boundary for River Rch & Prof#=NASH CREEK,Reach-1,1
Up Type=0
Dn Type=3
Dn Slope=0.005
Boundary for River Rch & Prof#=NASH CREEK,Reach-1,2
Up Type=0
Dn Type=3
Dn Slope=0.005
Boundary for River Rch & Prof#=NASH CREEK,Reach-1,3
Up Type=0
Dn Type=3
Dn Slope=0.005
Boundary for River Rch & Prof#=NASH CREEK,Reach-1,4
Up Type=0
Dn Type=3
Dn Slope=0.005
Boundary for River Rch & Prof#=NASH CREEK,Reach-1,5
Up Type=0
Dn Type=3
Dn Slope=0.005
Boundary for River Rch & Prof#=NASH CREEK,Reach-1,6
Up Type=0
Dn Type=3
Dn Slope=0.005
Boundary for River Rch & Prof#=NASH CREEK,Reach-1,7
Up Type=0
Dn Type=3
Dn Slope=0.005

--- NASH CREEK.g01 (geometry) ---

Geom Title=Existing Conditions
Program Version=4.10

River Reach=NASH CREEK      ,Reach-1
Reach XY= 30
        2344325.       13780175.      2347568.81     13777282.85
        2350525.       13776275.      2350994.46     13774454.46
      2353884.71     13772814.25      2356422.55     13770280.47
      2358225.01     13769832.53      2358828.22     13770367.13
        2359825.       13769525.       2360628.3     13769916.92
       2364584.8     13768264.52      2366219.58     13766327.67
      2366585.51     13764715.19      2367671.85     13764123.37
      2367135.34     13761014.88      2368769.82     13760369.56
      2369822.71      13758580.1      2372517.36     13758281.45
      2373125.53     13755140.19      2372576.96     13754380.89
      2373825.12     13752555.05      2372928.15     13752166.68
      2373025.66     13751190.83      2374475.42     13749999.99
      2373076.03     13746535.43      2374358.82      13746191.7
       2374076.5     13744680.87       2374875.7     13744495.15
      2371580.45     13741477.46        2372875.       13740575.

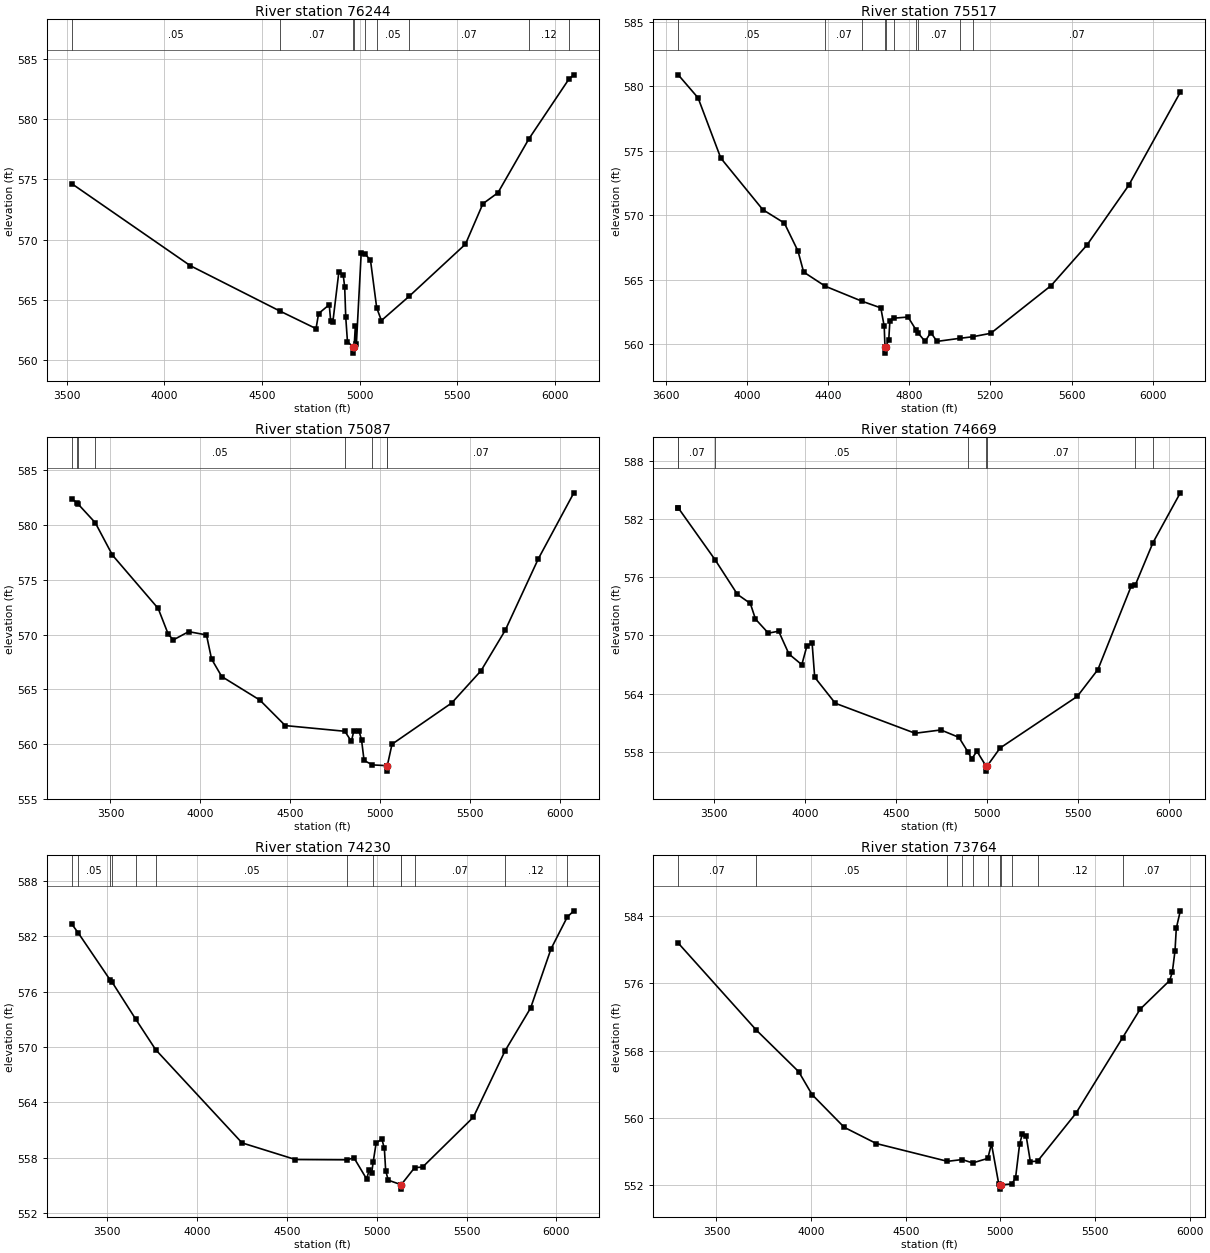
Type RM Length L Ch R = 1 ,76244   ,727,727,727
BEGIN DESCRIPTION:
B19772
END DESCRIPTION:
XS GIS Cut Line= 3
      2344894.42     13781511.55      2344324.12     13780035.89
      2343896.37     13779144.76
#Sta/Elev= 30
    3526  574.65  4133.4  567.85  4589.9  564.11  4776.6  562.64  4789.6  563.89
  4844.2  564.62  4851.7  563.24  4862.4  563.15  4893.4  567.34    4916  567.05
  4923.3  566.09  4928.7  563.58  4937.5  561.55  4967.6  561.11  4967.9  560.61
  4971.6  561.11  4977.9  562.89  4983.2  561.38  5007.8   568.9  5026.2  568.86
  5055.4   568.3  5087.2  564.36  5111.3  563.31  5252.7  565.31  5541.6  569.64
  5630.9  572.99    5708   573.9  5866.2  578.36  6071.8  583.33  6096.5  583.67
#Mann= 9 ,-1 , 0
    3526     .05       0  4589.9     .07       0  4967.6     .05       0
  4971.6     .07       0  5026.2     .12       0  5087.2     .05       0
  5252.7     .07       0  5866.2     .12       0  6071.8     .07       0
Bank Sta=4967.6,4971.6
XS Rating Curve= 0 ,0
Exp/Cntr=0.3,0.1

Type RM Length L Ch R = 1 ,75517   ,430,430,430
BEGIN DESCRIPTION:
NASH CREEK 133.0
END DESCRIPTION:
XS GIS Cut Line= 3
        2345575.       13781125.        2344975.       13779925.
      2344175.01     13779125.01
#Sta/Elev= 30
  3662.7  580.89  3760.5   579.1  3872.3  574.43  4079.2  570.43  4185.4  569.39
  4252.5  567.22  4280.4  565.59    4387  564.49  4565.6  563.34  4660.5  562.81
  4677.3  561.38  4680.9   559.8  4681.1   559.3    4685   559.8  4699.7  560.35
  4705.3  561.83  4723.5  562.01  4794.7   562.1  4835.2  561.07  4842.4  560.89
  4878.6  560.21  4906.5   560.9  4937.3  560.21  5050.1  560.45  5113.1  560.57
  5202.3  560.84  5499.3  564.54  5676.1  567.69  5881.2  572.31  6135.7  579.54
#Mann= 10 ,-1 , 0
  3662.7     .05       0    4387     .07       0  4565.6     .05       0
  4680.9     .05       0    4685     .05       0  4723.5     .07       0
  4835.2     .05       0  4842.4     .07       0  5050.1     .12       0
  5113.1     .07       0
Bank Sta=4680.9,4685
XS Rating Curve= 0 ,0
Exp/Cntr=0.3,0.1

Type RM Length L Ch R = 1 ,75087   ,418,418,418
BEGIN DESCRIPTION:
NASH CREEK 132.0
END DESCRIPTION:
XS GIS Cut Line= 3
      2346324.98     13780824.98        2345125.       13779625.
      2344325.01     13778875.01
#Sta/Elev= 30
  3284.6  582.41  3316.3  582.02  3318.9  581.95  3415.3  580.23  3510.9  577.27
  3765.4   572.4    3822  570.02  3850.3  569.53  3935.1  570.28  4034.1  569.98
  4062.4  567.78    4119  566.18  4331.1  564.03  4472.5   561.7  4804.1  561.18
  4840.2  560.26  4854.4  561.23  4882.6  561.21  4896.8  560.41  4910.9  558.52
    4957  558.11  5035.9  558.04  5036.2  557.54  5040.3  558.04  5066.4     560
    5399  563.77  5561.7  566.71    5696  570.39  5880.1  576.92  6078.2  582.96
#Mann= 8 ,-1 , 0
  3284.6    .035       0  3316.3     .05       0  3318.9     .07       0
  3415.3     .05       0  4804.1     .07       0    4957     .12       0
  5035.9     .05       0  5040.3     .07       0
Bank Sta=5035.9,5040.3
XS Rating Curve= 0 ,0
Exp/Cntr=0.3,0.1

Type RM Length L Ch R = 1 ,74669   ,439,439,439
BEGIN DESCRIPTION:
NASH CREEK 131.0
END DESCRIPTION:
XS GIS Cut Line= 3
      2346574.98     13780574.98        2345375.       13779375.
      2344624.99     13778624.99
#Sta/Elev= 30
    3303  583.13  3303.4  583.13  3504.9  577.81  3628.2  574.23  3698.9   573.3
  3727.2  571.69  3797.9  570.24  3854.5  570.44  3911.1  568.09  3981.8  566.99
  4010.1  568.95  4038.4  569.19  4052.5   565.7  4165.6  563.02    4604  559.93
  4745.5  560.27  4844.5  559.51  4895.7  557.96  4915.2  557.29  4943.5  558.08
  4994.2  556.53  4994.6  556.03  4998.7  556.53  5070.7  558.41    5495  563.73
  5608.1  566.49    5792  575.13  5813.6   575.2  5910.6  579.56  6060.7  584.69
#Mann= 8 ,-1 , 0
    3303    .035       0  3303.4     .07       0  3504.9     .05       0
  4895.7     .07       0  4994.2     .05       0  4998.7     .07       0
  5813.6     .12       0  5910.6     .07       0
Bank Sta=4994.2,4998.7
XS Rating Curve= 0 ,0
Exp/Cntr=0.3,0.1

Type RM Length L Ch R = 1 ,74230   ,466,466,466
BEGIN DESCRIPTION:
NASH CREEK 130.0
END DESCRIPTION:
XS GIS Cut Line= 3
      2346875.01     13780275.01        2345675.       13779075.
      2344925.03     13778275.04
#Sta/Elev= 30
  3303.4   583.3  3339.8  582.33  3515.2   577.3  3526.7  577.05  3658.6  573.03
  3770.3  569.71  4250.9  559.63  4547.9  557.83  4837.1   557.8  4873.2  558.03
  4943.9  555.73    4958  556.67  4972.2   556.4  4980.3  557.54  4996.9  559.61
  5028.6  560.05  5042.7  559.04    5050  556.63  5064.2   555.6  5132.8  555.13
  5133.1  554.63  5137.3  555.13  5211.4  556.96  5255.2  557.01    5538  562.41
  5713.8  569.57  5856.5  574.22  5969.8  580.61  6060.7  584.07    6097  584.73
#Mann= 13 ,-1 , 0
  3303.4    .035       0  3339.8     .05       0  3515.2     .07       0
  3526.7     .05       0  3658.6     .07       0  3770.3     .05       0
  4837.1     .07       0  4980.3     .12       0  5132.8     .05       0
  5137.3     .12       0  5211.4     .07       0  5713.8     .12       0
  6060.7     .07       0
Bank Sta=5132.8,5137.3
XS Rating Curve= 0 ,0
Exp/Cntr=0.3,0.1

Type RM Length L Ch R = 1 ,73764   ,444,444,444
BEGIN DESCRIPTION:
NASH CREEK 129.0
END DESCRIPTION:
XS GIS Cut Line= 3
      2347125.03     13779925.03        2345925.       13778725.
      2345275.03     13778025.03
#Sta/Elev= 30
  3298.1  580.77  3710.2  570.45  3934.5   565.5  4005.2  562.78  4174.9   558.9
  4344.7  556.97  4720.4  554.86  4798.2  555.07  4853.4  554.67  4933.5  555.21
  4952.8  556.94  4991.7  552.12    5000  552.06  5000.3  551.56  5004.6  552.06
  5060.2  552.18    5080  552.88  5101.5  556.91  5115.6  558.08  5136.6  557.81
  5158.2  554.83  5196.4  554.88  5398.5  560.55  5646.1  569.56  5738.1  572.92
    5894  576.32  5908.2  577.32  5922.4  579.86  5929.2  582.53  5950.4   584.6
#Mann= 11 ,-1 , 0
  3298.1     .07       0  3710.2     .05       0  4720.4     .07       0
  4798.2     .12       0  4853.4     .07       0  4933.5     .12       0
    5000     .05       0  5004.6     .12       0  5060.2     .07       0
  5196.4     .12       0  5646.1     .07       0
Bank Sta=5000,5004.6
XS Rating Curve= 0 ,0
Exp/Cntr=0.3,0.1

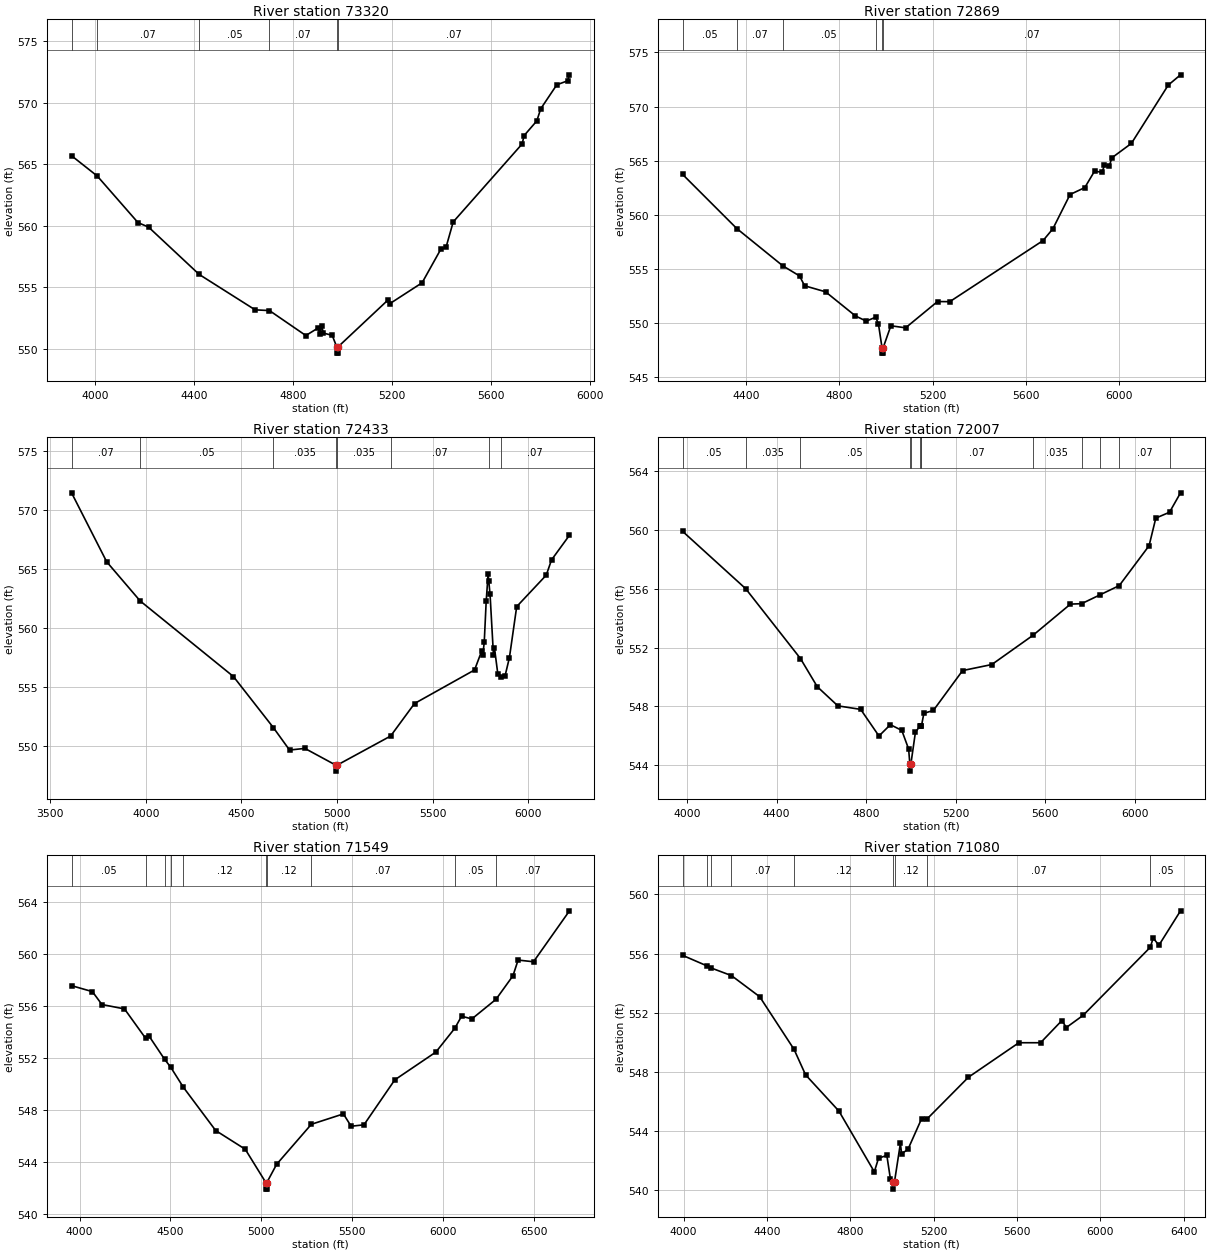
Type RM Length L Ch R = 1 ,73320   ,451,451,451
BEGIN DESCRIPTION:
NASH CREEK 128.0
END DESCRIPTION:
XS GIS Cut Line= 3
      2347075.02     13779275.02        2346275.       13778525.
        2345475.       13778075.
#Sta/Elev= 30
  3903.4  565.71  4007.4  564.06  4172.3  560.27  4214.8  559.91  4419.7  556.06
  4646.1  553.18  4704.1  553.12  4851.3  551.09  4901.1  551.71    4908  551.21
  4915.3  551.89  4922.1  551.29  4957.8  551.11  4976.5  550.16  4976.8  549.66
  4980.8  549.66  4981.1  550.16  5183.6  553.98  5191.6  553.69  5321.6  555.38
  5396.8  558.09  5418.5  558.27  5447.5  560.33  5726.4  566.67  5734.3  567.35
  5785.6  568.54  5801.6  569.53  5866.6  571.48  5909.9   571.8  5917.9  572.29
#Mann= 6 ,-1 , 0
  3903.4     .05       0  4007.4     .07       0  4419.7     .05       0
  4704.1     .07       0  4976.5     .05       0  4981.1     .07       0
Bank Sta=4976.5,4981.1
XS Rating Curve= 0 ,0
Exp/Cntr=0.3,0.1

Type RM Length L Ch R = 1 ,72869   ,436,436,436
BEGIN DESCRIPTION:
NASH CREEK 127.0
END DESCRIPTION:
XS GIS Cut Line= 3
        2347025.     13779174.99        2346675.       13778375.
      2345475.01       13777975.
#Sta/Elev= 30
  4126.8  563.72  4359.6  558.71  4557.4  555.26  4628.9  554.33  4650.7  553.42
  4740.8  552.86    4869  550.63  4915.4  550.15  4955.6  550.51  4967.6  549.91
  4983.1  547.69  4983.5  547.19  4987.7  547.19    4988  547.69  5021.1  549.72
  5084.3  549.53  5221.4  551.96  5274.1  551.95  5674.6   557.6  5716.8  558.69
  5790.6  561.86  5853.8   562.5    5896  564.03  5927.6  563.91  5938.1  564.55
  5959.2   564.5  5969.8  565.25  6054.1  566.59  6212.2  571.98  6264.9  572.93
#Mann= 6 ,-1 , 0
  4126.8     .05       0  4359.6     .07       0  4557.4     .05       0
  4955.6     .07       0  4983.1     .05       0    4988     .07       0
Bank Sta=4983.1,4988
XS Rating Curve= 0 ,0
Exp/Cntr=0.3,0.1

Type RM Length L Ch R = 1 ,72433   ,426,426,426
BEGIN DESCRIPTION:
NASH CREEK 126.0
END DESCRIPTION:
XS GIS Cut Line= 3
      2347575.01     13779275.02        2346875.       13778075.
      2345675.02       13777875.
#Sta/Elev= 30
  3610.7  571.48  3794.7  565.62  3969.7   562.3  4457.9  555.88  4666.6  551.55
  4751.5  549.64  4831.7  549.78  4994.6  548.35    4995  547.85  4999.5  548.35
  5280.5  550.83  5405.5  553.59  5719.8  556.44  5757.8  558.08  5762.8  557.68
  5770.5  558.81  5780.6  562.27  5790.7  564.58  5794.1     564  5800.9  562.85
  5818.6  557.73  5823.7  558.33  5841.4  556.11  5856.1  555.88  5879.4  555.94
  5902.2  557.49  5940.3  561.82  6094.9  564.49  6122.7  565.79  6216.5  567.88
#Mann= 8 ,-1 , 0
  3610.7     .07       0  3969.7     .05       0  4666.6    .035       0
  4994.6    .035       0  4999.5    .035       0  5280.5     .07       0
  5794.1     .12       0  5856.1     .07       0
Bank Sta=4994.6,4999.5
XS Rating Curve= 0 ,0
Exp/Cntr=0.3,0.1

Type RM Length L Ch R = 1 ,72007   ,458,458,458
BEGIN DESCRIPTION:
NASH CREEK 125.0
END DESCRIPTION:
XS GIS Cut Line= 3
      2347324.99     13778774.96        2347125.       13777775.
      2345925.02       13777675.
#Sta/Elev= 30
  3980.3  559.91    4262  556.01  4506.6  551.26  4581.9  549.34  4673.7  548.04
  4775.7   547.8  4857.3  545.99  4908.3  546.76  4959.3  546.37  4989.9   545.1
  4995.1   544.1  4995.4   543.6    5000   544.1  5020.1  546.24  5040.4  546.67
  5044.1  546.67  5047.2  546.68  5057.8  547.53  5100.4  547.73  5230.9  550.44
  5361.3  550.85  5545.4  552.84  5712.5  554.96  5762.4  554.99  5843.2  555.58
  5930.6  556.22  6063.7  558.93  6093.8  560.81  6155.1  561.21  6204.2  562.53
#Mann= 13 ,-1 , 0
  3980.3     .05       0    4262    .035       0  4506.6     .05       0
  4995.1     .05       0    5000     .05       0  5040.4     .07       0
  5044.1     .05       0  5047.2     .07       0  5545.4    .035       0
  5762.4     .07       0  5843.2     .12       0  5930.6     .07       0
  6155.1     .12       0
Bank Sta=4995.1,5000
XS Rating Curve= 0 ,0
Exp/Cntr=0.3,0.1

Type RM Length L Ch R = 1 ,71549   ,469,469,469
BEGIN DESCRIPTION:
NASH CREEK 124.0
END DESCRIPTION:
XS GIS Cut Line= 3
      2347724.99     13778474.97        2347425.       13777475.
      2346224.97     13776274.97
#Sta/Elev= 30
    3956  557.56  4070.8   557.1    4123  556.11  4247.4  555.77  4364.1   553.5
    4384  553.65  4467.8   551.9  4501.5  551.29  4571.5  549.74  4749.4  546.41
  4912.1  544.97  5025.7   542.4  5026.1   541.9  5030.4   541.9  5030.8   542.4
  5084.9  543.81    5276  546.89  5452.5  547.69    5495  546.74  5565.7  546.85
  5735.4  550.31  5961.7  552.45  6065.7  554.28  6103.1  555.21  6159.7     555
  6292.6  556.51  6385.9  558.32  6414.2  559.53  6499.1   559.4  6697.1  563.32
#Mann= 10 ,-1 , 0
    3956     .05       0  4364.1     .07       0  4467.8     .12       0
  4501.5     .07       0  4571.5     .12       0  5025.7     .05       0
  5030.8     .12       0    5276     .07       0  6065.7     .05       0
  6292.6     .07       0
Bank Sta=5025.7,5030.8
XS Rating Curve= 0 ,0
Exp/Cntr=0.3,0.1

Type RM Length L Ch R = 1 ,71080   ,462,462,462
BEGIN DESCRIPTION:
NASH CREEK 123.0
END DESCRIPTION:
XS GIS Cut Line= 3
        2347775.     13778224.96        2347775.       13777225.
        2347075.       13776025.
#Sta/Elev= 30
  3995.4  555.88  4113.5  555.16  4131.4  555.03  4229.8  554.51  4365.4  553.08
  4530.2  549.52  4585.4   547.8  4745.4  545.35  4915.4  541.24  4935.4  542.16
  4975.4  542.35  4992.9  540.73  5005.9  540.57  5006.4  540.07  5012.2  540.57
  5040.4  543.16  5046.2  542.47  5076.4  542.75  5142.1  544.83  5165.9  544.78
  5367.1  547.64  5608.9  549.97  5713.1  549.97  5815.3  551.47  5836.8     551
    5917  551.82  6239.2  556.42  6253.5  557.05  6280.8  556.56  6384.6  558.89
#Mann= 9 ,-1 , 0
  3995.4     .05       0  4113.5     .07       0  4131.4     .12       0
  4229.8     .07       0  4530.2     .12       0  5005.9     .05       0
  5012.2     .12       0  5165.9     .07       0  6239.2     .05       0
Bank Sta=5005.9,5012.2
XS Rating Curve= 0 ,0
Exp/Cntr=0.3,0.1

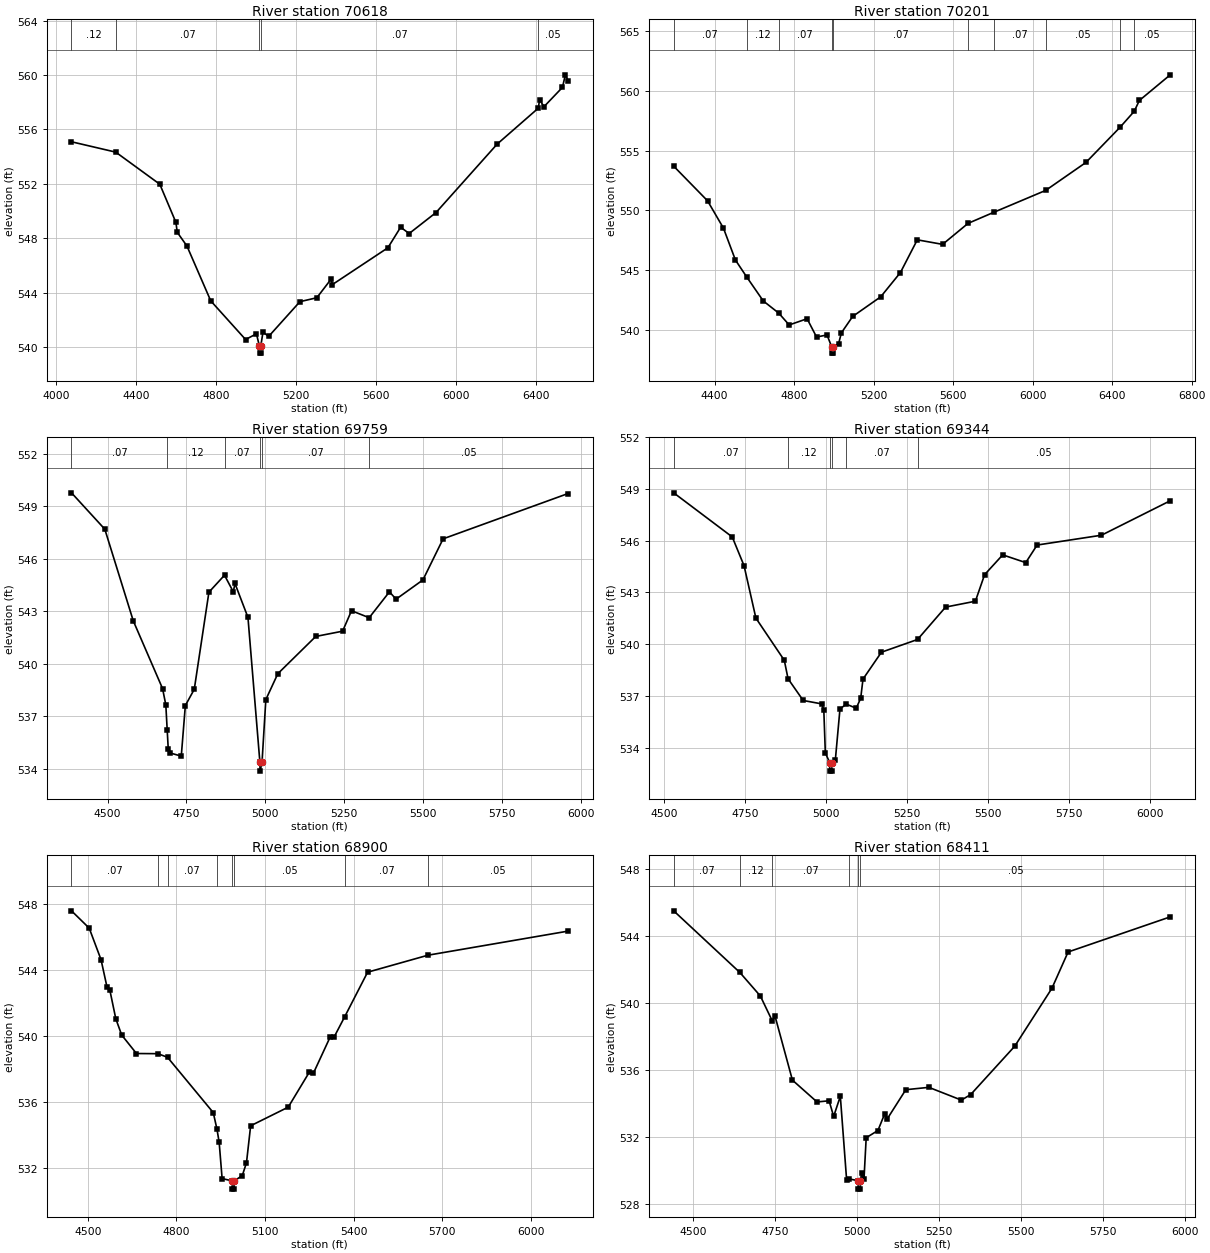
Type RM Length L Ch R = 1 ,70618   ,417,417,417
BEGIN DESCRIPTION:
NASH CREEK 122.0
END DESCRIPTION:
XS GIS Cut Line= 3
      2348325.01     13778025.03        2348125.       13777125.
      2347125.02     13775925.03
#Sta/Elev= 30
    4078  555.09  4299.3  554.33  4519.8  551.97  4600.5  549.16  4606.9  548.44
  4655.5  547.43  4774.6   543.4  4948.8  540.56  5003.2  540.98  5018.2  540.06
  5018.7  539.56  5024.2  539.56  5024.7  540.06  5035.8   541.1  5064.4  540.79
  5220.6  543.34  5305.2  543.63  5376.8     545  5383.3   544.6  5660.6   547.3
  5724.4  548.81  5767.3  548.35  5901.4  549.89  6207.3  554.92  6413.1  557.56
  6419.5  558.18  6441.6  557.67    6534  559.09  6548.4  560.01    6562  559.58
#Mann= 5 ,-1 , 0
    4078     .12       0  4299.3     .07       0  5018.2     .05       0
  5024.7     .07       0  6413.1     .05       0
Bank Sta=5018.2,5024.7
XS Rating Curve= 0 ,0
Exp/Cntr=0.3,0.1

Type RM Length L Ch R = 1 ,70201   ,442,442,442
BEGIN DESCRIPTION:
NASH CREEK 121.0
END DESCRIPTION:
XS GIS Cut Line= 3
        2348425.     13777724.95        2348475.       13776925.
      2347274.98     13775724.98
#Sta/Elev= 30
  4193.7  553.69    4364  550.79  4444.1   548.5  4504.3  545.83  4560.7  544.42
  4644.5   542.4  4722.4  541.38  4774.8  540.39    4865  540.91  4912.6  539.38
  4965.2  539.55  4989.5  538.53    4990  538.03  4995.5  538.03    4996  538.53
  5023.5  538.82  5037.6  539.73  5094.2   541.1  5235.6  542.75  5334.6  544.78
  5419.5  547.52  5546.8  547.14    5675   548.9  5807.8  549.85  6065.6  551.66
    6268     554  6440.4  556.96  6511.3  558.29  6536.7  559.19  6692.3  561.34
#Mann= 10 ,-1 , 0
  4193.7     .07       0  4560.7     .12       0  4722.4     .07       0
  4989.5     .05       0    4996     .07       0    5675     .05       0
  5807.8     .07       0  6065.6     .05       0  6440.4     .07       0
  6511.3     .05       0
Bank Sta=4989.5,4996
XS Rating Curve= 0 ,0
Exp/Cntr=0.3,0.1

Type RM Length L Ch R = 1 ,69759   ,415,415,415
BEGIN DESCRIPTION:
NASH CREEK 120.0
END DESCRIPTION:
XS GIS Cut Line= 3
        2348975.     13777274.99        2348825.       13776675.
        2348125.       13776025.
#Sta/Elev= 30
  4385.7  549.78  4491.3   547.7  4581.5  542.46  4674.3  538.59  4684.6  537.66
    4689  536.22  4692.3  535.14  4697.5  534.91  4733.6  534.73  4746.5  537.62
  4774.8  538.55  4821.2   544.1  4870.6  545.07  4898.5  544.12  4903.7   544.6
  4944.9  542.66  4982.8  534.37  4983.3  533.87  4989.5  534.37  5001.6  537.96
  5039.6  539.44  5159.8  541.57  5244.8  541.87  5273.1  543.04  5329.1  542.64
  5393.3  544.12  5414.3   543.7  5499.4   544.8  5563.4  547.15  5959.4  549.74
#Mann= 6 ,-1 , 0
  4385.7     .07       0    4689     .12       0  4870.6     .07       0
  4982.8     .05       0  4989.5     .07       0  5329.1     .05       0
Bank Sta=4982.8,4989.5
XS Rating Curve= 0 ,0
Exp/Cntr=0.3,0.1

Type RM Length L Ch R = 1 ,69344   ,444,444,444
BEGIN DESCRIPTION:
NASH CREEK 119.0
END DESCRIPTION:
XS GIS Cut Line= 3
      2349424.98     13776924.97        2349175.       13776525.
      2348374.99     13775824.99
#Sta/Elev= 30
  4528.5  548.78  4709.5  546.22    4746  544.55  4782.6  541.51  4870.4  539.06
    4882  537.99  4928.8  536.73  4986.6  536.53  4992.5  536.17  4997.2  533.69
  5010.5  533.13    5011  532.63  5016.8  532.63  5017.3  533.13  5028.2  533.29
  5042.4  536.23  5061.6  536.52  5092.7  536.28  5106.5  536.86  5113.6  537.97
  5170.5  539.53  5282.2  540.27  5368.9  542.15    5461  542.49  5489.4  544.03
  5545.4  545.18  5616.6  544.73  5651.7  545.75  5850.6  546.32  6063.2  548.32
#Mann= 6 ,-1 , 0
  4528.5     .07       0    4882     .12       0  5010.5     .05       0
  5017.3     .12       0  5061.6     .07       0  5282.2     .05       0
Bank Sta=5010.5,5017.3
XS Rating Curve= 0 ,0
Exp/Cntr=0.3,0.1

Type RM Length L Ch R = 1 ,68900   ,489,489,489
BEGIN DESCRIPTION:
NASH CREEK 118.0
END DESCRIPTION:
XS GIS Cut Line= 3
        2349525.     13776825.04        2349525.       13776275.
      2348725.01     13775475.01
#Sta/Elev= 30
  4444.8  547.59  4504.8  546.54  4544.8  544.63  4564.8  542.99  4574.8  542.77
  4594.8  541.05  4614.8  540.06  4664.8  538.94  4737.5  538.93    4770  538.71
  4924.8  535.36  4937.3  534.36  4944.8  533.56  4954.8  531.36  4988.9  531.22
  4989.4  530.72  4995.3  530.72  4995.8  531.22  5023.1  531.54  5037.3  532.32
  5051.4  534.56  5178.7  535.69  5249.4  537.79  5263.5  537.73  5320.1  539.92
  5334.3  539.95  5370.2  541.18  5447.4  543.87  5651.8   544.9  6126.2  546.36
#Mann= 8 ,-1 , 0
  4444.8     .07       0  4737.5     .12       0    4770     .07       0
  4937.3     .05       0  4988.9     .05       0  4995.8     .05       0
  5370.2     .07       0  5651.8     .05       0
Bank Sta=4988.9,4995.8
XS Rating Curve= 0 ,0
Exp/Cntr=0.3,0.1

Type RM Length L Ch R = 1 ,68411   ,466,466,466
BEGIN DESCRIPTION:
NASH CREEK 117.0
END DESCRIPTION:
XS GIS Cut Line= 3
      2349874.99     13776775.04        2349975.       13776225.
      2349275.01     13775575.01
#Sta/Elev= 30
  4440.8  545.48  4642.6  541.81  4705.1  540.41  4742.1   538.9  4749.6  539.23
  4802.9   535.4  4877.9   534.1  4914.7  534.17  4928.7  533.24    4949  534.44
  4968.1  529.48  4975.6  529.52  5003.4  529.41  5003.9  528.91  5009.9  528.91
  5010.4  529.41  5013.8  529.88  5021.1  529.49  5027.9  531.97  5063.6   532.4
  5084.6  533.41    5092  533.09  5148.7  534.83    5219  534.97  5318.2  534.21
  5346.5  534.54  5480.9  537.42  5594.3  540.87  5643.6  543.03  5955.1  545.12
#Mann= 6 ,-1 , 0
  4440.8     .07       0  4642.6     .12       0  4742.1     .07       0
  4975.6     .05       0  5003.4     .05       0  5010.4     .05       0
Bank Sta=5003.4,5010.4
XS Rating Curve= 0 ,0
Exp/Cntr=0.3,0.1

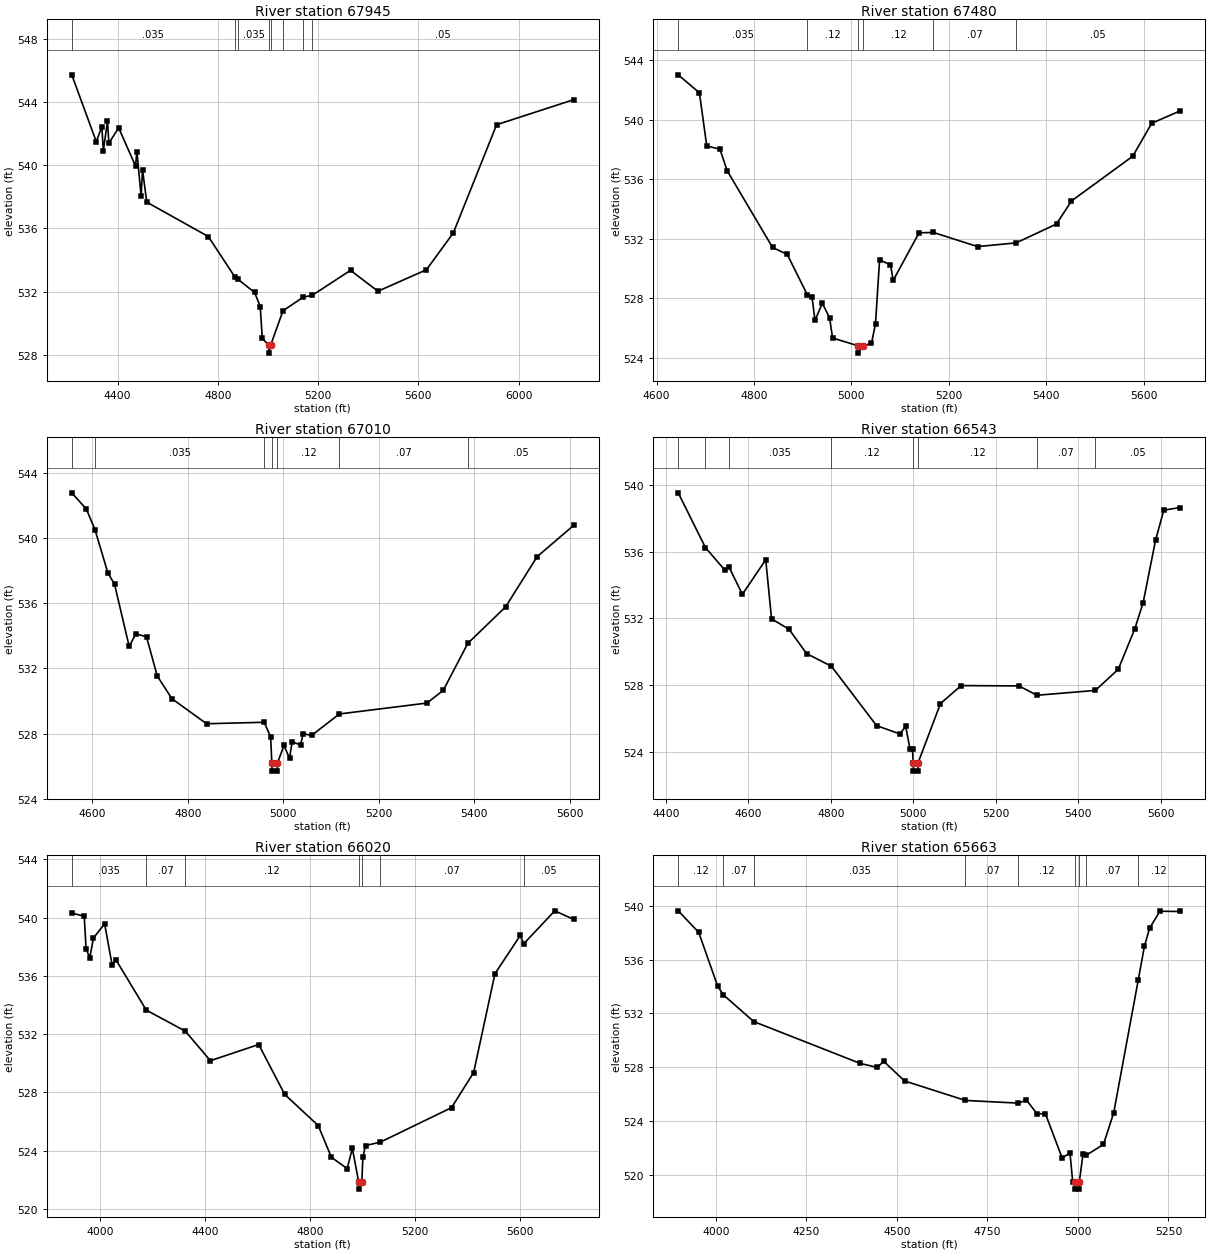
Type RM Length L Ch R = 1 ,67945   ,465,465,465
BEGIN DESCRIPTION:
NASH CREEK 116.0
END DESCRIPTION:
XS GIS Cut Line= 3
      2350075.01     13776974.99        2350425.       13776275.
      2349424.97     13775574.98
#Sta/Elev= 30
  4217.4  545.72  4315.2  541.49  4337.6  542.44  4343.2   540.9  4359.9  542.77
  4365.5   541.4  4404.7  542.36  4471.7  539.95  4477.3  540.86  4494.1  538.05
  4499.7  539.72  4516.5  537.66  4762.4  535.48  4868.2  532.92  4880.7  532.77
  4946.9  531.94  4969.3  531.05  4977.6  529.03  5003.9   528.6  5004.4   528.1
  5010.9   528.6  5060.1  530.78  5140.5  531.64  5177.9  531.77  5329.6  533.34
    5439  532.02  5632.6  533.38  5739.8  535.71  5912.5  542.56  6220.7  544.15
#Mann= 8 ,-1 , 0
  4217.4    .035       0  4868.2     .12       0  4880.7    .035       0
  5003.9    .035       0  5010.9    .035       0  5060.1     .12       0
  5140.5     .07       0  5177.9     .05       0
Bank Sta=5003.9,5010.9
XS Rating Curve= 0 ,0
Exp/Cntr=0.3,0.1

Type RM Length L Ch R = 1 ,67480   ,470,470,470
BEGIN DESCRIPTION:
NASH CREEK 115.0
END DESCRIPTION:
XS GIS Cut Line= 3
      2350774.98     13776224.97        2350575.       13775925.
      2350275.02     13775325.04
#Sta/Elev= 30
  4644.3  543.03  4687.8  541.82  4702.9  538.24  4729.9  538.03  4744.9  536.57
  4838.1  531.41  4868.1  530.95  4909.7  528.21  4919.2  528.05  4925.2  526.51
  4940.2  527.65  4955.2  526.68  4961.3  525.32  5012.9   524.8  5013.4   524.3
  5024.7   524.8  5041.2  524.95  5049.5  526.28  5057.9  530.58  5080.3  530.24
  5085.9   529.2    5139   532.4  5168.5  532.42  5259.2  531.47  5338.3  531.72
  5421.3  532.99    5452  534.54  5577.8  537.55  5616.9  539.77  5675.6  540.61
#Mann= 6 ,-1 , 0
  4644.3    .035       0  4909.7     .12       0  5012.9     .05       0
  5024.7     .12       0  5168.5     .07       0  5338.3     .05       0
Bank Sta=5012.9,5024.7
XS Rating Curve= 0 ,0
Exp/Cntr=0.3,0.1

Type RM Length L Ch R = 1 ,67010   ,467,467,467
BEGIN DESCRIPTION:
NASH CREEK 114.0
END DESCRIPTION:
XS GIS Cut Line= 3
      2351075.01     13775975.02        2350875.       13775575.
      2350324.98     13775324.99
#Sta/Elev= 30
  4557.1  542.78  4587.9  541.77  4605.8  540.51  4632.6  537.87  4646.6  537.17
  4677.3  533.35  4691.3  534.12  4713.6  533.94    4736  531.54  4766.7  530.14
  4839.4   528.6    4960  528.69  4973.6  527.79    4976  526.19  4976.5  525.69
  4987.4  525.69  4987.9  526.19  5001.5  527.27  5013.1  526.48  5018.6   527.5
  5036.2  527.29  5041.7  527.99  5059.3  527.88  5117.4   529.2  5300.9  529.87
    5335  530.65  5386.3  533.53  5465.7  535.78  5531.6  538.86  5608.5  540.79
#Mann= 7 ,-1 , 0
  4557.1     .12       0  4605.8    .035       0    4960     .12       0
    4976     .05       0  4987.9     .12       0  5117.4     .07       0
  5386.3     .05       0
Bank Sta=4976,4987.9
XS Rating Curve= 0 ,0
Exp/Cntr=0.3,0.1

Type RM Length L Ch R = 1 ,66543   ,523,523,523
BEGIN DESCRIPTION:
NASH CREEK 113.0
END DESCRIPTION:
XS GIS Cut Line= 3
      2351525.02     13775625.02        2351125.       13775225.
      2350475.04       13775175.
#Sta/Elev= 30
  4429.9  539.52  4495.8  536.24  4543.1  534.88  4552.4   535.1  4585.5  533.43
  4642.1  535.51  4656.2  531.96  4698.6  531.34  4741.1  529.88  4801.4  529.12
  4910.8  525.56  4967.3  525.06  4981.5  525.51  4992.1  524.14  4998.1  524.14
  4999.7  523.33  5000.2  522.83  5011.1  522.83  5011.6  523.33  5065.8  526.88
    5116  527.96  5256.4  527.94  5299.8  527.38  5441.6  527.67  5497.1  528.94
  5537.2  531.37  5557.3  532.93  5587.4  536.67  5607.4  538.48  5647.5  538.64
#Mann= 8 ,-1 , 0
  4429.9     .07       0  4495.8     .12       0  4552.4    .035       0
  4801.4     .12       0  4999.7     .05       0  5011.6     .12       0
  5299.8     .07       0  5441.6     .05       0
Bank Sta=4999.7,5011.6
XS Rating Curve= 0 ,0
Exp/Cntr=0.3,0.1

Type RM Length L Ch R = 1 ,66020   ,357,357,357
BEGIN DESCRIPTION:
B19771
END DESCRIPTION:
XS GIS Cut Line= 4
      2351802.22     13775444.92      2351182.04     13774846.12
      2350854.11     13774831.86      2350199.14     13775137.99
#Sta/Elev= 30
  3892.1  540.31  3939.6  540.09  3946.6  537.84  3960.7  537.25  3974.9   538.6
  4017.3  539.57  4045.6  536.77  4059.8  537.12    4176  533.65  4324.6  532.21
  4420.4  530.18  4604.4  531.29  4703.4  527.87  4831.3  525.73  4881.3  523.56
  4941.4  522.78  4961.4  524.16  4985.4  521.87  4985.9  521.37  4997.5  521.87
  5001.5  523.56  5011.5  524.36  5067.6  524.59  5339.3  526.96  5423.6  529.37
  5504.8  536.15  5601.7  538.78  5613.9  538.19  5732.7  540.46  5805.4  539.87
#Mann= 7 ,-1 , 0
  3892.1    .035       0    4176     .07       0  4324.6     .12       0
  4985.4     .05       0  4997.5     .12       0  5067.6     .07       0
  5613.9     .05       0
Bank Sta=4985.4,4997.5
XS Rating Curve= 0 ,0
Exp/Cntr=0.3,0.1

Type RM Length L Ch R = 1 ,65663   ,391,391,391
BEGIN DESCRIPTION:
NASH CREEK 112.0
END DESCRIPTION:
XS GIS Cut Line= 3
       2351984.7     13774971.52        2350975.       13774525.
      2350774.98     13774324.98
#Sta/Elev= 30
  3895.9  539.64  3952.4  538.04  4004.9  534.03  4020.5  533.39  4104.4   531.4
  4399.1  528.28  4445.7  527.99  4463.5  528.44    4521  526.98  4689.4  525.53
  4835.7  525.33  4857.8  525.56  4886.9  524.54  4910.2  524.54  4956.2  521.26
  4978.1  521.62  4985.5  519.46  4990.7  519.43  4991.2  518.93  5003.1  518.93
  5003.6  519.43  5014.1  521.56  5023.5  521.46  5070.6  522.26  5098.9  524.62
  5166.7  534.51  5183.8  537.02  5197.9  538.34  5226.2  539.61  5282.8  539.59
#Mann= 9 ,-1 , 0
  3895.9     .12       0  4020.5     .07       0  4104.4    .035       0
  4689.4     .07       0  4835.7     .12       0  4990.7     .05       0
  5003.6     .12       0  5023.5     .07       0  5166.7     .12       0
Bank Sta=4990.7,5003.6
XS Rating Curve= 0 ,0
Exp/Cntr=0.3,0.1

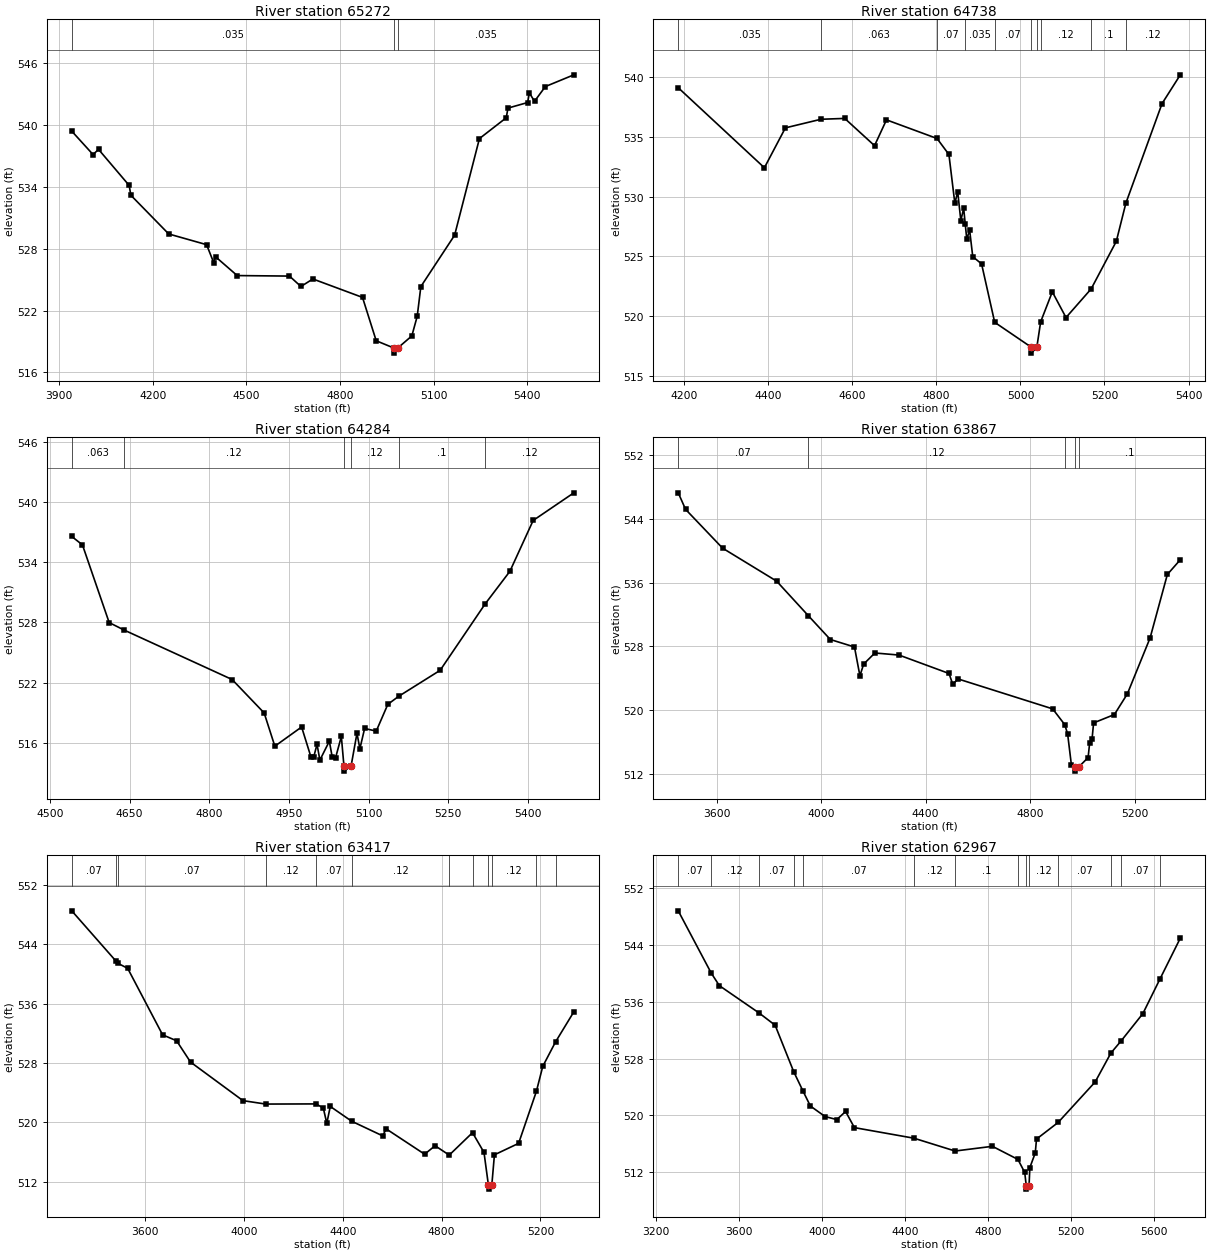
Type RM Length L Ch R = 1 ,65272   ,534,534,534
BEGIN DESCRIPTION:
NASH CREEK 111.0
END DESCRIPTION:
XS GIS Cut Line= 3
      2352234.57     13774766.81      2351277.21      13774336.3
       2350770.9     13774099.62
#Sta/Elev= 30
  3940.3  539.43  4008.4  537.16  4026.1  537.66  4124.2  534.16  4129.6  533.21
  4250.9  529.45  4372.2  528.41  4395.3  526.65  4400.8  527.24  4470.3  525.41
  4637.8  525.36  4674.5  524.35  4712.8  525.08  4871.8  523.29  4915.7  519.08
    4972  518.38  4972.5  517.88  4984.9  518.38  5029.8  519.55  5047.1  521.46
  5058.7  524.34  5166.9  529.33  5246.4  538.71  5332.3  540.73  5337.8  541.67
  5400.8  542.21  5406.4  543.14  5422.9  542.33  5457.6  543.76  5548.9   544.9
#Mann= 3 ,-1 , 0
  3940.3    .035       0    4972    .035       0  4984.9    .035       0
Bank Sta=4972,4984.9
XS Rating Curve= 0 ,0
Exp/Cntr=0.3,0.1

Type RM Length L Ch R = 1 ,64738   ,454,454,454
BEGIN DESCRIPTION:
NASH CREEK 110.0
END DESCRIPTION:
XS GIS Cut Line= 3
        2352275.       13774725.        2351725.       13774125.
      2351575.01     13773775.03
#Sta/Elev= 30
  4185.7  539.11  4390.7  532.41  4440.7  535.75  4525.4  536.47  4581.9  536.54
  4652.8  534.26  4681.2  536.42  4801.5  534.86  4829.8  533.52  4843.9  529.43
  4850.7   530.4  4858.1  527.99  4864.9  529.01  4868.7  527.68  4872.3  526.42
  4879.1  527.19  4886.5  524.97  4907.5  524.36  4938.7  519.47  5025.6  517.39
  5026.1  516.89    5039  517.39  5048.1  519.51  5075.8  522.02  5108.4  519.87
  5168.3  522.27  5228.1  526.25  5250.8  529.44  5336.9  537.78  5380.4  540.19
#Mann= 10 ,-1 , 0
  4185.7    .035       0  4525.4    .063       0  4801.5     .07       0
  4868.7    .035       0  4938.7     .07       0  5025.6     .05       0
    5039     .07       0  5048.1     .12       0  5168.3      .1       0
  5250.8     .12       0
Bank Sta=5025.6,5039
XS Rating Curve= 0 ,0
Exp/Cntr=0.3,0.1

Type RM Length L Ch R = 1 ,64284   ,417,417,417
BEGIN DESCRIPTION:
NASH CREEK 109.0
END DESCRIPTION:
XS GIS Cut Line= 3
        2352075.     13774375.01        2352025.       13773925.
      2351575.02     13773725.01
#Sta/Elev= 30
  4541.1  536.59  4561.2  535.75  4611.5  527.99  4639.7  527.24    4843   522.3
  4903.3  518.96  4923.4  515.64  4973.8  517.56  4991.4  514.56  4996.6  514.56
  5002.8  515.83  5008.2  514.25    5026  516.14  5031.5  514.53  5037.7  514.48
  5048.6  516.61  5053.5  513.65    5054  513.15  5066.9  513.65    5078  516.93
  5083.5  515.39  5092.4  517.41  5114.3  517.15  5136.1  519.82  5156.4  520.62
  5234.6  523.22  5319.4  529.86  5365.9  533.11  5409.7  538.19  5486.3  540.95
#Mann= 6 ,-1 , 0
  4541.1    .063       0  4639.7     .12       0  5053.5     .05       0
  5066.9     .12       0  5156.4      .1       0  5319.4     .12       0
Bank Sta=5053.5,5066.9
XS Rating Curve= 0 ,0
Exp/Cntr=0.3,0.1

Type RM Length L Ch R = 1 ,63867   ,450,450,450
BEGIN DESCRIPTION:
NASH CREEK 108.0
END DESCRIPTION:
XS GIS Cut Line= 3
      2353324.98     13774624.98        2352125.       13773625.
      2351924.99     13773324.98
#Sta/Elev= 30
  3452.8  547.25  3480.8  545.18  3622.6  540.31  3829.6  536.17  3950.3  531.86
  4035.3  528.85  4127.7  527.91  4148.5   524.3  4162.9  525.77  4205.8  527.16
  4298.2   526.9  4489.6  524.59  4503.9  523.25  4524.7   523.9  4886.6  520.15
  4932.9  518.17  4943.9     517  4958.2  513.15  4972.3  512.84  4972.8  512.34
  4985.8  512.84  5022.3  514.04  5028.3  515.89  5037.4  516.37  5043.4  518.39
    5123  519.44  5172.6  522.03  5259.7  529.05  5325.8  537.01  5375.4  538.86
#Mann= 5 ,-1 , 0
  3452.8     .07       0  3950.3     .12       0  4932.9      .1       0
  4972.3     .05       0  4985.8      .1       0
Bank Sta=4972.3,4985.8
XS Rating Curve= 0 ,0
Exp/Cntr=0.3,0.1

Type RM Length L Ch R = 1 ,63417   ,450,450,450
BEGIN DESCRIPTION:
NASH CREEK 107.0
END DESCRIPTION:
XS GIS Cut Line= 3
        2353575.       13774475.        2352375.       13773275.
      2352074.97     13773124.98
#Sta/Elev= 30
  3302.7  548.49  3481.2  541.74  3489.8  541.42    3529  540.75  3670.4   531.8
    3727     531  3783.5  528.13  3995.7  522.94  4087.9  522.48  4291.1   522.5
  4320.9  521.95  4335.1  519.89  4349.2  522.16  4435.8  520.17  4561.3   518.2
  4575.5  519.14  4731.1  515.73  4773.5  516.87  4830.7  515.61    4925  518.63
  4971.5  515.97  4989.5  511.53    4990  511.03    5003  511.53  5013.7  515.65
  5111.6  517.19  5183.5  524.18  5209.4  527.56    5261  530.84  5335.2   534.9
#Mann= 12 ,-1 , 0
  3302.7     .07       0  3481.2     .12       0  3489.8     .07       0
  4087.9     .12       0  4291.1     .07       0  4435.8     .12       0
  4830.7      .1       0    4925     .12       0  4989.5     .05       0
    5003     .12       0  5183.5      .1       0    5261     .12       0
Bank Sta=4989.5,5003
XS Rating Curve= 0 ,0
Exp/Cntr=0.3,0.1

Type RM Length L Ch R = 1 ,62967   ,424,424,424
BEGIN DESCRIPTION:
NASH CREEK 106.0
END DESCRIPTION:
XS GIS Cut Line= 3
        2353925.       13774225.        2352725.       13773025.
      2352124.98     13772624.98
#Sta/Elev= 30
  3307.4  548.77    3466  540.03  3505.4  538.25  3696.9   534.4  3774.1  532.68
  3863.8  526.13  3908.5  523.41  3943.8  521.32  4014.5  519.84  4071.1  519.41
  4113.5  520.55  4155.9  518.28  4442.9  516.79  4640.9  514.99  4820.6  515.65
  4943.4  513.81  4976.2  511.98  4983.5  510.13    4984  509.63  4997.1  510.13
  5000.9  512.66    5027  514.72    5033  516.67  5137.2  519.01  5315.4   524.7
  5391.1  528.76  5441.5  530.51  5545.3  534.32  5626.7  539.13  5725.6  544.93
#Mann= 14 ,-1 , 0
  3307.4     .07       0    3466     .12       0  3696.9     .07       0
  3863.8     .12       0  3908.5     .07       0  4442.9     .12       0
  4640.9      .1       0  4943.4     .12       0  4983.5     .05       0
  4997.1     .12       0  5137.2     .07       0  5391.1     .12       0
  5441.5     .07       0  5626.7     .12       0
Bank Sta=4983.5,4997.1
XS Rating Curve= 0 ,0
Exp/Cntr=0.3,0.1