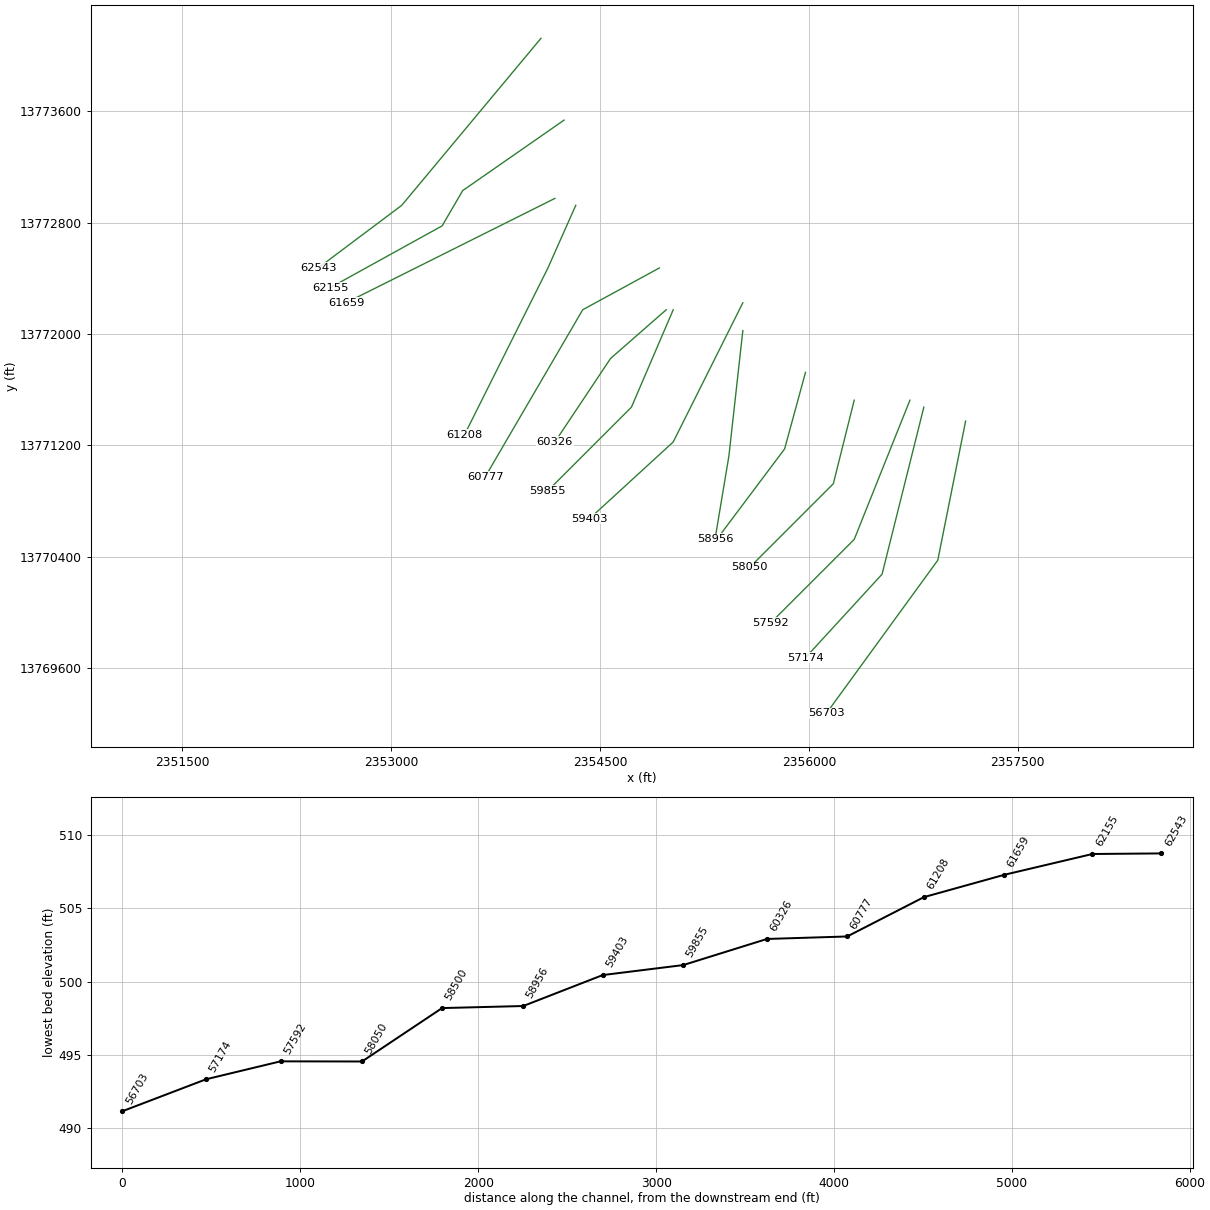
HEC-RAS study NASH CREEK.prj: NASH CREEK Base Level Engineering

--- NASH CREEK.g01 (geometry) --- (continued)

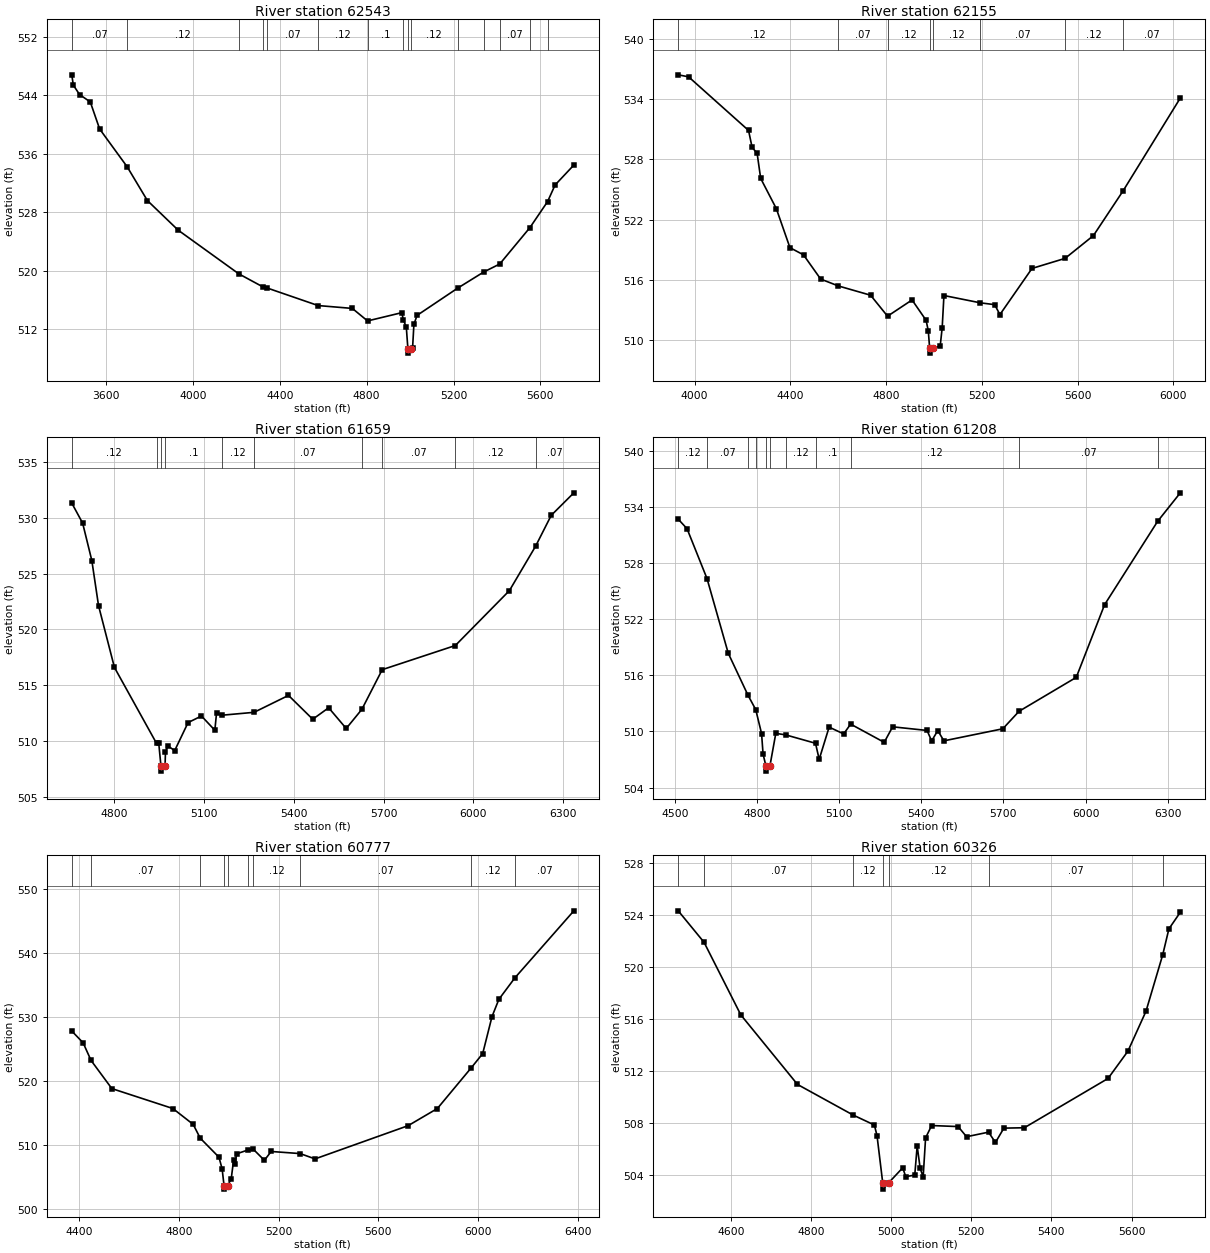
Type RM Length L Ch R = 1 ,62543   ,388,388,388
BEGIN DESCRIPTION:
NASH CREEK 105.0
END DESCRIPTION:
XS GIS Cut Line= 3
      2354075.02     13774125.03        2353075.       13772925.
      2352474.99     13772474.99
#Sta/Elev= 30
  3442.1  546.77  3449.3  545.36  3477.9  544.08  3527.4  543.06  3570.4  539.37
  3697.3   534.2  3790.3  529.59  3932.2  525.54  4211.5  519.57  4324.3  517.76
  4342.9  517.63  4576.6  515.24  4734.1  514.85  4804.2  513.14  4961.9  514.27
  4969.1  513.29  4982.7  512.28  4990.2  509.24  4990.7  508.74  5003.9  509.24
  5011.5  509.42  5017.7  512.68  5032.3   513.9  5218.6  517.61  5339.4  519.83
    5413  520.92  5552.1   525.9  5633.3  529.45  5667.7  531.71  5754.2  534.44
#Mann= 15 ,-1 , 0
  3442.1     .07       0  3697.3     .12       0  4211.5     .07       0
  4324.3     .12       0  4342.9     .07       0  4576.6     .12       0
  4804.2      .1       0  4969.1     .12       0  4990.2     .05       0
  5003.9     .12       0  5218.6     .07       0  5339.4     .12       0
    5413     .07       0  5552.1     .12       0  5633.3     .07       0
Bank Sta=4990.2,5003.9
XS Rating Curve= 0 ,0
Exp/Cntr=0.3,0.1

Type RM Length L Ch R = 1 ,62155   ,496,496,496
BEGIN DESCRIPTION:
B19770
END DESCRIPTION:
XS GIS Cut Line= 4
       2354241.3     13773537.63      2353512.88      13773030.9
      2353365.09     13772777.55      2352562.79     13772334.18
#Sta/Elev= 30
  3931.3  536.43  3974.6  536.23    4225  530.89  4239.9   529.2  4260.8  528.61
  4275.7  526.11    4341   523.1  4397.9  519.21  4454.6  518.49  4526.2  516.08
  4600.6  515.39  4734.8  514.47  4805.7  512.38    4908     514  4966.7  511.97
    4976   510.9  4981.4   509.2  4981.9   508.7  4995.1   509.2  5025.4  509.38
  5033.9  511.23  5041.2  514.44  5193.6  513.71  5253.2  513.53    5275  512.54
  5409.1  517.14  5547.2  518.14  5665.6  520.41  5789.6  524.87  6028.6  534.12
#Mann= 8 ,-1 , 0
  3931.3     .12       0  4600.6     .07       0  4805.7     .12       0
  4981.4     .05       0  4995.1     .12       0  5193.6     .07       0
  5547.2     .12       0  5789.6     .07       0
Bank Sta=4981.4,4995.1
XS Rating Curve= 0 ,0
Exp/Cntr=0.3,0.1

Type RM Length L Ch R = 1 ,61659   ,451,451,451
BEGIN DESCRIPTION:
NASH CREEK 104.0
END DESCRIPTION:
XS GIS Cut Line= 3
      2354174.96     13772974.98        2353875.       13772825.
        2352675.       13772225.
#Sta/Elev= 30
  4658.6  531.35  4694.9  529.55  4725.6  526.19    4748  522.14  4801.1  516.59
  4941.8  509.77  4949.2  509.77  4956.3  507.78  4956.8  507.28  4970.2  507.78
  4971.6  509.02    4980  509.54  5002.3  509.12  5047.1  511.64  5091.8  512.23
  5136.5  510.95  5142.1  512.48  5160.1   512.3  5267.4  512.56  5382.5  514.08
  5463.5  511.94  5516.6  512.97  5575.3  511.11  5627.6  512.83  5695.5  516.39
  5939.8  518.56  6120.4  523.49  6207.7  527.47  6260.1  530.25  6335.6  532.27
#Mann= 10 ,-1 , 0
  4658.6     .12       0  4941.8      .1       0  4956.3     .05       0
  4970.2      .1       0  5160.1     .12       0  5267.4     .07       0
  5627.6     .12       0  5695.5     .07       0  5939.8     .12       0
  6207.7     .07       0
Bank Sta=4956.3,4970.2
XS Rating Curve= 0 ,0
Exp/Cntr=0.3,0.1

Type RM Length L Ch R = 1 ,61208   ,431,431,431
BEGIN DESCRIPTION:
NASH CREEK 103.0
END DESCRIPTION:
XS GIS Cut Line= 3
      2354325.02     13772925.04        2354125.       13772475.
      2353525.01     13771275.03
#Sta/Elev= 30
  4512.1  532.71  4544.3  531.69  4617.3  526.35  4694.8  518.37  4766.7  513.89
  4795.2  512.34  4816.5  509.78    4822  507.59  4832.8  506.26  4833.3  505.76
  4846.7  506.26  4868.5   509.8  4904.3  509.64  5013.6  508.74    5027  507.02
  5063.3  510.47  5116.4  509.74  5141.9  510.79  5264.5  508.84  5295.3   510.5
  5421.1  510.11  5437.8  508.99  5460.2   510.1  5482.6     509  5697.8  510.29
  5757.1  512.16  5966.1  515.79  6069.5  523.56  6263.3  532.48  6346.2  535.53
#Mann= 11 ,-1 , 0
  4512.1     .12       0  4617.3     .07       0  4766.7     .12       0
  4795.2      .1       0  4832.8     .05       0  4846.7      .1       0
  4904.3     .12       0  5013.6      .1       0  5141.9     .12       0
  5757.1     .07       0  6263.3     .12       0
Bank Sta=4832.8,4846.7
XS Rating Curve= 0 ,0
Exp/Cntr=0.3,0.1

Type RM Length L Ch R = 1 ,60777   ,451,451,451
BEGIN DESCRIPTION:
NASH CREEK 102.0
END DESCRIPTION:
XS GIS Cut Line= 3
      2354925.02     13772475.01        2354375.       13772175.
      2353674.98     13770974.97
#Sta/Elev= 30
    4369  527.77  4414.6  525.93  4446.2  523.19  4529.9  518.78  4774.8  515.67
  4856.5  513.19  4884.7  511.04  4959.9  508.07  4972.7  506.24  4980.5  503.58
    4981  503.08  4994.4  503.58  5009.2  504.71  5018.7  507.58  5024.9  506.95
  5030.7  508.59  5076.8   509.2  5098.1   509.3  5142.3  507.58  5169.6  508.96
  5285.9  508.63  5345.7   507.8  5719.5  512.99  5836.9  515.67  5973.6  522.06
  6018.8  524.24  6056.1  530.01  6083.8  532.72  6147.8  536.06  6384.8  546.54
#Mann= 10 ,-1 , 0
    4369     .12       0  4446.2     .07       0  4884.7     .12       0
  4980.5     .05       0  4994.4     .12       0  5076.8      .1       0
  5098.1     .12       0  5285.9     .07       0  5973.6     .12       0
  6147.8     .07       0
Bank Sta=4980.5,4994.4
XS Rating Curve= 0 ,0
Exp/Cntr=0.3,0.1

Type RM Length L Ch R = 1 ,60326   ,471,471,471
BEGIN DESCRIPTION:
NASH CREEK 101.0
END DESCRIPTION:
XS GIS Cut Line= 3
      2354974.99     13772174.99        2354575.       13771825.
        2354175.     13771225.01
#Sta/Elev= 30
  4469.1  524.31  4533.5  521.89  4625.2  516.31  4766.6  510.96  4905.2  508.61
  4958.4  507.84    4965  507.03  4979.2  503.41  4979.7  502.91  4994.5  503.41
  5029.1  504.55  5036.7  503.87  5059.2  503.99  5065.2  506.23  5072.7   504.5
  5080.2  503.86  5086.2  506.85  5101.3   507.8  5167.4  507.72  5188.4  506.94
  5243.2  507.29  5260.5   506.5  5281.5   507.6  5332.6  507.63  5541.4  511.42
    5591  513.52  5636.1  516.59  5677.9  520.94  5693.2  522.92  5721.7   524.2
#Mann= 7 ,-1 , 0
  4469.1     .12       0  4533.5     .07       0  4905.2     .12       0
  4979.2     .05       0  4994.5     .12       0  5243.2     .07       0
  5677.9     .12       0
Bank Sta=4979.2,4994.5
XS Rating Curve= 0 ,0
Exp/Cntr=0.3,0.1

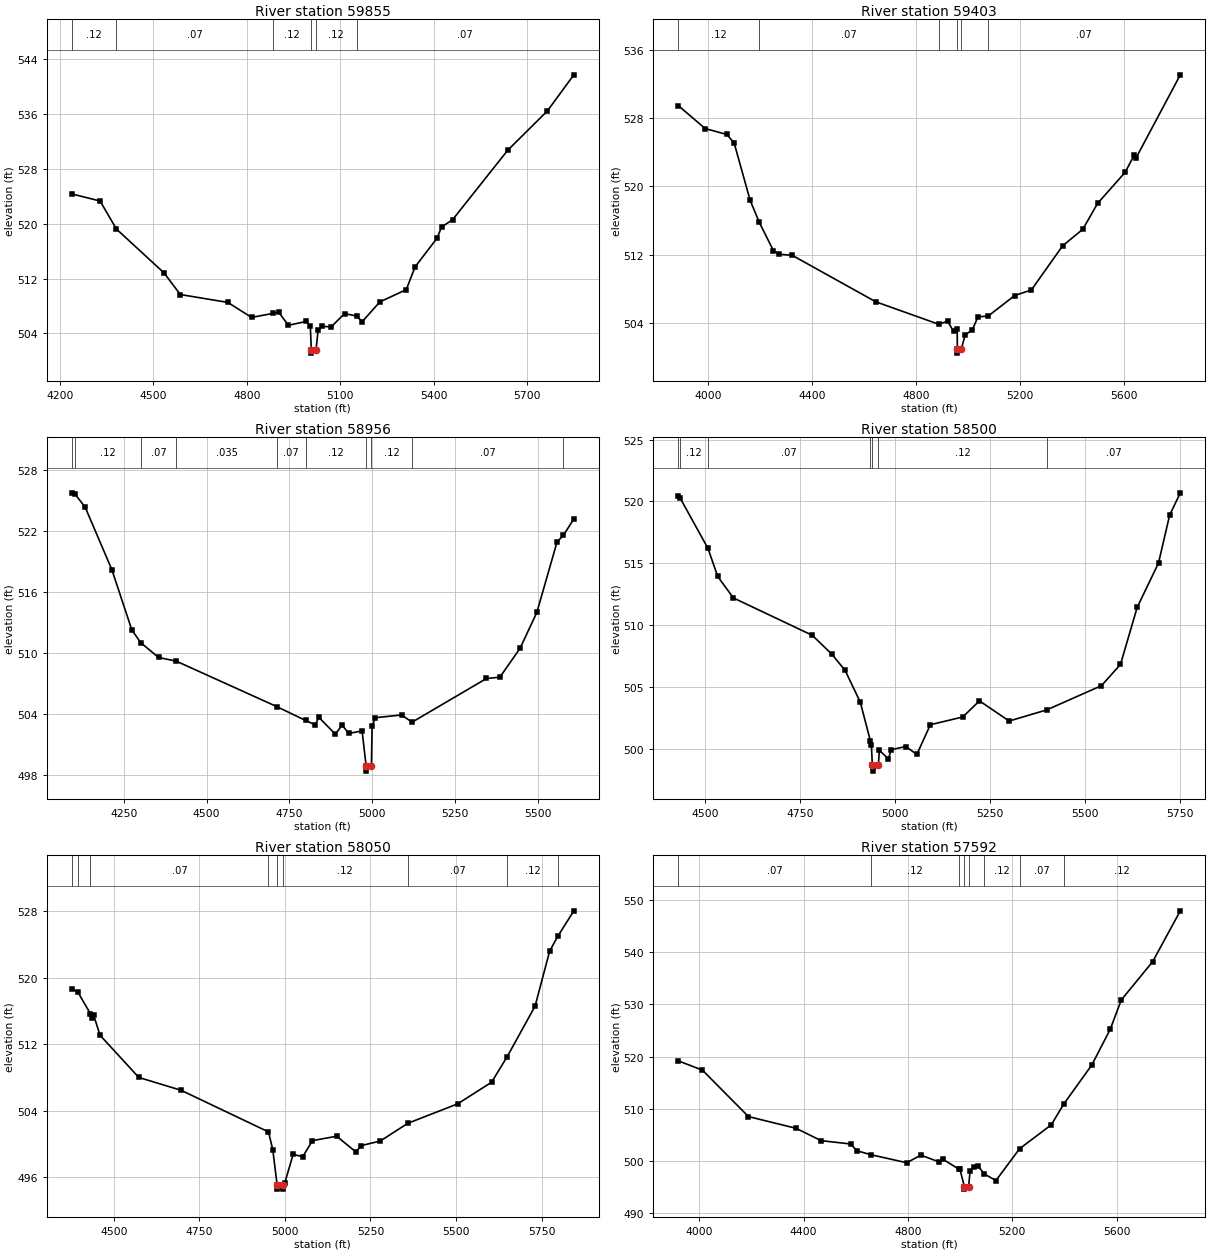
Type RM Length L Ch R = 1 ,59855   ,452,452,452
BEGIN DESCRIPTION:
NASH CREEK 100.0
END DESCRIPTION:
XS GIS Cut Line= 3
        2355025.     13772175.01        2354725.       13771475.
      2354125.01     13770875.01
#Sta/Elev= 30
  4238.9  524.36  4329.6  523.33  4382.2  519.23  4534.5  512.85  4587.1  509.68
  4739.4  508.53  4815.5  506.34  4883.1  506.92  4902.6  507.11  4933.4  505.19
  4991.4  505.76    5004  505.05    5007  501.63  5007.5  501.13  5022.3  501.63
  5028.8  504.47  5042.9  505.02  5071.2  504.98  5113.6   506.9    5152  506.55
  5170.2  505.72  5226.8   508.6  5311.6   510.4  5339.9  513.72  5410.6  517.92
  5424.7  519.53  5460.1   520.6  5636.9  530.73  5764.2  536.48    5849  541.74
#Mann= 6 ,-1 , 0
  4238.9     .12       0  4382.2     .07       0  4883.1     .12       0
    5007     .05       0  5022.3     .12       0    5152     .07       0
Bank Sta=5007,5022.3
XS Rating Curve= 0 ,0
Exp/Cntr=0.3,0.1

Type RM Length L Ch R = 1 ,59403   ,447,447,447
BEGIN DESCRIPTION:
NASH CREEK 99.0
END DESCRIPTION:
XS GIS Cut Line= 3
      2355524.98     13772224.96        2355025.       13771225.
      2354425.02     13770675.02
#Sta/Elev= 30
  3885.9   529.5  3989.3   526.8  4073.1   526.1  4101.1   525.1  4162.6  518.37
  4197.7   515.8    4252  512.48  4274.4  512.05  4324.7  511.92  4646.1  506.47
  4887.9  503.84  4922.8  504.19  4945.2     503  4959.2  503.23  4959.9  500.95
  4960.4  500.45  4975.3  500.95  4989.9  502.57  5017.8   503.2  5039.3  504.71
  5078.6   504.8  5180.6  507.21  5244.7  507.86  5364.9  513.04  5442.6  514.98
  5499.3  518.01  5605.4  521.66  5641.2  523.72    5648  523.38  5817.8   533.1
#Mann= 6 ,-1 , 0
  3885.9     .12       0  4197.7     .07       0  4887.9     .12       0
  4959.9     .05       0  4975.3     .12       0  5078.6     .07       0
Bank Sta=4959.9,4975.3
XS Rating Curve= 0 ,0
Exp/Cntr=0.3,0.1

Type RM Length L Ch R = 1 ,58956   ,456,456,456
BEGIN DESCRIPTION:
NASH CREEK 98.0
END DESCRIPTION:
XS GIS Cut Line= 3
        2355525.     13772025.02        2355425.       13771125.
      2355325.01     13770525.04
#Sta/Elev= 30
  4093.6  525.74  4102.8  525.64  4133.9  524.33  4214.4  518.18  4274.7  512.24
  4301.5  510.99  4355.2  509.53  4408.5  509.17  4711.9  504.69  4798.5  503.33
  4828.1  502.89  4838.2  503.65  4888.5  501.97  4908.6  502.88  4928.7  502.05
    4969   502.3  4981.1  498.84  4981.6  498.34  4997.1  498.84  4999.2  502.81
  5009.3   503.6  5087.9  503.87  5119.7  503.16  5343.9  507.46  5384.4  507.59
  5445.2  510.43  5495.9  513.97  5556.7   520.9  5575.9  521.56  5607.4  523.17
#Mann= 10 ,-1 , 0
  4093.6     .07       0  4102.8     .12       0  4301.5     .07       0
  4408.5    .035       0  4711.9     .07       0  4798.5     .12       0
  4981.1     .05       0  4997.1     .12       0  5119.7     .07       0
  5575.9     .12       0
Bank Sta=4981.1,4997.1
XS Rating Curve= 0 ,0
Exp/Cntr=0.3,0.1

Type RM Length L Ch R = 1 ,58500   ,450,450,450
BEGIN DESCRIPTION:
NASH CREEK 97.0
END DESCRIPTION:
XS GIS Cut Line= 3
      2355975.01     13771725.03        2355825.       13771175.
      2355375.01     13770575.02
#Sta/Elev= 30
  4429.9  520.47  4435.4  520.25  4508.2   516.2  4533.6  513.94    4575   512.2
  4782.4  509.18  4834.2  507.64  4868.7  506.34  4908.5  503.78  4935.2  500.64
  4937.8   500.3  4940.2   498.7  4940.7   498.2  4956.2   498.7  4958.6  499.88
  4982.7  499.19  4989.7  499.93  5028.1  500.19  5057.3  499.55  5092.7  501.95
  5178.1  502.58  5221.9  503.88    5300  502.25  5398.7  503.15  5542.7  505.11
  5592.7  506.83  5636.5  511.43  5692.7  515.03  5721.9  518.89    5750   520.7
#Mann= 7 ,-1 , 0
  4429.9     .07       0  4435.4     .12       0  4508.2     .07       0
  4935.2     .12       0  4940.2     .05       0  4956.2     .12       0
  5398.7     .07       0
Bank Sta=4940.2,4956.2
XS Rating Curve= 0 ,0
Exp/Cntr=0.3,0.1

Type RM Length L Ch R = 1 ,58050   ,458,458,458
BEGIN DESCRIPTION:
NASH CREEK 96.0
END DESCRIPTION:
XS GIS Cut Line= 3
      2356324.99     13771524.97        2356175.       13770925.
      2355574.98     13770324.98
#Sta/Elev= 30
  4377.3  518.69  4395.5  518.26    4432  515.66  4436.5  515.11  4441.7  515.47
  4459.7   513.1  4573.1  508.01  4696.8  506.46  4952.1  501.45  4964.8  499.27
  4977.3  495.06  4977.8  494.56  4993.1  494.56  4993.6  495.06  4999.3  495.25
    5024  498.73  5052.3  498.48  5080.6   500.4  5151.3  500.93  5207.9  499.02
    5222  499.79  5278.6  500.35  5359.4  502.49  5504.9  504.83  5603.9  507.43
  5649.4   510.5  5731.1   516.6  5773.6  523.22  5797.9  525.04  5844.3  528.07
#Mann= 9 ,-1 , 0
  4377.3     .07       0  4395.5     .12       0    4432     .07       0
  4952.1     .12       0  4977.3     .05       0  4993.6     .12       0
  5359.4     .07       0  5649.4     .12       0  5797.9     .07       0
Bank Sta=4977.3,4993.6
XS Rating Curve= 0 ,0
Exp/Cntr=0.3,0.1

Type RM Length L Ch R = 1 ,57592   ,418,418,418
BEGIN DESCRIPTION:
NASH CREEK 95.0
END DESCRIPTION:
XS GIS Cut Line= 3
      2356725.02     13771525.04        2356325.       13770525.
        2355725.       13769925.
#Sta/Elev= 30
    3919  519.18  4011.9  517.39  4188.3  508.49  4371.4  506.23    4467  503.87
  4580.1  503.23  4604.3  501.93  4657.4  501.18  4795.5  499.63  4849.3  501.09
  4920.7  499.77  4932.8  500.35    4996  498.37  4999.6  498.37  5016.2  495.07
  5016.7  494.57  5032.5  495.07  5038.5  498.06  5052.6  498.87  5066.8  499.09
    5093  497.48  5137.5  496.21  5228.1  502.32  5349.6   506.9  5397.3  510.87
  5505.2  518.39  5575.9  525.24  5618.3  530.87  5738.5  538.21  5844.6  547.96
#Mann= 8 ,-1 , 0
    3919     .07       0  4657.4     .12       0    4996      .1       0
  5016.2     .05       0  5032.5      .1       0    5093     .12       0
  5228.1     .07       0  5397.3     .12       0
Bank Sta=5016.2,5032.5
XS Rating Curve= 0 ,0
Exp/Cntr=0.3,0.1

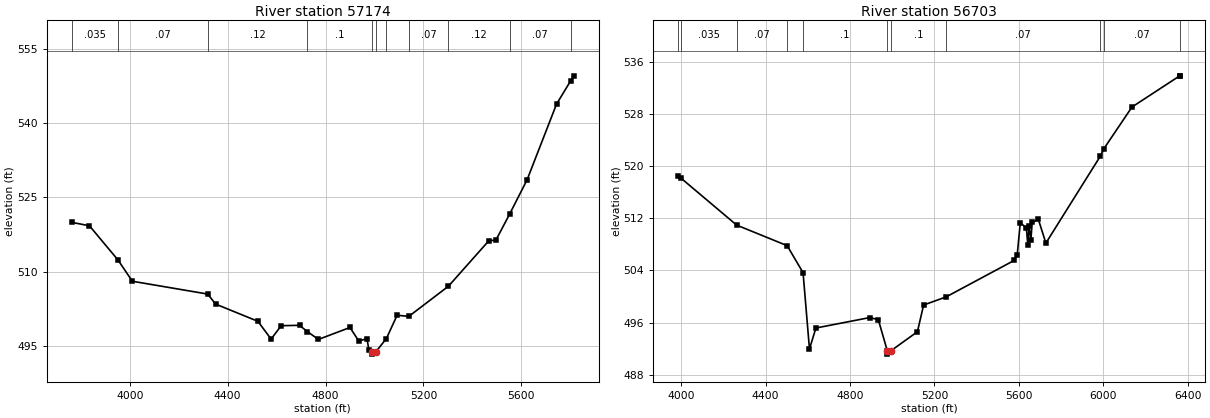
Type RM Length L Ch R = 1 ,57174   ,471,471,471
BEGIN DESCRIPTION:
NASH CREEK 94.0
END DESCRIPTION:
XS GIS Cut Line= 3
        2356825.       13771475.        2356525.       13770275.
      2355974.98     13769674.98
#Sta/Elev= 30
  3763.4  519.97  3835.6  519.27  3952.4  512.35  4010.8  508.07  4318.8  505.48
  4350.9  503.46  4523.6  499.98  4577.7  496.39  4618.9  499.09  4693.7  499.17
  4725.1  497.92    4771  496.32  4899.8  498.73  4935.9  495.99  4969.4  496.48
  4977.1  494.17  4989.6  493.85  4990.1  493.35    5006  493.85  5048.6   496.5
  5092.5  501.21  5140.1  500.97  5302.1  507.07  5467.4  516.27  5495.8  516.36
  5551.7  521.61  5623.4  528.57  5743.7  543.86  5801.6  548.57  5814.3  549.56
#Mann= 11 ,-1 , 0
  3763.4    .035       0  3952.4     .07       0  4318.8     .12       0
  4725.1      .1       0  4989.6     .05       0    5006      .1       0
  5048.6     .12       0  5140.1     .07       0  5302.1     .12       0
  5551.7     .07       0  5801.6     .12       0
Bank Sta=4989.6,5006
XS Rating Curve= 0 ,0
Exp/Cntr=0.3,0.1

Type RM Length L Ch R = 1 ,56703   ,472,472,472
BEGIN DESCRIPTION:
NASH CREEK 93.0
END DESCRIPTION:
XS GIS Cut Line= 3
      2357124.99     13771374.95        2356925.       13770375.
        2356125.       13769275.
#Sta/Elev= 30
  3985.6  518.47    3998  518.15  4262.5  510.94  4501.8  507.79  4577.3  503.65
  4607.6  491.96  4638.2  495.17  4893.2  496.77    4934  496.45  4976.7  491.67
  4977.2  491.17  4993.2  491.67  5119.3   494.6  5148.7  498.69  5255.5  499.94
  5577.6  505.52  5592.3  506.32    5607  511.33    5636  510.47  5642.5  507.92
  5648.7   510.8  5657.2  508.67  5663.4  511.36  5692.8   511.8  5728.3  508.18
  5986.4   521.5  6001.9  522.58  6136.4  529.03  6362.8  533.81  6365.5  533.81
#Mann= 11 ,-1 , 0
  3985.6     .07       0    3998    .035       0  4262.5     .07       0
  4501.8     .12       0  4577.3      .1       0  4976.7     .05       0
  4993.2      .1       0  5255.5     .07       0  5986.4     .12       0
  6001.9     .07       0  6362.8     .12       0
Bank Sta=4976.7,4993.2
XS Rating Curve= 0 ,0
Exp/Cntr=0.3,0.1