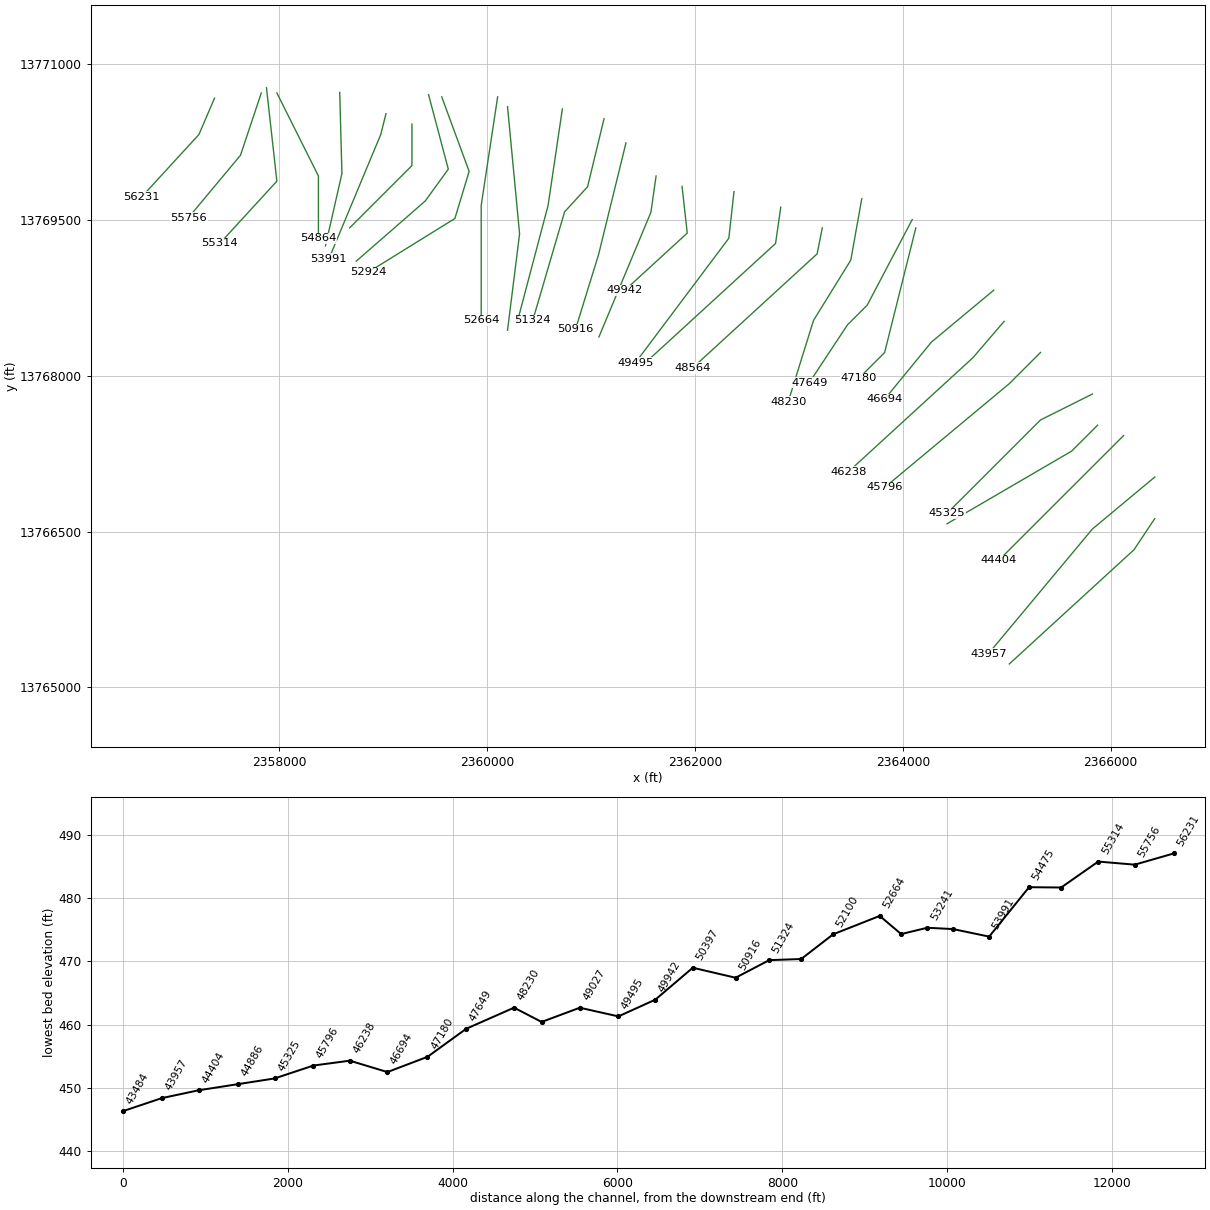
HEC-RAS study NASH CREEK.prj: NASH CREEK Base Level Engineering

--- NASH CREEK.g01 (geometry) --- (continued)

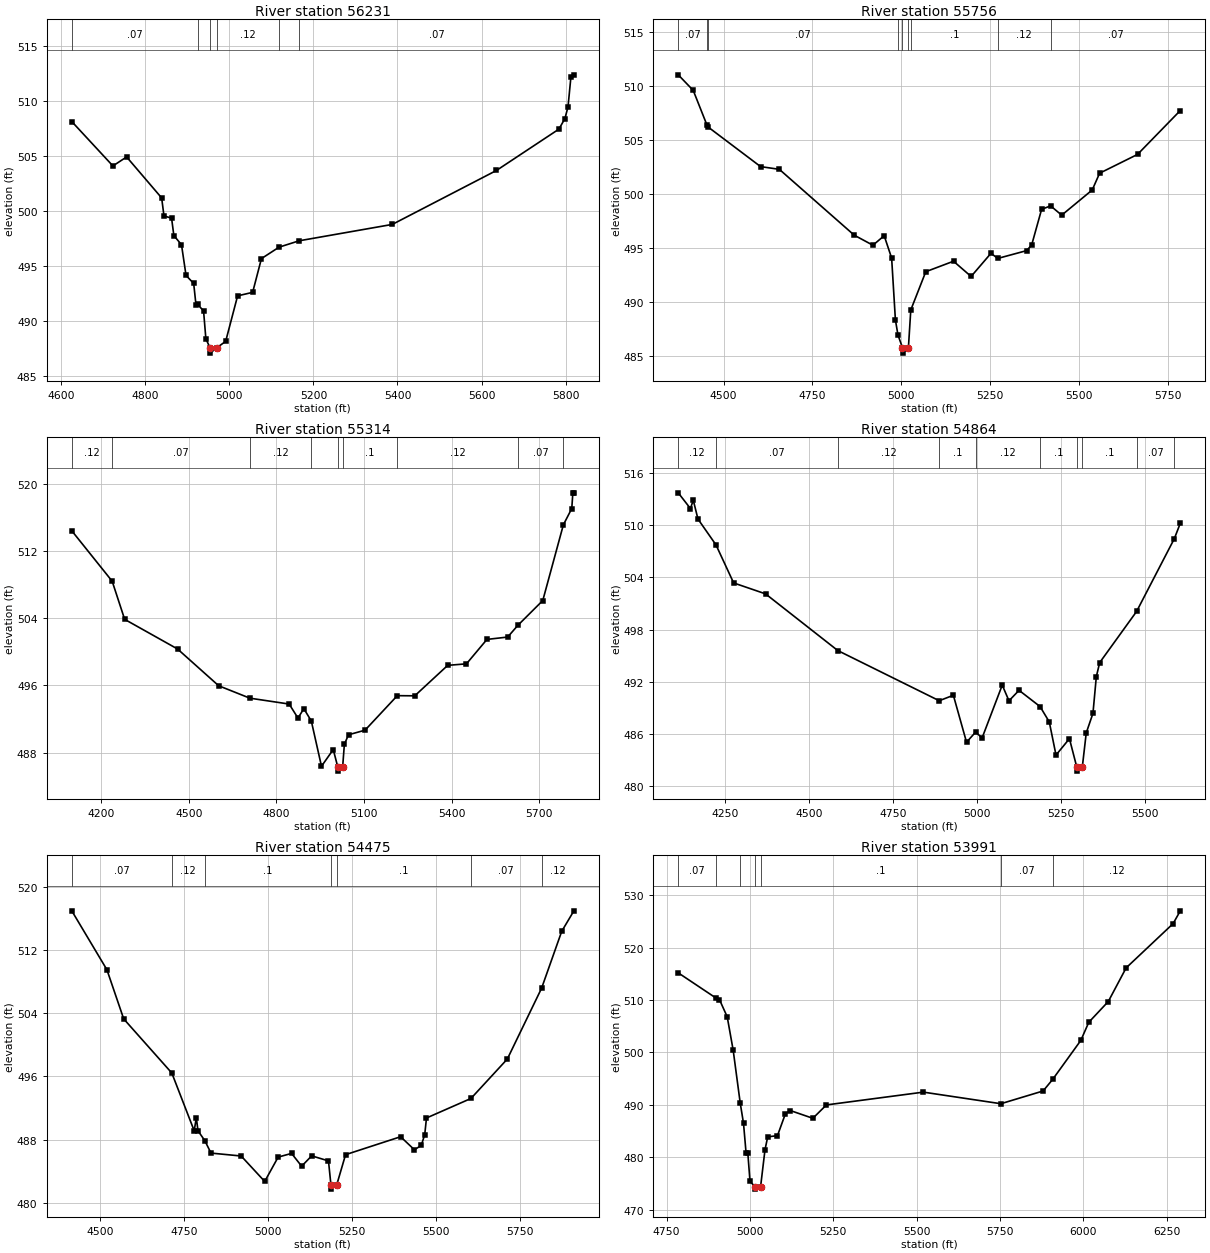
Type RM Length L Ch R = 1 ,56231   ,475,475,475
BEGIN DESCRIPTION:
NASH CREEK 92.0
END DESCRIPTION:
XS GIS Cut Line= 3
      2357374.98     13770674.96        2357225.       13770325.
      2356674.99     13769724.99
#Sta/Elev= 30
    4625  508.15  4722.9  504.11  4755.5  504.93  4838.9   501.2  4844.4  499.56
  4862.5  499.36  4867.9  497.78  4886.1  496.94  4896.9  494.15  4915.1  493.42
  4920.5  491.49  4924.2  491.51  4938.6  490.93  4944.1  488.38  4953.9  487.58
  4954.4  487.08  4970.5  487.58  4991.2  488.15  5019.6  492.29  5055.4  492.61
  5076.3  495.68  5118.2  496.72    5166   497.3  5387.7  498.79  5635.6   503.7
  5784.2  507.46  5798.4  508.42  5805.8  509.48  5812.6  512.16  5819.7   512.4
#Mann= 6 ,-1 , 0
    4625     .07       0  4924.2     .12       0  4953.9     .05       0
  4970.5     .12       0  5118.2      .1       0    5166     .07       0
Bank Sta=4953.9,4970.5
XS Rating Curve= 0 ,0
Exp/Cntr=0.3,0.1

Type RM Length L Ch R = 1 ,55756   ,442,442,442
BEGIN DESCRIPTION:
NASH CREEK 91.0
END DESCRIPTION:
XS GIS Cut Line= 3
        2357825.     13770725.01        2357625.       13770125.
      2357124.99     13769524.99
#Sta/Elev= 30
  4372.1  511.04  4414.3   509.6  4452.5  506.43  4455.1  506.24    4604  502.55
  4656.7   502.3  4867.5  496.21  4920.2  495.28  4951.9  496.16  4972.9  494.09
  4983.5  488.37  4990.7  486.98  5003.4   485.8  5003.9   485.3  5020.1   485.8
  5026.8  489.29    5069  492.83  5147.1   493.8  5196.6  492.39  5252.5  494.53
  5271.9  494.06  5352.8  494.78  5367.1   495.3  5395.1   498.6  5420.5  498.92
  5451.7  498.06  5537.6  500.39  5558.4  501.94  5665.2  503.68  5785.6  507.74
#Mann= 9 ,-1 , 0
  4372.1     .07       0  4452.5     .12       0  4455.1     .07       0
  4990.7     .12       0  5003.4     .05       0  5020.1     .12       0
  5026.8      .1       0  5271.9     .12       0  5420.5     .07       0
Bank Sta=5003.4,5020.1
XS Rating Curve= 0 ,0
Exp/Cntr=0.3,0.1

Type RM Length L Ch R = 1 ,55314   ,450,450,450
BEGIN DESCRIPTION:
NASH CREEK 90.0
END DESCRIPTION:
XS GIS Cut Line= 3
        2357875.     13770774.99        2357975.       13769875.
      2357424.98     13769274.98
#Sta/Elev= 30
  4099.3  514.42  4237.7  508.41  4280.4  503.87  4461.5  500.34  4602.4  495.96
  4709.2  494.48  4843.8  493.78    4874  492.11  4894.1  493.23  4919.7  491.76
  4954.5  486.37  4994.8  488.36  5010.3  486.29  5010.8  485.79    5027  486.29
  5032.9  488.99  5047.1  490.12  5103.8  490.67  5214.2  494.78    5274  494.76
  5386.8  498.39    5451  498.57  5521.2  501.48  5592.2  501.76  5626.9  503.15
  5712.4  506.11  5782.9  515.13  5811.7  517.07  5815.4  518.94  5818.8  518.94
#Mann= 9 ,-1 , 0
  4099.3     .12       0  4237.7     .07       0  4709.2     .12       0
  4919.7      .1       0  5010.3     .05       0    5027      .1       0
  5214.2     .12       0  5626.9     .07       0  5782.9     .12       0
Bank Sta=5010.3,5027
XS Rating Curve= 0 ,0
Exp/Cntr=0.3,0.1

Type RM Length L Ch R = 1 ,54864   ,389,389,389
BEGIN DESCRIPTION:
NASH CREEK 89.0
END DESCRIPTION:
XS GIS Cut Line= 3
      2357975.01     13770724.98        2358375.       13769925.
        2358375.     13769325.01
#Sta/Elev= 30
  4110.8  513.75  4147.1  511.94  4155.5  512.91  4169.5  510.73  4223.2  507.75
  4275.7  503.37  4370.7  502.11  4585.7  495.58  4887.6   489.8  4929.7  490.43
  4968.9  485.02    4996  486.19  5015.2  485.51  5075.2   491.6  5095.2  489.79
  5125.2     491  5187.7  489.13  5215.2  487.36  5235.2  483.54  5275.2  485.43
  5296.8  482.19  5297.3  481.69  5313.6  482.19  5325.2  486.09  5345.2  488.35
  5355.2  492.57  5365.2  494.19    5475  500.08  5587.5  508.48  5605.2  510.25
#Mann= 10 ,-1 , 0
  4110.8     .12       0  4223.2     .07       0  4585.7     .12       0
  4887.6      .1       0    4996     .12       0  5187.7      .1       0
  5296.8     .05       0  5313.6      .1       0    5475     .07       0
  5587.5     .12       0
Bank Sta=5296.8,5313.6
XS Rating Curve= 0 ,0
Exp/Cntr=0.3,0.1

Type RM Length L Ch R = 1 ,54475   ,484,484,484
BEGIN DESCRIPTION:
B19769
END DESCRIPTION:
XS GIS Cut Line= 3
      2358579.94     13770729.65      2358601.05     13769948.44
       2358442.7     13769251.71
#Sta/Elev= 30
  4415.3  516.95    4520   509.5    4570  503.28  4713.4  496.43  4780.1  489.12
  4786.4  490.78  4791.4  489.12  4811.8  487.87  4830.1   486.3  4920.1  485.93
  4990.2  482.71  5030.2  485.79  5070.2  486.26  5100.2  484.64  5130.2  485.95
  5180.2  485.31  5187.6  482.24  5188.1  481.74  5204.5  482.24  5231.1   486.1
  5395.2  488.37  5436.2  486.72  5456.7  487.27    5467  488.64  5472.2  490.74
  5604.7  493.21  5713.1   498.2  5815.3  507.17  5875.2  514.36  5911.3  516.94
#Mann= 7 ,-1 , 0
  4415.3     .07       0  4713.4     .12       0  4811.8      .1       0
  5187.6     .05       0  5204.5      .1       0  5604.7     .07       0
  5815.3     .12       0
Bank Sta=5187.6,5204.5
XS Rating Curve= 0 ,0
Exp/Cntr=0.3,0.1

Type RM Length L Ch R = 1 ,53991   ,438,438,438
BEGIN DESCRIPTION:
NASH CREEK 88.0
END DESCRIPTION:
XS GIS Cut Line= 3
        2359025.     13770524.98        2358975.       13770325.
      2358475.01     13769125.04
#Sta/Elev= 30
    4785  515.18  4899.1  510.34  4908.7  510.07  4931.9   506.8  4949.9  500.39
  4970.8  490.41  4980.8  486.48  4988.6  480.75  4993.8  480.75  5000.3  475.39
  5015.1  474.43  5015.6  473.93  5032.1  474.43  5045.3  481.46  5053.4   483.9
  5082.7  484.13  5106.5  488.31  5121.1  488.92  5188.8  487.44  5229.5  489.99
  5520.3  492.43  5752.8  490.22  5879.5  492.65    5908  494.84  5992.7   502.3
  6016.5  505.75    6075  509.71  6128.6  516.13  6269.5  524.57  6291.1  527.01
#Mann= 7 ,-1 , 0
    4785     .07       0  4899.1     .12       0  4970.8      .1       0
  5015.1     .05       0  5032.1      .1       0  5752.8     .07       0
    5908     .12       0
Bank Sta=5015.1,5032.1
XS Rating Curve= 0 ,0
Exp/Cntr=0.3,0.1

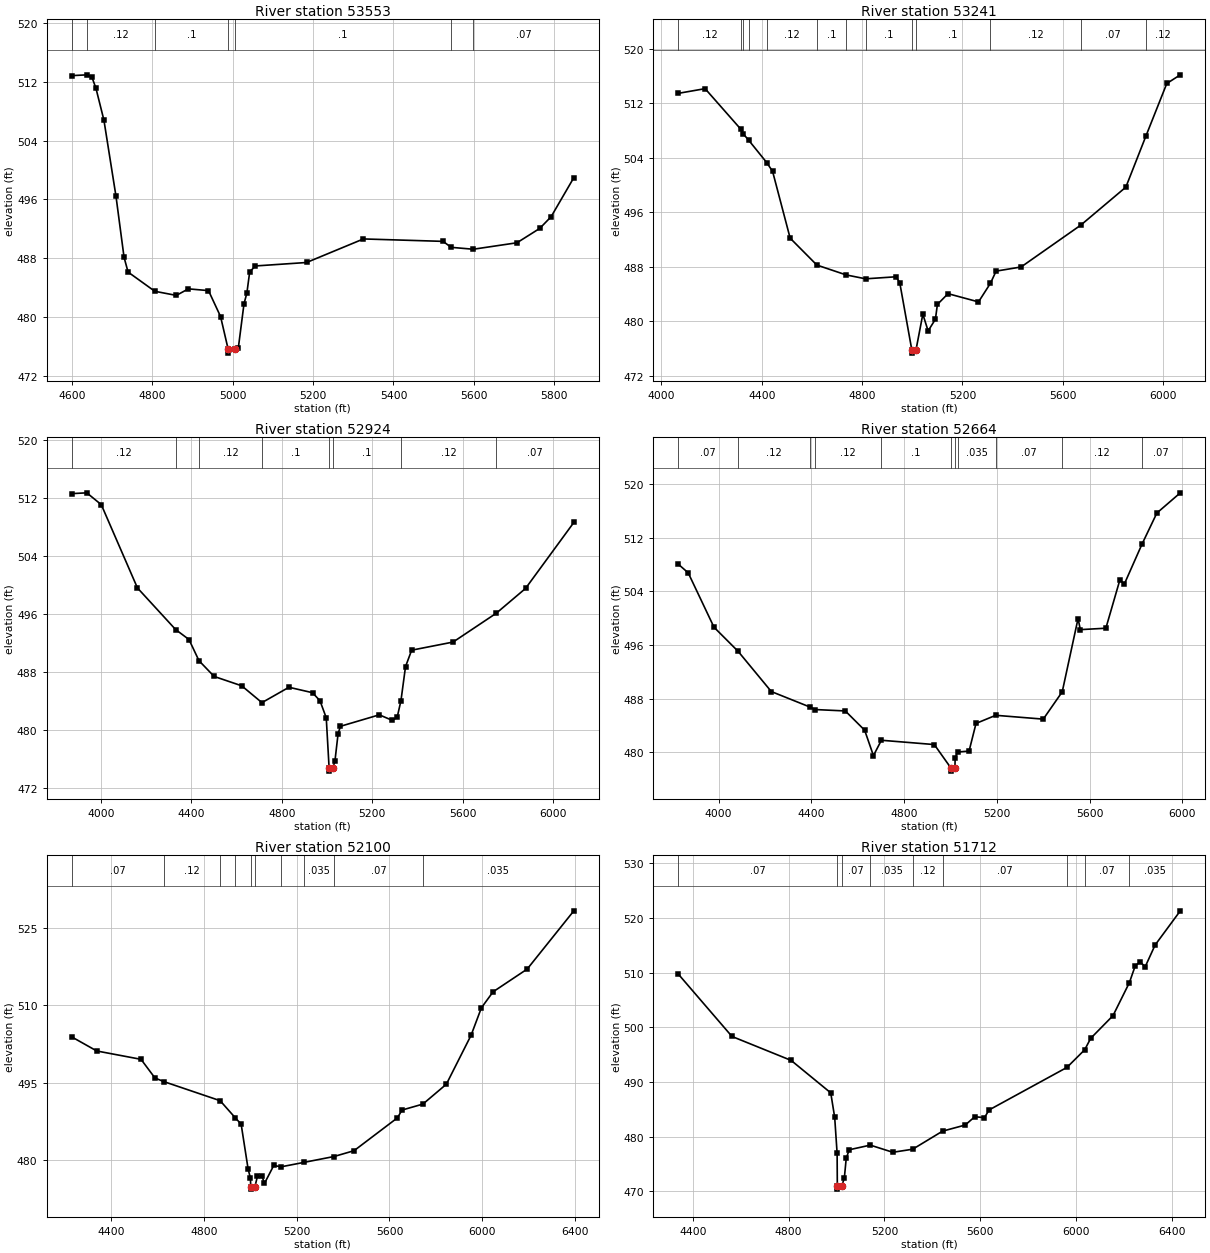
Type RM Length L Ch R = 1 ,53553   ,312,312,312
BEGIN DESCRIPTION:
NASH CREEK 87.0
END DESCRIPTION:
XS GIS Cut Line= 3
        2359275.     13770425.01        2359275.       13770025.
      2358675.03     13769425.03
#Sta/Elev= 30
    4600  512.81  4638.6  512.92    4650  512.61    4660  511.12    4680  506.75
    4710  496.41    4730  488.14    4740  486.13  4806.5  483.52    4860  482.96
    4890  483.85    4940  483.61    4970  480.09    4989  475.62  4989.5  475.12
    5006  475.62  5014.2  475.83  5028.3  481.83  5035.4  483.27  5042.4  486.15
  5056.6  486.96  5183.9  487.43  5325.3  490.63  5523.3   490.3  5543.4  489.49
  5598.4  489.23  5707.1  490.11  5763.7  492.06    5792  493.65  5848.5  498.96
#Mann= 7 ,-1 , 0
    4600     .07       0  4638.6     .12       0  4806.5      .1       0
    4989     .05       0    5006      .1       0  5543.4     .12       0
  5598.4     .07       0
Bank Sta=4989,5006
XS Rating Curve= 0 ,0
Exp/Cntr=0.3,0.1

Type RM Length L Ch R = 1 ,53241   ,317,317,317
BEGIN DESCRIPTION:
B19768
END DESCRIPTION:
XS GIS Cut Line= 4
        2359435.     13770708.51      2359625.02     13769990.67
      2359403.34     13769684.53      2358739.17      13769104.7
#Sta/Elev= 30
  4066.9  513.47    4174  514.16  4316.8  508.19  4325.7  507.54  4347.4  506.61
  4420.1  503.29  4443.1  502.02  4513.2  492.21  4619.7  488.26  4736.8  486.81
  4814.4  486.24  4935.6  486.54  4950.3  485.67  4998.2  475.83  4998.7  475.33
  5015.2  475.83  5042.3  481.05  5063.4  478.59  5092.5  480.31  5100.4  482.48
  5142.8  484.06  5264.3  482.85    5312  485.59  5334.5  487.37  5434.2  487.98
  5672.1  494.12  5851.9   499.7  5931.5  507.16  6015.2  514.92  6069.1  516.19
#Mann= 13 ,-1 , 0
  4066.9     .12       0  4316.8     .07       0  4325.7     .12       0
  4347.4     .07       0  4420.1     .12       0  4619.7      .1       0
  4736.8     .12       0  4814.4      .1       0  4998.2     .05       0
  5015.2      .1       0    5312     .12       0  5672.1     .07       0
  5931.5     .12       0
Bank Sta=4998.2,5015.2
XS Rating Curve= 0 ,0
Exp/Cntr=0.3,0.1

Type RM Length L Ch R = 1 ,52924   ,260,260,260
BEGIN DESCRIPTION:
B19767
END DESCRIPTION:
XS GIS Cut Line= 4
      2359561.69     13770687.36      2359825.59     13769969.55
      2359688.36     13769515.63      2358855.72     13768999.18
#Sta/Elev= 30
  3872.1  512.58  3938.5  512.69  4002.5  511.06  4162.3  499.58  4330.9  493.85
  4390.1  492.47  4434.3  489.55  4501.3  487.38  4623.2  486.09  4712.5  483.77
  4831.9  485.89    4936  485.14    4969  484.03  4996.7  481.68  5009.2  474.83
  5009.7  474.33  5026.3  474.83  5034.9  475.66  5049.1  479.51  5059.5  480.51
  5231.2  482.09  5289.1  481.32  5310.4  481.79  5326.9  484.05    5347  488.73
  5374.1     491  5557.2  492.12  5747.9  496.09  5877.4  499.51  6090.9  508.61
#Mann= 8 ,-1 , 0
  3872.1     .12       0  4330.9     .07       0  4434.3     .12       0
  4712.5      .1       0  5009.2     .05       0  5026.3      .1       0
  5326.9     .12       0  5747.9     .07       0
Bank Sta=5009.2,5026.3
XS Rating Curve= 0 ,0
Exp/Cntr=0.3,0.1

Type RM Length L Ch R = 1 ,52664   ,564,564,564
BEGIN DESCRIPTION:
B19766
END DESCRIPTION:
XS GIS Cut Line= 3
      2360100.07     13770687.43      2359941.71     13769642.31
      2359941.71     13768533.86
#Sta/Elev= 30
  3825.6  508.05  3868.5  506.76  3979.8  498.65  4083.7  495.06  4227.1  489.06
  4393.9  486.75    4415  486.38  4546.2  486.17  4629.6   483.3  4667.5  479.51
  4701.8   481.8    4930  481.16    5001   477.7  5001.5   477.2    5019   477.7
    5020  479.22  5031.4  480.05    5080  480.19    5110  484.31    5195  485.52
    5400  484.95  5481.8  489.02    5550  499.93    5560  498.29    5670   498.5
    5730  505.65    5750  505.11  5825.6  511.01    5890  515.67  5991.1  518.68
#Mann= 11 ,-1 , 0
  3825.6     .07       0  4083.7     .12       0  4393.9     .07       0
    4415     .12       0  4701.8      .1       0    5001     .05       0
    5019      .1       0  5031.4    .035       0    5195     .07       0
  5481.8     .12       0  5825.6     .07       0
Bank Sta=5001,5019
XS Rating Curve= 0 ,0
Exp/Cntr=0.3,0.1

Type RM Length L Ch R = 1 ,52100   ,388,388,388
BEGIN DESCRIPTION:
B19765
END DESCRIPTION:
XS GIS Cut Line= 3
      2360195.07     13770592.37      2360311.19     13769367.84
      2360195.13     13768439.39
#Sta/Elev= 30
  4229.6  503.85  4337.5  501.12  4528.3   499.5  4588.6  495.87  4627.7  495.16
  4869.5  491.47  4935.2  488.13  4960.2  486.91  4990.4  478.16  5000.4  476.42
  5001.3   474.8  5001.8   474.3  5019.7   474.8  5030.5  476.79  5050.6  476.76
  5060.7   475.4  5100.9   478.9  5132.4  478.63    5231  479.49  5360.6  480.63
  5447.2  481.76  5634.6  488.15    5654  489.65  5744.2  490.81  5845.4  494.67
  5952.1  504.18  5996.6  509.51    6047  512.61    6194  517.02  6395.3  528.33
#Mann= 10 ,-1 , 0
  4229.6     .07       0  4627.7     .12       0  4869.5     .07       0
  4935.2     .12       0  5001.3     .05       0  5019.7     .12       0
  5132.4      .1       0    5231    .035       0  5360.6     .07       0
  5744.2    .035       0
Bank Sta=5001.3,5019.7
XS Rating Curve= 0 ,0
Exp/Cntr=0.3,0.1

Type RM Length L Ch R = 1 ,51712   ,388,388,388
BEGIN DESCRIPTION:
B19764
END DESCRIPTION:
XS GIS Cut Line= 3
      2360722.88     13770571.24      2360585.65     13769642.31
      2360290.07     13768523.31
#Sta/Elev= 30
  4338.9  509.74  4563.2  498.32  4810.2  493.94  4975.7     488  4992.2  483.51
  5002.3  476.93  5003.2  470.89  5003.7  470.39  5021.6  470.89  5032.6  472.49
  5040.3  476.01  5052.8  477.59  5140.8  478.44  5234.8  477.13  5317.8  477.69
  5442.7     481  5536.9  482.11  5577.2  483.63  5617.5  483.47  5637.1  484.88
  5962.1  492.66    6036  495.88  6061.2  497.98  6154.3  502.13  6222.6  508.16
  6247.4  511.28  6268.1  511.94  6288.7  511.07  6330.1  515.05  6435.3   521.3
#Mann= 9 ,-1 , 0
  4338.9     .07       0  5003.2     .05       0  5021.6     .07       0
  5140.8    .035       0  5317.8     .12       0  5442.7     .07       0
  5962.1    .035       0    6036     .07       0  6222.6    .035       0
Bank Sta=5003.2,5021.6
XS Rating Curve= 0 ,0
Exp/Cntr=0.3,0.1

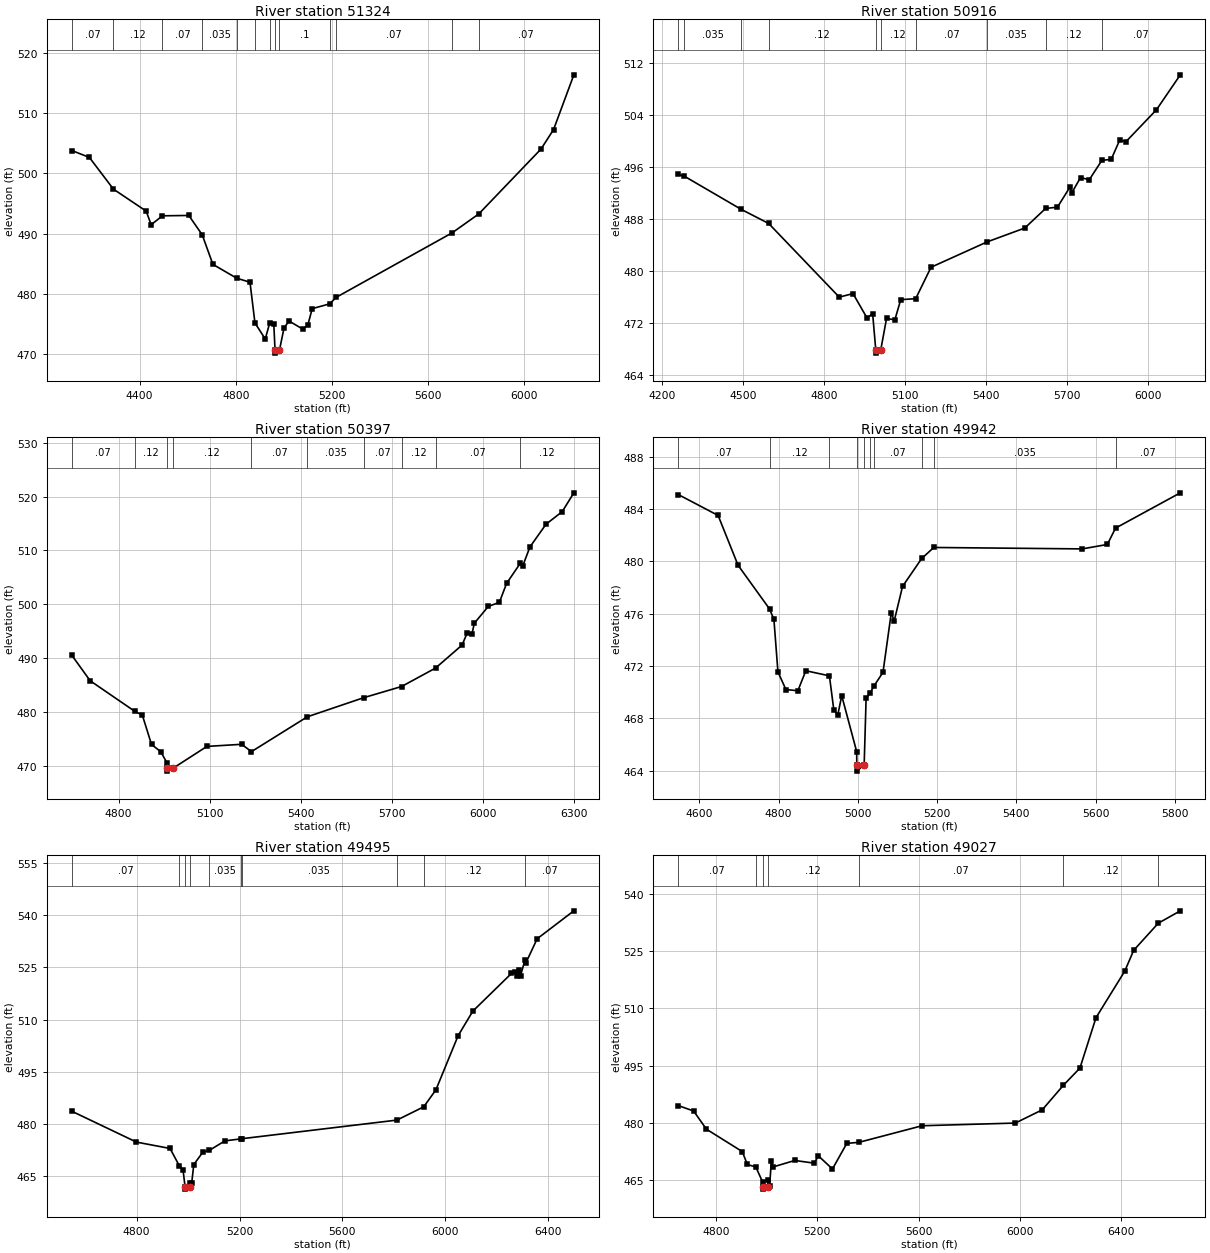
Type RM Length L Ch R = 1 ,51324   ,408,408,408
BEGIN DESCRIPTION:
B19763
END DESCRIPTION:
XS GIS Cut Line= 4
      2361124.04     13770476.31      2360965.68     13769821.76
        2360744.     13769578.97      2360437.86     13768533.88
#Sta/Elev= 30
  4117.2  503.81  4190.6  502.66  4290.8   497.4  4427.1  493.76  4447.8   491.5
  4494.8  492.98  4604.7  493.04  4660.5  489.83    4705  484.93  4804.3  482.63
  4859.5  481.97  4880.1  475.22  4923.1  472.55  4941.2  475.16  4958.8  474.96
  4963.8  470.71  4964.3  470.21  4982.3  470.71  5001.4  474.41  5022.4  475.53
  5079.1   474.2  5100.1  474.83  5118.7  477.59  5191.7  478.38    5218  479.45
  5701.2  490.15  5812.4  493.29  6071.8  504.06  6123.9  507.28  6208.4  516.36
#Mann= 13 ,-1 , 0
  4117.2     .07       0  4290.8     .12       0  4494.8     .07       0
  4660.5    .035       0  4804.3     .12       0  4880.1    .035       0
  4941.2      .1       0  4963.8     .05       0  4982.3      .1       0
  5191.7     .12       0    5218     .07       0  5701.2    .035       0
  5812.4     .07       0
Bank Sta=4963.8,4982.3
XS Rating Curve= 0 ,0
Exp/Cntr=0.3,0.1

Type RM Length L Ch R = 1 ,50916   ,519,519,519
BEGIN DESCRIPTION:
B19762
END DESCRIPTION:
XS GIS Cut Line= 3
      2361335.15     13770243.99      2361071.24     13769167.27
      2360849.88     13768450.46
#Sta/Elev= 30
  4259.8  494.89  4282.6  494.62  4492.5  489.54  4594.6  487.36  4855.9  476.04
  4906.9  476.58  4958.9  472.82  4979.5  473.51  4991.1  467.93  4991.6  467.43
  5009.6  467.93    5031  472.76  5061.8  472.55  5083.6  475.65  5138.9   475.8
  5195.7  480.63  5403.5  484.53  5542.8  486.66  5619.9  489.67  5663.8  489.87
  5711.2  493.03  5716.4  492.04  5749.1  494.41  5781.7  494.09  5828.3  497.07
  5862.7  497.21  5894.1  500.17  5917.5  499.94  6030.1  504.83  6118.6  510.21
#Mann= 10 ,-1 , 0
  4259.8     .07       0  4282.6    .035       0  4492.5     .07       0
  4594.6     .12       0  4991.1     .05       0  5009.6     .12       0
  5138.9     .07       0  5403.5    .035       0  5619.9     .12       0
  5828.3     .07       0
Bank Sta=4991.1,5009.6
XS Rating Curve= 0 ,0
Exp/Cntr=0.3,0.1

Type RM Length L Ch R = 1 ,50397   ,455,455,455
BEGIN DESCRIPTION:
NASH CREEK 82.0
END DESCRIPTION:
XS GIS Cut Line= 3
        2361625.     13769924.98        2361575.       13769575.
      2361075.01     13768375.03
#Sta/Elev= 30
  4646.1  490.54  4706.7  485.79  4853.2  480.13  4878.4  479.43  4908.7  473.96
    4939  472.63  4959.2  470.59    4960  469.51  4960.5  469.01  4978.6  469.51
  5091.2   473.6  5205.5  473.99  5237.9  472.63  5421.9   479.1  5607.1  482.64
  5732.2  484.72  5844.2  488.15  5931.3  492.41  5948.1  494.62  5963.8  494.41
  5971.9  496.48    6018   499.6  6054.3  500.35  6078.1  503.87  6123.6  507.64
  6131.2   507.1    6155  510.64  6208.1  514.87  6261.2  517.19  6299.6  520.69
#Mann= 10 ,-1 , 0
  4646.1     .07       0  4853.2     .12       0    4960     .05       0
  4978.6     .12       0  5237.9     .07       0  5421.9    .035       0
  5607.1     .07       0  5732.2     .12       0  5844.2     .07       0
  6123.6     .12       0
Bank Sta=4960,4978.6
XS Rating Curve= 0 ,0
Exp/Cntr=0.3,0.1

Type RM Length L Ch R = 1 ,49942   ,447,447,447
BEGIN DESCRIPTION:
NASH CREEK 81.0
END DESCRIPTION:
XS GIS Cut Line= 3
        2361875.     13769824.97        2361925.       13769375.
      2361324.99     13768824.99
#Sta/Elev= 30
  4546.8  485.12  4647.4  483.52  4697.7  479.71  4777.3  476.36  4788.2  475.56
  4798.3  471.56  4818.4   470.2  4848.6  470.11  4868.7  471.64  4928.2  471.25
  4939.2  468.67  4949.2  468.24  4959.3  469.73    4997  465.45  4997.3  464.46
  4997.8  463.96  5015.9  464.46  5020.8  469.52    5031  469.96  5041.2   470.5
  5063.4  471.52  5084.3  476.08  5091.7  475.45  5112.7  478.09  5161.1  480.23
  5191.6  481.07  5565.9  480.96  5629.4   481.3  5650.1  482.55  5813.5  485.25
#Mann= 10 ,-1 , 0
  4546.8     .07       0  4777.3     .12       0  4928.2      .1       0
  4997.3     .05       0  5015.9      .1       0    5031     .12       0
  5041.2     .07       0  5161.1     .12       0  5191.6    .035       0
  5650.1     .07       0
Bank Sta=4997.3,5015.9
XS Rating Curve= 0 ,0
Exp/Cntr=0.3,0.1

Type RM Length L Ch R = 1 ,49495   ,468,468,468
BEGIN DESCRIPTION:
NASH CREEK 80.0
END DESCRIPTION:
XS GIS Cut Line= 3
      2362374.99     13769774.95        2362325.       13769325.
      2361425.01     13768125.02
#Sta/Elev= 30
  4547.6   483.7  4799.1  474.83  4929.9     473  4965.6  468.06  4980.2  466.94
  4988.5  461.82    4989  461.32  5007.1  461.82  5007.6  462.99  5013.9     463
  5022.2  468.38  5057.6  471.96  5082.2  472.43    5143  475.18  5203.9  475.74
  5207.9  475.79  5812.3  481.15  5916.6  484.97  5963.9  489.85  6050.3  505.41
  6107.6  512.46  6257.6  523.27  6272.2  523.79  6278.4  522.48  6286.8  524.27
    6293  522.68  6309.9  527.02  6313.9  526.33  6357.6  533.23  6500.3  541.26
#Mann= 10 ,-1 , 0
  4547.6     .07       0  4965.6      .1       0  4988.5     .05       0
  5007.1      .1       0  5082.2    .035       0  5203.9     .07       0
  5207.9    .035       0  5812.3     .07       0  5916.6     .12       0
  6309.9     .07       0
Bank Sta=4988.5,5007.1
XS Rating Curve= 0 ,0
Exp/Cntr=0.3,0.1

Type RM Length L Ch R = 1 ,49027   ,463,463,463
BEGIN DESCRIPTION:
NASH CREEK 79.0
END DESCRIPTION:
XS GIS Cut Line= 3
      2362825.01     13769625.04        2362775.       13769275.
      2361574.98     13768174.98
#Sta/Elev= 30
  4651.6  484.56  4712.3  483.14  4762.8  478.38  4904.2  472.52  4924.4  469.14
  4957.9  468.48    4985   464.5  4985.7  463.19  4986.2  462.69  5004.4  463.19
  5005.2     465  5012.3  463.51  5019.1  470.13  5026.5  468.51  5111.6  470.19
  5189.3  469.48  5203.4  471.48  5260.2  467.96  5316.9  474.67  5364.3  474.93
  5614.1  479.28  5981.9  479.98  6088.3  483.45  6171.6  489.87  6236.9  494.37
  6300.4  507.57  6413.9  519.74    6449  525.19  6546.2  532.29  6633.1  535.53
#Mann= 7 ,-1 , 0
  4651.6     .07       0  4957.9     .12       0  4985.7     .05       0
  5004.4     .12       0  5364.3     .07       0  6171.6     .12       0
  6546.2     .07       0
Bank Sta=4985.7,5004.4
XS Rating Curve= 0 ,0
Exp/Cntr=0.3,0.1

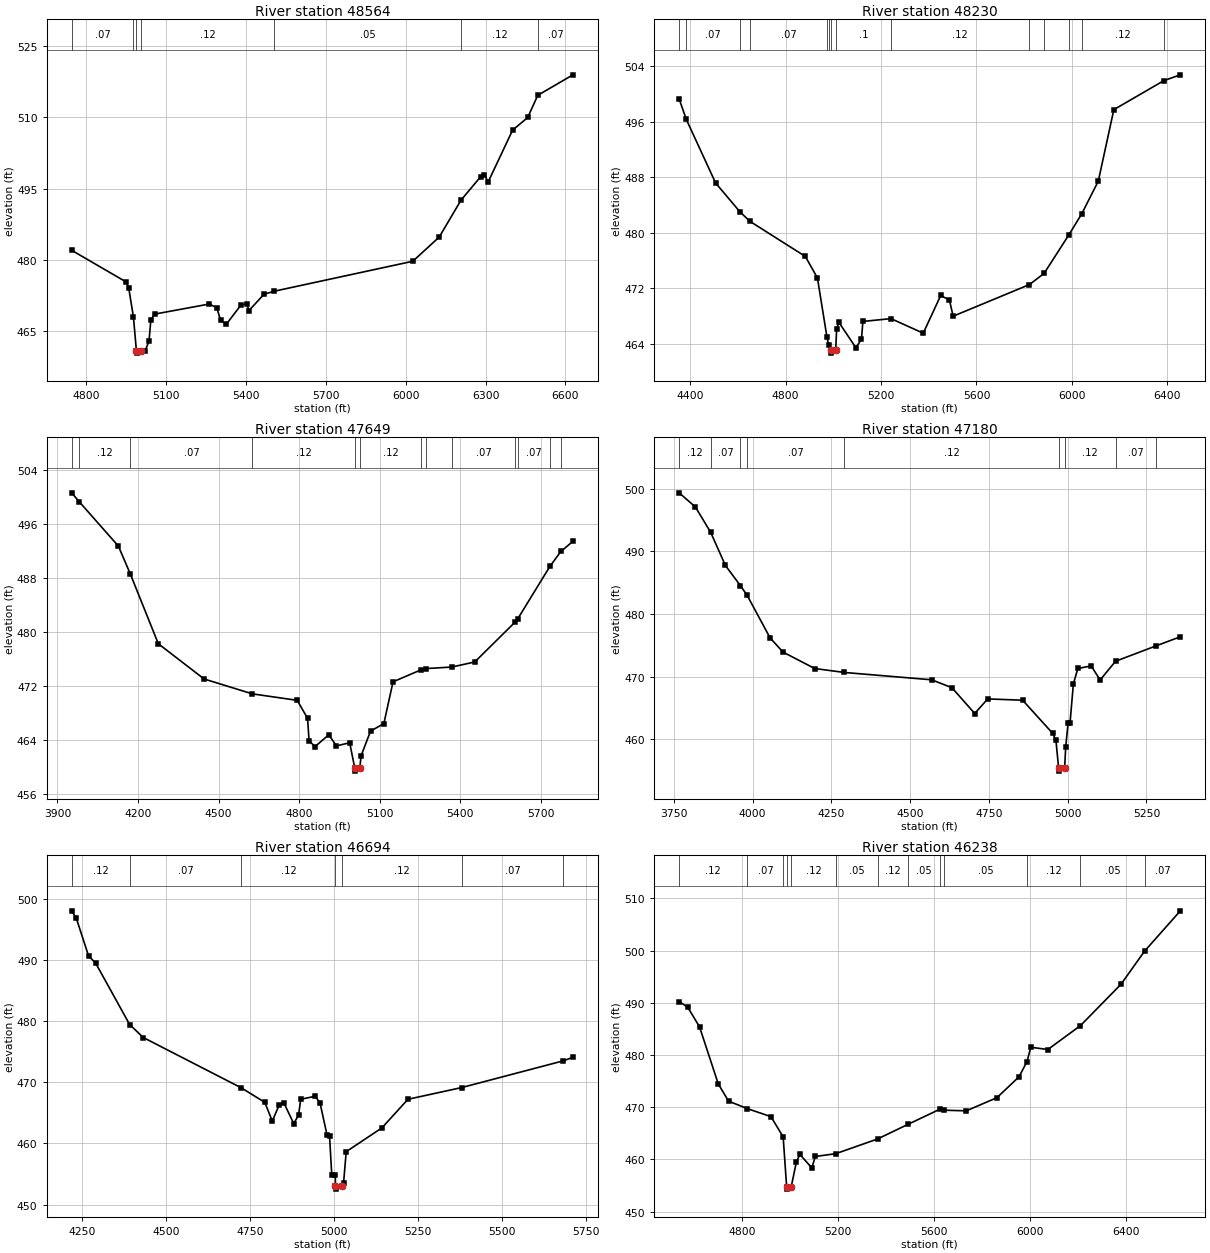
Type RM Length L Ch R = 1 ,48564   ,334,334,334
BEGIN DESCRIPTION:
NASH CREEK 78.0
END DESCRIPTION:
XS GIS Cut Line= 3
      2363225.01     13769425.03        2363175.       13769175.
      2361974.97     13768074.97
#Sta/Elev= 30
  4745.1  482.05  4949.1  475.41  4959.3  474.13    4977  467.98  4988.1  460.94
  4988.6  460.44  5006.9  460.94  5021.4  460.99  5035.5  462.99  5042.3  467.42
  5056.5  468.64  5261.8  470.76  5290.2  469.98  5304.4  467.31  5325.7   466.5
  5382.1  470.65  5403.7  470.77  5410.4  469.35  5467.2  472.81  5506.3  473.46
  6026.4  479.75  6125.7  484.84  6207.8  492.62  6281.1  497.51  6295.3  497.94
  6309.5  496.42  6401.4  507.32  6458.1  509.97  6495.8  514.63    6628  518.94
#Mann= 7 ,-1 , 0
  4745.1     .07       0    4977     .12       0  4988.1     .05       0
  5006.9     .12       0  5506.3     .05       0  6207.8     .12       0
  6495.8     .07       0
Bank Sta=4988.1,5006.9
XS Rating Curve= 0 ,0
Exp/Cntr=0.3,0.1

Type RM Length L Ch R = 1 ,48230   ,581,581,581
BEGIN DESCRIPTION:
B19761
END DESCRIPTION:
XS GIS Cut Line= 4
      2363604.77     13769705.63      2363499.21     13769114.49
       2363140.3     13768533.89       2362897.5     13767752.72
#Sta/Elev= 30
  4353.5  499.27  4383.5  496.32  4506.5  487.17  4608.2  483.03  4650.1  481.66
  4882.4  476.61  4933.2  473.52  4973.4  464.95  4980.9  463.83    4991   463.2
  4991.5   462.7  5009.9   463.2  5013.8   466.2  5023.3  467.12  5094.5  463.47
  5117.9  464.72  5123.8  467.26  5241.5  467.66  5376.7  465.57    5450  470.99
  5486.7  470.33    5502  468.01  5821.8  472.56  5883.3  474.16  5987.4  479.72
  6041.2  482.74  6110.6  487.44  6175.7  497.72  6385.2  501.89  6454.6  502.73
#Mann= 14 ,-1 , 0
  4353.5     .12       0  4383.5     .07       0  4608.2     .12       0
  4650.1     .07       0  4973.4     .12       0  4980.9      .1       0
    4991     .05       0  5009.9      .1       0  5241.5     .12       0
  5821.8     .05       0  5883.3     .12       0  5987.4     .07       0
  6041.2     .12       0  6385.2     .07       0
Bank Sta=4991,5009.9
XS Rating Curve= 0 ,0
Exp/Cntr=0.3,0.1

Type RM Length L Ch R = 1 ,47649   ,469,469,469
BEGIN DESCRIPTION:
B19760
END DESCRIPTION:
XS GIS Cut Line= 4
      2364090.35     13769505.03      2363657.56     13768681.67
      2363467.54     13768491.66      2363099.05     13767933.65
#Sta/Elev= 30
  3953.1  500.56  3980.4  499.27    4127  492.67  4171.8  488.51  4275.7  478.22
  4446.4     473  4625.9   470.8  4793.4  469.84  4831.9  467.17  4837.5  463.85
  4859.6  462.99    4911  464.74  4939.3  463.09  4988.8  463.56  5007.5  459.86
    5008  459.36  5026.6  459.86  5031.2  461.62  5066.6  465.29  5116.1  466.39
  5150.3  472.58    5256  474.38  5272.9  474.54  5369.3  474.77  5454.8  475.52
  5604.6   481.4  5614.6  481.88  5734.9  489.67  5775.7  491.88  5820.7  493.38
#Mann= 13 ,-1 , 0
  3953.1     .07       0  3980.4     .12       0  4171.8     .07       0
  4625.9     .12       0  5007.5     .05       0  5026.6     .12       0
    5256     .07       0  5272.9     .12       0  5369.3     .07       0
  5604.6     .05       0  5614.6     .07       0  5734.9     .05       0
  5775.7     .12       0
Bank Sta=5007.5,5026.6
XS Rating Curve= 0 ,0
Exp/Cntr=0.3,0.1

Type RM Length L Ch R = 1 ,47180   ,486,486,486
BEGIN DESCRIPTION:
NASH CREEK 76.0
END DESCRIPTION:
XS GIS Cut Line= 3
      2364124.99     13769424.97        2363825.       13768225.
      2363574.97     13767974.97
#Sta/Elev= 30
    3767  499.36  3818.5  497.11  3866.9  493.07  3913.9  487.76  3961.2  484.56
  3982.9  482.99  4055.6   476.2  4096.8  473.93  4197.3  471.31  4291.7  470.68
  4568.4  469.51  4632.8  468.24    4705  464.13  4746.2  466.46    4857  466.25
  4952.4  460.96  4962.7  459.83  4971.2  455.43  4971.7  454.93  4990.3  455.43
  4993.6  458.72  5001.3  462.63  5007.4  462.63    5018  468.85  5032.2  471.32
  5074.6  471.72  5102.9  469.48  5151.8  472.47    5280  474.92  5357.5  476.38
#Mann= 9 ,-1 , 0
    3767     .12       0  3866.9     .07       0  3961.2     .12       0
  3982.9     .07       0  4291.7     .12       0  4971.2     .05       0
  4990.3     .12       0  5151.8     .07       0    5280     .05       0
Bank Sta=4971.2,4990.3
XS Rating Curve= 0 ,0
Exp/Cntr=0.3,0.1

Type RM Length L Ch R = 1 ,46694   ,456,456,456
BEGIN DESCRIPTION:
NASH CREEK 75.0
END DESCRIPTION:
XS GIS Cut Line= 3
      2364875.02     13768825.02        2364275.       13768325.
      2363824.99     13767774.99
#Sta/Elev= 30
  4219.1  498.08  4232.8  496.86  4269.2   490.7  4290.1  489.54  4391.4  479.47
    4432  477.34  4724.2  469.09  4793.8  466.72    4816  463.66  4836.8  466.33
  4851.1  466.57  4879.7  463.26  4894.1   464.6  4900.6  467.23  4943.5  467.72
  4957.9  466.67  4978.7  461.44  4986.5  461.15    4993  454.84  5003.4  454.82
  5004.1  453.02  5004.6  452.52  5023.4  453.02  5028.2  453.57    5036  458.65
  5142.3  462.55  5219.8  467.23  5379.9  469.15  5681.9  473.52  5710.8   474.1
#Mann= 7 ,-1 , 0
  4219.1     .12       0  4391.4     .07       0  4724.2     .12       0
  5004.1     .05       0  5023.4     .12       0  5379.9     .07       0
  5681.9     .05       0
Bank Sta=5004.1,5023.4
XS Rating Curve= 0 ,0
Exp/Cntr=0.3,0.1

Type RM Length L Ch R = 1 ,46238   ,442,442,442
BEGIN DESCRIPTION:
NASH CREEK 74.0
END DESCRIPTION:
XS GIS Cut Line= 3
      2364974.98     13768524.97        2364675.       13768175.
      2363475.02     13767075.01
#Sta/Elev= 30
  4539.1  490.23  4574.7  489.16  4624.1  485.39  4702.1  474.47  4744.9  471.17
  4823.9  469.72  4921.6   468.2  4972.6  464.33    4987  454.82  4987.5  454.32
  5006.4  454.82  5028.1  459.59  5042.3  460.96  5092.2  458.38  5106.4  460.57
  5191.4   461.1  5365.9  463.92  5492.3  466.71  5626.2  469.63  5642.8  469.43
    5736  469.31  5863.6  471.83  5955.5  475.82  5988.5  478.71  6004.8  481.48
  6075.7  481.05  6211.7  485.63  6380.3  493.53  6478.8  499.88  6627.9   507.6
#Mann= 13 ,-1 , 0
  4539.1     .12       0  4823.9     .07       0  4972.6     .12       0
    4987     .05       0  5006.4     .12       0  5191.4     .05       0
  5365.9     .12       0  5492.3     .05       0  5626.2     .07       0
  5642.8     .05       0  5988.5     .12       0  6211.7     .05       0
  6478.8     .07       0
Bank Sta=4987,5006.4
XS Rating Curve= 0 ,0
Exp/Cntr=0.3,0.1

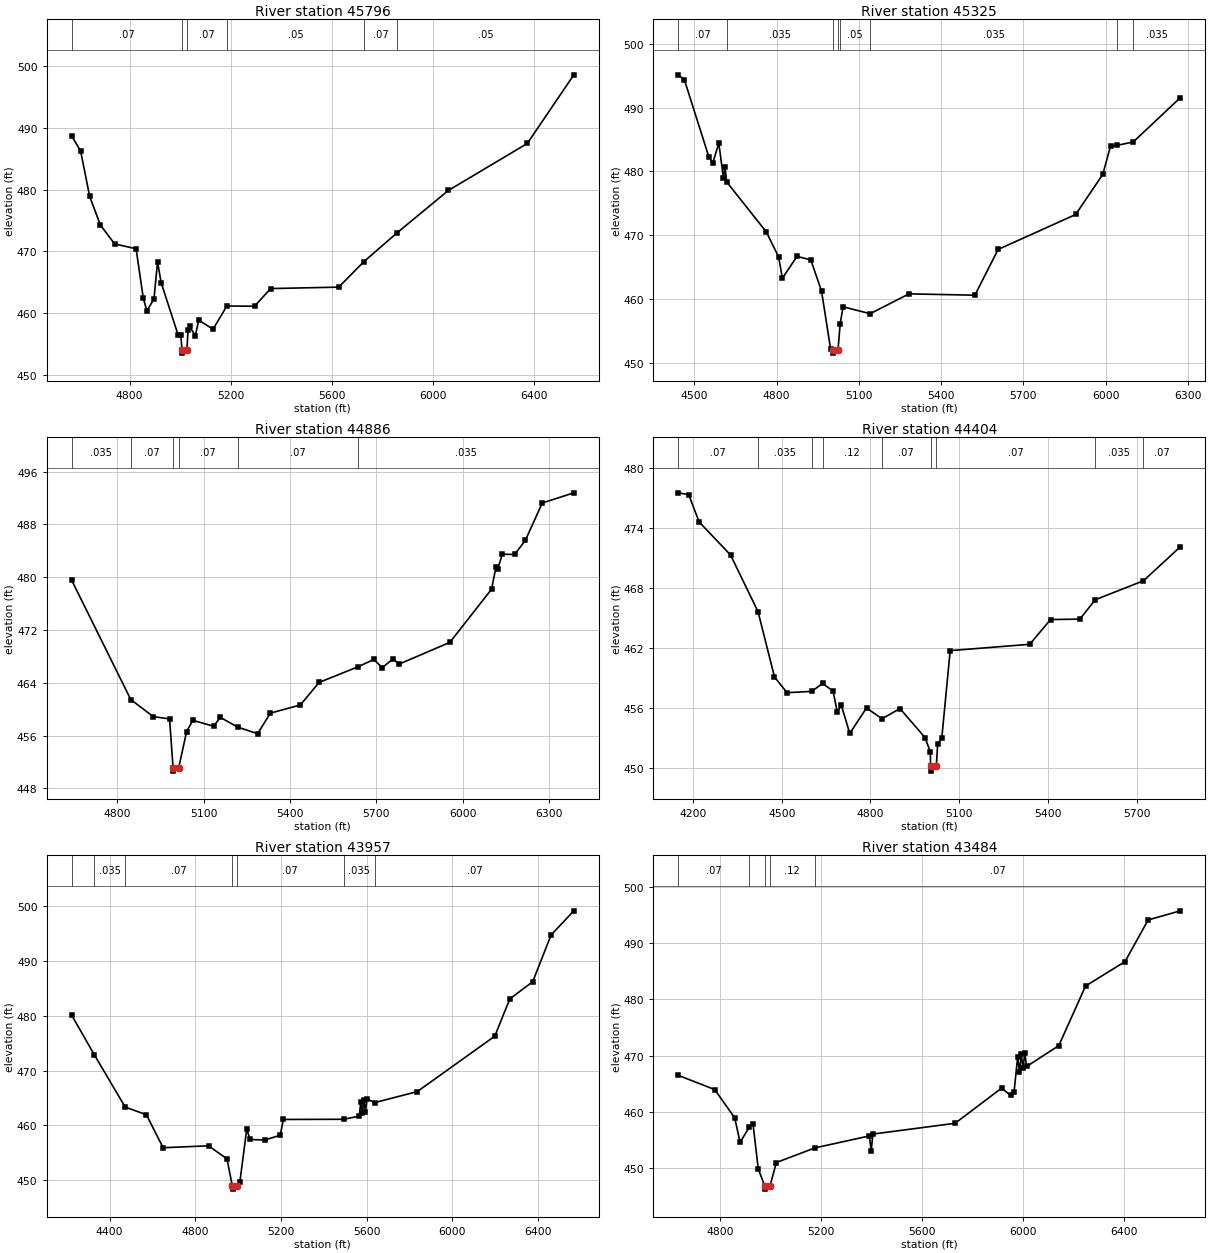
Type RM Length L Ch R = 1 ,45796   ,471,471,471
BEGIN DESCRIPTION:
NASH CREEK 73.0
END DESCRIPTION:
XS GIS Cut Line= 3
      2365324.98     13768224.98        2365025.       13767925.
      2363824.99     13766924.99
#Sta/Elev= 30
  4570.9   488.7  4606.2  486.22  4641.6  478.92    4684  474.29  4740.6  471.22
  4825.4  470.44  4853.7  462.48  4867.9  460.39  4896.1  462.31  4910.3  468.32
  4924.4  464.97  4991.6  456.49  5002.3  456.54  5006.9  454.05  5007.4  453.55
  5026.3  454.05  5030.9  457.25  5037.4  457.86  5059.6  456.36  5073.2  458.87
  5129.9  457.43  5184.5  461.18  5293.9  461.14  5357.7     464  5627.1  464.23
  5726.1  468.34  5858.7  473.05  6060.6  479.87    6373  487.48  6557.2  498.59
#Mann= 6 ,-1 , 0
  4570.9     .07       0  5006.9     .05       0  5026.3     .07       0
  5184.5     .05       0  5726.1     .07       0  5858.7     .05       0
Bank Sta=5006.9,5026.3
XS Rating Curve= 0 ,0
Exp/Cntr=0.3,0.1

Type RM Length L Ch R = 1 ,45325   ,439,439,439
BEGIN DESCRIPTION:
NASH CREEK 72.0
END DESCRIPTION:
XS GIS Cut Line= 3
        2365825.       13767825.        2365325.       13767575.
      2364425.01     13766675.01
#Sta/Elev= 30
    4441  495.13  4463.4  494.36  4552.8  482.25  4566.8   481.3  4589.1   484.4
  4605.9  478.96  4611.5  480.65  4617.9  478.33  4762.4  470.51  4807.2  466.59
  4821.1  463.25  4874.2  466.67  4924.6  466.13  4963.7  461.27  4997.2  452.08
  5004.5  452.01    5005  451.51  5023.9  452.01  5031.9  456.13  5042.4  458.77
  5141.2  457.69  5282.9   460.8  5523.3  460.59  5608.1  467.76    5891  473.24
    5990  479.53  6018.3  483.98  6041.2  484.07  6100.9   484.6  6272.8  491.55
#Mann= 8 ,-1 , 0
    4441     .07       0  4617.9    .035       0  5004.5    .035       0
  5023.9    .035       0  5031.9     .05       0  5141.2    .035       0
  6041.2     .07       0  6100.9    .035       0
Bank Sta=5004.5,5023.9
XS Rating Curve= 0 ,0
Exp/Cntr=0.3,0.1

Type RM Length L Ch R = 1 ,44886   ,482,482,482
BEGIN DESCRIPTION:
NASH CREEK 71.0
END DESCRIPTION:
XS GIS Cut Line= 3
      2365875.01     13767525.01        2365625.       13767275.
      2364425.01     13766575.01
#Sta/Elev= 30
  4642.6   479.5  4847.5  461.45  4925.5  458.88    4982  458.53  4994.3  451.12
  4994.8  450.62  5013.8  451.12  5041.2  456.62  5062.7  458.31  5135.1  457.42
  5158.2  458.76  5218.4  457.29  5287.7  456.29  5331.9   459.4  5436.1  460.64
    5501  464.05  5636.2  466.42  5690.8  467.53  5720.1   466.3  5757.4  467.59
  5778.9  466.83    5955  470.12  6099.7  478.17  6115.4  481.59  6121.2  481.21
  6136.9  483.48  6179.9  483.43  6217.1  485.58  6275.8  491.23  6385.4  492.77
#Mann= 6 ,-1 , 0
  4642.6    .035       0  4847.5     .07       0  4994.3     .05       0
  5013.8     .07       0  5218.4     .07       0  5636.2    .035       0
Bank Sta=4994.3,5013.8
XS Rating Curve= 0 ,0
Exp/Cntr=0.3,0.1

Type RM Length L Ch R = 1 ,44404   ,447,447,447
BEGIN DESCRIPTION:
NASH CREEK 70.0
END DESCRIPTION:
XS GIS Cut Line= 3
        2366125.       13767425.        2365525.       13766825.
      2364924.97     13766224.97
#Sta/Elev= 30
  4150.3  477.49  4185.7  477.31    4221  474.57  4327.1  471.27    4420   465.6
  4475.6  459.07    4518  457.49  4601.4  457.62  4638.3  458.42  4673.6  457.64
  4687.7  455.59  4701.8  456.22  4730.1  453.41  4786.7  455.96  4839.1  454.88
  4899.8   455.9  4984.7  452.99  5002.4  451.56  5003.2  450.14  5003.7  449.64
  5022.8  450.14  5027.1  452.36  5041.2  452.96  5069.5   461.7  5338.2  462.33
  5408.9  464.81  5507.9  464.85  5559.8  466.79  5722.9  468.69  5847.4  472.09
#Mann= 9 ,-1 , 0
  4150.3     .07       0    4420    .035       0  4601.4     .07       0
  4638.3     .12       0  4839.1     .07       0  5003.2     .05       0
  5022.8     .07       0  5559.8    .035       0  5722.9     .07       0
Bank Sta=5003.2,5022.8
XS Rating Curve= 0 ,0
Exp/Cntr=0.3,0.1

Type RM Length L Ch R = 1 ,43957   ,473,473,473
BEGIN DESCRIPTION:
NASH CREEK 69.0
END DESCRIPTION:
XS GIS Cut Line= 3
      2366425.01     13767025.01        2365825.       13766525.
        2364825.     13765324.99
#Sta/Elev= 30
  4223.7  480.05  4328.4  472.91  4473.1  463.34  4571.9  461.95    4650  455.94
  4862.2  456.29  4948.1   453.9  4973.4   448.9  4973.9   448.4  4993.1   448.9
    5008  449.64  5040.5  459.41  5054.9  457.44  5125.2  457.35  5196.7  458.22
  5211.1  461.09  5493.4  461.12  5565.1   461.7  5572.9  464.35  5579.4  462.24
  5587.3   464.7  5593.8  462.44  5601.6  464.78  5638.8  464.17  5835.9  466.16
  6197.8  476.26  6268.1  483.05  6374.8  486.18  6460.7   494.7  6566.8  499.09
#Mann= 7 ,-1 , 0
  4223.7     .07       0  4328.4    .035       0  4473.1     .07       0
  4973.4     .05       0  4993.1     .07       0  5493.4    .035       0
  5638.8     .07       0
Bank Sta=4973.4,4993.1
XS Rating Curve= 0 ,0
Exp/Cntr=0.3,0.1

Type RM Length L Ch R = 1 ,43484   ,448,448,448
BEGIN DESCRIPTION:
NASH CREEK 68.0
END DESCRIPTION:
XS GIS Cut Line= 3
      2366425.02     13766625.03        2366225.       13766325.
      2365024.98     13765224.98
#Sta/Elev= 30
  4635.3  466.52  4779.6     464  4859.2  458.96  4880.2  454.62  4917.4  457.38
  4931.3  457.96  4952.3   449.9  4978.5  446.83    4979  446.33  4998.3  446.83
  5023.9  451.05  5176.1  453.64  5392.1  455.77  5399.5  453.13  5406.2   456.1
  5731.8  458.01  5916.2  464.26  5951.3  462.96  5965.5  463.62  5979.7  469.85
  5986.5  467.06  5993.9  470.29  6000.7  467.82  6008.1  470.43  6014.9  468.09
  6142.5  471.79  6248.6  482.37  6404.6  486.69  6496.4  494.09  6623.8  495.71
#Mann= 5 ,-1 , 0
  4635.3     .07       0  4917.4     .12       0  4978.5     .05       0
  4998.3     .12       0  5176.1     .07       0
Bank Sta=4978.5,4998.3
XS Rating Curve= 0 ,0
Exp/Cntr=0.3,0.1