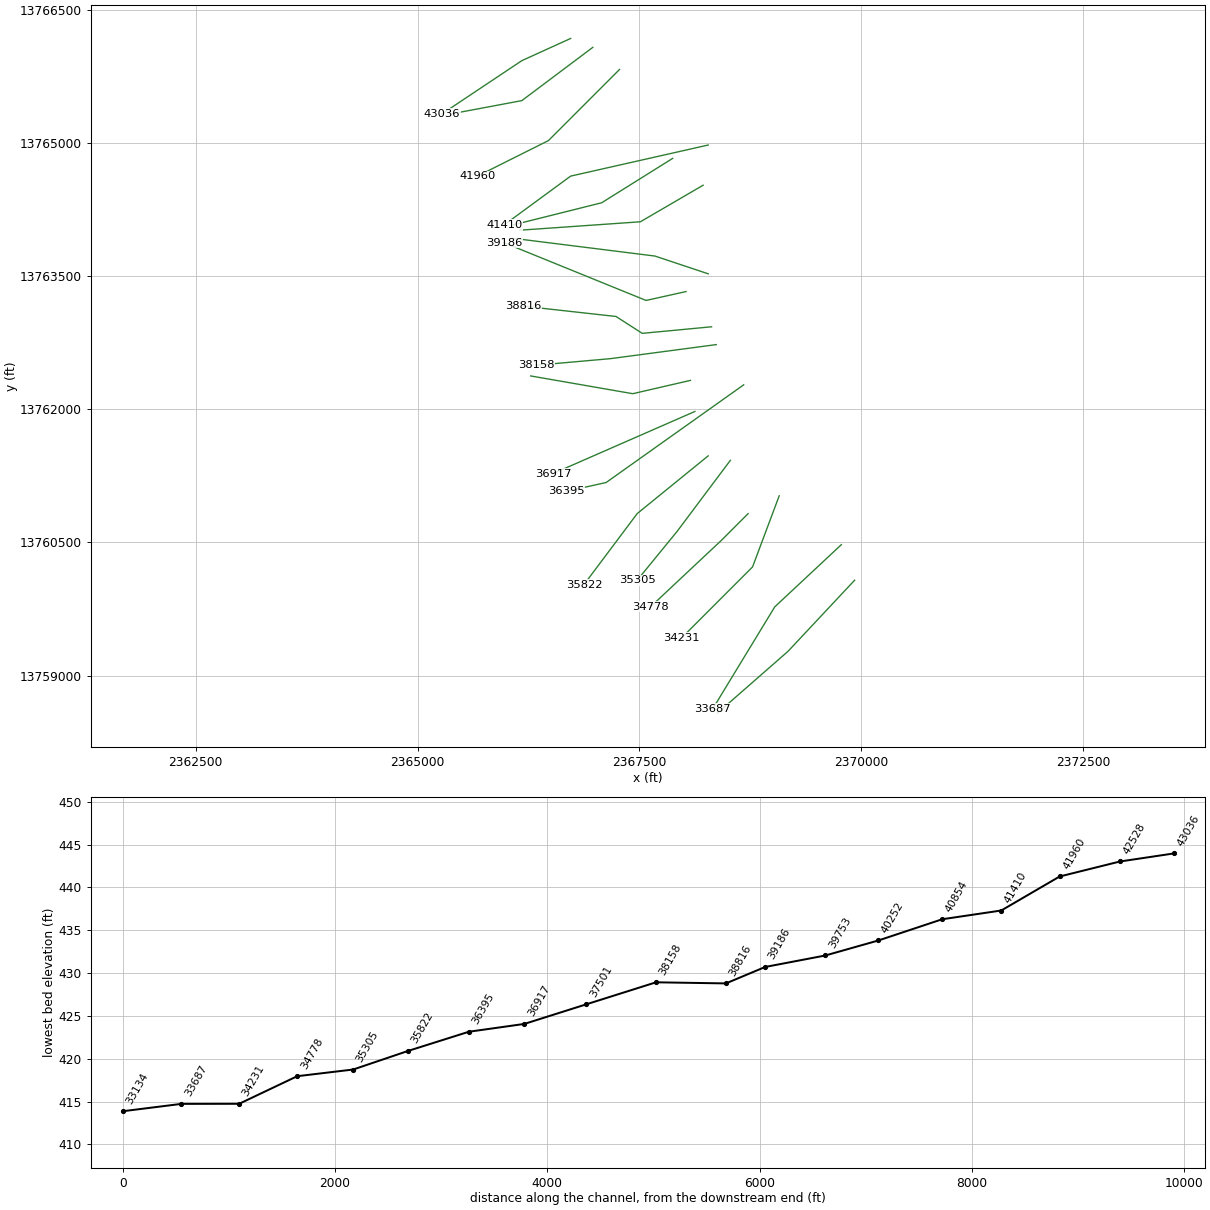
HEC-RAS study NASH CREEK.prj: NASH CREEK Base Level Engineering

--- NASH CREEK.g01 (geometry) --- (continued)

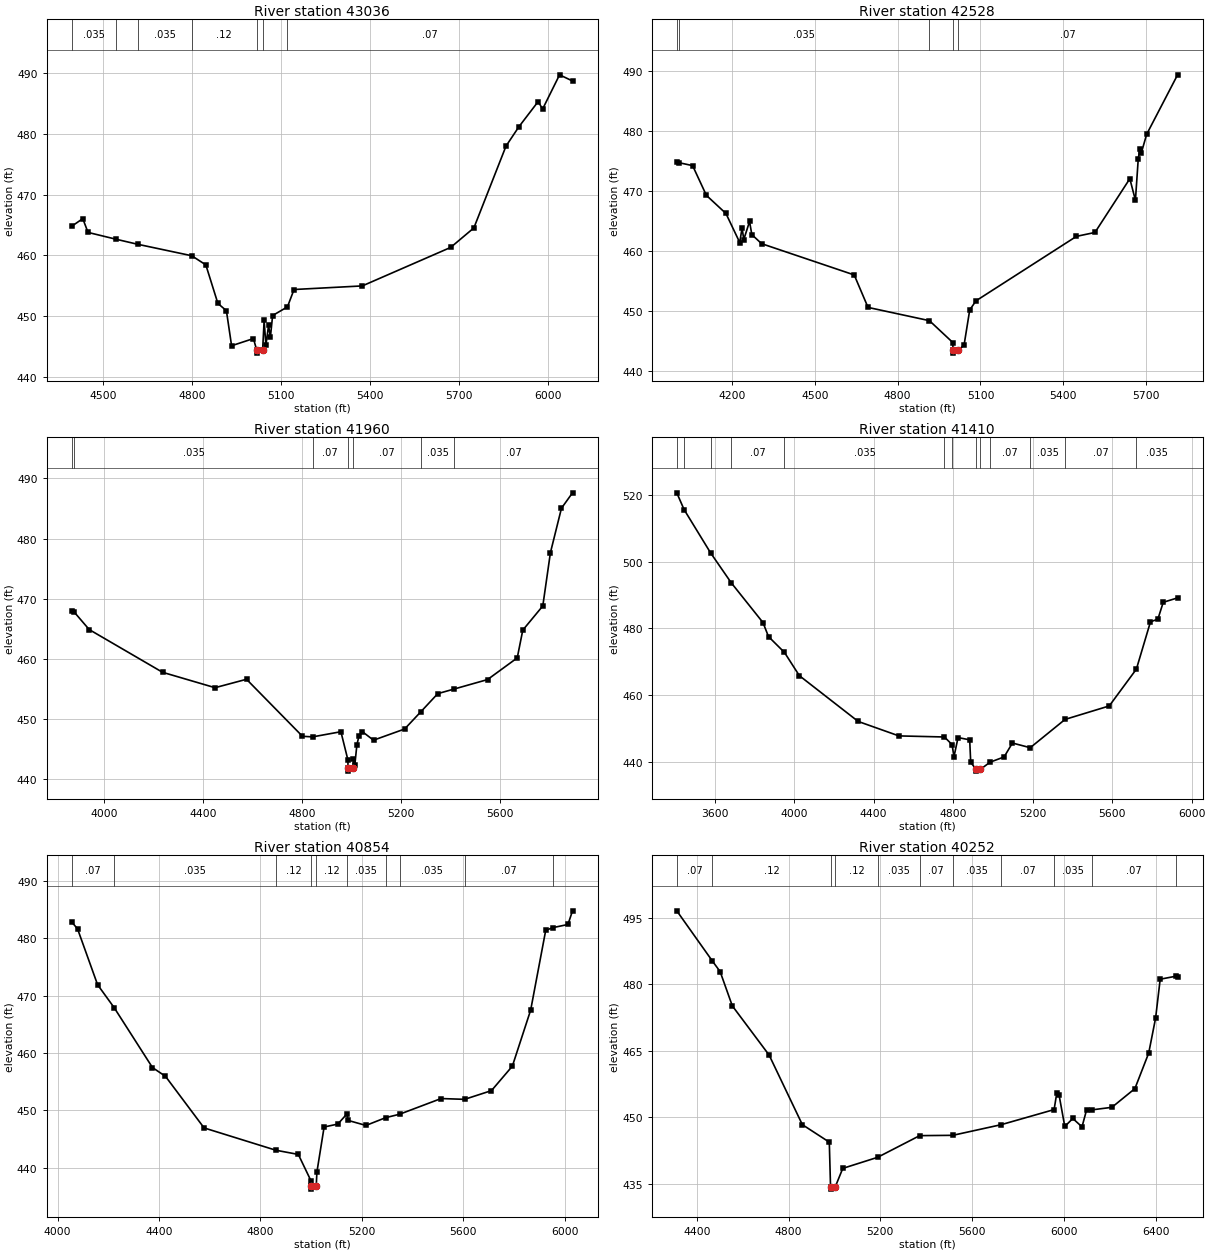
Type RM Length L Ch R = 1 ,43036   ,508,508,508
BEGIN DESCRIPTION:
NASH CREEK 67.0
END DESCRIPTION:
XS GIS Cut Line= 3
      2366724.99       13766175.        2366175.       13765925.
      2365275.01     13765325.01
#Sta/Elev= 30
  4395.7  464.79    4433  466.04  4450.6  463.78    4545  462.66  4617.2  461.84
  4799.8  459.95  4847.2  458.45  4887.8  452.12  4916.4  450.94  4933.9  445.18
  5007.4  446.36  5018.4  444.47  5018.9  443.97  5038.4  444.47  5043.4  449.33
  5049.4  445.27  5058.4  448.53  5064.4  446.54    5072  450.14  5121.9  451.56
  5144.1  454.41  5373.9     455  5671.4  461.32  5749.5  464.52  5857.7  477.95
  5901.2  481.13  5965.8  485.25  5980.9  484.03  6037.9  489.64  6081.5  488.63
#Mann= 7 ,-1 , 0
  4395.7    .035       0    4545     .07       0  4617.2    .035       0
  4799.8     .12       0  5018.4     .05       0  5038.4     .12       0
  5121.9     .07       0
Bank Sta=5018.4,5038.4
XS Rating Curve= 0 ,0
Exp/Cntr=0.3,0.1

Type RM Length L Ch R = 1 ,42528   ,568,568,568
BEGIN DESCRIPTION:
NASH CREEK 66.0
END DESCRIPTION:
XS GIS Cut Line= 3
      2366975.01     13766075.01        2366175.       13765475.
      2365374.95     13765324.99
#Sta/Elev= 30
  3999.9  474.83  4007.5  474.77  4057.2  474.28  4107.2  469.32    4178   466.3
    4228  461.46  4236.4   463.9  4242.6  461.96  4263.5  464.97  4271.8  462.78
  4307.2  461.27  4642.6  456.06  4692.6  450.65    4915  448.44  4999.9  444.79
  5000.1  443.53  5000.6  443.03  5020.1  443.53  5040.6   444.4    5061  450.23
  5083.8  451.75  5447.6  462.49  5514.6  463.14  5640.9   472.1  5661.2   468.5
  5671.4   475.4  5677.3  477.06  5682.4  476.38  5701.9   479.5  5813.9  489.41
#Mann= 5 ,-1 , 0
  3999.9     .07       0  4007.5    .035       0    4915     .07       0
  5000.1     .05       0  5020.1     .07       0
Bank Sta=5000.1,5020.1
XS Rating Curve= 0 ,0
Exp/Cntr=0.3,0.1

Type RM Length L Ch R = 1 ,41960   ,550,550,550
BEGIN DESCRIPTION:
NASH CREEK 65.0
END DESCRIPTION:
XS GIS Cut Line= 3
        2367275.       13765825.        2366475.       13765025.
        2365675.       13764625.
#Sta/Elev= 30
  3868.7   467.9  3879.4  467.73  3939.4  464.85  4236.4  457.73  4448.5  455.17
  4575.8  456.57  4802.1  447.08  4842.9  446.98  4957.6  447.84  4985.9  443.15
  4986.5  441.78    4987  441.28  5006.6  441.78  5008.5  443.36    5014  442.35
  5022.4  445.71  5030.8  447.12  5044.8  447.84  5089.5  446.43  5215.3  448.29
  5281.4  451.18  5349.5  454.18  5416.7  454.96  5550.7  456.52  5670.9  460.13
  5693.3  464.75  5774.3  468.78  5805.1  477.64  5849.8  485.05  5894.5  487.61
#Mann= 7 ,-1 , 0
  3868.7     .07       0  3879.4    .035       0  4842.9     .07       0
  4986.5     .05       0  5006.6     .07       0  5281.4    .035       0
  5416.7     .07       0
Bank Sta=4986.5,5006.6
XS Rating Curve= 0 ,0
Exp/Cntr=0.3,0.1

Type RM Length L Ch R = 1 ,41410   ,556,556,556
BEGIN DESCRIPTION:
NASH CREEK 64.0
END DESCRIPTION:
XS GIS Cut Line= 3
      2368275.03     13764975.01        2366725.       13764625.
      2365975.01       13764075.
#Sta/Elev= 30
  3410.2   520.6    3447  515.58  3580.4  502.62  3684.6  493.64  3843.7  481.78
  3871.6  477.57  3951.9  472.83  4026.8  465.88  4322.6  452.18  4527.7  447.85
  4756.5  447.53  4794.7  445.26  4804.5  441.64    4825  447.35  4883.6  446.68
  4888.7  439.91  4916.7  437.81  4917.2  437.31  4936.9  437.81  4985.5  439.97
  5056.7  441.56  5098.5  445.72  5188.1  444.32  5363.4  452.79  5585.5  456.82
  5722.1  467.84  5792.9     482  5830.1  482.79  5857.2  487.84  5929.3  489.16
#Mann= 13 ,-1 , 0
  3410.2     .12       0    3447     .07       0  3580.4    .035       0
  3684.6     .07       0  3951.9    .035       0  4756.5     .07       0
  4794.7     .12       0  4916.7     .05       0  4936.9     .12       0
  4985.5     .07       0  5188.1    .035       0  5363.4     .07       0
  5722.1    .035       0
Bank Sta=4916.7,4936.9
XS Rating Curve= 0 ,0
Exp/Cntr=0.3,0.1

Type RM Length L Ch R = 1 ,40854   ,602,602,602
BEGIN DESCRIPTION:
NASH CREEK 63.0
END DESCRIPTION:
XS GIS Cut Line= 3
      2367875.02     13764825.02        2367075.       13764325.
        2366075.       13764075.
#Sta/Elev= 30
    4056  482.86    4079  481.66    4158  471.92  4223.4  467.92  4374.4  457.48
  4425.7  455.95  4577.8  446.96  4860.8  443.07  4949.3  442.34  4999.4  437.72
  4999.5  436.79    5000  436.29  5019.9  436.79  5022.6  439.27    5051  447.12
  5105.1  447.63  5140.5  449.38  5146.3  448.26  5215.9  447.39  5293.8  448.75
  5348.2  449.34  5512.2  452.08  5604.6  451.94  5710.7  453.46  5793.1  457.73
  5865.3  467.51  5924.5  481.39  5951.6  481.86  6012.2  482.42  6030.2   484.8
#Mann= 10 ,-1 , 0
    4056     .07       0  4223.4    .035       0  4860.8     .12       0
  4999.5     .05       0  5019.9     .12       0  5140.5    .035       0
  5293.8     .07       0  5348.2    .035       0  5604.6     .07       0
  5951.6    .035       0
Bank Sta=4999.5,5019.9
XS Rating Curve= 0 ,0
Exp/Cntr=0.3,0.1

Type RM Length L Ch R = 1 ,40252   ,499,499,499
BEGIN DESCRIPTION:
B19759
END DESCRIPTION:
XS GIS Cut Line= 3
      2368217.89     13764522.45      2367510.64     13764110.76
      2366149.39     13764015.79
#Sta/Elev= 30
  4312.8  496.61  4468.3  485.26  4501.8  482.89  4554.8  475.17  4715.3  464.06
  4860.1  448.36  4977.6  444.41    4983  434.31  4983.5  433.81  5003.5  434.31
  5036.3  438.49  5187.8  440.98  5371.6  445.88  5515.7  445.95  5726.6  448.35
  5957.5  451.76  5968.8  455.39  5978.8  455.13    6004  447.95    6039  449.75
  6079.1  447.86  6099.1   451.7  6122.9   451.7  6209.4  452.27  6309.6  456.49
  6369.8  464.51  6399.9  472.42  6419.9  481.18  6486.9  481.84  6495.7  481.64
#Mann= 11 ,-1 , 0
  4312.8     .07       0  4468.3     .12       0    4983     .05       0
  5003.5     .12       0  5187.8    .035       0  5371.6     .07       0
  5515.7    .035       0  5726.6     .07       0  5957.5    .035       0
  6122.9     .07       0  6486.9    .035       0
Bank Sta=4983,5003.5
XS Rating Curve= 0 ,0
Exp/Cntr=0.3,0.1

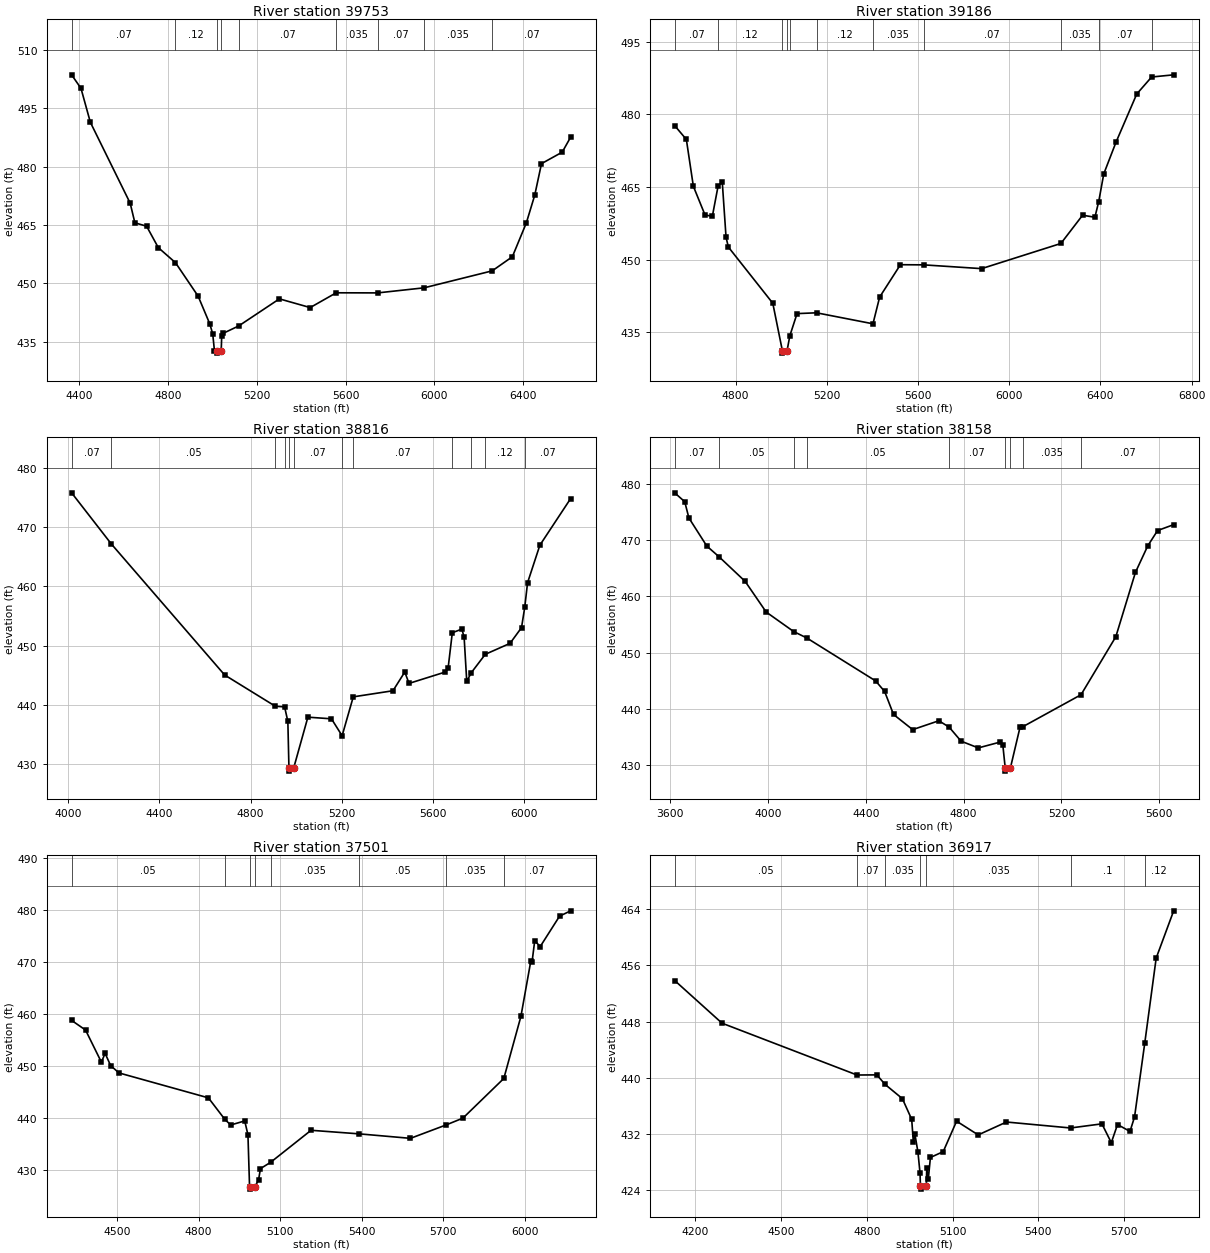
Type RM Length L Ch R = 1 ,39753   ,567,567,567
BEGIN DESCRIPTION:
NASH CREEK 62.0
END DESCRIPTION:
XS GIS Cut Line= 3
      2368274.97     13763525.01        2367675.       13763725.
      2366074.98       13763925.
#Sta/Elev= 30
  4367.6   503.6  4409.7  500.13  4451.9   491.4  4631.1   470.6  4652.2  465.56
  4704.9  464.69  4757.6  459.18  4834.9  455.31  4936.8   446.7  4989.5  439.54
  5002.5  436.98  5010.1  432.71    5020  432.56  5020.5  432.06  5040.5  432.56
  5042.9  436.39  5050.4  437.18  5119.1  439.04  5302.4  446.01  5440.9  443.77
    5558  447.57  5744.1  447.54  5953.7  448.85  6259.8  453.21  6350.5  456.84
  6413.4  465.54  6451.2  472.67  6481.5  480.77  6574.7  483.72  6612.5  487.56
#Mann= 9 ,-1 , 0
  4367.6     .07       0  4834.9     .12       0    5020     .05       0
  5040.5     .12       0  5119.1     .07       0    5558    .035       0
  5744.1     .07       0  5953.7    .035       0  6259.8     .07       0
Bank Sta=5020,5040.5
XS Rating Curve= 0 ,0
Exp/Cntr=0.3,0.1

Type RM Length L Ch R = 1 ,39186   ,370,370,370
BEGIN DESCRIPTION:
NASH CREEK 61.0
END DESCRIPTION:
XS GIS Cut Line= 3
      2368024.98     13763324.99        2367575.       13763225.
      2365975.04     13763874.98
#Sta/Elev= 30
  4533.2  477.65  4584.4   474.8  4615.1  465.14  4666.3  459.21  4698.4  458.96
  4723.8  465.25  4741.9  465.98  4758.5  454.58  4768.8  452.59  4963.4  441.01
  5005.4  431.22  5005.9  430.72    5026  431.22  5038.1  434.29  5069.7  438.87
  5155.1  439.04  5402.6  436.77  5431.9  442.28    5523  448.96  5624.3  448.93
    5879  448.15  6226.6  453.34  6321.8  459.17  6375.7  458.75  6392.4  461.96
  6414.6  467.69  6468.1  474.21  6559.2  484.17  6624.4  487.68  6721.1  488.13
#Mann= 11 ,-1 , 0
  4533.2     .07       0  4723.8     .12       0  5005.4     .05       0
    5026     .12       0  5038.1     .07       0  5155.1     .12       0
  5402.6    .035       0  5624.3     .07       0  6226.6    .035       0
  6392.4     .07       0  6624.4    .035       0
Bank Sta=5005.4,5026
XS Rating Curve= 0 ,0
Exp/Cntr=0.3,0.1

Type RM Length L Ch R = 1 ,38816   ,658,658,658
BEGIN DESCRIPTION:
B19758
END DESCRIPTION:
XS GIS Cut Line= 4
      2368312.95     13762928.45      2367531.75     13762854.55
      2367236.17     13763044.57      2366191.08     13763160.69
#Sta/Elev= 30
  4015.7  475.78  4190.4  467.12  4686.6  445.03  4908.9  439.75  4949.4  439.65
  4963.7   437.2  4968.5   429.3    4969   428.8  4989.1   429.3  5051.5  437.91
  5154.9  437.63  5201.6  434.77  5250.5  441.34  5424.6  442.37  5476.3  445.53
    5495  443.61  5652.4  445.51  5666.1  446.13  5684.7  452.16  5726.5  452.78
  5736.5  451.41    5748  443.96    5768  445.42  5829.3  448.52  5937.8  450.37
  5988.1  453.02  6002.2  456.44  6014.6   460.6  6068.6  466.94  6203.3   474.8
#Mann= 12 ,-1 , 0
  4015.7     .07       0  4190.4     .05       0  4908.9     .12       0
  4949.4     .07       0  4968.5     .05       0  4989.1     .07       0
  5201.6     .12       0  5250.5     .07       0  5684.7     .12       0
    5768     .07       0  5829.3     .12       0  6002.2     .07       0
Bank Sta=4968.5,4989.1
XS Rating Curve= 0 ,0
Exp/Cntr=0.3,0.1

Type RM Length L Ch R = 1 ,38158   ,657,657,657
BEGIN DESCRIPTION:
NASH CREEK 60.0
END DESCRIPTION:
XS GIS Cut Line= 3
      2368365.73     13762727.88      2367172.83     13762569.53
      2366339.46     13762495.69
#Sta/Elev= 30
  3618.7  478.43  3659.8  476.85  3676.8  473.96  3750.1  468.96    3800  467.06
  3906.8  462.68  3992.7  457.23  4105.4  453.75  4158.6  452.62  4440.1  444.98
  4476.9  443.11  4513.4  439.01  4591.7  436.31  4698.8  437.89  4740.9  436.75
  4789.6  434.26    4860  433.06  4950.4  434.11  4960.4  433.52  4970.2  429.43
  4970.7  428.93  4990.9  429.43  5030.7  436.76  5043.3  436.86    5280  442.52
  5422.2  452.83  5502.5  464.29  5552.7  468.99  5592.9  471.72  5658.7  472.77
#Mann= 9 ,-1 , 0
  3618.7     .07       0    3800     .05       0  4105.4    .035       0
  4158.6     .05       0  4740.9     .07       0  4970.2     .05       0
  4990.9     .07       0  5043.3    .035       0    5280     .07       0
Bank Sta=4970.2,4990.9
XS Rating Curve= 0 ,0
Exp/Cntr=0.3,0.1

Type RM Length L Ch R = 1 ,37501   ,584,584,584
BEGIN DESCRIPTION:
NASH CREEK 59.0
END DESCRIPTION:
XS GIS Cut Line= 3
      2368074.97     13762324.99        2367425.       13762175.
      2366275.01       13762375.
#Sta/Elev= 30
  4333.4  458.82  4384.7  456.96  4442.8  450.79  4456.5  452.48    4477  450.11
  4507.8  448.71  4836.2  443.92  4896.5  439.79  4918.3   438.7  4969.7  439.48
  4981.6  436.82  4987.5  426.86    4988  426.36  5008.3  426.86  5020.7  428.19
  5027.7  430.31    5065  431.52  5213.6  437.68  5391.2  436.99    5579  436.13
  5710.1  438.71  5771.9  440.02  5922.2  447.65    5985  459.58  6021.2  470.17
  6026.2  470.15  6035.8  474.14  6056.1  473.03  6127.1  478.87  6167.7   479.9
#Mann= 8 ,-1 , 0
  4333.4     .05       0  4896.5     .07       0  4987.5     .05       0
  5008.3     .07       0    5065    .035       0  5391.2     .05       0
  5710.1    .035       0  5922.2     .07       0
Bank Sta=4987.5,5008.3
XS Rating Curve= 0 ,0
Exp/Cntr=0.3,0.1

Type RM Length L Ch R = 1 ,36917   ,522,522,522
BEGIN DESCRIPTION:
NASH CREEK 58.0
END DESCRIPTION:
XS GIS Cut Line= 3
      2368125.04     13761975.02        2367325.       13761625.
      2366524.98     13761274.99
#Sta/Elev= 30
  4127.5  453.85  4293.2  447.76  4765.8  440.36  4835.1  440.38  4863.9  439.02
  4924.4  436.99  4957.1  434.03  4962.9  430.77  4968.4  431.89  4978.9  429.37
  4986.3  426.34  4987.6  424.57  4988.1  424.07  5008.4  424.57  5009.7  427.13
  5015.2  425.51  5022.6  428.59  5067.4  429.42  5114.2  433.77  5189.8  431.81
  5288.8  433.65    5513   432.8  5622.9  433.39  5655.7   430.7  5677.5  433.29
  5721.2  432.31  5737.1  434.38  5772.7  444.88  5812.8  457.05    5874   463.8
#Mann= 7 ,-1 , 0
  4127.5     .05       0  4765.8     .07       0  4863.9    .035       0
  4987.6    .035       0  5008.4    .035       0    5513      .1       0
  5772.7     .12       0
Bank Sta=4987.6,5008.4
XS Rating Curve= 0 ,0
Exp/Cntr=0.3,0.1

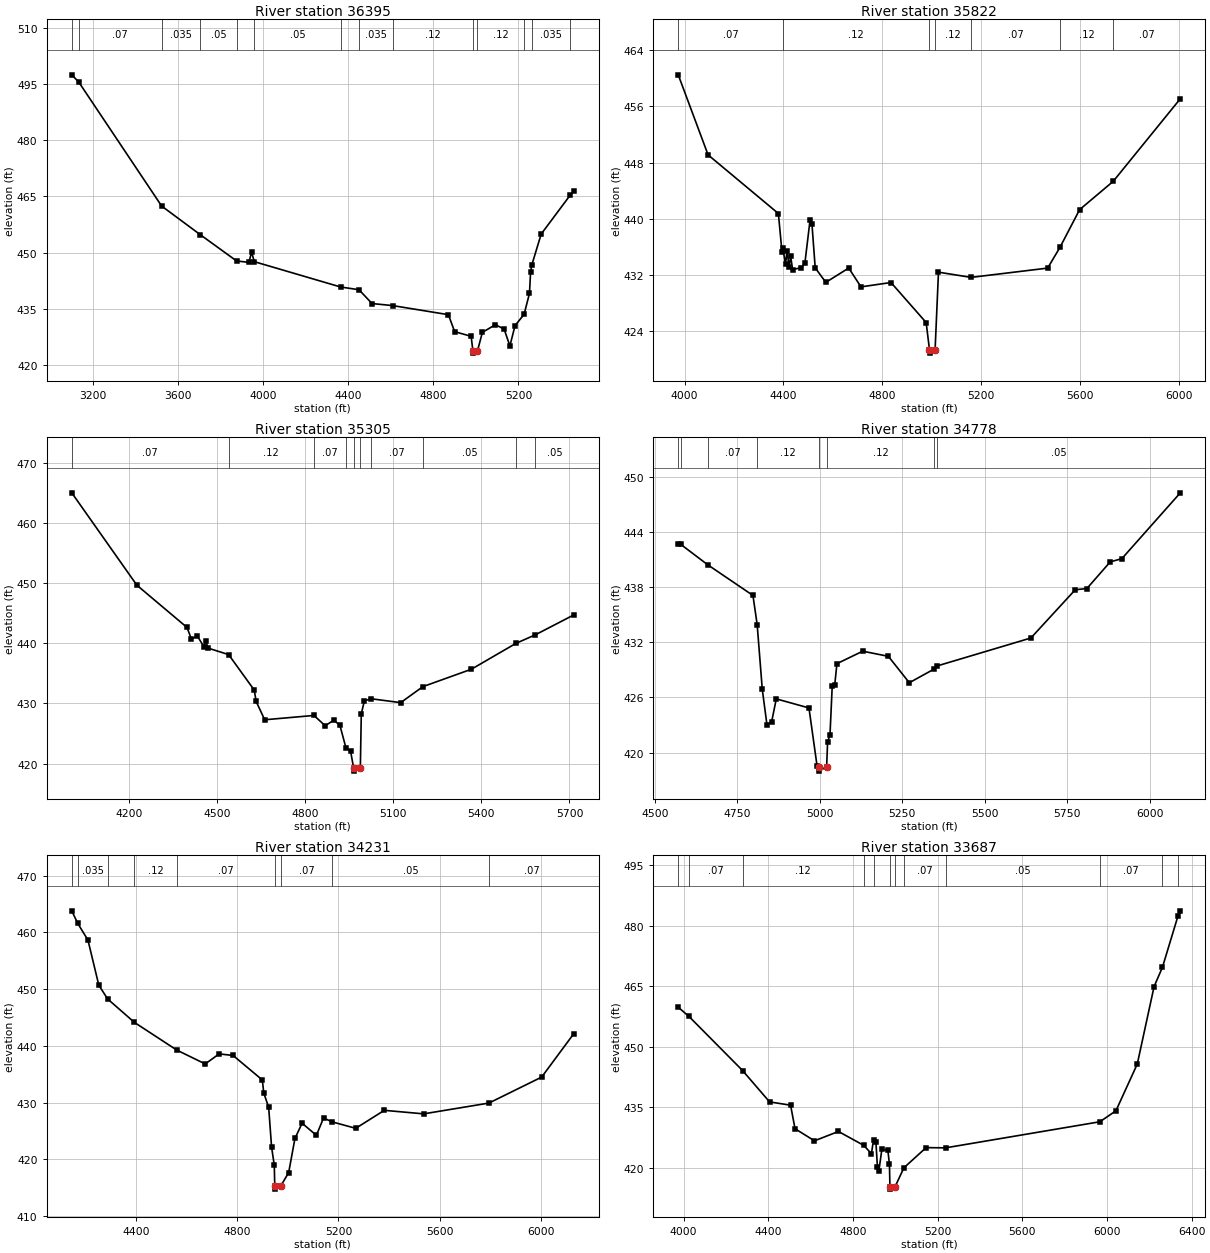
Type RM Length L Ch R = 1 ,36395   ,573,573,573
BEGIN DESCRIPTION:
NASH CREEK 57.0
END DESCRIPTION:
XS GIS Cut Line= 3
      2368675.03     13762275.02        2367125.       13761175.
      2366674.97     13761074.99
#Sta/Elev= 30
  3099.2  497.43    3132   495.5  3522.1   462.4  3704.4  454.74  3874.1  447.77
  3932.1  447.37  3945.3  450.09  3957.6  447.57  4363.7  440.81  4450.3  440.08
  4511.5  436.39  4608.1  435.85  4870.7  433.42  4900.3  428.89  4977.7  427.65
  4986.4  423.66  4986.9  423.16  5007.2  423.66  5030.6   428.7  5092.1  430.75
  5133.1  429.56    5160  425.07  5184.3  430.51  5226.8   433.5  5252.2  439.11
  5257.3  444.71  5262.7  446.59  5307.2  454.93  5442.6  465.23  5460.9  466.49
#Mann= 14 ,-1 , 0
  3099.2     .05       0    3132     .07       0  3522.1    .035       0
  3704.4     .05       0  3874.1     .07       0  3957.6     .05       0
  4363.7     .07       0  4450.3    .035       0  4608.1     .12       0
  4986.4     .05       0  5007.2     .12       0  5226.8      .1       0
  5262.7    .035       0  5442.6     .07       0
Bank Sta=4986.4,5007.2
XS Rating Curve= 0 ,0
Exp/Cntr=0.3,0.1

Type RM Length L Ch R = 1 ,35822   ,517,517,517
BEGIN DESCRIPTION:
NASH CREEK 56.0
END DESCRIPTION:
XS GIS Cut Line= 3
        2368275.       13761475.        2367475.       13760825.
      2366874.98     13760024.98
#Sta/Elev= 30
  3974.3  460.49    4095  449.11  4379.4  440.77  4393.8  435.36  4397.2  435.85
  4408.2  433.58  4414.6  435.51  4422.5  433.13    4429  434.68  4436.9  432.81
  4472.1  433.06  4486.5  433.69  4507.3  439.79  4515.2  439.26  4528.3  433.05
  4571.2  430.98  4663.9  433.02  4713.4  430.34  4834.8  430.96  4977.1  425.27
  4990.5  421.42    4991  420.92  5013.3  421.42  5026.9  432.43    5159  431.69
  5468.6  433.01  5518.6  435.98  5597.8  441.32  5733.8  445.35  6005.1  457.09
#Mann= 7 ,-1 , 0
  3974.3     .07       0  4397.2     .12       0  4990.5     .05       0
  5013.3     .12       0    5159     .07       0  5518.6     .12       0
  5733.8     .07       0
Bank Sta=4990.5,5013.3
XS Rating Curve= 0 ,0
Exp/Cntr=0.3,0.1

Type RM Length L Ch R = 1 ,35305   ,527,527,527
BEGIN DESCRIPTION:
NASH CREEK 55.0
END DESCRIPTION:
XS GIS Cut Line= 3
      2368524.98     13761424.97        2367925.       13760625.
        2367475.       13760075.
#Sta/Elev= 30
  4004.3  465.03  4226.1  449.67    4397  442.64  4411.6  440.74  4432.4  441.19
  4454.3  439.46  4461.6  440.42  4467.8  439.22  4538.7  438.13  4626.1  432.22
  4632.4  430.35  4661.6  427.29  4829.5  428.01  4867.8  426.29    4897  427.23
  4917.8  426.38  4938.5   422.6  4954.3  422.05  4964.7  419.25  4965.2  418.75
  4987.5  419.25  4990.7  428.27  5001.1  430.42  5023.3  430.79  5124.9  430.14
  5200.6   432.8    5366   435.7  5517.4  439.99  5583.8  441.42  5714.9  444.73
#Mann= 10 ,-1 , 0
  4004.3     .07       0  4538.7     .12       0  4829.5     .07       0
  4938.5     .12       0  4964.7     .05       0  4987.5     .12       0
  5023.3     .07       0  5200.6     .05       0  5517.4     .07       0
  5583.8     .05       0
Bank Sta=4964.7,4987.5
XS Rating Curve= 0 ,0
Exp/Cntr=0.3,0.1

Type RM Length L Ch R = 1 ,34778   ,547,547,547
BEGIN DESCRIPTION:
NASH CREEK 54.0
END DESCRIPTION:
XS GIS Cut Line= 3
      2368725.01     13760825.01        2368425.       13760525.
      2367624.97     13759774.97
#Sta/Elev= 30
  4571.1  442.75  4578.7   442.7  4660.2  440.48  4797.4  437.13  4810.2  433.95
  4825.7  426.88  4839.8  423.04    4854  423.34  4868.1  425.85  4967.1  424.86
  4991.8   418.5  4997.9  418.47  4998.4  417.97  5020.7  418.47  5023.5  421.13
  5030.8  421.92  5037.6  427.28    5045  427.31  5051.8  429.69  5129.9  431.05
  5207.6  430.49  5271.1  427.61  5346.6  429.11  5355.3  429.44  5639.4  432.49
  5773.7  437.75  5808.9  437.88  5879.7  440.79  5914.9  441.14    6092  448.32
#Mann= 8 ,-1 , 0
  4571.1     .07       0  4578.7     .12       0  4660.2     .07       0
  4810.2     .12       0  4997.9     .05       0  5020.7     .12       0
  5346.6     .07       0  5355.3     .05       0
Bank Sta=4997.9,5020.7
XS Rating Curve= 0 ,0
Exp/Cntr=0.3,0.1

Type RM Length L Ch R = 1 ,34231   ,544,544,544
BEGIN DESCRIPTION:
NASH CREEK 53.0
END DESCRIPTION:
XS GIS Cut Line= 3
        2369075.       13761025.        2368775.       13760225.
      2367974.98     13759424.98
#Sta/Elev= 30
  4145.5  463.81  4169.3  461.58  4209.6  458.64  4252.3  450.72  4287.3  448.27
  4393.6  444.13  4560.9  439.26  4673.3  436.82  4728.5  438.59  4783.6  438.31
  4899.3  433.99  4904.7  431.73  4924.3  429.16  4935.8  422.15  4946.5  418.96
  4948.4  415.25  4948.9  414.75  4971.3  415.25  5003.4  417.67  5028.2  423.69
  5056.5  426.37    5113  424.23  5141.3  427.29  5175.9   426.6  5268.6  425.47
  5381.7  428.64  5537.3  428.02  5795.3  429.92    6004   434.5  6131.3  442.17
#Mann= 9 ,-1 , 0
  4145.5     .07       0  4169.3    .035       0  4287.3     .07       0
  4393.6     .12       0  4560.9     .07       0  4948.4     .05       0
  4971.3     .07       0  5175.9     .05       0  5795.3     .07       0
Bank Sta=4948.4,4971.3
XS Rating Curve= 0 ,0
Exp/Cntr=0.3,0.1

Type RM Length L Ch R = 1 ,33687   ,553,553,553
BEGIN DESCRIPTION:
NASH CREEK 52.0
END DESCRIPTION:
XS GIS Cut Line= 3
      2369775.02     13760475.02        2369025.       13759775.
      2368325.02     13758625.03
#Sta/Elev= 30
  3974.5  459.83  4024.8  457.57  4278.6  444.13  4406.1  436.36  4505.3  435.55
  4526.3  429.71  4618.2  426.72  4731.5  429.03  4850.9  425.59  4887.3  423.53
  4897.4  427.02  4908.4  426.49  4915.7  420.12  4922.5  419.27  4936.7  424.66
    4965  424.35  4972.4  420.89  4974.8  415.24  4975.3  414.74  4998.2  415.24
  5040.7  420.03  5145.7  425.03  5237.4  424.97  5966.7  431.44  6042.4  434.15
  6143.3  445.74  6222.8  464.96  6262.3  469.74  6335.8  482.47  6346.7  483.73
#Mann= 12 ,-1 , 0
  3974.5     .12       0  4024.8     .07       0  4278.6     .12       0
  4850.9     .07       0  4897.4     .12       0  4974.8     .05       0
  4998.2     .12       0  5040.7     .07       0  5237.4     .05       0
  5966.7     .07       0  6262.3     .12       0  6335.8     .07       0
Bank Sta=4974.8,4998.2
XS Rating Curve= 0 ,0
Exp/Cntr=0.3,0.1

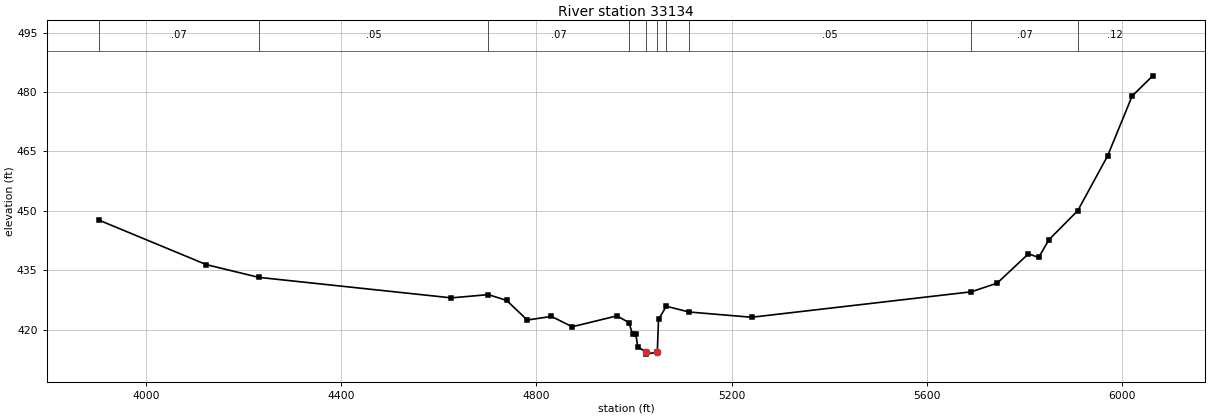
Type RM Length L Ch R = 1 ,33134   ,568,568,568
BEGIN DESCRIPTION:
NASH CREEK 51.0
END DESCRIPTION:
XS GIS Cut Line= 3
      2369925.02     13760075.02        2369175.       13759275.
      2368375.02     13758575.02
#Sta/Elev= 30
  3903.9  447.64  4123.2  436.46  4230.3  433.25  4625.6  428.07  4701.3  428.89
  4738.9  427.43  4781.2  422.48  4830.8  423.39  4873.3  420.78  4965.1  423.53
  4989.7  421.83  4997.1  418.87  5003.8  418.87  5007.6  415.78  5024.4  414.38
  5024.9  413.88  5047.8  414.38  5050.3  422.63  5066.2  425.96  5112.6  424.51
  5241.1  423.18  5691.4   429.6  5744.6  431.79  5808.7  439.19  5829.6  438.27
  5850.9  442.77  5909.8  450.07    5971   463.9  6021.3     479  6063.5  484.08
#Mann= 10 ,-1 , 0
  3903.9     .07       0  4230.3     .05       0  4701.3     .07       0
  4989.7     .05       0  5024.4     .05       0  5047.8     .05       0
  5066.2     .07       0  5112.6     .05       0  5691.4     .07       0
  5909.8     .12       0
Bank Sta=5024.4,5047.8
XS Rating Curve= 0 ,0
Exp/Cntr=0.3,0.1