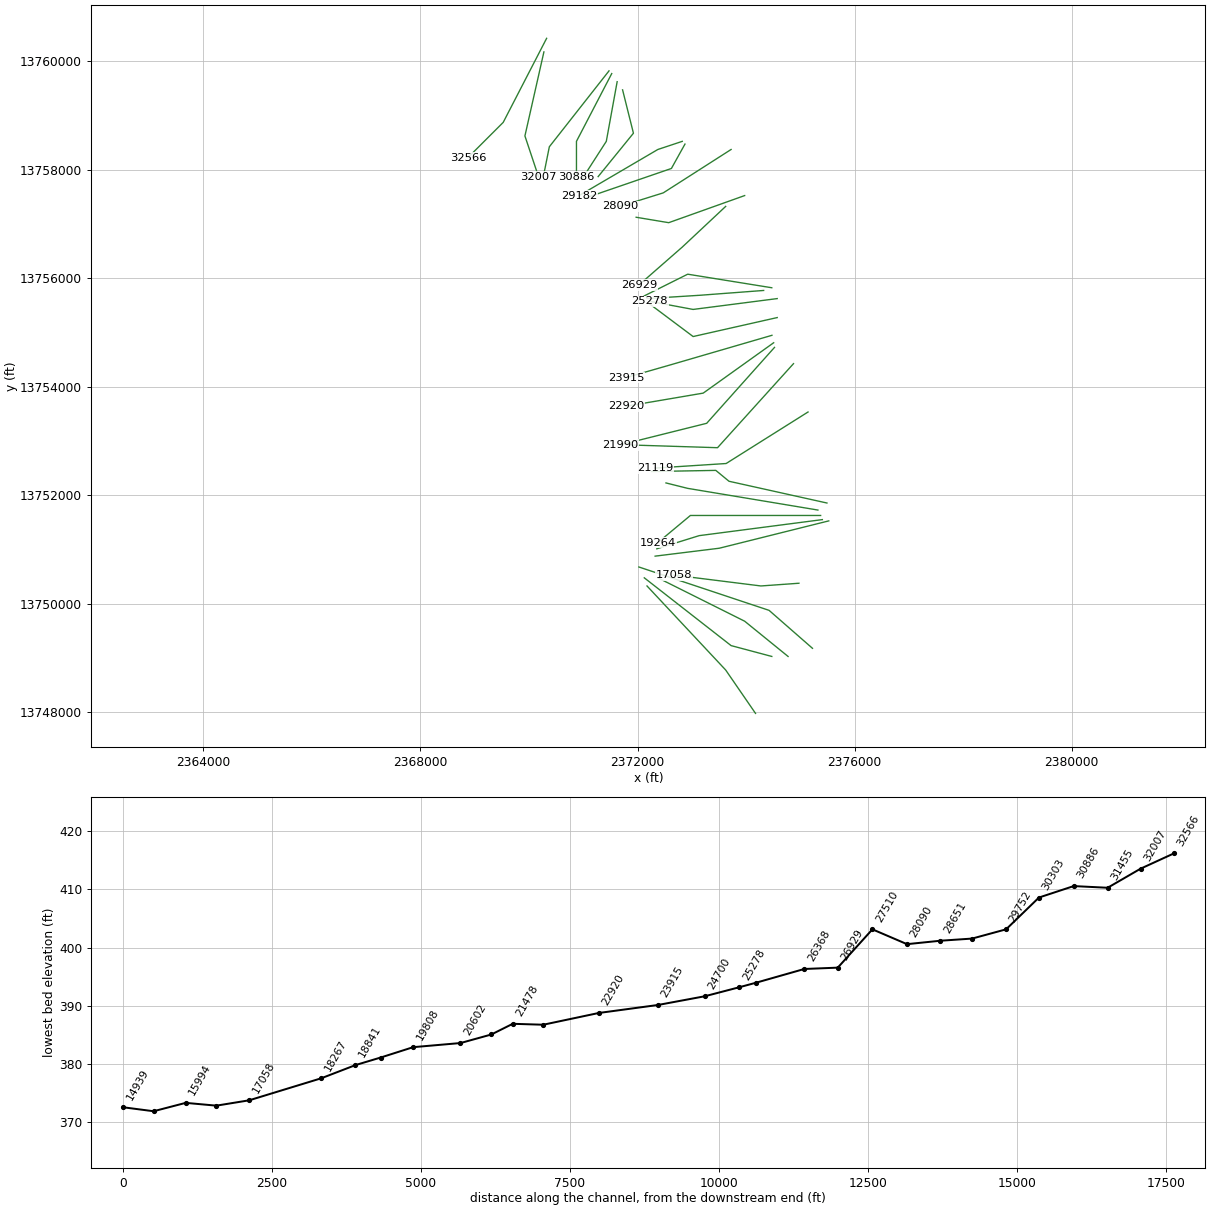
HEC-RAS study NASH CREEK.prj: NASH CREEK Base Level Engineering

--- NASH CREEK.g01 (geometry) --- (continued)

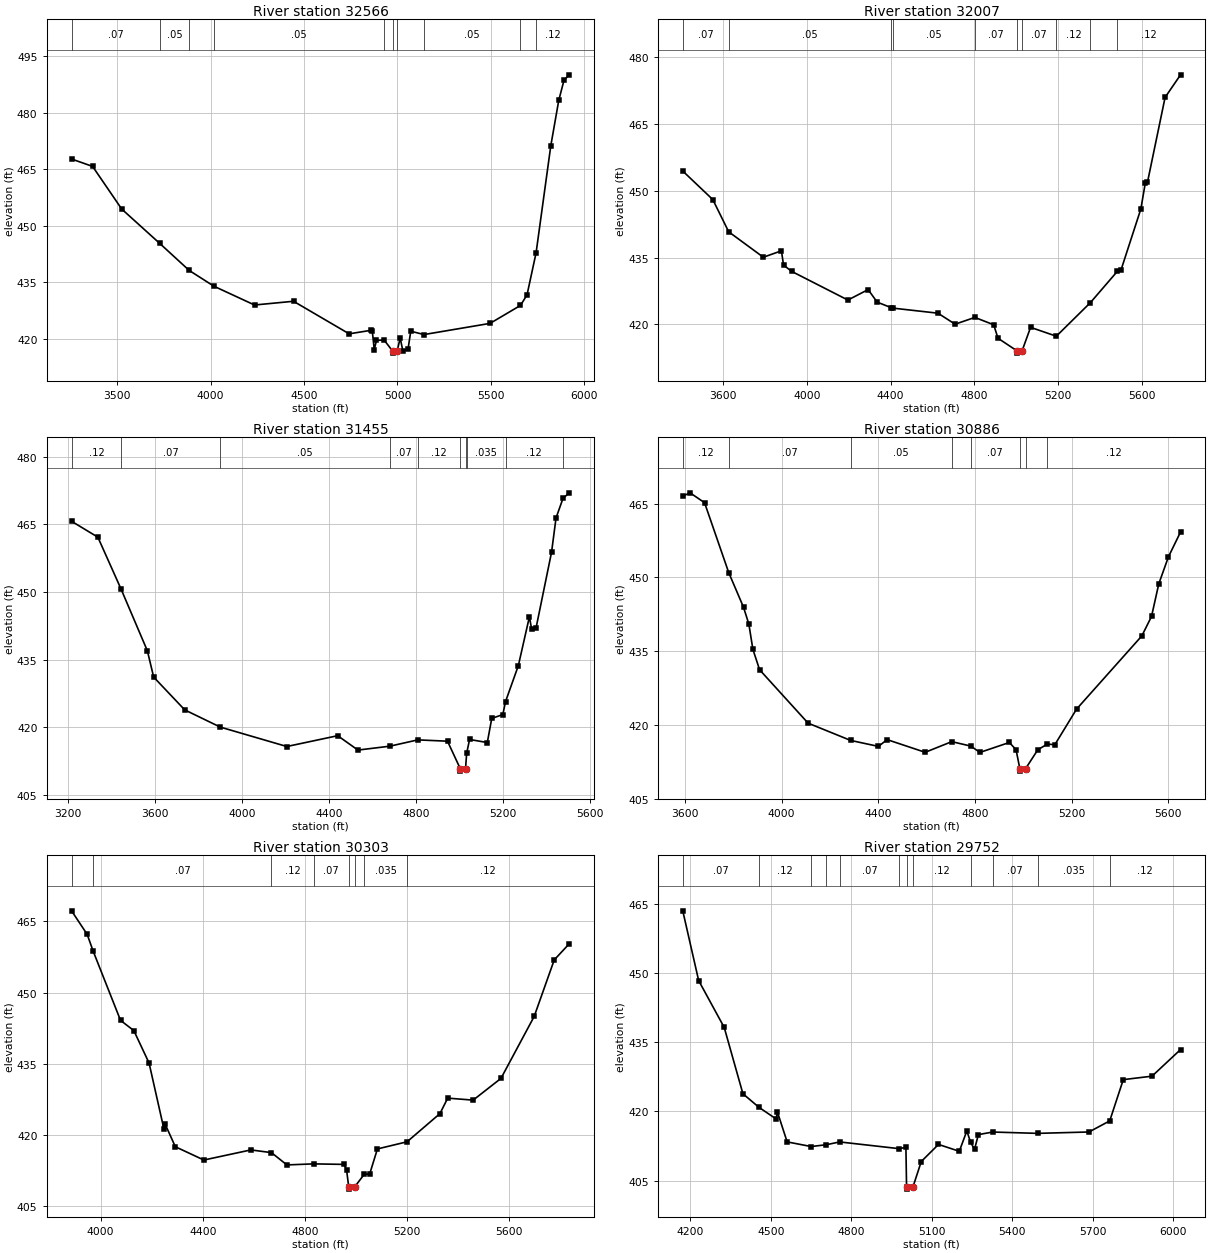
Type RM Length L Ch R = 1 ,32566   ,559,559,559
BEGIN DESCRIPTION:
NASH CREEK 50.0
END DESCRIPTION:
XS GIS Cut Line= 3
      2370324.98     13760424.97        2369525.       13758875.
      2368874.99     13758224.99
#Sta/Elev= 30
    3256   467.7  3368.5  465.74  3524.5  454.42  3727.7  445.31  3885.5  438.13
    4018  433.94    4235  428.96  4443.7  429.95  4741.4  421.31    4859  422.25
  4865.2  422.03  4875.6  417.15  4887.7  419.57  4928.3  419.67  4974.6  416.69
  4975.1  416.19  4998.1  416.69  5014.4  420.21  5028.5  416.85  5056.8  417.35
    5071     422  5142.1  421.12  5495.2  424.08  5658.2  428.85  5693.2  431.66
  5741.6   442.8  5820.5  471.27  5862.9  483.25  5891.2  488.64  5919.5  490.04
#Mann= 10 ,-1 , 0
    3256     .07       0  3727.7     .05       0  3885.5     .07       0
    4018     .05       0  4928.3     .07       0  4974.6     .05       0
  4998.1     .07       0  5142.1     .05       0  5658.2     .07       0
  5741.6     .12       0
Bank Sta=4974.6,4998.1
XS Rating Curve= 0 ,0
Exp/Cntr=0.3,0.1

Type RM Length L Ch R = 1 ,32007   ,552,552,552
BEGIN DESCRIPTION:
NASH CREEK 49.0
END DESCRIPTION:
XS GIS Cut Line= 3
      2370275.01     13760175.03        2369925.       13758625.
      2370174.99     13757875.02
#Sta/Elev= 30
  3406.8  454.46  3550.4  448.05  3626.5  440.81    3792   435.1  3878.4  436.54
  3888.7  433.34  3926.7  431.94  4196.2  425.48  4292.9  427.83  4336.1  425.02
  4403.8  423.76  4409.5  423.68  4626.8  422.53  4708.8  420.06  4803.1  421.58
  4893.3  419.93  4913.8   416.9    5005  414.06  5005.5  413.56  5028.8  414.06
  5069.6  419.35  5192.7  417.36  5355.9  424.92  5483.8   431.9  5501.8  432.22
  5596.7  445.94  5617.8  451.72  5628.3  451.92  5712.6     471  5786.4  476.07
#Mann= 10 ,-1 , 0
  3406.8     .07       0  3626.5     .05       0  4403.8     .07       0
  4409.5     .05       0  4803.1     .07       0    5005     .05       0
  5028.8     .07       0  5192.7     .12       0  5355.9    .035       0
  5483.8     .12       0
Bank Sta=5005,5028.8
XS Rating Curve= 0 ,0
Exp/Cntr=0.3,0.1

Type RM Length L Ch R = 1 ,31455   ,569,569,569
BEGIN DESCRIPTION:
NASH CREEK 48.0
END DESCRIPTION:
XS GIS Cut Line= 3
      2371475.01     13759825.01        2370375.       13758425.
      2370274.99     13757924.96
#Sta/Elev= 30
  3214.8   465.7  3335.9  462.17  3443.4  450.57  3563.7  436.96  3592.6  431.14
  3735.4  423.87  3898.9  420.05  4205.3  415.74  4439.4  418.14  4532.5  414.95
  4679.1  415.81  4807.9  417.21  4944.7  416.92  5003.8  410.78  5004.3  410.28
  5027.6  410.78  5032.8  414.27  5046.3   417.3  5127.8  416.62  5148.2  421.97
  5199.2  422.83  5211.7  425.71  5270.6  433.68  5321.6  444.53  5331.8  441.71
  5352.2  442.06  5423.6  458.89    5444  466.43  5476.3  470.81  5505.2  472.01
#Mann= 10 ,-1 , 0
  3214.8     .12       0  3443.4     .07       0  3898.9     .05       0
  4679.1     .07       0  4807.9     .12       0  5003.8     .05       0
  5027.6     .12       0  5032.8    .035       0  5211.7     .12       0
  5476.3     .07       0
Bank Sta=5003.8,5027.6
XS Rating Curve= 0 ,0
Exp/Cntr=0.3,0.1

Type RM Length L Ch R = 1 ,30886   ,583,583,583
BEGIN DESCRIPTION:
NASH CREEK 47.0
END DESCRIPTION:
XS GIS Cut Line= 3
        2371525.       13759775.        2370875.       13758525.
        2370875.       13757875.
#Sta/Elev= 30
  3591.2  466.53  3621.5   467.2  3681.4  465.19  3781.3  450.97  3842.6  443.91
  3864.7  440.47  3881.2  435.37    3909   431.2  4109.7  420.33  4285.5  416.82
  4400.6   415.6  4436.5  416.98  4593.9   414.4  4703.9  416.57  4782.1  415.67
  4820.6  414.38    4942   416.4  4969.8  414.93  4985.4  411.07  4985.9  410.57
  5009.2  411.07  5060.1  414.94  5099.8  416.08  5130.1  415.94  5220.1  423.19
  5490.1  438.09  5530.1  442.04  5560.1  448.67  5600.1  454.18  5650.1  459.22
#Mann= 8 ,-1 , 0
  3591.2     .12       0  3781.3     .07       0  4285.5     .05       0
  4703.9     .12       0  4782.1     .07       0  4985.4    .035       0
  5009.2     .07       0  5099.8     .12       0
Bank Sta=4985.4,5009.2
XS Rating Curve= 0 ,0
Exp/Cntr=0.3,0.1

Type RM Length L Ch R = 1 ,30303   ,551,551,551
BEGIN DESCRIPTION:
NASH CREEK 46.0
END DESCRIPTION:
XS GIS Cut Line= 3
        2371625.     13759625.02        2371425.       13758525.
      2370975.01     13757825.02
#Sta/Elev= 30
  3886.2  467.23  3947.2  462.29  3971.1   458.7  4078.1  444.15  4130.2     442
  4189.9  435.16  4248.3  421.21  4253.4  422.22  4292.8  417.53  4404.6  414.73
  4588.8  416.86  4669.4  416.29  4729.8   413.7  4834.5  413.92  4953.4  413.81
  4963.6  412.69    4972   409.1  4972.5   408.6  4995.8   409.1  5033.3  411.75
  5054.1  411.76  5084.5  417.07  5200.6  418.57  5329.5  424.51  5359.9  427.77
  5459.6  427.35  5568.6  431.93  5698.7  444.98  5777.3  456.89  5836.4  460.31
#Mann= 8 ,-1 , 0
  3886.2     .12       0  3971.1     .07       0  4669.4     .12       0
  4834.5     .07       0    4972     .05       0  4995.8     .07       0
  5033.3    .035       0  5200.6     .12       0
Bank Sta=4972,4995.8
XS Rating Curve= 0 ,0
Exp/Cntr=0.3,0.1

Type RM Length L Ch R = 1 ,29752   ,570,570,570
BEGIN DESCRIPTION:
NASH CREEK 45.0
END DESCRIPTION:
XS GIS Cut Line= 3
        2371725.     13759474.99        2371925.       13758675.
      2371274.99     13757874.99
#Sta/Elev= 30
  4172.1  463.52  4231.4  448.38  4326.7  438.21  4396.3  423.83  4455.7   420.9
    4520  418.36  4525.1  419.84  4561.2  413.38  4650.8  412.37  4707.8  412.77
  4756.9  413.37  4978.9  411.91  5003.9  412.21  5006.3  403.63  5006.8  403.13
  5030.3  403.63  5061.1  409.12  5125.3  412.83  5202.9  411.34  5230.9  415.75
  5245.2  413.27  5259.6  411.76    5274  414.96  5327.5  415.52  5494.6  415.23
  5686.3  415.53  5763.6  417.94  5814.1  426.89  5921.2  427.64  6027.5  433.41
#Mann= 12 ,-1 , 0
  4172.1     .07       0  4455.7     .12       0  4650.8     .07       0
  4707.8     .12       0  4756.9     .07       0  4978.9     .12       0
  5006.3     .05       0  5030.3     .12       0  5245.2    .035       0
  5327.5     .07       0  5494.6    .035       0  5763.6     .12       0
Bank Sta=5006.3,5030.3
XS Rating Curve= 0 ,0
Exp/Cntr=0.3,0.1

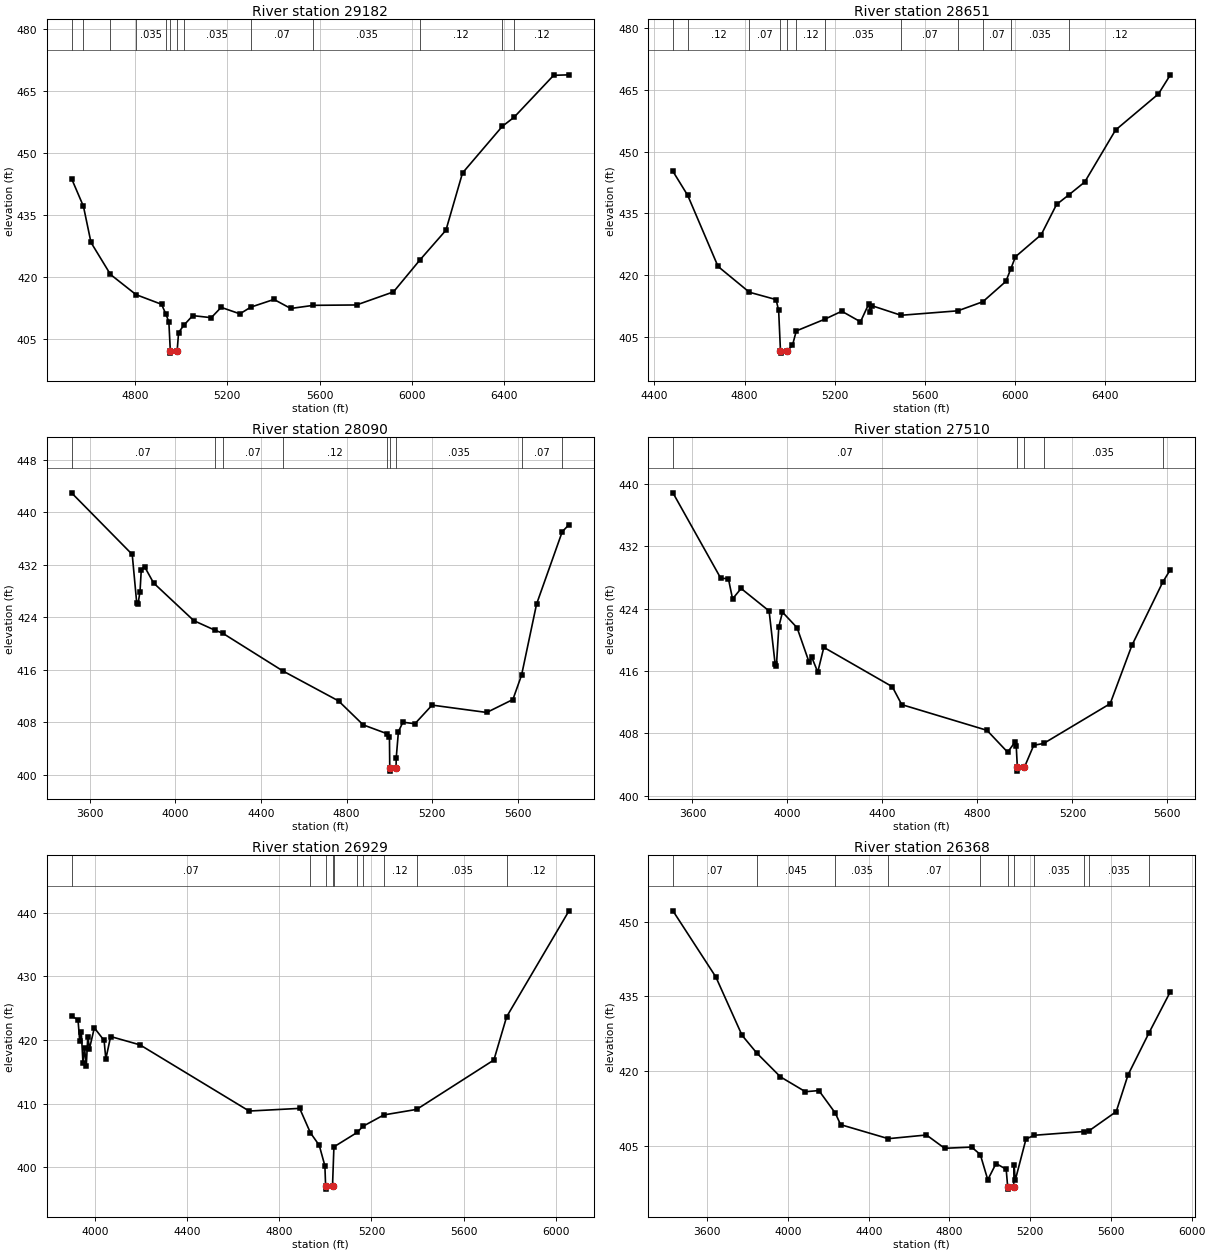
Type RM Length L Ch R = 1 ,29182   ,531,531,531
BEGIN DESCRIPTION:
NASH CREEK 44.0
END DESCRIPTION:
XS GIS Cut Line= 3
      2372824.99       13758525.        2372375.       13758375.
      2370925.01       13757525.
#Sta/Elev= 30
  4525.7  443.84  4577.3   437.1    4610  428.35  4694.4   420.6  4805.2  415.71
  4915.7  413.37  4934.9  410.93  4947.3   409.1  4953.7  402.04  4954.2  401.54
  4983.2  402.04  4989.5  406.53  5012.4  408.31  5050.8  410.63    5131  410.13
  5173.9  412.63    5255  411.06  5302.2  412.68  5402.7  414.55  5475.3  412.36
  5573.5  413.12  5760.3  413.21  5920.5  416.38  6035.4  424.14  6147.6  431.31
  6219.5  445.19  6391.9  456.49  6442.7  458.68  6614.3  468.85  6680.8  468.97
#Mann= 13 ,-1 , 0
  4525.7     .07       0  4577.3     .12       0  4694.4     .07       0
  4805.2    .035       0  4934.9     .07       0  4953.7     .05       0
  4983.2     .07       0  5012.4    .035       0  5302.2     .07       0
  5573.5    .035       0  6035.4     .12       0  6391.9     .07       0
  6442.7     .12       0
Bank Sta=4953.7,4983.2
XS Rating Curve= 0 ,0
Exp/Cntr=0.3,0.1

Type RM Length L Ch R = 1 ,28651   ,561,561,561
BEGIN DESCRIPTION:
NASH CREEK 43.0
END DESCRIPTION:
XS GIS Cut Line= 3
      2372874.98     13758474.96        2372625.       13758025.
      2371025.03     13757475.01
#Sta/Elev= 30
  4481.9  445.21  4547.7  439.37    4682  422.17  4821.1  415.92  4939.4  414.14
  4950.9   411.5    4959  401.67  4959.5  401.17  4988.5  401.67  5012.3  403.08
  5029.1  406.55    5156   409.4    5231  411.32  5313.9  408.76  5350.6  413.09
  5356.2  411.14  5366.7  412.62  5493.8  410.34  5745.9  411.42  5856.7  413.62
  5958.9  418.55  5980.7  421.58  6001.4  424.52  6115.8  429.88  6183.6  437.18
  6238.3  439.52  6308.6  442.62  6445.3  455.21  6635.7  463.97  6688.5  468.59
#Mann= 12 ,-1 , 0
  4481.9     .07       0  4547.7     .12       0  4821.1     .07       0
    4959     .05       0  4988.5     .07       0  5029.1     .12       0
    5156    .035       0  5493.8     .07       0  5745.9    .035       0
  5856.7     .07       0  5980.7    .035       0  6238.3     .12       0
Bank Sta=4959,4988.5
XS Rating Curve= 0 ,0
Exp/Cntr=0.3,0.1

Type RM Length L Ch R = 1 ,28090   ,580,580,580
BEGIN DESCRIPTION:
NASH CREEK 42.0
END DESCRIPTION:
XS GIS Cut Line= 3
      2373725.03     13758375.02        2372475.       13757575.
      2371674.98     13757324.99
#Sta/Elev= 30
  3515.9  442.99  3799.2   433.6  3820.4  426.14  3826.3  426.08  3835.6  427.95
  3841.5  431.27  3856.7  431.74    3899  429.25  4086.8  423.51  4184.3  422.07
  4221.9  421.59  4501.6  415.86  4762.4  411.28  4877.4  407.63  4987.3   406.3
    5000  405.76  5001.5  401.08    5002  400.58  5031.1  401.08  5031.5  402.53
  5041.9   406.6  5062.9  408.04  5118.9   407.8  5199.1  410.64  5454.2  409.52
  5576.3  411.49  5616.9  415.22  5686.8  426.03  5806.6  437.06  5838.2  438.14
#Mann= 9 ,-1 , 0
  3515.9     .07       0  4184.3     .12       0  4221.9     .07       0
  4501.6     .12       0  4987.3    .035       0  5001.5    .035       0
  5031.1    .035       0  5616.9     .07       0  5806.6    .035       0
Bank Sta=5001.5,5031.1
XS Rating Curve= 0 ,0
Exp/Cntr=0.3,0.1

Type RM Length L Ch R = 1 ,27510   ,581,581,581
BEGIN DESCRIPTION:
NASH CREEK 41.0
END DESCRIPTION:
XS GIS Cut Line= 3
      2373974.98     13757524.99        2372575.       13757025.
      2371974.96     13757125.01
#Sta/Elev= 30
  3517.7  438.86  3719.4  427.88  3751.3  427.85  3768.8  425.24  3804.9  426.58
  3922.8  423.69  3948.3  416.84  3953.6  416.67  3963.7  421.68  3979.1  423.54
  4040.6  421.54  4091.1  417.12  4102.2  417.76  4127.7  415.85  4153.2  419.02
  4441.5  413.97  4481.3  411.67  4840.2  408.37  4927.3  405.56  4958.1  406.85
  4963.4  406.41  4968.2  403.63  4968.7  403.13  4997.9  403.63  5037.2  406.45
  5078.8  406.68  5359.1  411.79  5450.4  419.26  5580.3  427.38  5612.6     429
#Mann= 5 ,-1 , 0
  3517.7     .07       0  4968.2     .05       0  4997.9     .07       0
  5078.8    .035       0  5580.3     .07       0
Bank Sta=4968.2,4997.9
XS Rating Curve= 0 ,0
Exp/Cntr=0.3,0.1

Type RM Length L Ch R = 1 ,26929   ,561,561,561
BEGIN DESCRIPTION:
NASH CREEK 40.0
END DESCRIPTION:
XS GIS Cut Line= 3
      2373625.02     13757325.02        2372825.       13756575.
      2372025.02     13755875.02
#Sta/Elev= 30
  3898.3  423.77  3926.4  423.17  3933.7  419.87  3940.6  421.28  3947.9  416.39
  3954.8  418.75  3962.1  415.84  3968.9  420.53  3976.2  418.63  3997.2  421.91
  4039.7  419.92  4047.1  417.01  4068.1  420.54  4195.5  419.23  4669.4  408.82
  4888.7  409.24  4935.3   405.4  4973.7  403.43  4998.2   400.2  5001.3  397.04
  5001.8  396.54  5031.3  397.04  5037.4  403.19  5138.1  405.45  5162.9  406.41
  5254.1  408.21  5396.7  409.08  5731.9  416.85  5787.1  423.64  6057.9  440.31
#Mann= 10 ,-1 , 0
  3898.3     .07       0  4935.3     .12       0  5001.3     .05       0
  5031.3     .12       0  5037.4     .07       0  5138.1     .12       0
  5162.9     .07       0  5254.1     .12       0  5396.7    .035       0
  5787.1     .12       0
Bank Sta=5001.3,5031.3
XS Rating Curve= 0 ,0
Exp/Cntr=0.3,0.1

Type RM Length L Ch R = 1 ,26368   ,805,805,805
BEGIN DESCRIPTION:
NASH CREEK 39.0
END DESCRIPTION:
XS GIS Cut Line= 3
      2374475.04     13755824.99        2372925.       13756075.
        2372125.       13755675.
#Sta/Elev= 30
    3430  452.19  3642.8   438.9  3772.4   427.2  3845.8  423.62  3962.8  418.85
  4086.4  415.87  4153.3   416.1  4234.6  411.57  4260.6  409.26  4497.1  406.44
  4686.1  407.18  4776.2  404.51  4909.9  404.75  4952.9  403.25  4989.9  398.19
  5030.8  401.45  5081.1   400.3  5088.4  396.81  5088.9  396.31  5118.5  396.81
  5120.3  401.25  5125.8  398.06    5179  406.34  5218.9  407.12  5466.8  407.88
  5490.8     408  5626.2  411.87  5684.9  419.26  5787.9  427.63  5894.5  435.96
#Mann= 11 ,-1 , 0
    3430     .07       0  3845.8    .045       0  4234.6    .035       0
  4497.1     .07       0  4952.9     .12       0  5088.4     .05       0
  5118.5     .12       0  5218.9    .035       0  5466.8     .07       0
  5490.8    .035       0  5787.9     .12       0
Bank Sta=5088.4,5118.5
XS Rating Curve= 0 ,0
Exp/Cntr=0.3,0.1

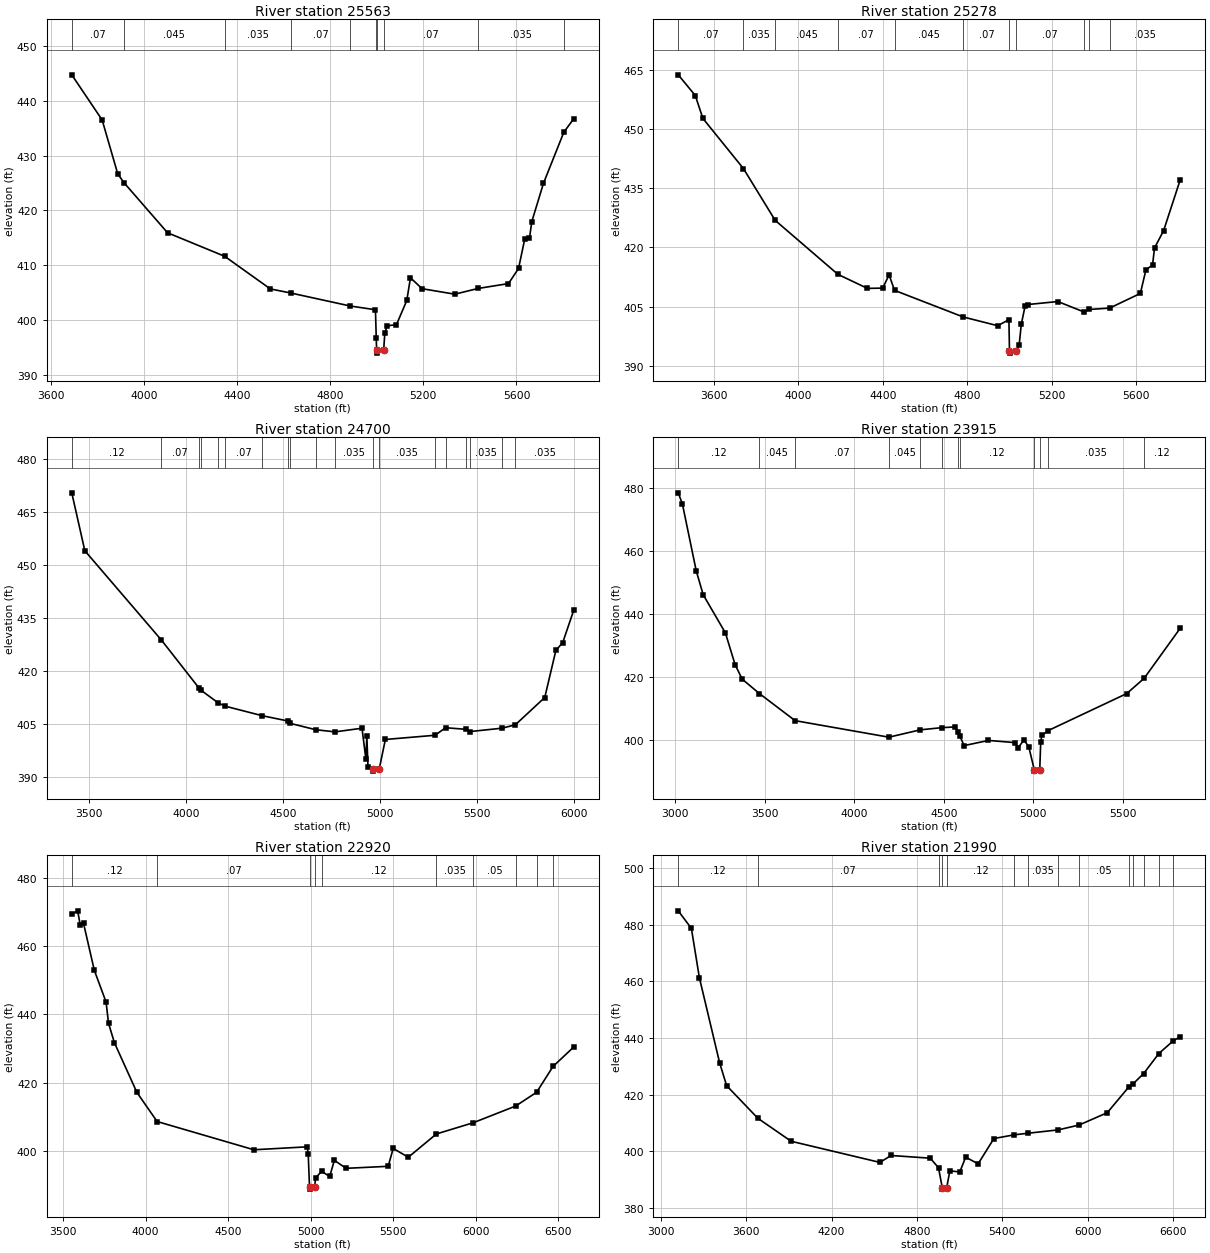
Type RM Length L Ch R = 1 ,25563   ,285,285,285
BEGIN DESCRIPTION:
NASH CREEK 38.0
END DESCRIPTION:
XS GIS Cut Line= 3
      2374325.02       13755775.       2373158.3     13755686.77
      2372174.99       13755625.
#Sta/Elev= 30
  3691.1  444.72  3821.5  436.49  3888.4  426.66  3915.6  425.03  4102.3  415.91
  4347.1  411.63  4543.6  405.67  4630.8  404.93  4885.7  402.56  4994.7  401.87
  4998.2  396.68  4999.7  394.46  5000.2  393.96  5029.9  394.46  5034.8  397.55
  5044.8  398.94  5084.9  399.15  5129.3  403.56    5145   407.7  5195.1  405.71
  5335.4  404.71  5435.7  405.76  5565.8  406.64    5609   409.4    5636  414.85
    5656  414.97    5666  417.96  5716.1  424.95  5803.4  434.25  5846.4  436.74
#Mann= 10 ,-1 , 0
  3691.1     .07       0  3915.6    .045       0  4347.1    .035       0
  4630.8     .07       0  4885.7     .12       0  4998.2     .07       0
  4999.7     .05       0  5029.9     .07       0  5435.7    .035       0
  5803.4     .12       0
Bank Sta=4999.7,5029.9
XS Rating Curve= 0 ,0
Exp/Cntr=0.3,0.1

Type RM Length L Ch R = 1 ,25278   ,578,578,578
BEGIN DESCRIPTION:
NASH CREEK 37.0
END DESCRIPTION:
XS GIS Cut Line= 3
        2374575.       13755625.        2373025.       13755425.
      2372224.99       13755575.
#Sta/Elev= 30
    3432  463.84  3512.7  458.59  3548.6  452.78  3740.7  440.03    3891  426.88
  4187.7  413.18  4327.5  409.61    4400  409.68  4430.2  413.04  4455.9  409.11
  4781.2  402.35  4944.4  400.13  4997.4  401.67  5000.1  393.67  5000.6  393.17
  5030.4  393.67  5045.7  395.12  5055.9  400.45  5073.7  405.06  5086.4  405.51
  5228.9  406.27  5352.1  403.64  5377.1  404.25  5474.2  404.61  5619.7  408.33
    5646  414.32  5677.4  415.57  5686.7  419.86  5729.9   424.3  5808.8  437.26
#Mann= 11 ,-1 , 0
    3432     .07       0  3740.7    .035       0    3891    .045       0
  4187.7     .07       0  4455.9    .045       0  4781.2     .07       0
  5000.1     .05       0  5030.4     .07       0  5352.1    .035       0
  5377.1     .07       0  5474.2    .035       0
Bank Sta=5000.1,5030.4
XS Rating Curve= 0 ,0
Exp/Cntr=0.3,0.1

Type RM Length L Ch R = 1 ,24700   ,785,785,785
BEGIN DESCRIPTION:
NASH CREEK 36.0
END DESCRIPTION:
XS GIS Cut Line= 3
      2374574.96     13755274.99        2373025.       13754925.
      2372224.99     13755525.01
#Sta/Elev= 30
  3410.8  470.47  3478.1  454.06  3873.4  428.73  4066.3   415.2  4076.6  414.56
  4166.6  410.93  4202.2  410.02  4393.7  407.31  4524.2  405.84  4536.7  405.16
  4668.1  403.36  4768.4  402.74  4907.5  403.78  4927.3  395.04  4932.4  401.53
  4938.3  392.66  4965.6  392.12  4966.1  391.62  4995.9  392.12  5027.9  400.59
  5284.1  401.78  5338.6  403.92    5442  403.47  5464.4  402.83  5630.3  403.79
  5698.4  404.76  5849.8  412.48  5907.1  425.82  5942.5  428.04  5999.8  437.31
#Mann= 19 ,-1 , 0
  3410.8     .12       0  3873.4     .07       0  4066.3    .045       0
  4076.6     .07       0  4166.6    .045       0  4202.2     .07       0
  4393.7    .045       0  4524.2     .07       0  4536.7    .045       0
  4668.1     .07       0  4768.4    .035       0  4965.6    .035       0
  4995.9    .035       0  5284.1     .07       0  5338.6    .035       0
    5442     .07       0  5464.4    .035       0  5630.3     .07       0
  5698.4    .035       0
Bank Sta=4965.6,4995.9
XS Rating Curve= 0 ,0
Exp/Cntr=0.3,0.1

Type RM Length L Ch R = 1 ,23915   ,995,995,995
BEGIN DESCRIPTION:
B19757
END DESCRIPTION:
XS GIS Cut Line= 3
      2374477.84     13754947.82      2372630.48     13754409.45
      2371785.99     13754166.66
#Sta/Elev= 30
    3018  478.34  3041.3  474.79  3118.7  453.55  3157.4  446.03  3281.4  433.92
  3335.3  423.89  3375.1  419.27  3470.9  414.72  3670.5  406.12    4194  400.88
  4369.4  403.21    4488  403.89  4562.5  404.13  4582.4  402.61  4589.7  401.31
    4614  398.21    4750  399.85  4895.8  399.17  4916.7   397.6  4947.9  400.02
  4975.2  397.77  5005.3  390.62  5005.8  390.12  5036.2  390.62  5041.6   399.3
  5047.8  401.42  5082.3  402.95  5522.3  414.72  5619.3  419.56  5820.9  435.45
#Mann= 12 ,-1 , 0
    3018     .12       0  3470.9    .045       0  3670.5     .07       0
    4194    .045       0  4369.4     .07       0    4488    .045       0
  4582.4     .07       0  4589.7     .12       0  5005.3     .05       0
  5036.2     .12       0  5082.3    .035       0  5619.3     .12       0
Bank Sta=5005.3,5036.2
XS Rating Curve= 0 ,0
Exp/Cntr=0.3,0.1

Type RM Length L Ch R = 1 ,22920   ,930,930,930
BEGIN DESCRIPTION:
B19756
END DESCRIPTION:
XS GIS Cut Line= 3
      2374509.49     13754810.58      2373211.08     13753881.63
      2371786.01     13753638.84
#Sta/Elev= 30
  3552.6  469.38  3588.4  470.33  3603.2  466.32    3624  466.63  3689.2  452.89
  3760.4   443.6  3775.2  437.41  3810.8  431.68  3947.2   417.1  4069.7  408.56
  4656.1  400.28  4979.2  401.14  4985.3  399.01  4993.2  389.24  4993.7  388.74
  5024.1  389.24  5029.5     392    5066  393.95  5115.5  392.46  5143.6  397.18
  5214.7  394.84  5469.7  395.43  5500.2  400.68  5591.5  398.08  5761.7  404.91
    5986  408.22  6241.8  413.09  6369.1  417.13  6468.5   424.7  6594.7  430.44
#Mann= 10 ,-1 , 0
  3552.6     .12       0  4069.7     .07       0  4993.2     .05       0
  5024.1     .07       0    5066     .12       0  5761.7    .035       0
    5986     .05       0  6241.8     .07       0  6369.1     .05       0
  6468.5     .12       0
Bank Sta=4993.2,5024.1
XS Rating Curve= 0 ,0
Exp/Cntr=0.3,0.1

Type RM Length L Ch R = 1 ,21990   ,512,512,512
BEGIN DESCRIPTION:
NASH CREEK 33.0
END DESCRIPTION:
XS GIS Cut Line= 3
      2374524.99     13754724.99        2373275.       13753325.
      2371674.97     13752924.99
#Sta/Elev= 30
  3123.4  484.94  3215.8  478.74  3271.8  461.36  3413.9  431.33  3463.2  423.24
  3683.1   411.7  3916.4  403.61    4540  396.15  4617.8  398.59  4893.6  397.64
  4951.4  394.25  4977.6  387.22  4978.1  386.72  5008.6  387.22  5031.1  393.19
  5100.7  392.77    5142  397.99  5229.6  395.65  5340.4  404.58  5482.7  405.88
  5580.5  406.45  5792.4  407.63  5939.1  409.35  6136.7   413.7  6285.9  422.67
  6319.7  423.97  6392.1  427.52  6498.9  434.58  6599.6  439.05  6649.5  440.52
#Mann= 14 ,-1 , 0
  3123.4     .12       0  3683.1     .07       0  4951.4     .12       0
  4977.6     .05       0  5008.6     .12       0  5482.7     .07       0
  5580.5    .035       0  5792.4     .07       0  5939.1     .05       0
  6285.9     .07       0  6319.7     .05       0  6392.1     .12       0
  6498.9     .05       0  6599.6     .12       0
Bank Sta=4977.6,5008.6
XS Rating Curve= 0 ,0
Exp/Cntr=0.3,0.1

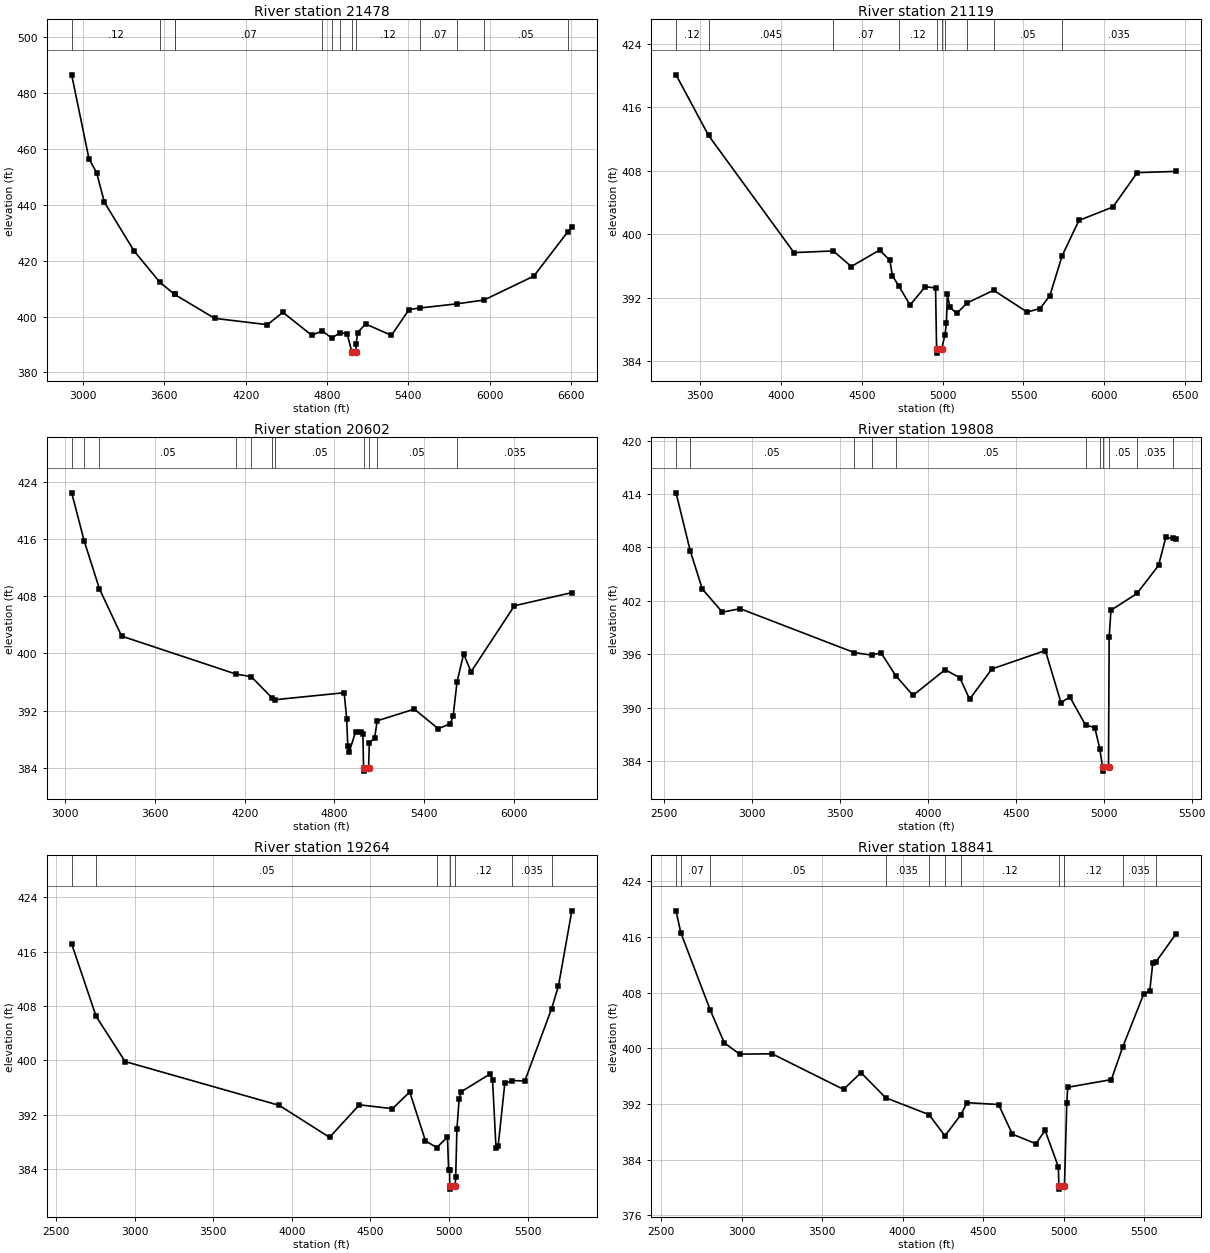
Type RM Length L Ch R = 1 ,21478   ,359,359,359
BEGIN DESCRIPTION:
NASH CREEK 32.0
END DESCRIPTION:
XS GIS Cut Line= 3
      2374875.03     13754425.03        2373475.       13752875.
      2371874.98       13752925.
#Sta/Elev= 30
  2916.2   486.6  3043.7  456.52  3100.4  451.52  3157.2  440.99  3376.2   423.5
  3566.8  412.27    3675  407.93  3675.5  407.92    3971  399.34  4360.4  397.07
    4474   401.5  4686.2  393.31  4765.5   394.8  4833.9  392.32  4897.8  394.16
  4948.5  393.83  4982.3  387.38  4982.8  386.88  5013.4  387.38  5014.9   390.1
  5024.9  394.25  5084.9  397.33    5275  393.24  5405.1  402.51  5489.3  403.07
  5759.9  404.56  5957.2   405.9  6325.5  414.48  6575.5  430.35  6605.7  431.94
#Mann= 13 ,-1 , 0
  2916.2     .12       0  3566.8     .07       0    3675     .12       0
  3675.5     .07       0  4765.5     .12       0  4833.9     .07       0
  4897.8     .12       0  4982.3     .05       0  5013.4     .12       0
  5489.3     .07       0  5759.9    .035       0  5957.2     .05       0
  6575.5     .12       0
Bank Sta=4982.3,5013.4
XS Rating Curve= 0 ,0
Exp/Cntr=0.3,0.1

Type RM Length L Ch R = 1 ,21119   ,517,517,517
BEGIN DESCRIPTION:
B19755
END DESCRIPTION:
XS GIS Cut Line= 3
      2375142.86     13753533.25      2373633.34      13752583.2
      2372324.37     13752498.75
#Sta/Elev= 30
  3349.7  420.09  3550.8  412.46  4079.7   397.7  4322.8  397.91  4434.2  395.95
  4609.6  398.02  4673.2  396.72  4688.5  394.79  4730.1  393.44    4798   391.1
  4892.2  393.41  4955.8  393.24  4962.2  385.54  4962.7  385.04  4993.3  385.54
  5014.3  387.37  5022.9  388.85  5028.8   392.5  5044.1  390.84  5086.5  390.05
    5151  391.35  5314.9  392.96  5522.5  390.21  5602.6  390.66  5662.7  392.25
  5739.1   397.3  5843.1  401.75  6053.6  403.45  6203.9  407.77    6445  407.93
#Mann= 10 ,-1 , 0
  3349.7     .12       0  3550.8    .045       0  4322.8     .07       0
  4730.1     .12       0  4962.2     .05       0  4993.3     .12       0
  5014.3    .035       0    5151     .12       0  5314.9     .05       0
  5739.1    .035       0
Bank Sta=4962.2,4993.3
XS Rating Curve= 0 ,0
Exp/Cntr=0.3,0.1

Type RM Length L Ch R = 1 ,20602   ,794,794,794
BEGIN DESCRIPTION:
B19754
END DESCRIPTION:
XS GIS Cut Line= 4
      2375491.28      13751854.8      2373686.12     13752255.95
      2373443.32     13752456.52      2372261.03     13752435.41
#Sta/Elev= 30
  3042.2  422.44  3126.8  415.66  3228.3  409.01  3376.4  402.43    4142  397.12
  4243.5  396.77  4384.4  393.76  4405.7  393.55  4865.5  394.52  4882.3   390.9
  4889.4  387.14  4898.5  386.22  4941.6  389.03  4976.7  389.08    4991  388.74
    4995  384.07  4995.6  383.57  5028.8  384.07  5034.1  387.51  5069.2  388.18
  5086.4   390.6  5334.7  392.23  5494.7   389.5  5575.6  390.18  5594.7  391.28
  5620.9  396.05  5664.7  399.92  5714.7  397.45  6004.8  406.67  6388.8   408.5
#Mann= 11 ,-1 , 0
  3042.2     .07       0  3126.8     .12       0  3228.3     .05       0
    4142    .035       0  4243.5     .05       0  4384.4     .07       0
  4405.7     .05       0    4995     .05       0  5028.8     .05       0
  5086.4     .05       0  5620.9    .035       0
Bank Sta=4995,5028.8
XS Rating Curve= 0 ,0
Exp/Cntr=0.3,0.1

Type RM Length L Ch R = 1 ,19808   ,544,544,544
BEGIN DESCRIPTION:
NASH CREEK 31.0
END DESCRIPTION:
XS GIS Cut Line= 3
      2375324.99       13751725.        2372925.       13752125.
        2372525.       13752225.
#Sta/Elev= 30
  2566.7  414.13  2647.4  407.62  2716.2  403.32  2830.3  400.72  2931.7  401.11
  3580.4  396.18  3680.7  395.89  3732.6  396.16  3816.4  393.59    3915  391.37
  4097.5  394.26  4181.2  393.35  4236.9  390.94  4363.6  394.34  4667.8  396.41
  4756.5  390.56  4807.2  391.19  4896.2  388.04  4949.1  387.75  4976.9   385.4
  4993.2  383.36  4993.9  382.86    5027  383.36  5030.7  397.89    5041  400.94
    5189  402.82  5311.6  405.97  5352.8  409.12  5393.4  409.01  5412.1  408.93
#Mann= 11 ,-1 , 0
  2566.7     .07       0  2647.4     .05       0  3580.4    .035       0
  3680.7     .07       0  3816.4     .05       0  4896.2     .12       0
  4976.9     .05       0  4993.2     .05       0    5027     .05       0
    5189    .035       0  5393.4     .07       0
Bank Sta=4993.2,5027
XS Rating Curve= 0 ,0
Exp/Cntr=0.3,0.1

Type RM Length L Ch R = 1 ,19264   ,423,423,423
BEGIN DESCRIPTION:
NASH CREEK 30.0
END DESCRIPTION:
XS GIS Cut Line= 3
        2375375.       13751625.        2372975.       13751625.
      2372375.02     13751125.02
#Sta/Elev= 30
  2600.4  417.14  2755.7   406.5  2940.4  399.84  3920.4   393.4  4240.4   388.7
  4430.4  393.48  4640.4  392.91  4750.4  395.37  4850.4  388.19  4921.8  387.19
  4990.4  388.73  4997.9  383.86  5003.7  383.86  5004.9  381.58  5005.6  381.08
  5038.8  381.58  5042.7  382.81  5050.5  389.91  5064.8  394.39  5078.5  395.41
  5262.7  398.04    5277  397.18  5299.1  387.14  5312.8  387.42  5355.1  396.63
  5402.2  397.04  5482.7     397  5652.4   407.6  5696.2  410.95  5781.4  422.01
#Mann= 7 ,-1 , 0
  2600.4     .07       0  2755.7     .05       0  4921.8     .12       0
  5004.9     .05       0  5038.8     .12       0  5402.2    .035       0
  5652.4     .07       0
Bank Sta=5004.9,5038.8
XS Rating Curve= 0 ,0
Exp/Cntr=0.3,0.1

Type RM Length L Ch R = 1 ,18841   ,574,574,574
BEGIN DESCRIPTION:
B19753
END DESCRIPTION:
XS GIS Cut Line= 3
      2375406.78     13751548.67      2373137.19     13751253.09
      2372356.01      13751010.3
#Sta/Elev= 30
  2593.1  419.78  2622.7  416.64  2805.4  405.54  2892.5  400.81  2988.2  399.18
  3189.9  399.23  3633.6  394.11  3741.9  396.52  3895.4  392.91  4164.4  390.49
  4263.4  387.43  4362.3  390.47    4400  392.21  4596.4  391.94  4682.4  387.68
  4828.5   386.3  4885.6  388.22  4967.9  382.99    4971  380.28  4971.8  379.78
  5005.9  380.28  5020.3  392.23  5026.3  394.42  5297.2  395.52    5367  400.16
  5497.7   407.8  5535.5  408.24  5554.3  412.27  5571.6  412.36  5699.9   416.5
#Mann= 11 ,-1 , 0
  2593.1     .12       0  2622.7     .07       0  2805.4     .05       0
  3895.4    .035       0  4164.4     .12       0  4263.4     .05       0
  4362.3     .12       0    4971     .05       0  5005.9     .12       0
    5367    .035       0  5571.6     .12       0
Bank Sta=4971,5005.9
XS Rating Curve= 0 ,0
Exp/Cntr=0.3,0.1

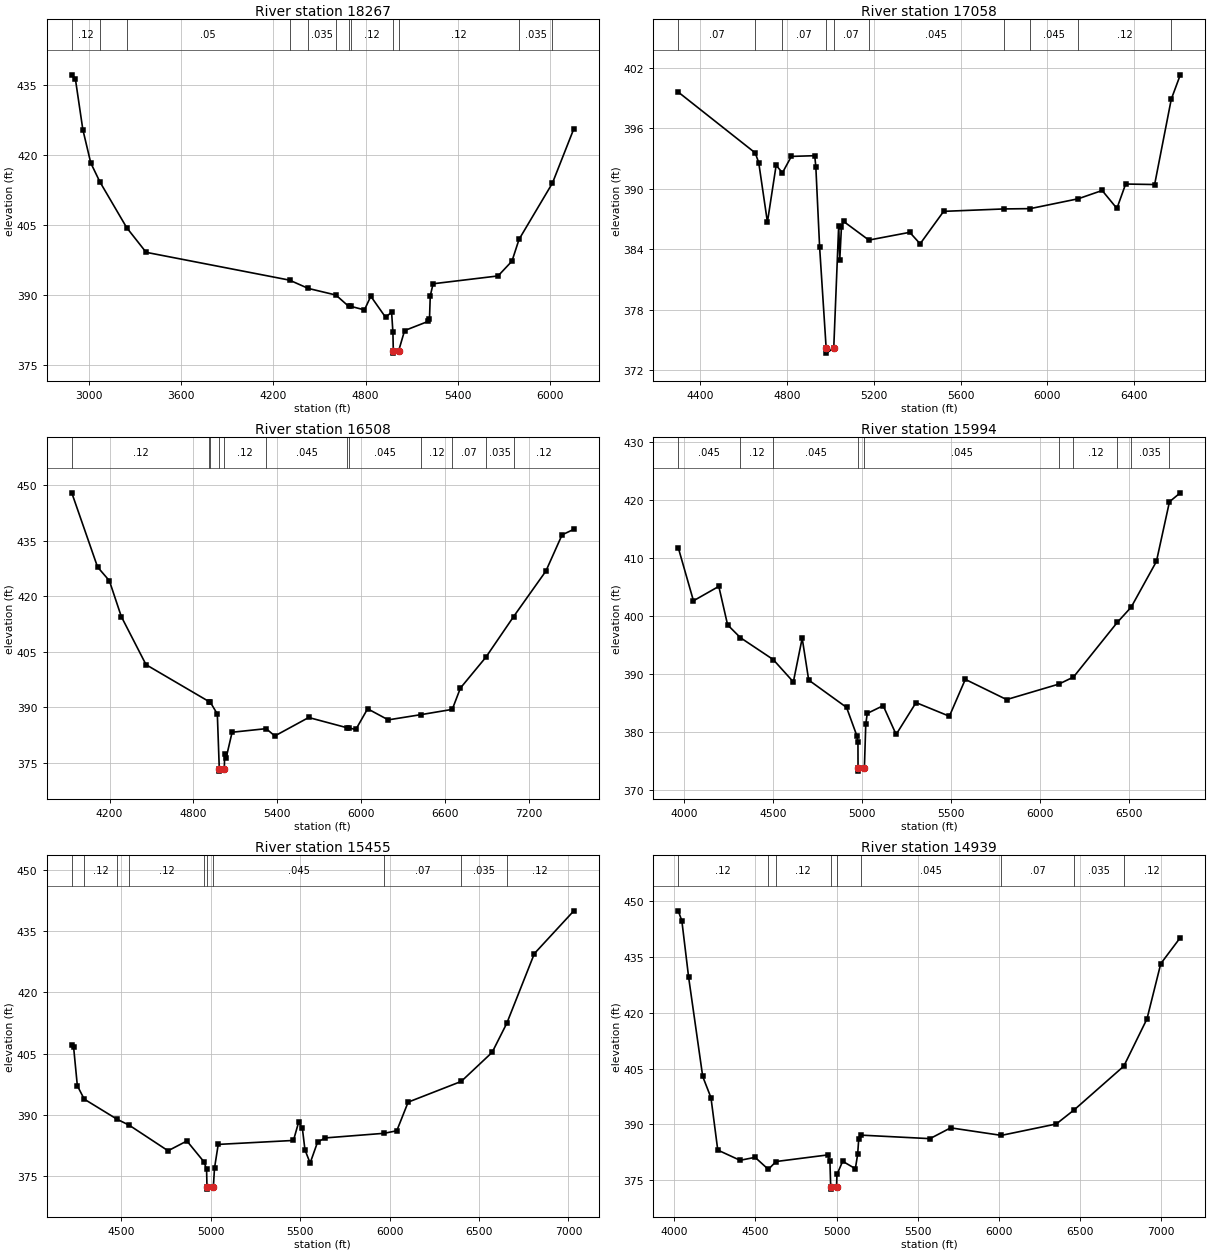
Type RM Length L Ch R = 1 ,18267   ,1209,1209,1209
BEGIN DESCRIPTION:
NASH CREEK 29.0
END DESCRIPTION:
XS GIS Cut Line= 3
      2375524.99       13751525.      2373506.66     13751020.85
      2372324.97       13750875.
#Sta/Elev= 30
  2886.2  437.25  2909.4  436.44  2958.3   425.5  3009.9  418.34  3069.2  414.28
  3244.3  404.43  3370.6  399.15  4304.7  393.18    4427   391.4    4607  389.98
  4689.9  387.56  4707.7  387.52    4793  386.79  4834.3  389.72  4930.5  385.21
  4969.9   386.3  4978.4  381.98    4981  378.01  4981.7  377.51  5015.9  378.01
  5054.5  382.35    5210  384.35  5216.7   384.8  5221.8  389.81  5240.3   392.4
  5663.5  394.08  5754.1  397.26  5800.1  401.93  6017.6     414  6157.2  425.68
#Mann= 12 ,-1 , 0
  2886.2     .12       0  3069.2     .07       0  3244.3     .05       0
  4304.7     .07       0    4427    .035       0    4607     .12       0
  4689.9     .07       0  4707.7     .12       0    4981     .05       0
  5015.9     .12       0  5800.1    .035       0  6017.6     .12       0
Bank Sta=4981,5015.9
XS Rating Curve= 0 ,0
Exp/Cntr=0.3,0.1

Type RM Length L Ch R = 1 ,17058   ,550,550,550
BEGIN DESCRIPTION:
NASH CREEK 28.0
END DESCRIPTION:
XS GIS Cut Line= 3
      2374975.04       13750375.        2374275.       13750325.
      2372674.98       13750525.
#Sta/Elev= 30
  4298.2  399.61  4652.9  393.58  4669.2  392.62  4709.3  386.71  4749.4  392.34
  4778.6  391.61  4819.6  393.23  4927.3   393.3  4932.4  392.22  4949.9  384.23
    4980  374.22  4980.8  373.72    5015  374.22  5037.8  386.37  5042.9     383
  5050.4   386.2  5060.5  386.78  5176.8  384.93  5365.3   385.7  5413.2  384.56
  5521.6  387.78  5799.7  388.02  5920.6  388.05  6142.2  389.03  6252.2  389.85
  6320.2  388.07  6360.5  390.49  6494.1  390.44  6570.8   398.9  6612.5  401.32
#Mann= 10 ,-1 , 0
  4298.2     .07       0  4652.9     .12       0  4778.6     .07       0
    4980     .05       0    5015     .07       0  5176.8    .045       0
  5799.7     .12       0  5920.6    .045       0  6142.2     .12       0
  6570.8     .07       0
Bank Sta=4980,5015
XS Rating Curve= 0 ,0
Exp/Cntr=0.3,0.1

Type RM Length L Ch R = 1 ,16508   ,514,514,514
BEGIN DESCRIPTION:
NASH CREEK 27.0
END DESCRIPTION:
XS GIS Cut Line= 3
      2375224.97     13749175.03        2374425.       13749875.
      2372024.99       13750675.
#Sta/Elev= 30
  3929.9  447.89  4114.5  427.87  4198.9  424.17  4284.4   414.5  4461.4  401.52
    4915   391.5  4922.4  391.32  4971.5  388.21  4985.7   373.3  4986.5   372.8
  5021.2   373.3  5024.5  377.51    5035  376.44  5077.2  383.29  5320.8  384.26
  5382.9  382.29  5625.3  387.27  5902.2  384.48    5911  384.46  5962.6  384.04
    6047  389.62  6194.5  386.63    6432  388.06  6652.6  389.46    6711  395.21
  6893.3  403.54  7092.1  414.52  7322.4  426.76  7438.4  436.55  7522.7  438.05
#Mann= 12 ,-1 , 0
  3929.9     .12       0    4915    .045       0  4922.4     .12       0
  4985.7     .05       0  5021.2     .12       0  5320.8    .045       0
  5902.2     .12       0    5911    .045       0    6432     .12       0
  6652.6     .07       0  6893.3    .035       0  7092.1     .12       0
Bank Sta=4985.7,5021.2
XS Rating Curve= 0 ,0
Exp/Cntr=0.3,0.1

Type RM Length L Ch R = 1 ,15994   ,539,539,539
BEGIN DESCRIPTION:
NASH CREEK 26.0
END DESCRIPTION:
XS GIS Cut Line= 3
      2374775.03     13749024.97        2373975.       13749675.
      2372374.98     13750475.01
#Sta/Elev= 30
  3968.7  411.77  4054.2  402.61  4196.5  405.09    4246  398.46  4318.3  396.25
  4502.1  392.49  4615.2  388.64  4664.8  396.17  4701.4  388.96    4914  384.25
  4971.5   379.4    4978  378.21  4978.5  373.78  4979.3  373.28  5014.1  373.78
  5021.9  381.36  5030.3  383.22  5119.7  384.55  5192.4  379.59  5304.2  385.08
  5491.5  382.73  5580.9  389.08  5812.9   385.6  6105.7  388.26  6188.5  389.48
  6434.7   398.9  6512.4  401.51  6654.2  409.38  6727.5  419.66  6788.4   421.2
#Mann= 10 ,-1 , 0
  3968.7    .045       0  4318.3     .12       0  4502.1    .045       0
  4978.5    .045       0  5014.1    .045       0  6105.7     .07       0
  6188.5     .12       0  6434.7     .07       0  6512.4    .035       0
  6727.5     .12       0
Bank Sta=4978.5,5014.1
XS Rating Curve= 0 ,0
Exp/Cntr=0.3,0.1

Type RM Length L Ch R = 1 ,15455   ,516,516,516
BEGIN DESCRIPTION:
NASH CREEK 25.0
END DESCRIPTION:
XS GIS Cut Line= 3
      2374475.02       13749025.        2373725.       13749225.
      2372125.02     13750474.99
#Sta/Elev= 30
  4223.5  407.19  4233.9  406.55  4254.6  397.16    4293  393.88  4476.5  388.96
  4545.4  387.47  4761.7  381.23  4867.1  383.63  4962.3  378.53  4977.1  376.71
  4979.3  372.34  4980.1  371.84  5014.9  372.34  5021.4  376.99  5042.2  382.79
  5462.8  383.76  5491.7  388.24  5512.5  386.73    5527  381.47  5555.9  378.21
  5597.6  383.37  5640.9  384.38  5970.1  385.51  6040.3  386.13  6103.8  393.14
  6400.5  398.21  6573.4  405.33  6655.2  412.44  6809.4  429.51  7030.1  439.98
#Mann= 10 ,-1 , 0
  4223.5    .045       0    4293     .12       0  4476.5    .045       0
  4545.4     .12       0  4962.3    .045       0  4979.3    .045       0
  5014.9    .045       0  5970.1     .07       0  6400.5    .035       0
  6655.2     .12       0
Bank Sta=4979.3,5014.9
XS Rating Curve= 0 ,0
Exp/Cntr=0.3,0.1

Type RM Length L Ch R = 1 ,14939   ,1107,1107,1107
BEGIN DESCRIPTION:
NASH CREEK 24.0
END DESCRIPTION:
XS GIS Cut Line= 3
      2374174.99     13747975.02        2373625.       13748775.
        2372175.       13750325.
#Sta/Elev= 30
  4024.6  447.46  4046.9  444.75  4088.8  429.52  4175.4  402.86  4226.2  397.16
  4268.1  383.05  4405.5  380.29  4498.1  381.09  4579.7  377.85  4627.1  379.96
    4946  381.74    4959  380.15    4964  373.03  4964.9  372.53  4999.7  373.03
  5002.5  376.47  5037.7  380.03  5115.8  378.03    5130   381.9  5136.8  386.16
  5150.1  387.07  5575.5  386.12    5703  389.03  6015.2     387  6353.7  390.07
  6465.6  393.93  6769.8  405.64  6912.5  418.36  6997.5  433.23  7117.9  440.25
#Mann= 9 ,-1 , 0
  4024.6     .12       0  4579.7    .045       0  4627.1     .12       0
    4964     .05       0  4999.7     .12       0  5150.1    .045       0
  6015.2     .07       0  6465.6    .035       0  6769.8     .12       0
Bank Sta=4964,4999.7
XS Rating Curve= 0 ,0
Exp/Cntr=0.3,0.1