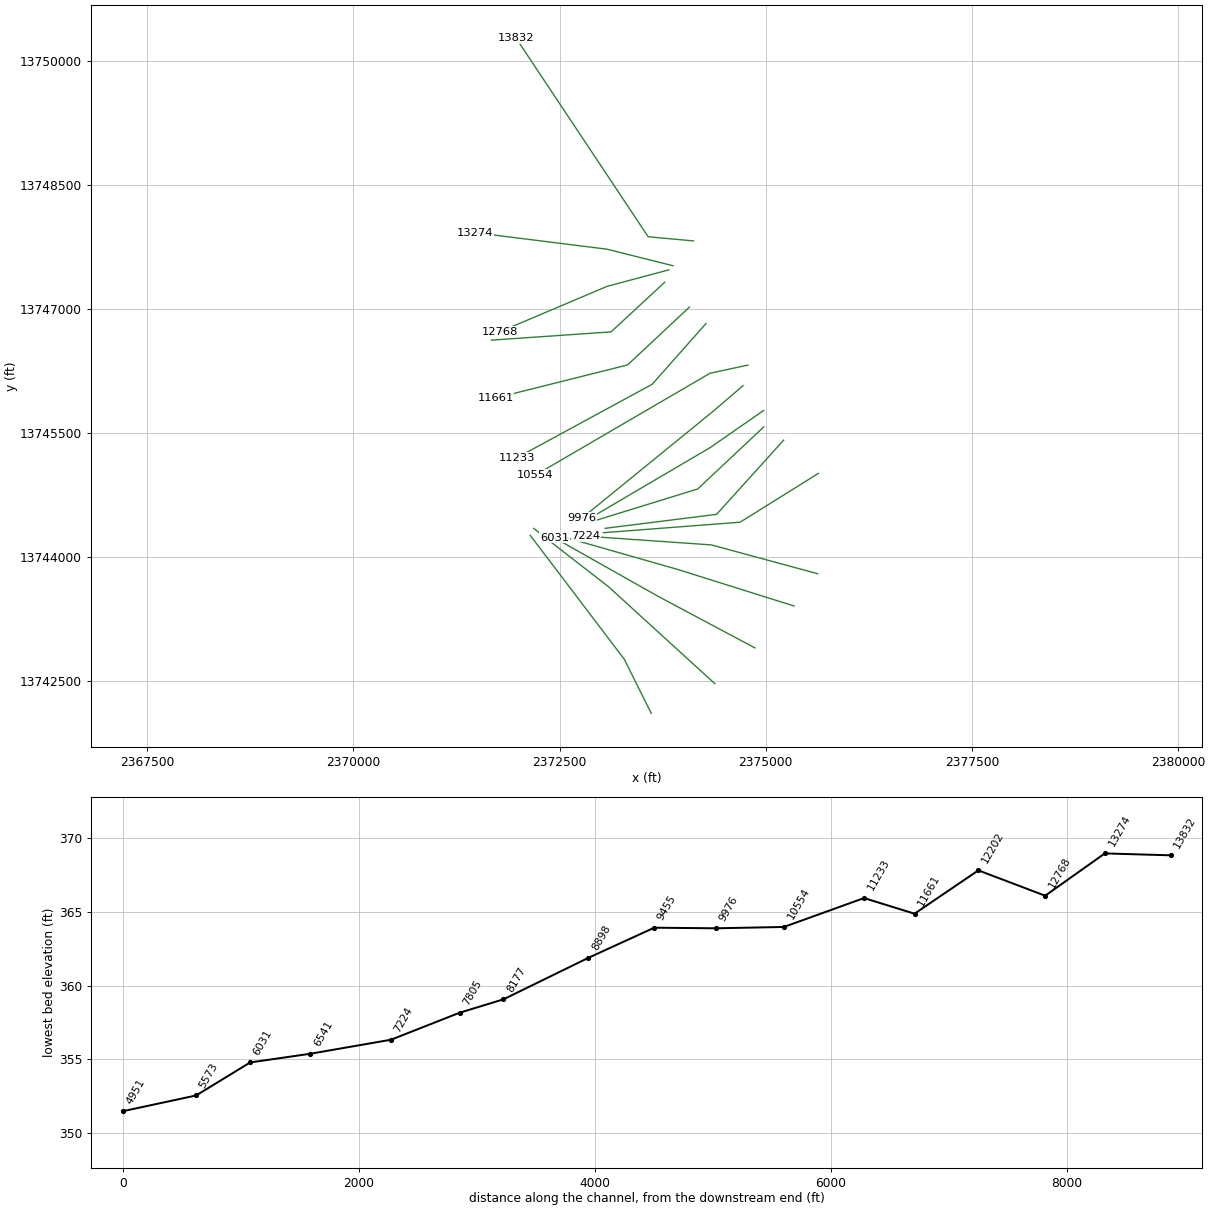
HEC-RAS study NASH CREEK.prj: NASH CREEK Base Level Engineering

--- NASH CREEK.g01 (geometry) --- (continued)

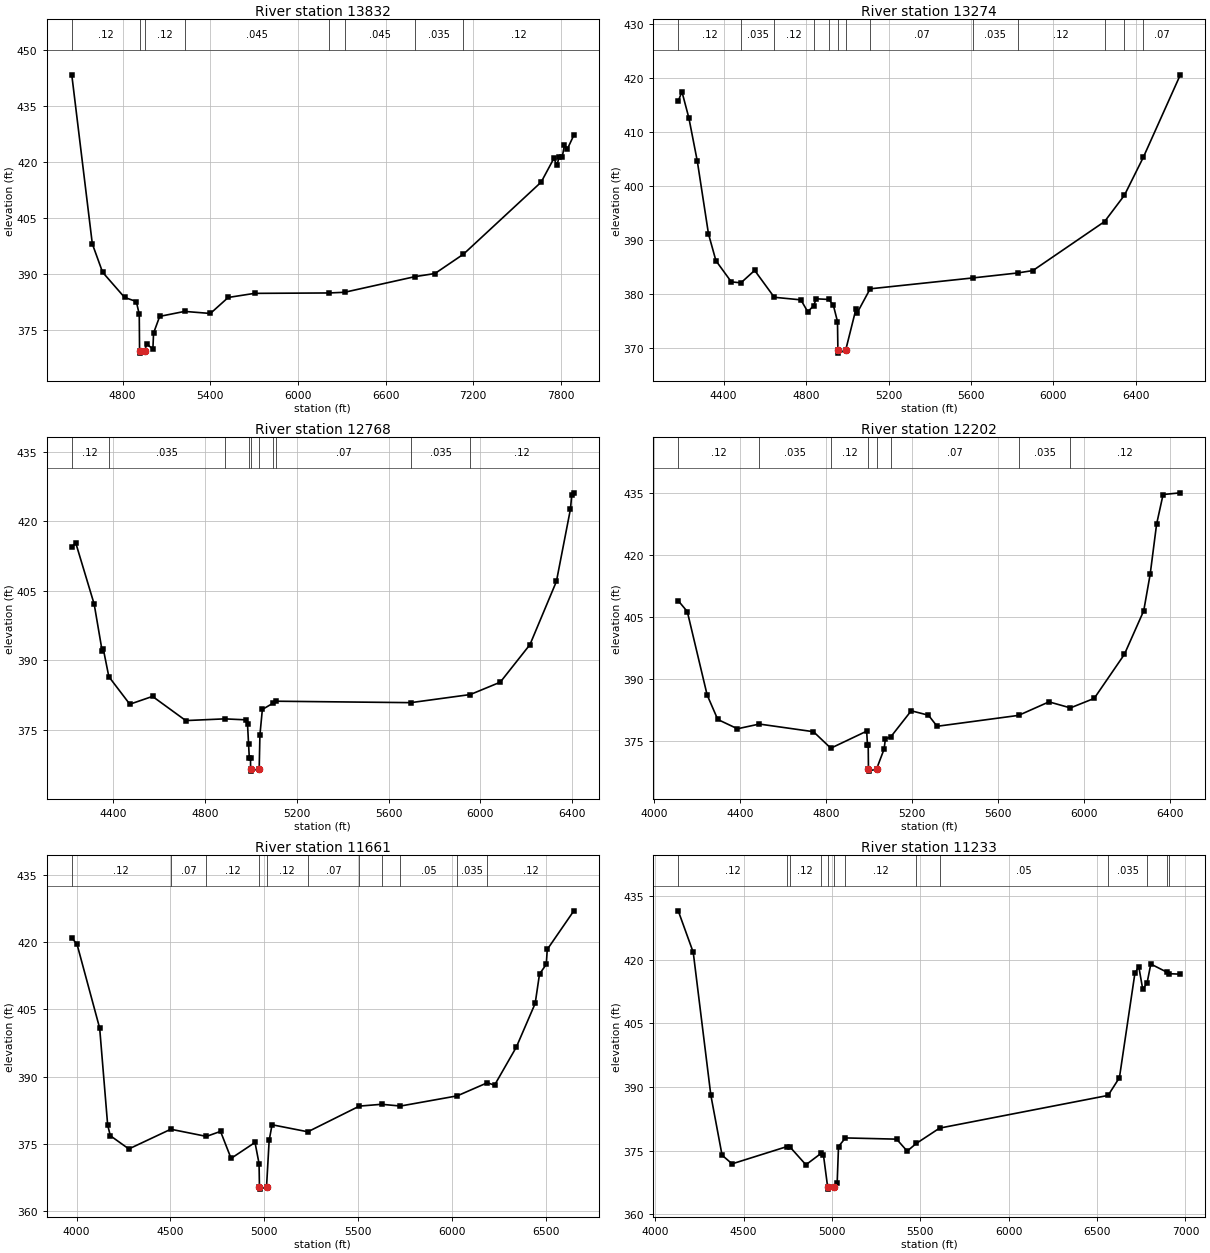
Type RM Length L Ch R = 1 ,13832   ,558,558,558
BEGIN DESCRIPTION:
NASH CREEK 23.0
END DESCRIPTION:
XS GIS Cut Line= 3
      2374125.03       13747825.        2373575.       13747875.
      2371975.02     13750274.96
#Sta/Elev= 30
  4451.8  443.35  4592.4  398.11  4662.7   390.5  4813.3  383.75  4893.6  382.66
  4913.7  379.23  4915.9  369.34  4916.7  368.84  4951.8  369.34  4963.9  371.32
  5007.1  369.92  5011.6   374.2  5053.7  378.68  5224.4  380.01  5400.7  379.46
  5522.4  383.74  5702.7  384.84  6214.2  384.95    6319  385.13  6801.1  389.32
  6937.6  390.15  7133.1  395.34  7664.7  414.62  7751.8  420.97  7772.9  419.12
  7787.9  421.45  7808.9  421.36  7823.9  424.44    7845  423.57  7888.5  427.19
#Mann= 8 ,-1 , 0
  4451.8     .12       0  4915.9     .05       0  4951.8     .12       0
  5224.4    .045       0  6214.2     .12       0    6319    .045       0
  6801.1    .035       0  7133.1     .12       0
Bank Sta=4915.9,4951.8
XS Rating Curve= 0 ,0
Exp/Cntr=0.3,0.1

Type RM Length L Ch R = 1 ,13274   ,506,506,506
BEGIN DESCRIPTION:
NASH CREEK 22.0
END DESCRIPTION:
XS GIS Cut Line= 3
      2373874.96     13747525.01        2373075.       13747725.
      2371475.03       13747925.
#Sta/Elev= 30
  4179.4  415.77  4197.4   417.5  4230.9  412.65  4272.1  404.58  4326.2  391.11
  4362.3  386.13    4437   382.2  4483.7  382.02  4550.4  384.33  4645.5  379.34
  4774.6  378.86  4808.1  376.65    4836  377.74  4849.4  379.05  4909.4  378.94
  4931.8  377.94  4952.4  374.83  4954.4  369.47  4955.3  368.97  4991.8  369.47
  5041.8  377.12  5046.8  376.37    5111  380.91  5609.1  382.93  5826.2  383.85
  5900.9   384.3  6248.9   393.4  6345.1  398.28    6437  405.34  6616.4  420.64
#Mann= 13 ,-1 , 0
  4179.4     .12       0  4483.7    .035       0  4645.5     .12       0
    4836    .045       0  4909.4     .07       0  4954.4    .045       0
  4991.8     .07       0    5111     .07       0  5609.1    .035       0
  5826.2     .12       0  6248.9     .07       0  6345.1    .035       0
    6437     .07       0
Bank Sta=4954.4,4991.8
XS Rating Curve= 0 ,0
Exp/Cntr=0.3,0.1

Type RM Length L Ch R = 1 ,12768   ,566,566,566
BEGIN DESCRIPTION:
NASH CREEK 21.0
END DESCRIPTION:
XS GIS Cut Line= 3
      2373825.02     13747475.01        2373075.       13747275.
      2371774.99       13746725.
#Sta/Elev= 30
  4219.5  414.54    4237  415.33  4317.2  402.13  4352.1  391.99  4357.3  392.37
    4381  386.49  4472.4  380.54  4571.4  382.23  4716.3  377.01  4885.3  377.38
  4978.3  377.17  4985.4  376.19  4989.8  372.04  4993.1  368.92  4998.4  368.92
  4998.7   366.6  4999.7   366.1  5036.2   366.6  5039.4  373.95    5050  379.41
  5095.2  380.73  5109.8  381.19  5696.8  380.88  5956.1  382.63  6086.7   385.3
    6216   393.4  6331.3  407.04  6392.7  422.71  6398.2   425.8  6407.3  426.17
#Mann= 10 ,-1 , 0
  4219.5     .12       0    4381    .035       0  4885.3     .12       0
  4989.8     .07       0  4998.7     .05       0  5036.2     .07       0
  5095.2     .12       0  5109.8     .07       0  5696.8    .035       0
  5956.1     .12       0
Bank Sta=4998.7,5036.2
XS Rating Curve= 0 ,0
Exp/Cntr=0.3,0.1

Type RM Length L Ch R = 1 ,12202   ,541,541,541
BEGIN DESCRIPTION:
NASH CREEK 20.0
END DESCRIPTION:
XS GIS Cut Line= 3
      2373774.97     13747324.98        2373125.       13746725.
        2371675.       13746625.
#Sta/Elev= 30
  4110.7  409.05  4152.9  406.43  4245.3  386.25  4294.7  380.32  4386.5  378.07
  4488.3  379.21  4740.4  377.36  4821.2  373.37  4988.2  377.49  4991.9   374.1
  4995.3   374.1  4996.5  368.32  4997.5  367.82  5034.1  368.32  5069.2  373.13
  5075.4  375.61  5100.4  376.11  5195.7  382.42  5275.9  381.35    5316  378.67
  5695.6  381.31  5837.2  384.58  5936.9  383.12  6047.7  385.42  6188.1  396.06
  6278.3  406.61  6308.4  415.47  6338.4  427.62  6368.5  434.75  6448.7  435.16
#Mann= 8 ,-1 , 0
  4110.7     .12       0  4488.3    .035       0  4821.2     .12       0
  4996.5     .05       0  5034.1     .12       0  5100.4     .07       0
  5695.6    .035       0  5936.9     .12       0
Bank Sta=4996.5,5034.1
XS Rating Curve= 0 ,0
Exp/Cntr=0.3,0.1

Type RM Length L Ch R = 1 ,11661   ,428,428,428
BEGIN DESCRIPTION:
NASH CREEK 19.0
END DESCRIPTION:
XS GIS Cut Line= 3
      2374074.98     13747024.98        2373325.       13746325.
      2371725.03     13745925.01
#Sta/Elev= 30
  3974.1  420.98  4002.2  419.53  4122.8  400.81  4165.3  379.21  4179.3  376.81
  4278.2  373.85  4501.6  378.25  4691.7  376.65  4766.7  377.77  4822.9  371.74
  4950.4   375.3  4971.9   370.6  4974.1  365.38    4975  364.88  5011.8  365.38
  5025.8  375.75  5041.2  379.25  5231.9  377.68  5506.2  383.41  5624.7  383.82
  5725.5  383.43  6027.8   385.7  6188.5  388.63  6226.6  388.08  6342.6  396.57
  6443.1  406.33  6466.3   412.9  6502.3  415.06  6507.5  418.39  6649.2  427.01
#Mann= 11 ,-1 , 0
  3974.1     .12       0  4501.6     .07       0  4691.7     .12       0
  4974.1     .05       0  5011.8     .12       0  5231.9     .07       0
  5506.2     .05       0  5624.7     .07       0  5725.5     .05       0
  6027.8    .035       0  6188.5     .12       0
Bank Sta=4974.1,5011.8
XS Rating Curve= 0 ,0
Exp/Cntr=0.3,0.1

Type RM Length L Ch R = 1 ,11233   ,679,679,679
BEGIN DESCRIPTION:
NASH CREEK 18.0
END DESCRIPTION:
XS GIS Cut Line= 3
      2374275.01     13746825.01      2373622.78     13746091.02
      2371988.28     13745205.23
#Sta/Elev= 30
  4130.1  431.54    4215  421.75  4314.5   388.1  4378.1  373.94  4434.9   371.9
  4746.3  375.98  4761.4  375.92  4852.5  371.68  4937.4  374.34  4951.7  374.02
  4975.5  366.44  4976.5  365.94  5013.2  366.44  5029.5  367.49    5037  375.98
  5076.3  378.01  5365.7  377.72  5425.6   374.9  5476.9   376.7  5608.9  380.32
  6562.5  388.03  6626.6  392.22  6714.1  416.81    6736   418.4  6758.7  413.01
    6783  414.54  6804.2     419  6893.2  417.12  6907.3  416.72  6971.1  416.61
#Mann= 13 ,-1 , 0
  4130.1     .12       0  4746.3     .07       0  4761.4     .12       0
  4937.4      .1       0  4975.5     .05       0  5013.2      .1       0
  5076.3     .12       0  5476.9     .07       0  5608.9     .05       0
  6562.5    .035       0    6783    .045       0  6893.2     .12       0
  6907.3    .045       0
Bank Sta=4975.5,5013.2
XS Rating Curve= 0 ,0
Exp/Cntr=0.3,0.1

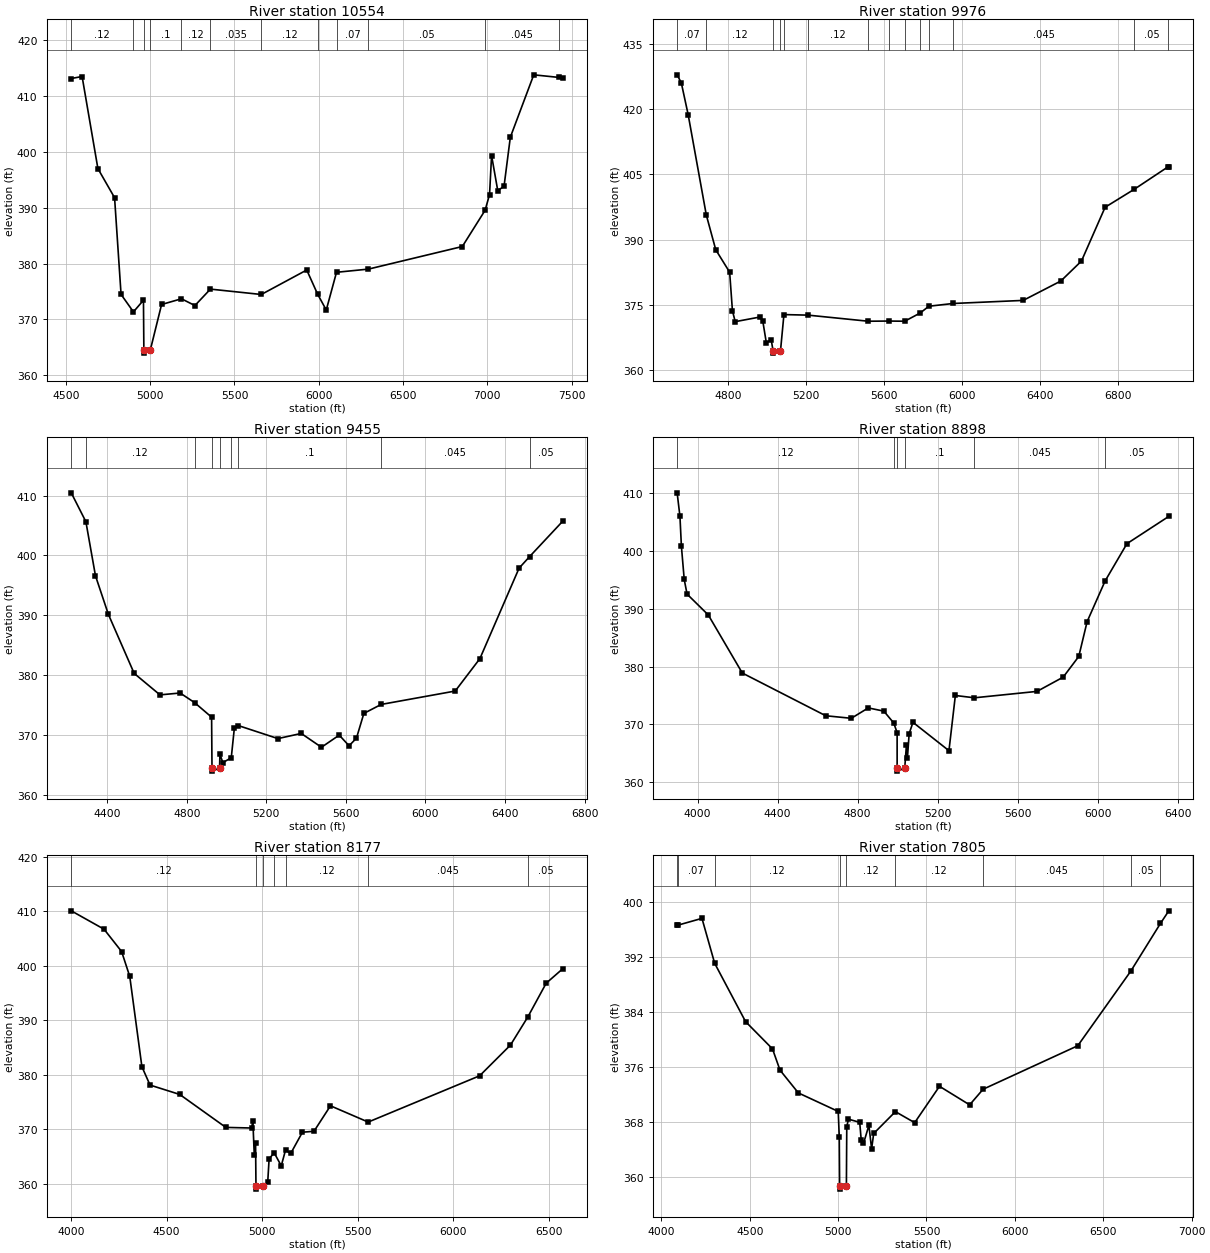
Type RM Length L Ch R = 1 ,10554   ,578,578,578
BEGIN DESCRIPTION:
NASH CREEK 17.0
END DESCRIPTION:
XS GIS Cut Line= 3
        2374784.     13746323.27        2374325.       13746225.
      2372209.11     13744993.68
#Sta/Elev= 30
  4531.3   413.1  4595.7  413.46  4689.5  396.98  4788.4  391.78  4826.9  374.48
  4900.3  371.36  4959.8  373.44  4962.2  364.48  4963.2  363.98    5000  364.48
  5067.3  372.68  5185.3   373.7  5265.1  372.49    5357  375.43    5659  374.47
  5928.7  378.85    5993  374.54  6044.5  371.69  6105.3  378.44  6294.9  379.01
  6851.9  383.05    6987  389.53  7013.4  392.34  7025.5  399.32  7062.2  393.04
  7099.5  393.84  7136.7  402.59  7275.7  413.76  7424.2   413.3  7448.8  413.19
#Mann= 12 ,-1 , 0
  4531.3     .12       0  4900.3      .1       0  4962.2     .05       0
    5000      .1       0  5185.3     .12       0    5357    .035       0
    5659     .12       0    5993     .05       0  6105.3     .07       0
  6294.9     .05       0    6987    .045       0  7424.2    .035       0
Bank Sta=4962.2,5000
XS Rating Curve= 0 ,0
Exp/Cntr=0.3,0.1

Type RM Length L Ch R = 1 ,9976    ,521,521,521
BEGIN DESCRIPTION:
NASH CREEK 16.0
END DESCRIPTION:
XS GIS Cut Line= 3
      2374724.98     13746074.98        2374375.       13745775.
        2372775.       13744475.
#Sta/Elev= 30
  4539.3  427.92  4560.7  426.07  4595.8  418.77    4689  395.65  4737.4  387.67
  4808.7  382.51    4823  373.63  4837.3  371.13  4964.6   372.2  4978.8  371.24
    4997  366.24  5021.8  366.98  5031.6  364.39  5032.6  363.89  5069.5  364.39
  5087.2  372.76  5211.2  372.63  5519.6  371.23  5624.2  371.27  5706.9  371.23
  5786.2  373.12  5830.9  374.68  5954.8  375.31  6314.7  376.02  6507.8  380.48
  6613.6  385.07    6735  397.45  6884.6  401.59  7059.5   406.8  7061.8   406.8
#Mann= 14 ,-1 , 0
  4539.3     .07       0    4689     .12       0  5031.6     .05       0
  5069.5     .12       0  5087.2    .035       0  5211.2     .12       0
  5519.6     .05       0  5624.2     .12       0  5706.9     .07       0
  5786.2     .12       0  5830.9     .07       0  5954.8    .045       0
  6884.6     .05       0  7059.5    .045       0
Bank Sta=5031.6,5069.5
XS Rating Curve= 0 ,0
Exp/Cntr=0.3,0.1

Type RM Length L Ch R = 1 ,9455    ,557,557,557
BEGIN DESCRIPTION:
NASH CREEK 15.0
END DESCRIPTION:
XS GIS Cut Line= 3
      2374975.03     13745775.02        2374325.       13745325.
      2372874.99     13744474.99
#Sta/Elev= 30
  4219.5  410.46  4293.1  405.63  4341.2   396.6    4406  390.15  4535.8  380.27
  4665.5  376.68  4766.9  376.99  4839.7  375.38    4925  372.95    4927  364.43
    4928  363.93  4964.9  364.43  4966.9  366.73  4981.7  365.35  5023.8  366.17
  5039.4  371.14  5059.8  371.54  5258.3  369.37  5375.6  370.23  5477.2  367.92
  5566.5  369.95  5615.9  368.17  5653.1  369.44  5690.3  373.58  5777.3  375.08
  6149.5  377.32  6273.6  382.74  6470.6  397.87  6523.8  399.81  6690.9  405.75
#Mann= 9 ,-1 , 0
  4219.5     .07       0  4293.1     .12       0  4839.7      .1       0
    4927     .05       0  4964.9      .1       0  5023.8     .12       0
  5059.8      .1       0  5777.3    .045       0  6523.8     .05       0
Bank Sta=4927,4964.9
XS Rating Curve= 0 ,0
Exp/Cntr=0.3,0.1

Type RM Length L Ch R = 1 ,8898    ,721,721,721
BEGIN DESCRIPTION:
NASH CREEK 14.0
END DESCRIPTION:
XS GIS Cut Line= 3
      2374975.03     13745575.03        2374175.       13744825.
      2372874.97     13744424.99
#Sta/Elev= 30
  3898.1  410.09  3912.1  406.01  3919.4  400.84  3933.5  395.08  3947.7  392.55
  4053.7  388.94  4223.7  378.88  4640.8  371.48  4768.3  371.04  4853.3  372.84
    4931  372.28  4980.3  370.23  4997.3  368.56  4997.4  362.39  4998.4  361.89
  5035.3  362.39  5043.8   366.4    5049  364.25  5057.5  368.39  5076.5  370.34
  5256.3  365.43  5288.3  374.99  5383.4  374.59  5696.4   375.7  5827.2  378.17
    5905  381.75  5946.8  387.79  6036.7  394.83  6145.6  401.28  6354.9  406.01
#Mann= 6 ,-1 , 0
  3898.1     .12       0  4980.3      .1       0  4997.4     .05       0
  5035.3      .1       0  5383.4    .045       0  6036.7     .05       0
Bank Sta=4997.4,5035.3
XS Rating Curve= 0 ,0
Exp/Cntr=0.3,0.1

Type RM Length L Ch R = 1 ,8177    ,372,372,372
BEGIN DESCRIPTION:
B19752
END DESCRIPTION:
XS GIS Cut Line= 3
      2375216.79     13745415.42      2374403.95     13744518.12
      2373052.69     13744349.22
#Sta/Elev= 30
  4001.3  410.07  4172.9   406.7  4264.8  402.61  4307.4  398.05  4370.9  381.51
  4413.5  378.14  4568.9  376.42  4810.2  370.38  4944.7  370.27  4951.5  371.58
  4958.9  365.34  4965.7  367.59  4967.8  359.57  4968.8  359.07    5006  359.57
  5029.2   360.3  5036.6  364.65  5063.3  365.71  5100.1  363.34  5122.5  366.23
  5149.5   365.6  5210.8   369.5  5271.4  369.67  5357.6  374.34  5554.9  371.36
  6138.1  379.84  6299.4  385.47    6390  390.61  6486.3  396.81  6573.8  399.48
#Mann= 7 ,-1 , 0
  4001.3     .12       0  4967.8     .05       0    5006     .12       0
  5063.3      .1       0  5122.5     .12       0  5554.9    .045       0
    6390     .05       0
Bank Sta=4967.8,5006
XS Rating Curve= 0 ,0
Exp/Cntr=0.3,0.1

Type RM Length L Ch R = 1 ,7805    ,581,581,581
BEGIN DESCRIPTION:
B19751
END DESCRIPTION:
XS GIS Cut Line= 3
      2375639.01     13745014.25      2374688.97     13744423.12
      2373031.64     13744296.44
#Sta/Elev= 30
  4089.6  396.68    4093  396.68    4230  397.68  4301.9  391.12  4476.7  382.61
  4628.9  378.63  4671.4  375.53  4775.3   372.2  5000.8   369.5  5006.7  365.73
  5008.7  358.66  5009.7  358.16    5047  358.66  5049.1  367.28  5058.6  368.37
  5122.3  367.91  5130.8  365.33  5143.6  364.82  5174.3  367.47  5189.6  364.03
  5201.4  366.28  5324.2  369.47  5433.2  367.86  5573.6  373.17  5744.1  370.46
  5820.3  372.74  6355.8  379.09    6656  389.99  6823.4  396.94  6870.7  398.78
#Mann= 9 ,-1 , 0
  4089.6     .12       0    4093     .07       0  4301.9     .12       0
  5008.7     .05       0    5047     .12       0  5324.2     .12       0
  5820.3    .045       0    6656     .05       0  6823.4    .035       0
Bank Sta=5008.7,5047
XS Rating Curve= 0 ,0
Exp/Cntr=0.3,0.1

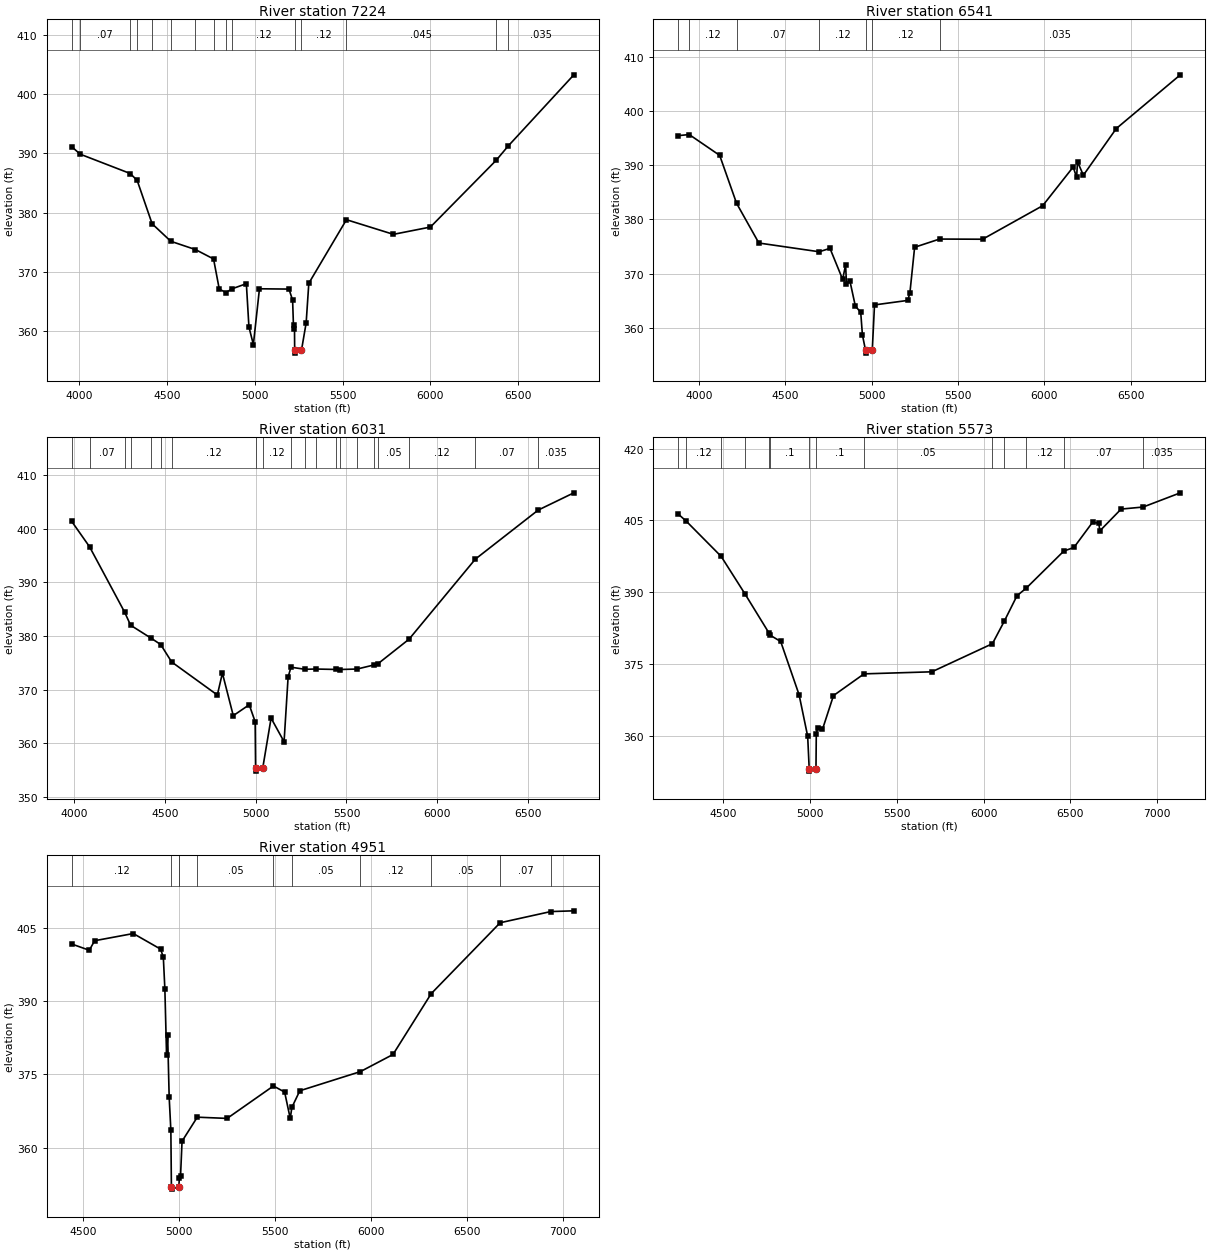
Type RM Length L Ch R = 1 ,7224    ,683,683,683
BEGIN DESCRIPTION:
B19750
END DESCRIPTION:
XS GIS Cut Line= 3
      2375628.54     13743800.28      2374340.61     13744148.65
      2372820.48     13744254.22
#Sta/Elev= 30
  3958.3  391.13  4006.2  389.88  4290.9  386.62  4330.5  385.46  4415.7  378.14
  4522.1  375.19  4662.6  373.79  4765.4  372.21  4797.8  367.15  4834.9  366.54
  4872.8   367.2  4952.1  368.04  4966.8  360.74    4992  357.78  5026.7  367.18
  5194.7  367.13  5215.4  365.26  5220.9  360.37    5226  361.14  5227.1  356.83
  5228.1  356.33    5266  356.83  5292.5  361.43  5307.6  368.11  5521.9  378.83
  5789.3  376.36  5999.8  377.59    6374  388.84  6441.2  391.21  6816.3  403.26
#Mann= 15 ,-1 , 0
  3958.3    .035       0  4006.2     .07       0  4290.9     .12       0
  4330.5     .07       0  4415.7     .12       0  4522.1     .07       0
  4662.6      .1       0  4765.4     .12       0  4834.9      .1       0
  4872.8     .12       0  5227.1     .05       0    5266     .12       0
  5521.9    .045       0    6374     .05       0  6441.2    .035       0
Bank Sta=5227.1,5266
XS Rating Curve= 0 ,0
Exp/Cntr=0.3,0.1

Type RM Length L Ch R = 1 ,6541    ,510,510,510
BEGIN DESCRIPTION:
B19749
END DESCRIPTION:
XS GIS Cut Line= 3
      2375343.47      13743409.7      2373928.91     13743853.07
      2372558.26     13744243.18
#Sta/Elev= 30
  3880.5  395.44  3944.1  395.64  4120.4  391.81  4218.4  382.97  4347.4  375.66
  4696.9  374.05  4759.2  374.68  4832.5  368.97  4849.7  371.61  4854.9  368.13
  4874.5  368.69  4905.9  364.08  4937.3  362.87    4947  358.75  4965.2  355.88
  4966.2  355.38  5004.1  355.88  5017.1  364.26  5209.8  365.09  5222.2  366.52
  5249.4  374.88  5393.7  376.39  5643.2  376.36  5990.8  382.53  6167.6  389.66
  6187.5  387.76  6192.7  390.63  6226.6  388.15  6417.1  396.74    6788  406.64
#Mann= 7 ,-1 , 0
  3880.5     .07       0  3944.1     .12       0  4218.4     .07       0
  4696.9     .12       0  4965.2     .05       0  5004.1     .12       0
  5393.7    .035       0
Bank Sta=4965.2,5004.1
XS Rating Curve= 0 ,0
Exp/Cntr=0.3,0.1

Type RM Length L Ch R = 1 ,6031    ,458,458,458
BEGIN DESCRIPTION:
B19748
END DESCRIPTION:
XS GIS Cut Line= 3
       2374868.4     13742903.01      2373696.67     13743525.82
      2372440.46      13744233.1
#Sta/Elev= 30
  3985.2  401.32  4083.2  396.61  4276.5  384.43  4309.7  381.98    4423  379.56
  4475.4  378.39  4536.2  375.13  4787.9  368.98  4815.8  373.05  4875.8  365.13
  4963.8  367.16  4996.4     364  4998.9  355.29  4999.9  354.79  5037.9  355.29
  5084.3  364.67  5155.9  360.27  5178.2  372.34    5194  374.16  5270.9  373.77
  5329.2  373.82  5444.1  373.74  5463.4  373.73    5559  373.82  5654.2   374.6
  5673.9  374.81    5845  379.38  6210.5   394.3    6557  403.44  6753.8  406.66
#Mann= 20 ,-1 , 0
  3985.2     .07       0  4083.2     .07       0  4276.5    .063       0
  4309.7     .07       0    4423    .035       0  4475.4    .063       0
  4536.2     .12       0  4998.9     .05       0  5037.9     .12       0
    5194      .1       0  5270.9     .12       0  5329.2      .1       0
  5444.1     .05       0  5463.4      .1       0    5559     .05       0
  5654.2      .1       0  5673.9     .05       0    5845     .12       0
  6210.5     .07       0    6557    .035       0
Bank Sta=4998.9,5037.9
XS Rating Curve= 0 ,0
Exp/Cntr=0.3,0.1

Type RM Length L Ch R = 1 ,5573    ,622,622,622
BEGIN DESCRIPTION:
B19747
END DESCRIPTION:
XS GIS Cut Line= 4
      2374382.85     13742470.18      2373094.96     13743641.94
      2372345.46     13744222.55      2372188.55     13744348.08
#Sta/Elev= 30
  4242.6  406.31  4288.8  404.82  4489.6  397.46  4626.3  389.64  4765.2  381.42
  4768.4  381.05  4832.3  379.66  4938.3  368.52  4987.7  359.84  4996.5  353.05
  4997.5  352.55  5035.5  353.05  5037.3  360.27  5044.4  361.52  5072.8  361.27
  5136.3  368.35  5312.2  372.89  5702.6  373.32  6051.2   379.2  6120.3  383.96
  6192.7  389.23  6246.6  390.84  6462.4  398.58  6520.4  399.32  6628.1  404.61
  6663.5  404.38  6669.8   402.8    6792  407.35  6918.8  407.78  7132.8  410.75
#Mann= 14 ,-1 , 0
  4242.6     .07       0  4288.8     .12       0  4489.6     .07       0
  4626.3    .035       0  4765.2     .12       0  4768.4      .1       0
  4996.5     .05       0  5035.5      .1       0  5312.2     .05       0
  6051.2     .12       0  6120.3     .05       0  6246.6     .12       0
  6462.4     .07       0  6918.8    .035       0
Bank Sta=4996.5,5035.5
XS Rating Curve= 0 ,0
Exp/Cntr=0.3,0.1

Type RM Length L Ch R = 1 ,4951    ,797,797,797
BEGIN DESCRIPTION:
B19746
END DESCRIPTION:
XS GIS Cut Line= 3
      2373612.22     13742111.27      2373284.97     13742765.77
      2372144.92     13744264.73
#Sta/Elev= 30
  4441.5  401.66  4532.7  400.39  4560.7  402.34  4761.9  403.81  4904.1  400.62
  4918.4  398.95  4926.4  392.45  4935.2  378.95  4940.8   383.1  4948.8  370.31
  4957.6  363.53  4960.4  351.98  4961.4  351.48  4999.4  351.98  5001.5  353.67
  5007.9  354.08  5015.9  361.29  5095.2  366.21  5250.7  365.96  5491.8   372.6
  5550.2  371.35  5579.3  365.95  5587.9  368.21  5629.2  371.62  5944.7  375.54
  6114.6  379.05  6313.5   391.5  6672.7  406.02  6936.4  408.31  7056.5  408.46
#Mann= 11 ,-1 , 0
  4441.5     .12       0  4960.4     .05       0  4999.4     .12       0
  5001.5      .1       0  5095.2     .05       0  5491.8      .1       0
  5587.9     .05       0  5944.7     .12       0  6313.5     .05       0
  6672.7     .07       0  6936.4    .035       0
Bank Sta=4960.4,4999.4
XS Rating Curve= 0 ,0
Exp/Cntr=0.3,0.1