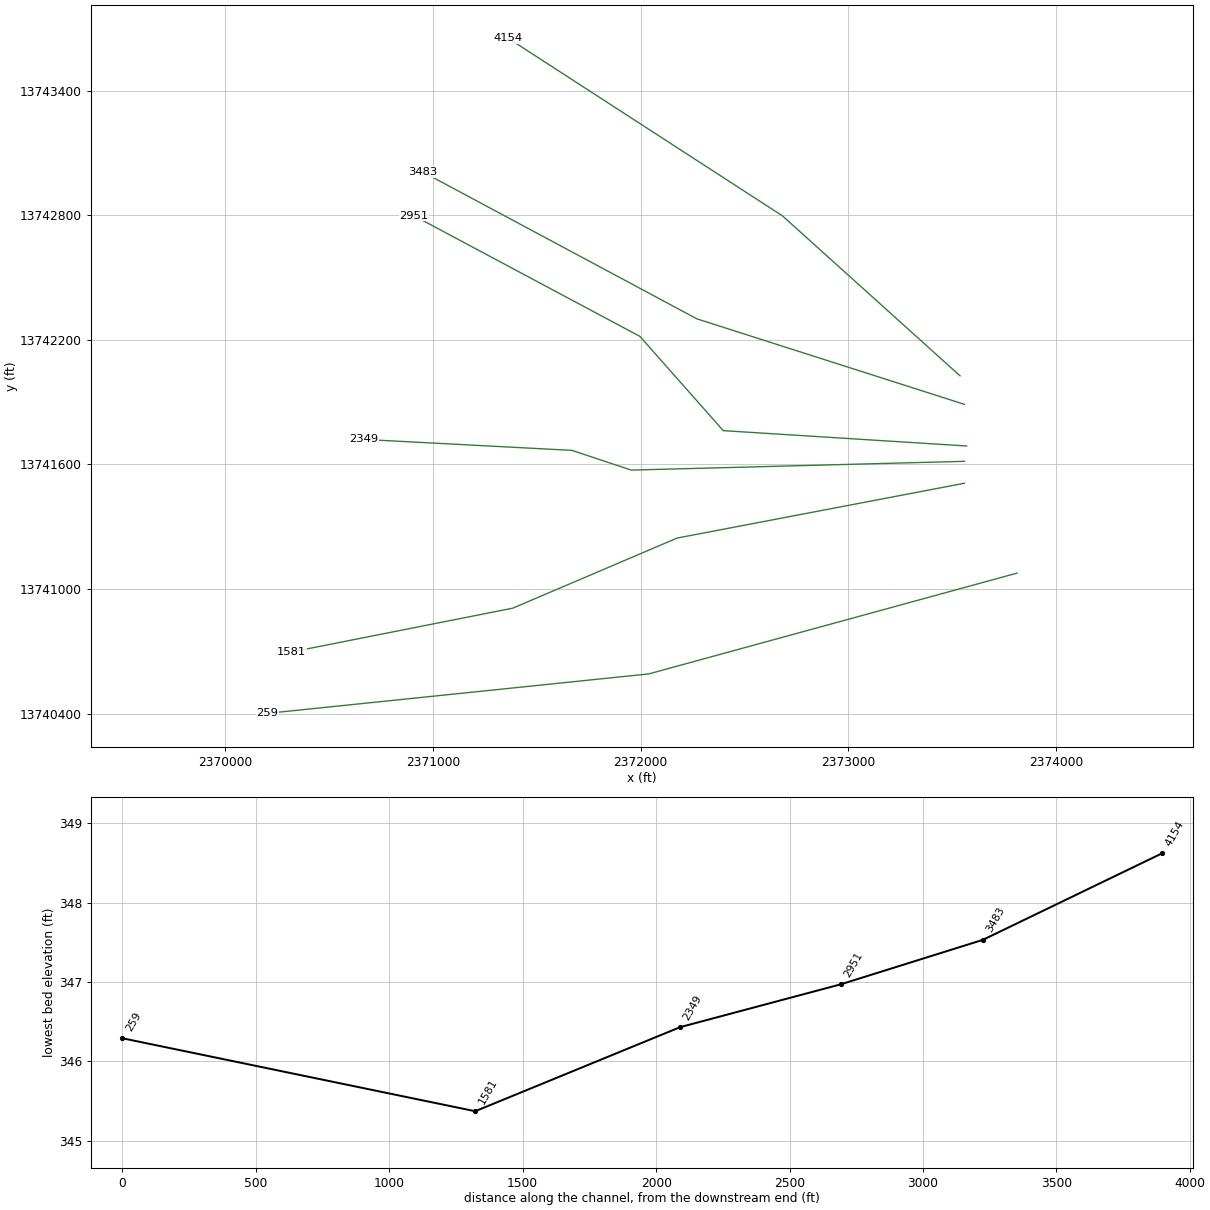
HEC-RAS study NASH CREEK.prj: NASH CREEK Base Level Engineering

--- NASH CREEK.g01 (geometry) --- (continued)

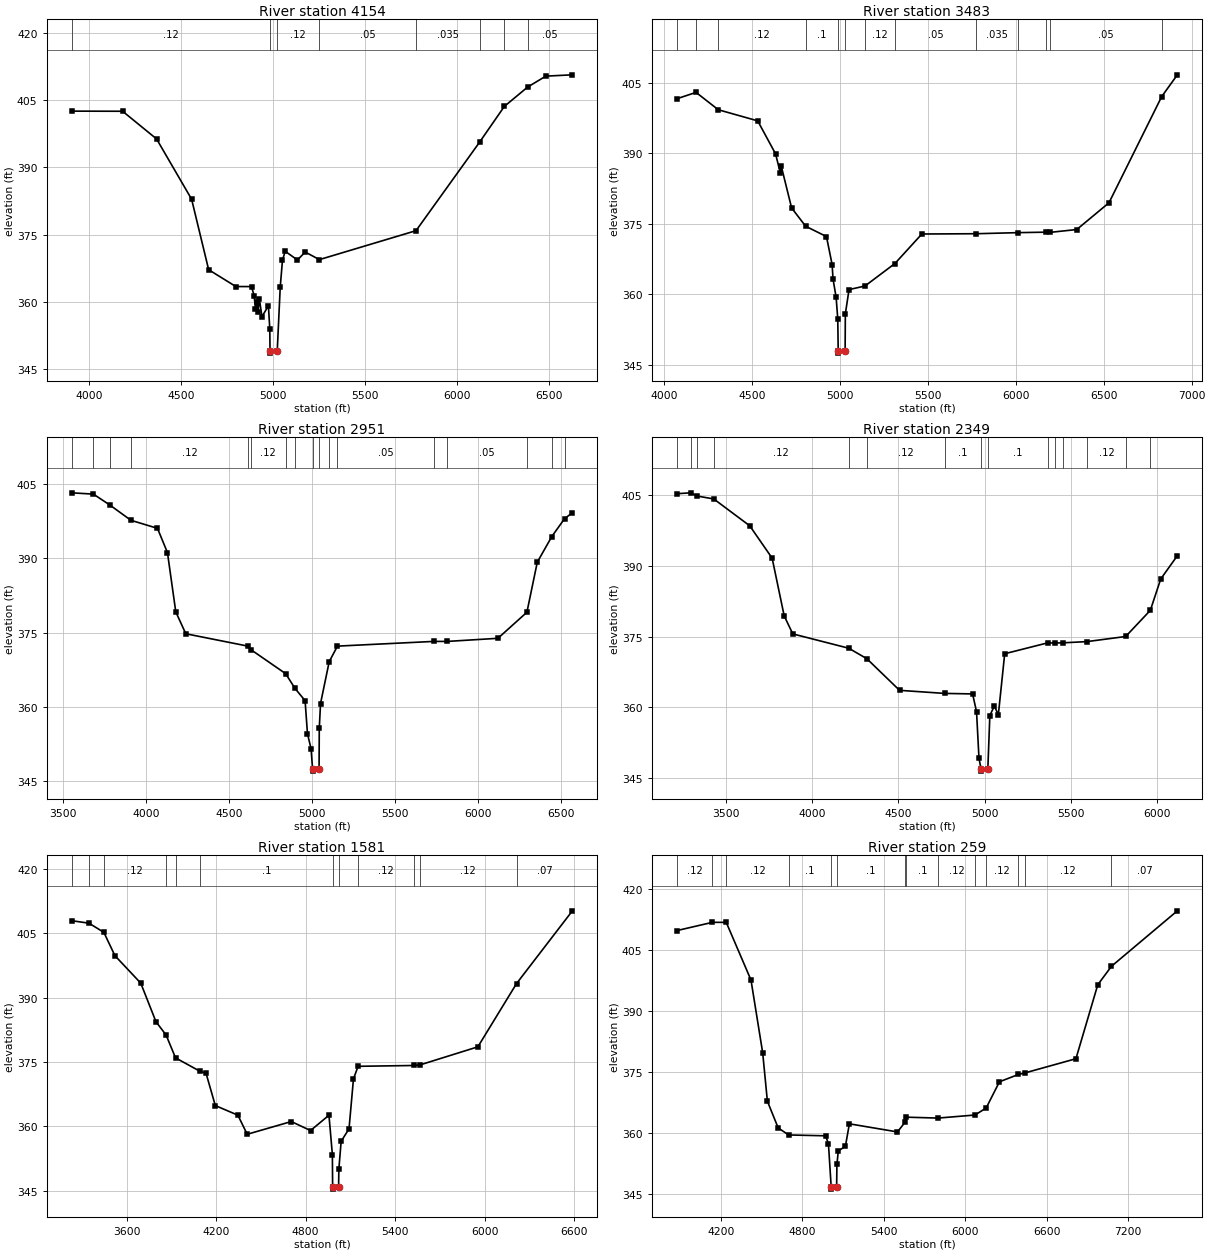
Type RM Length L Ch R = 1 ,4154    ,671,671,671
BEGIN DESCRIPTION:
B19745
END DESCRIPTION:
XS GIS Cut Line= 3
      2373538.31     13742026.83      2372683.26     13742797.43
      2371363.74     13743652.48
#Sta/Elev= 30
    3905  402.55    4182  402.52  4366.6  396.35  4557.2  382.92  4649.9  367.21
  4797.9  363.46    4883  363.45  4897.2  361.45  4904.7  358.42  4911.4  360.02
  4918.9  357.86  4925.6  360.77  4939.8  356.73    4975  359.18  4982.4  354.04
  4983.8  349.12  4984.8  348.62    5023  349.12  5039.2   363.3  5051.5  369.35
  5066.3  371.31  5132.9  369.38  5175.1  371.15  5252.3  369.46  5777.9  375.91
  6123.2  395.61  6258.2   403.6  6385.2  407.92  6483.9  410.35  6628.4  410.64
#Mann= 8 ,-1 , 0
    3905     .12       0  4983.8     .05       0    5023     .12       0
  5252.3     .05       0  5777.9    .035       0  6123.2     .05       0
  6258.2    .035       0  6385.2     .05       0
Bank Sta=4983.8,5023
XS Rating Curve= 0 ,0
Exp/Cntr=0.3,0.1

Type RM Length L Ch R = 1 ,3483    ,532,532,532
BEGIN DESCRIPTION:
B19744
END DESCRIPTION:
XS GIS Cut Line= 3
      2373559.42     13741889.59      2372271.56     13742301.28
      2370952.02     13743008.56
#Sta/Elev= 30
  4069.4  401.56  4179.8  402.93  4306.4  399.24  4530.6  396.88  4632.4  389.86
  4659.3  385.83  4664.5  387.29  4723.6  378.38  4803.4  374.49  4921.9   372.3
  4954.1  366.36  4959.3  363.27  4976.9   359.4  4986.2  354.82  4988.8  348.03
  4989.8  347.53  5028.1  348.03  5029.4  355.87  5050.4  361.03  5141.1  361.79
  5311.5  366.57  5464.8  372.84  5774.1   372.9  6013.8  373.13  6168.8  373.23
  6191.8  373.18  6346.2  373.79  6529.5  379.47  6829.5  402.03  6918.6  406.66
#Mann= 13 ,-1 , 0
  4069.4    .035       0  4179.8     .07       0  4306.4     .12       0
  4803.4      .1       0  4988.8     .05       0  5028.1      .1       0
  5141.1     .12       0  5311.5     .05       0  5774.1    .035       0
  6013.8     .05       0  6168.8     .07       0  6191.8     .05       0
  6829.5     .07       0
Bank Sta=4988.8,5028.1
XS Rating Curve= 0 ,0
Exp/Cntr=0.3,0.1

Type RM Length L Ch R = 1 ,2951    ,602,602,602
BEGIN DESCRIPTION:
B19743
END DESCRIPTION:
XS GIS Cut Line= 4
        2373570.     13741689.01      2372398.24     13741762.91
       2371997.1     13742216.83      2370909.86      13742797.4
#Sta/Elev= 30
  3554.3  403.25  3684.8  402.99  3783.6  400.79  3910.4   397.7  4070.3  396.07
  4130.4  391.16  4180.5  379.18  4240.7  374.75  4614.3  372.25  4632.7  371.53
  4841.9  366.67    4897  363.73  4958.5  361.22  4972.7  354.55  4994.5  351.49
  5003.3  347.47  5004.3  346.97  5042.6  347.47  5043.8   355.6  5051.4  360.64
  5103.6  369.11  5153.2  372.25  5731.1   373.2  5813.2   373.2  6118.7  373.83
    6293   379.1  6355.5  389.23  6442.9  394.41  6519.7  398.03  6566.7  399.22
#Mann= 17 ,-1 , 0
  3554.3     .07       0  3684.8    .035       0  3783.6     .07       0
  3910.4     .12       0  4614.3      .1       0  4632.7     .12       0
  4841.9      .1       0    4897     .12       0  5003.3     .05       0
  5042.6     .12       0  5103.6      .1       0  5153.2     .05       0
  5731.1     .07       0  5813.2     .05       0    6293     .07       0
  6442.9     .05       0  6519.7     .07       0
Bank Sta=5003.3,5042.6
XS Rating Curve= 0 ,0
Exp/Cntr=0.3,0.1

Type RM Length L Ch R = 1 ,2349    ,768,768,768
BEGIN DESCRIPTION:
B19742
END DESCRIPTION:
XS GIS Cut Line= 4
      2373559.47     13741615.12      2371954.87     13741572.89
      2371669.85      13741667.9      2370668.53      13741720.6
#Sta/Elev= 30
  3211.4  405.32  3293.9  405.51  3328.6  404.84    3427  404.21    3636  398.51
  3766.1  391.64  3836.1  379.38  3886.1  375.56  4211.1  372.52  4316.1   370.3
  4506.3  363.58  4767.3  362.93  4930.5  362.82  4953.4  359.03  4967.4  349.22
    4979  346.93    4980  346.43    5019  346.93  5030.6  358.23    5057  360.28
  5079.9  358.36  5116.9  371.35  5365.6  373.65  5409.8  373.63  5457.6  373.67
  5595.7  373.93  5819.6  375.01  5962.9  380.57  6023.1  387.21  6119.7  392.16
#Mann= 15 ,-1 , 0
  3211.4     .07       0  3293.9     .12       0  3328.6    .035       0
    3427     .12       0  4211.1      .1       0  4316.1     .12       0
  4767.3      .1       0    4979     .05       0    5019      .1       0
  5365.6     .07       0  5409.8     .12       0  5457.6     .07       0
  5595.7     .12       0  5819.6     .05       0  5962.9     .12       0
Bank Sta=4979,5019
XS Rating Curve= 0 ,0
Exp/Cntr=0.3,0.1

Type RM Length L Ch R = 1 ,1581    ,1322,1322,1322
BEGIN DESCRIPTION:
B19741
END DESCRIPTION:
XS GIS Cut Line= 4
      2373559.46     13741509.56      2372176.56     13741245.65
      2371384.83     13740907.84      2370319.36     13740696.86
#Sta/Elev= 30
  3232.8  407.92  3348.4  407.34  3448.1  405.21  3522.4  399.77  3695.5  393.37
  3797.3  384.39  3865.3  381.27  3928.5  375.96  4093.4  372.81  4132.7   372.4
    4195  364.84  4346.3   362.6  4408.6  358.15  4704.1  361.12    4833  359.02
  4956.5  362.59  4979.4  353.42  4981.1  345.87  4982.1  345.37  5021.1  345.87
  5022.9  350.07  5038.2  356.52  5090.9  359.41  5120.7  371.05  5151.7  373.99
  5524.1  374.18  5565.9  374.31  5954.3  378.53  6213.5  393.28  6587.6  410.22
#Mann= 12 ,-1 , 0
  3232.8     .12       0  3348.4    .035       0  3448.1     .12       0
  3865.3      .1       0  3928.5     .12       0  4093.4      .1       0
  4981.1     .05       0  5021.1      .1       0  5151.7     .12       0
  5524.1    .035       0  5565.9     .12       0  6213.5     .07       0
Bank Sta=4981.1,5021.1
XS Rating Curve= 0 ,0
Exp/Cntr=0.3,0.1

Type RM Length L Ch R = 1 ,259     ,0,0,0
BEGIN DESCRIPTION:
B19740
END DESCRIPTION:
XS GIS Cut Line= 3
      2373812.75     13741076.73      2372039.32     13740591.15
      2370202.53     13740401.14
#Sta/Elev= 30
  3875.5   409.7  4139.3  411.74  4240.6  411.73  4422.7  397.58  4508.8  379.73
  4543.3  367.87  4622.7  361.31  4699.7  359.58  4972.2  359.37  4992.9  357.38
    5013  346.79    5014  346.29  5053.1  346.79  5055.1  352.37  5065.5  355.68
  5117.6  356.78  5146.9  362.31    5501  360.32  5555.1  362.65  5567.1  363.94
  5799.5  363.72  6071.8  364.47  6153.8   366.2  6251.4  372.62  6390.1  374.41
  6439.3   374.8  6814.4  378.28  6975.2  396.43  7076.1  400.96  7560.8  414.56
#Mann= 14 ,-1 , 0
  3875.5     .12       0  4139.3    .035       0  4240.6     .12       0
  4699.7      .1       0    5013     .05       0  5053.1      .1       0
  5555.1     .12       0  5567.1      .1       0  5799.5     .12       0
  6071.8      .1       0  6153.8     .12       0  6390.1    .035       0
  6439.3     .12       0  7076.1     .07       0
Bank Sta=5013,5053.1
XS Rating Curve= 0 ,0
Exp/Cntr=0.3,0.1

Chan Stop Cuts=-1
Use User Specified Reach Order=0
Composite Channel Slope=5