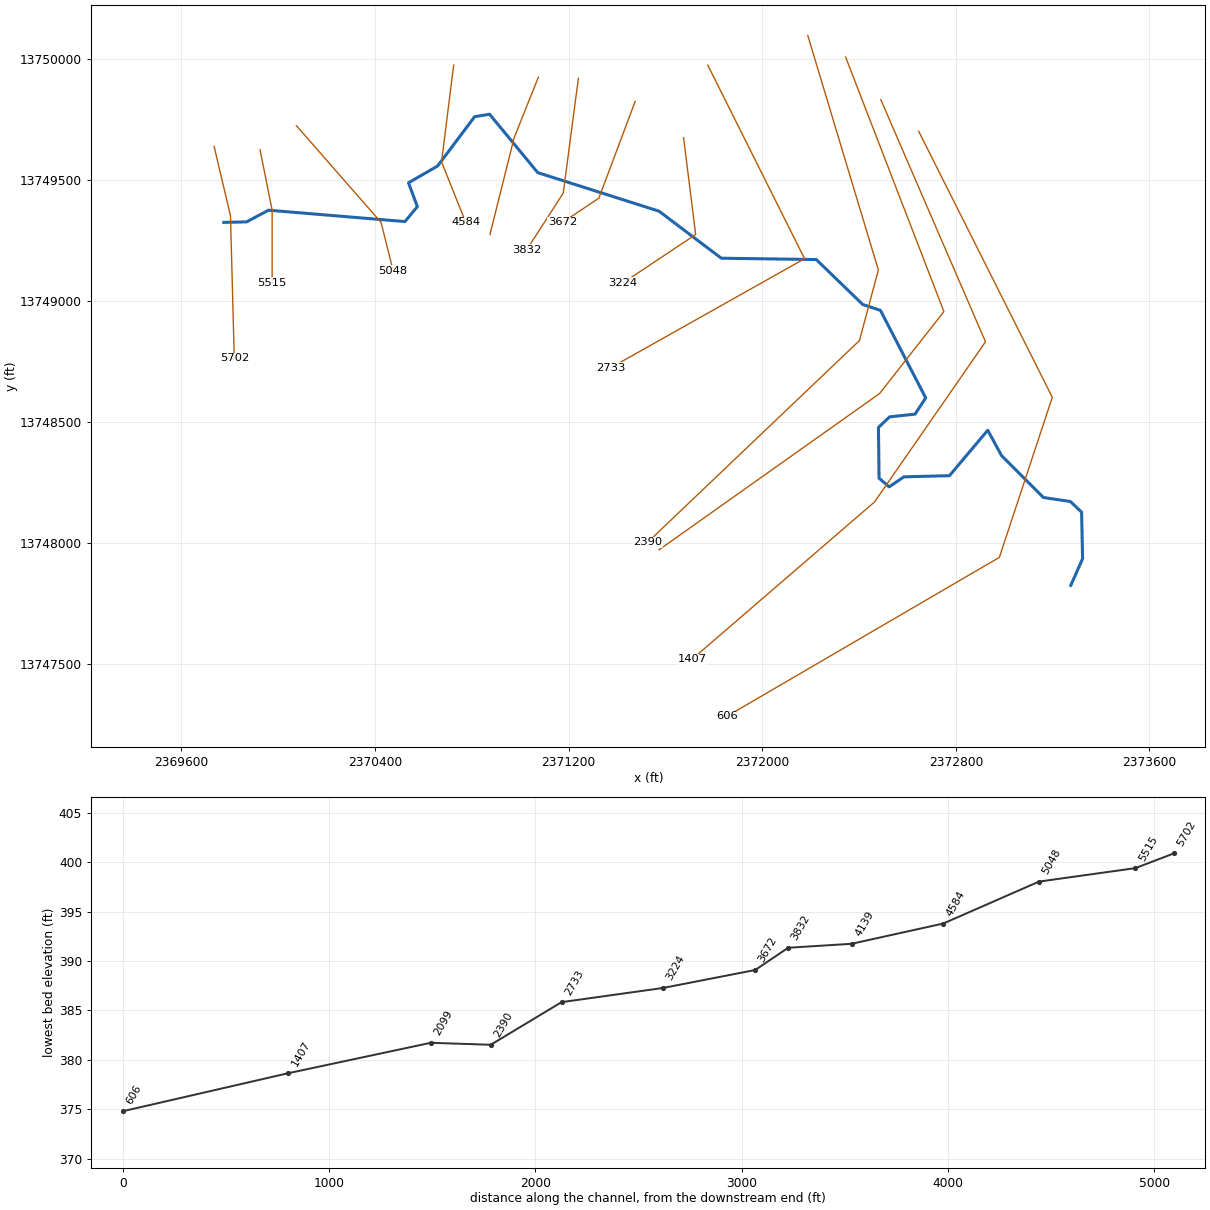
--- NASH TRIBUTARY 1.prj (project) ---

Proj Title=NASH TRIBUTARY 1 Base Level Engineering
Current Plan=p01
Default Exp/Contr=0.3,0.1
English Units
Geom File=g01
Flow File=f01
Plan File=p01
BEGIN DESCRIPTION:
NASH TRIBUTARY 1
END DESCRIPTION:

--- NASH TRIBUTARY 1.p01 (plan) ---

Plan Title=Multiple Run
Short Identifier=Multiple
Geom File=g01
Flow File=f01
Subcritical Flow
K Sum by GR= 0
Std Step Tol= 0.01
Critical Tol= 0.01
Num of Std Step Trials= 20
Max Error Tol= 0.3
Flow Tol Ratio= 0.001
Split Flow NTrial= 30
Split Flow Tol= 0.02
Split Flow Ratio= 0.02
Log Output Level= 0
Friction Slope Method= 1
Unsteady Friction Slope Method= 2
Unsteady Bridges Friction Slope Method= 1
Parabolic Critical Depth
Global Vel Dist=  1 , 1 , 1
Global Log Level= 0
CheckData=True
Encroach Param= -1, 0, 0, 0
BEGIN DESCRIPTION:
Multiple Run
END DESCRIPTION:

--- NASH TRIBUTARY 1.f01 (steady flow) ---

Flow Title=Multiple
Number of Profiles=7
Profile Names=10-year,25-year,50-year,1pct_min,100-year,1pct_plu,500-year
River Rch & RM= NASH TRIBUTARY 1,Reach-1,5702
     755    1232    1667    1092    2178    4346    3686
Boundary for River Rch & Prof#=NASH TRIBUTARY 1,Reach-1,1
Up Type=0
Dn Type=3
Dn Slope=0.005
Boundary for River Rch & Prof#=NASH TRIBUTARY 1,Reach-1,2
Up Type=0
Dn Type=3
Dn Slope=0.005
Boundary for River Rch & Prof#=NASH TRIBUTARY 1,Reach-1,3
Up Type=0
Dn Type=3
Dn Slope=0.005
Boundary for River Rch & Prof#=NASH TRIBUTARY 1,Reach-1,4
Up Type=0
Dn Type=3
Dn Slope=0.005
Boundary for River Rch & Prof#=NASH TRIBUTARY 1,Reach-1,5
Up Type=0
Dn Type=3
Dn Slope=0.005
Boundary for River Rch & Prof#=NASH TRIBUTARY 1,Reach-1,6
Up Type=0
Dn Type=3
Dn Slope=0.005
Boundary for River Rch & Prof#=NASH TRIBUTARY 1,Reach-1,7
Up Type=0
Dn Type=3
Dn Slope=0.005

--- NASH TRIBUTARY 1.g01 (geometry) ---

Geom Title=Existing Conditions

River Reach=NASH TRIBUTARY 1,Reach-1
Reach XY= 30
      2369775.00     13749325.00      2369869.13     13749327.10
      2369959.82     13749375.43      2370523.81     13749328.45
      2370575.04     13749390.22      2370538.40     13749488.73
      2370658.57     13749557.92      2370811.76     13749761.90
      2370873.35     13749771.91      2371072.45     13749530.73
      2371573.50     13749371.38      2371830.86     13749177.06
      2372223.54     13749171.46      2372415.34     13748985.79
      2372488.56     13748961.51      2372675.55     13748599.87
      2372631.55     13748532.75      2372526.25     13748521.49
      2372480.34     13748477.74      2372482.80     13748268.16
      2372524.65     13748232.21      2372585.43     13748273.61
      2372773.75     13748278.45      2372931.94     13748466.17
      2372988.63     13748361.82      2373161.70     13748188.41
      2373273.75     13748171.49      2373319.66     13748127.74
      2373323.88     13747935.46      2373275.00     13747825.00

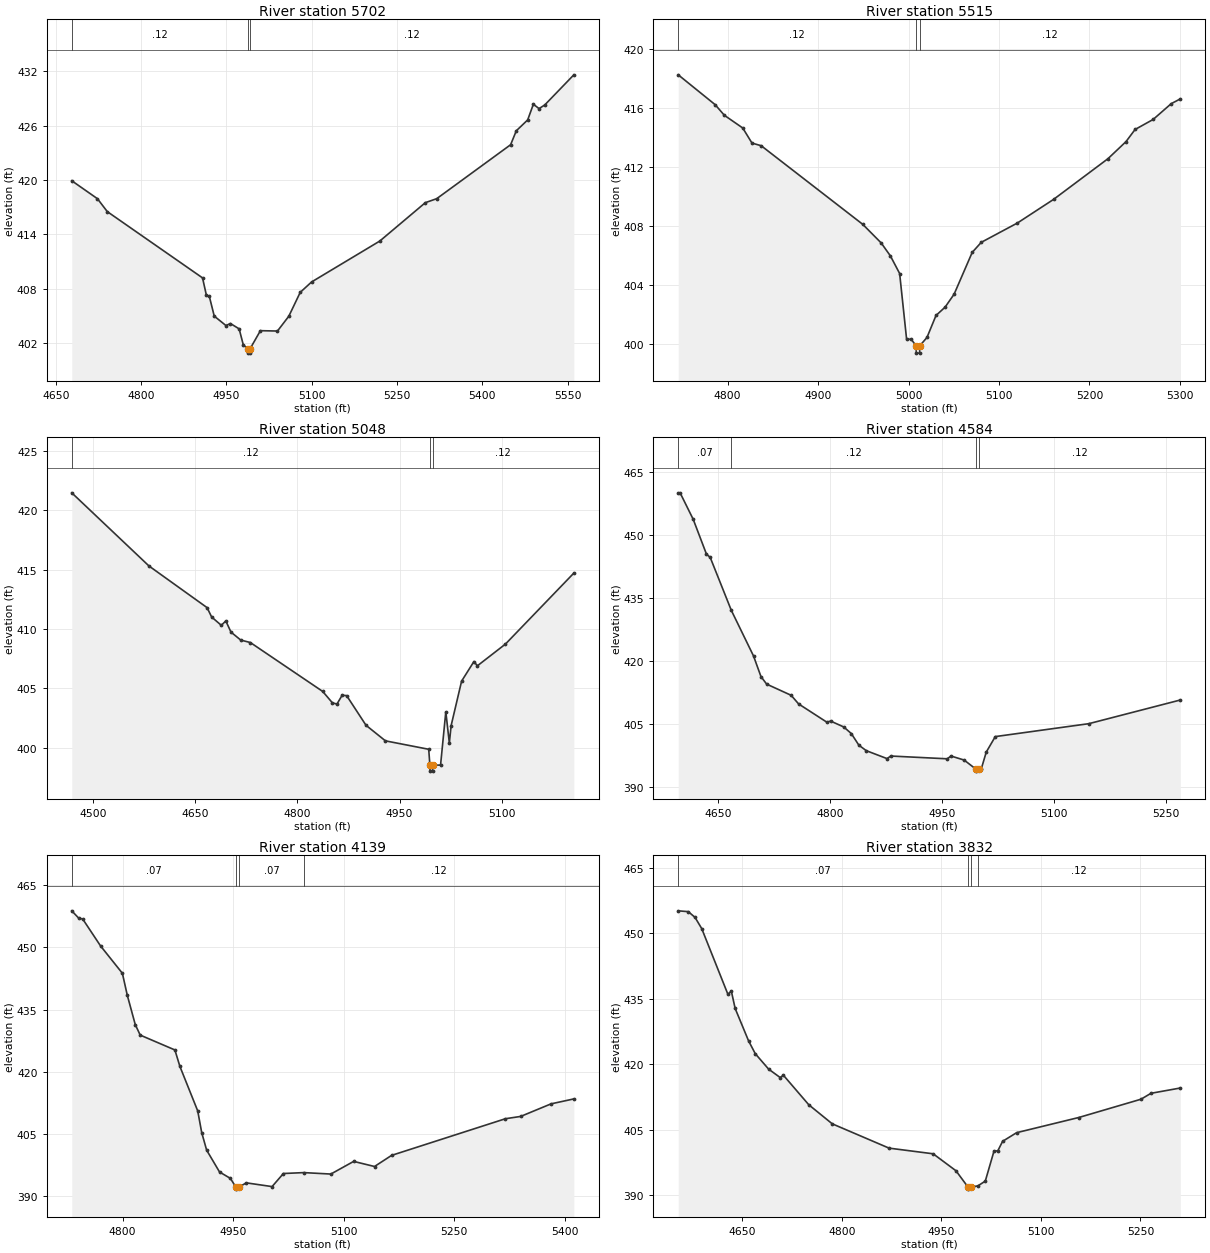
Type RM Length L Ch R = 1,5702,187,187,187
BEGIN DESCRIPTION:
B19778
END DESCRIPTION:
XS GIS Cut Line= 3
      2369735.15     13749638.87      2369802.87     13749352.38
      2369818.49     13748763.87
#Sta/Elev= 30
  4677.9  419.92  4723.0  417.94  4740.4  416.51  4907.9  409.19  4914.7  407.27
  4919.8  407.16  4928.5  404.97  4949.0  403.93  4957.0  404.15  4972.3  403.56
  4979.7  401.77  4987.6  401.38  4987.9  400.88  4991.5  400.88  4991.7  401.38
  5009.7  403.36  5039.7  403.32  5059.7  404.96  5079.7  407.59  5099.7  408.74
  5219.7  413.26  5299.8  417.50  5319.8  417.94  5449.8  423.90  5459.8  425.44
  5479.8  426.64  5489.8  428.37  5499.8  427.89  5509.8  428.29  5561.0  431.62
#Mann=3,-1,0
  4677.9    0.12       0  4987.6    0.05       0  4991.7    0.12       0
Bank Sta=4987.6,4991.7
Exp/Cntr=0.3,0.1

Type RM Length L Ch R = 1,5515,467,467,467
BEGIN DESCRIPTION:
NASH TRIBUTARY 1 7.0
END DESCRIPTION:
XS GIS Cut Line= 3
      2369925.01     13749624.96      2369975.00     13749375.00
      2369975.00     13749075.01
#Sta/Elev= 30
  4745.5  418.23  4786.3  416.21  4796.5  415.49  4816.8  414.63  4827.0  413.61
  4837.2  413.43  4949.4  408.11  4969.8  406.85  4980.0  405.97  4990.2  404.78
  4997.9  400.33  5002.9  400.33  5008.4  399.89  5008.6  399.39  5012.2  399.39
  5012.5  399.89  5020.4  400.45  5030.4  401.94  5040.4  402.50  5050.4  403.38
  5070.4  406.21  5080.4  406.89  5120.4  408.20  5160.4  409.80  5220.4  412.55
  5240.4  413.71  5250.4  414.53  5270.4  415.21  5290.4  416.28  5300.4  416.60
#Mann=3,-1,0
  4745.5    0.12       0  5008.4    0.05       0  5012.5    0.12       0
Bank Sta=5008.4,5012.5
Exp/Cntr=0.3,0.1

Type RM Length L Ch R = 1,5048,464,464,464
BEGIN DESCRIPTION:
NASH TRIBUTARY 1 6.0
END DESCRIPTION:
XS GIS Cut Line= 3
      2370075.02     13749724.98      2370425.00     13749325.00
      2370474.99     13749125.04
#Sta/Elev= 30
  4468.4  421.47  4581.8  415.31  4667.2  411.80  4673.9  411.01  4688.1  410.31
  4694.7  410.68  4702.3  409.74  4716.6  409.07  4730.8  408.86  4837.1  404.74
  4851.3  403.78  4858.0  403.68  4865.6  404.42  4872.2  404.39  4900.7  401.89
  4929.2  400.58  4992.8  399.87  4994.5  398.53  4994.8  398.03  4998.4  398.03
  4998.7  398.53  5010.2  398.54  5017.9  403.03  5023.1  400.40  5025.7  401.86
  5041.1  405.61  5059.2  407.26  5064.3  406.90  5105.5  408.73  5206.0  414.71
#Mann=3,-1,0
  4468.4    0.12       0  4994.5    0.05       0  4998.7    0.12       0
Bank Sta=4994.5,4998.7
Exp/Cntr=0.3,0.1

Type RM Length L Ch R = 1,4584,445,445,445
BEGIN DESCRIPTION:
NASH TRIBUTARY 1 5.0
END DESCRIPTION:
XS GIS Cut Line= 3
      2370725.00     13749974.99      2370675.00     13749575.00
      2370775.02     13749324.96
#Sta/Elev= 30
  4596.4  459.96  4598.9  459.96  4616.5  453.64  4634.2  445.38  4639.2  444.61
  4667.5  432.01  4697.2  421.18  4707.2  416.27  4714.8  414.48  4747.6  411.82
  4757.6  409.77  4795.4  405.43  4800.5  405.69  4818.1  404.29  4828.2  402.72
  4838.3  399.96  4848.3  398.65  4876.0  396.77  4881.1  397.38  4956.7  396.72
  4961.7  397.38  4979.3  396.42  4994.9  394.29  4995.1  393.79  4999.1  394.29
  5002.2  394.29  5008.9  398.31  5021.0  402.00  5146.2  405.07  5268.8  410.70
#Mann=4,-1,0
  4596.4    0.07       0  4667.5    0.12       0  4994.9    0.05       0
  4999.1    0.12       0
Bank Sta=4994.9,4999.1
Exp/Cntr=0.3,0.1

Type RM Length L Ch R = 1,4139,307,307,307
BEGIN DESCRIPTION:
NASH TRIBUTARY 1 4.0
END DESCRIPTION:
XS GIS Cut Line= 3
      2371075.01     13749925.01      2370975.00     13749675.00
      2370875.00     13749274.98
#Sta/Elev= 30
  4731.0  458.77  4740.4  457.01  4745.8  456.81  4770.1  450.31  4799.7  443.73
  4806.4  438.41  4817.2  431.37  4823.9  428.84  4871.0  425.26  4877.8  421.29
  4902.0  410.57  4907.4  405.36  4914.1  401.13  4931.6  395.87  4946.4  394.32
  4953.7  392.24  4954.0  391.74  4957.9  392.24  4968.0  393.25  5002.9  392.35
  5018.3  395.50  5046.0  395.72  5082.7  395.37  5113.7  398.42  5142.0  397.19
  5165.2  399.87  5319.8  408.70  5340.4  409.25  5381.7  412.28  5412.6  413.47
#Mann=4,-1,0
  4731.0    0.07       0  4953.7    0.05       0  4957.9    0.07       0
  5046.0    0.12       0
Bank Sta=4953.7,4957.9
Exp/Cntr=0.3,0.1

Type RM Length L Ch R = 1,3832,160,160,160
BEGIN DESCRIPTION:
B19777
END DESCRIPTION:
XS GIS Cut Line= 3
      2371240.37     13749920.08      2371177.87     13749446.13
      2371026.81     13749211.74
#Sta/Elev= 30
  4553.2  455.14  4568.4  454.95  4578.5  453.64  4588.6  451.07  4628.2  435.96
  4633.2  436.77  4639.0  432.76  4659.2  425.34  4669.3  422.40  4689.4  418.86
  4706.8  416.93  4711.8  417.44  4750.0  410.68  4785.4  406.31  4871.0  400.74
  4937.5  399.44  4971.9  395.55  4989.9  391.84  4990.2  391.34  4994.2  391.84
  5004.8  392.07  5016.1  393.18  5029.3  400.10  5034.9  400.10  5042.2  402.30
  5063.3  404.28  5157.0  407.76  5250.8  411.95  5265.9  413.31  5310.1  414.52
#Mann=4,-1,0
  4553.2    0.07       0  4989.9    0.05       0  4994.2    0.07       0
  5004.8    0.12       0
Bank Sta=4989.9,4994.2
Exp/Cntr=0.3,0.1

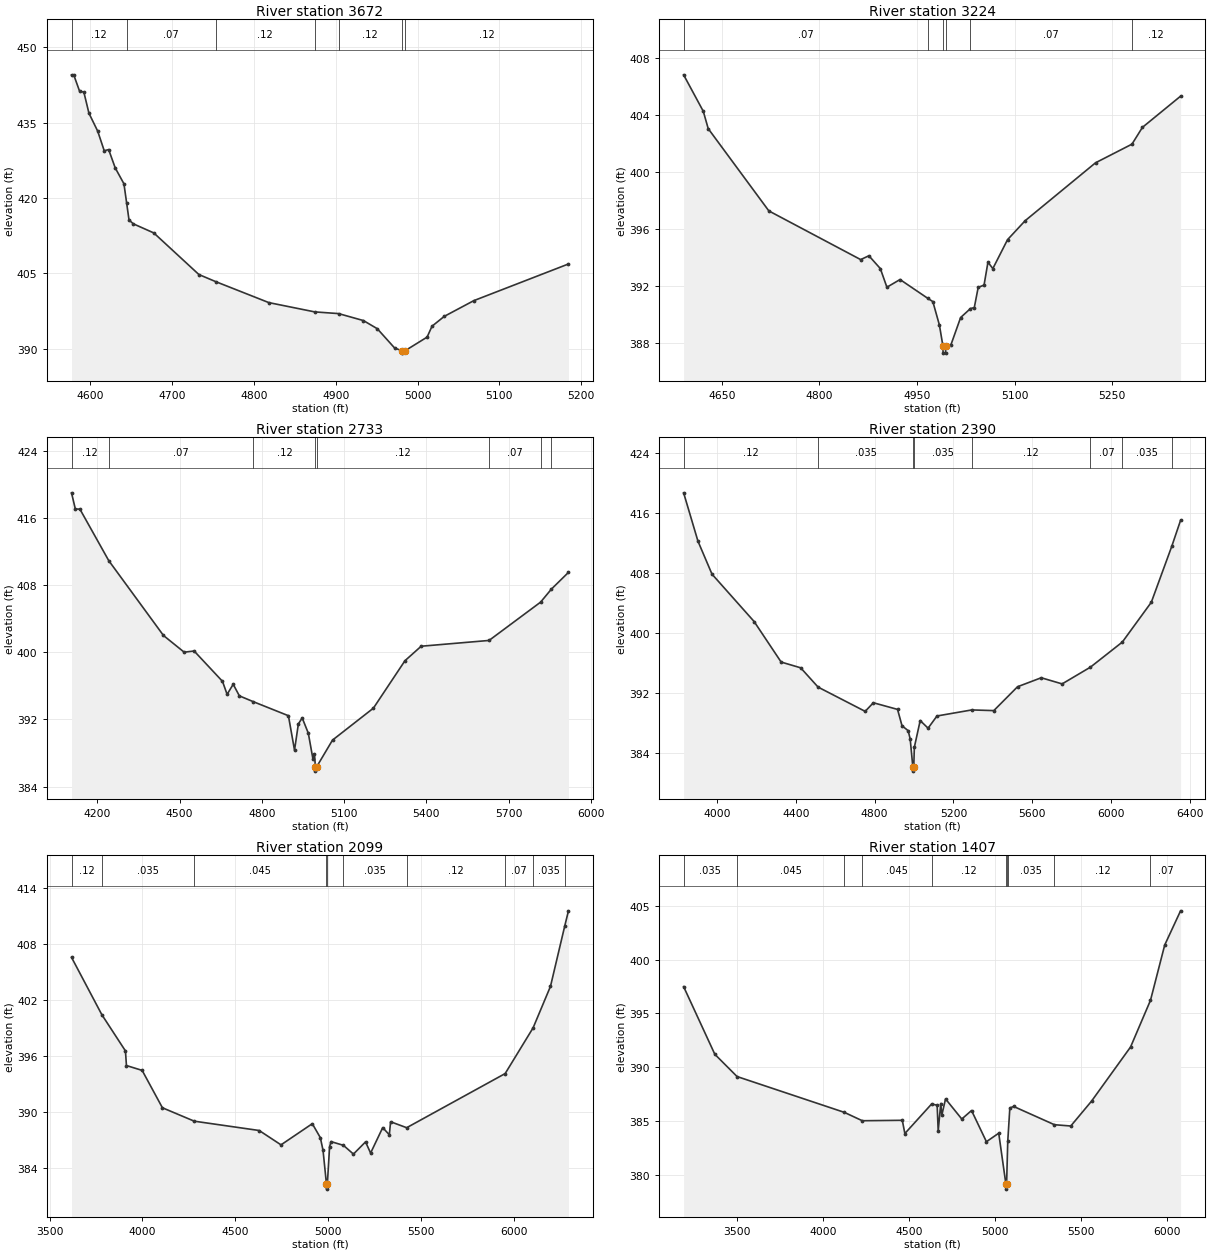
Type RM Length L Ch R = 1,3672,448,448,448
BEGIN DESCRIPTION:
NASH TRIBUTARY 1 3.0
END DESCRIPTION:
XS GIS Cut Line= 3
      2371474.99     13749824.98      2371325.00     13749425.00
      2371174.97     13749324.98
#Sta/Elev= 30
  4577.0  444.50  4579.7  444.50  4586.8  441.27  4592.1  441.05  4598.3  436.86
  4609.0  433.29  4617.0  429.38  4622.4  429.62  4630.4  425.98  4641.1  422.80
  4644.4  418.97  4647.3  415.60  4652.6  414.83  4677.6  413.02  4732.7  404.74
  4753.5  403.31  4818.2  399.15  4874.3  397.30  4903.5  396.96  4933.9  395.57
  4950.8  393.95  4972.1  390.09  4980.7  389.59  4981.0  389.09  4985.0  389.59
  5011.7  392.28  5017.7  394.45  5032.7  396.41  5068.8  399.54  5184.5  406.84
#Mann=7,-1,0
  4577.0    0.12       0  4644.4    0.07       0  4753.5    0.12       0
  4874.3    0.07       0  4903.5    0.12       0  4980.7    0.05       0
  4985.0    0.12       0
Bank Sta=4980.7,4985
Exp/Cntr=0.3,0.1

Type RM Length L Ch R = 1,3224,491,491,491
BEGIN DESCRIPTION:
NASH TRIBUTARY 1 2.0
END DESCRIPTION:
XS GIS Cut Line= 3
      2371675.00     13749675.02      2371725.00     13749275.00
      2371424.99     13749074.99
#Sta/Elev= 30
  4591.4  406.82  4621.6  404.26  4629.2  403.04  4722.4  397.26  4863.5  393.84
  4876.1  394.11  4893.7  393.21  4903.8  391.90  4924.0  392.44  4966.6  391.12
  4974.4  390.89  4984.5  389.24  4989.9  387.77  4990.2  387.27  4993.9  387.27
  4994.2  387.77  5002.0  387.83  5017.1  389.77  5032.2  390.40  5038.1  390.47
  5044.1  391.89  5053.1  392.05  5059.1  393.66  5066.6  393.21  5089.2  395.24
  5116.2  396.57  5224.4  400.64  5280.4  401.95  5296.5  403.13  5355.1  405.32
#Mann=6,-1,0
  4591.4    0.07       0  4966.6    0.12       0  4989.9    0.05       0
  4994.2    0.12       0  5032.2    0.07       0  5280.4    0.12       0
Bank Sta=4989.9,4994.2
Exp/Cntr=0.3,0.1

Type RM Length L Ch R = 1,2733,343,343,343
BEGIN DESCRIPTION:
NASH TRIBUTARY 1 1.0
END DESCRIPTION:
XS GIS Cut Line= 3
      2371775.02     13749974.96      2372175.00     13749175.00
      2371374.97     13748724.98
#Sta/Elev= 30
  4106.1  419.04  4120.0  417.12  4136.8  417.09  4241.9  410.95  4441.5  402.02
  4516.9  400.03  4553.3  400.17  4656.7  396.55  4673.5  395.00  4695.8  396.20
  4718.2  394.82  4769.4  394.12  4897.1  392.45  4919.4  388.34  4933.4  391.47
  4947.4  392.19  4969.7  390.36  4986.5  387.30  4992.1  387.89  4995.5  386.34
  4995.8  385.84  4999.8  386.34  5057.9  389.54  5207.0  393.35  5322.1  399.01
  5381.3  400.74  5628.8  401.43  5816.8  406.00  5856.1  407.55  5918.4  409.55
#Mann=8,-1,0
  4106.1    0.12       0  4241.9    0.07       0  4769.4    0.12       0
  4995.5    0.05       0  4999.8    0.12       0  5628.8    0.07       0
  5816.8    0.12       0  5856.1    0.05       0
Bank Sta=4995.5,4999.8
Exp/Cntr=0.3,0.1

Type RM Length L Ch R = 1,2390,291,291,291
BEGIN DESCRIPTION:
B19776
END DESCRIPTION:
XS GIS Cut Line= 4
      2372188.29     13750097.15      2372479.95     13749128.42
      2372401.83     13748836.75      2371526.80     13748003.40
#Sta/Elev= 30
  3830.6  418.73  3903.3  412.27  3974.6  407.86  4188.3  401.53  4325.5  396.11
  4424.6  395.34  4513.1  392.76  4751.9  389.52  4793.6  390.67  4916.3  389.78
  4939.0  387.59  4970.1  386.94  4980.4  385.83  4994.1  382.03  4994.4  381.53
  4998.5  382.03  5001.5  384.72  5031.2  388.29  5071.2  387.27  5116.4  388.90
  5292.9  389.71  5404.8  389.62  5525.3  392.81  5645.5  394.01  5751.5  393.19
  5895.3  395.43  6057.0  398.78  6204.1  404.10  6307.8  411.57  6352.6  415.05
#Mann=8,-1,0
  3830.6    0.12       0  4513.1   0.035       0  4994.1   0.035       0
  4998.5   0.035       0  5292.9    0.12       0  5895.3    0.07       0
  6057.0   0.035       0  6307.8    0.07       0
Bank Sta=4994.1,4998.5
Exp/Cntr=0.3,0.1

Type RM Length L Ch R = 1,2099,692,692,692
BEGIN DESCRIPTION:
B19775
END DESCRIPTION:
XS GIS Cut Line= 4
      2372344.55     13750008.59      2372750.78     13748956.55
      2372485.16     13748618.00      2371573.73     13747972.19
#Sta/Elev= 30
  3618.0  406.60  3781.1  400.45  3908.3  396.56  3913.7  394.99  3998.2  394.47
  4107.3  390.46  4278.8  389.02  4628.3  388.02  4745.7  386.48  4914.2  388.75
  4957.5  387.25  4972.0  385.89  4990.6  382.23  4990.9  381.73  4995.0  382.23
  5007.2  386.26  5014.6  386.83  5081.6  386.43  5135.6  385.49  5200.8  386.80
  5228.0  385.60  5293.2  388.33  5328.9  387.56  5335.6  388.96  5422.3  388.32
  5952.4  394.13  6102.9  399.04  6196.4  403.49  6273.3  409.98  6293.1  411.59
#Mann=10,-1,0
  3618.0    0.12       0  3781.1   0.035       0  4278.8   0.045       0
  4990.6   0.045       0  4995.0   0.045       0  5081.6   0.035       0
  5422.3    0.12       0  5952.4    0.07       0  6102.9   0.035       0
  6273.3    0.07       0
Bank Sta=4990.6,4995
Exp/Cntr=0.3,0.1

Type RM Length L Ch R = 1,1407,801,801,801
BEGIN DESCRIPTION:
B19774
END DESCRIPTION:
XS GIS Cut Line= 4
      2372490.36     13749831.57      2372922.66     13748831.55
      2372464.33     13748170.09      2371710.10     13747519.89
#Sta/Elev= 30
  3188.6  397.48  3370.1  391.19  3499.3  389.12  4123.0  385.79  4227.7  385.01
  4460.4  385.05  4475.2  383.82  4631.0  386.57  4663.0  386.45  4669.1  384.07
  4684.0  386.61  4690.1  385.53  4711.8  387.04  4806.3  385.17  4863.0  385.96
  4949.5  383.06  5021.1  383.85  5062.5  379.15  5062.8  378.65  5066.9  379.15
  5073.6  383.09  5085.7  386.19  5107.6  386.34  5345.0  384.64  5440.1  384.52
  5560.8  386.83  5787.9  391.87  5903.7  396.21  5986.4  401.35  6078.6  404.53
#Mann=10,-1,0
  3188.6   0.035       0  3499.3   0.045       0  4123.0    0.12       0
  4227.7   0.045       0  4631.0    0.12       0  5062.5    0.05       0
  5066.9    0.12       0  5073.6   0.035       0  5345.0    0.12       0
  5903.7    0.07       0
Bank Sta=5062.5,5066.9
Exp/Cntr=0.3,0.1

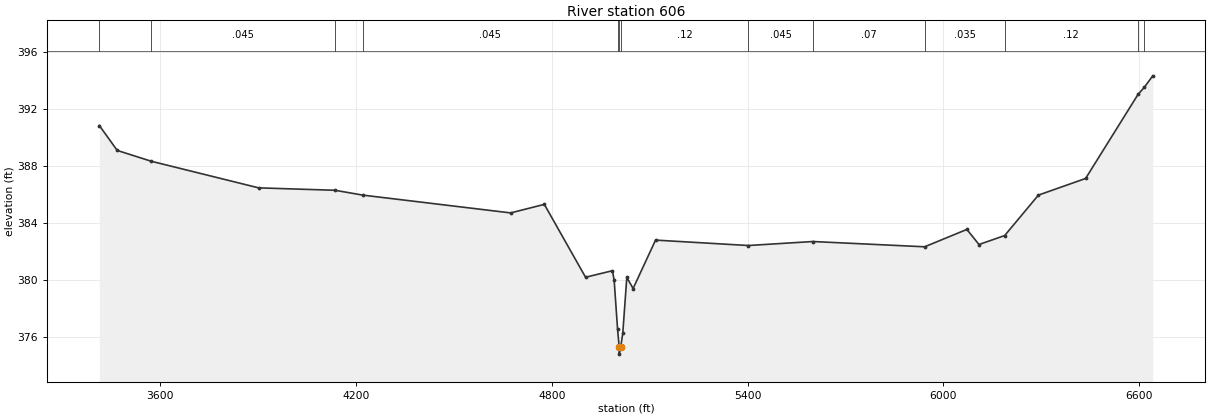
Type RM Length L Ch R = 1,606,0,0,0
BEGIN DESCRIPTION:
B19773
END DESCRIPTION:
XS GIS Cut Line= 4
      2372646.63     13749701.32      2373198.70     13748602.38
      2372979.95     13747940.92      2371854.97     13747284.69
#Sta/Elev= 30
  3413.1  390.87  3467.9  389.12  3572.1  388.36  3901.4  386.49  4135.5  386.32
  4220.8  385.98  4673.8  384.73  4777.1  385.33  4903.5  380.21  4985.8  380.67
  4991.1  380.01  5001.6  376.56  5006.5  375.31  5006.8  374.81  5011.1  375.31
  5017.5  376.26  5029.9  380.20  5049.2  379.42  5118.0  382.82  5402.4  382.44
  5600.2  382.72  5942.8  382.35  6072.3  383.57  6109.4  382.51  6188.2  383.14
  6291.5  385.98  6436.2  387.15  6596.8  393.05  6616.0  393.55  6642.0  394.36
#Mann=13,-1,0
  3413.1    0.07       0  3572.1   0.045       0  4135.5    0.12       0
  4220.8   0.045       0  5001.6    0.12       0  5006.5   0.045       0
  5011.1    0.12       0  5402.4   0.045       0  5600.2    0.07       0
  5942.8   0.035       0  6188.2    0.12       0  6596.8    0.07       0
  6616.0    0.12       0
Bank Sta=5006.5,5011.1
Exp/Cntr=0.3,0.1

Chan Stop Cuts=-1