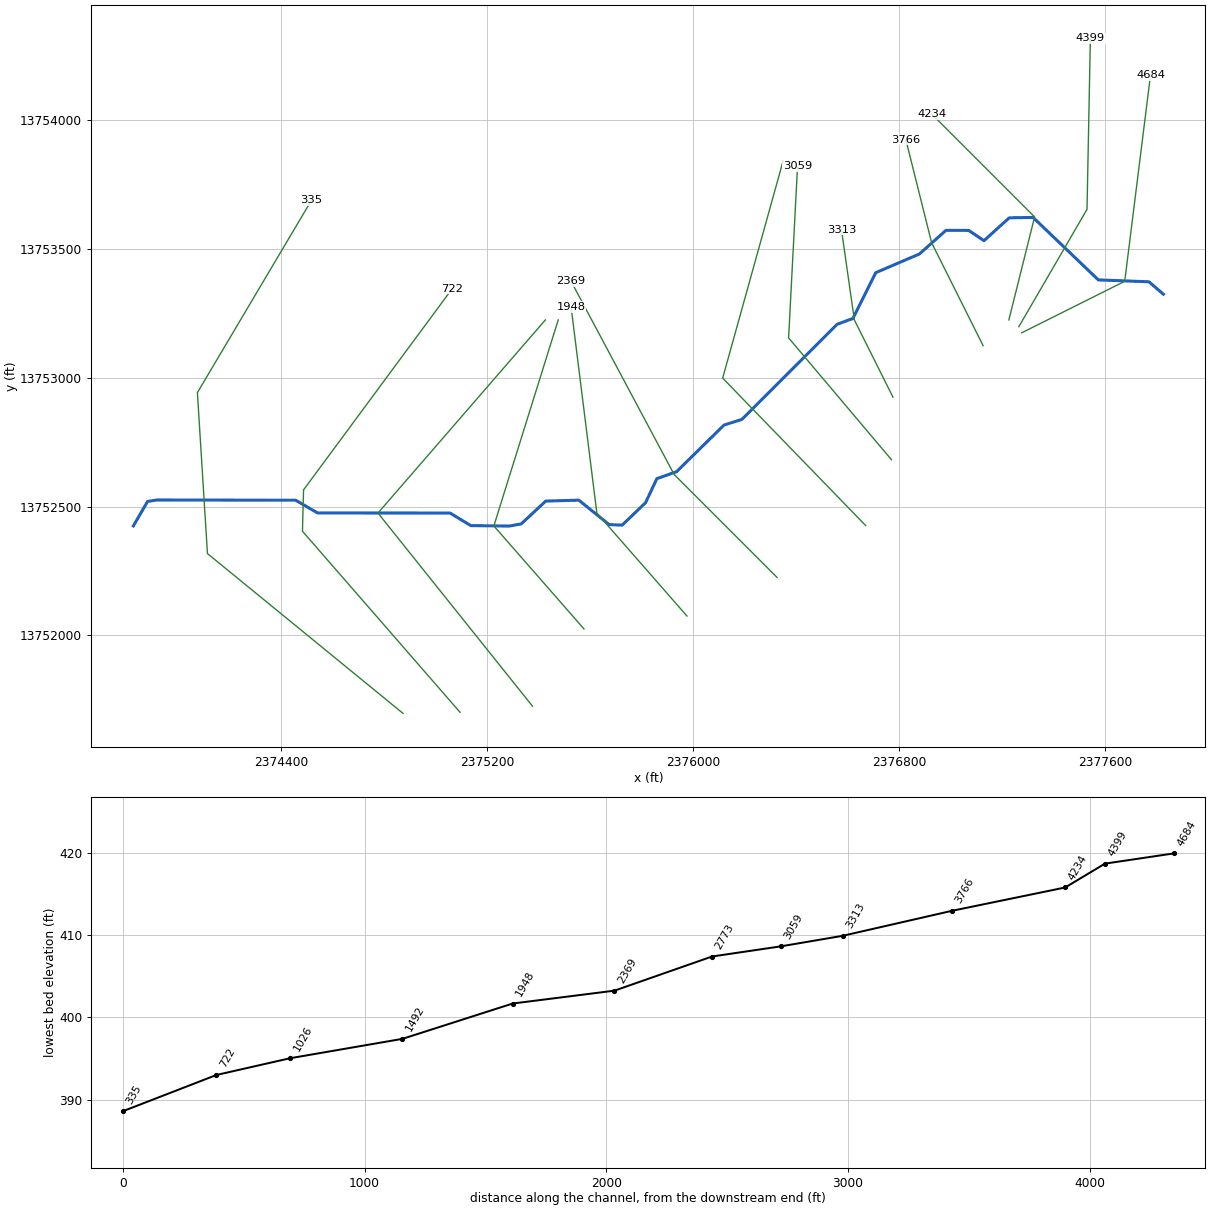
--- NASH TRIBUTARY 2.prj (project) ---

Proj Title=NASH TRIBUTARY 2 Base Level Engineering
Current Plan=p01
Default Exp/Contr=0.3,0.1
English Units
Geom File=g01
Flow File=f01
Plan File=p01
BEGIN DESCRIPTION:
NASH TRIBUTARY 2
END DESCRIPTION:

--- NASH TRIBUTARY 2.p01 (plan) ---

Plan Title=Multiple Run
Short Identifier=Multiple
Geom File=g01
Flow File=f01
Subcritical Flow
K Sum by GR= 0
Std Step Tol= 0.01
Critical Tol= 0.01
Num of Std Step Trials= 20
Max Error Tol= 0.3
Flow Tol Ratio= 0.001
Split Flow NTrial= 30
Split Flow Tol= 0.02
Split Flow Ratio= 0.02
Log Output Level= 0
Friction Slope Method= 1
Unsteady Friction Slope Method= 2
Unsteady Bridges Friction Slope Method= 1
Parabolic Critical Depth
Global Vel Dist=  1 , 1 , 1
Global Log Level= 0
CheckData=True
Encroach Param= -1, 0, 0, 0
BEGIN DESCRIPTION:
Multiple Run
END DESCRIPTION:

--- NASH TRIBUTARY 2.f01 (steady flow) ---

Flow Title=Multiple
Number of Profiles=7
Profile Names=10-year,25-year,50-year,1pct_min,100-year,1pct_plu,500-year
River Rch & RM= NASH TRIBUTARY 2,Reach-1,4684
     825    1348    1827    1198    2390    4769    4055
River Rch & RM= NASH TRIBUTARY 2,Reach-1,3313
    1145    1908    2619    1738    3468    6920    6027
Boundary for River Rch & Prof#=NASH TRIBUTARY 2,Reach-1,1
Up Type=0
Dn Type=3
Dn Slope=0.005
Boundary for River Rch & Prof#=NASH TRIBUTARY 2,Reach-1,2
Up Type=0
Dn Type=3
Dn Slope=0.005
Boundary for River Rch & Prof#=NASH TRIBUTARY 2,Reach-1,3
Up Type=0
Dn Type=3
Dn Slope=0.005
Boundary for River Rch & Prof#=NASH TRIBUTARY 2,Reach-1,4
Up Type=0
Dn Type=3
Dn Slope=0.005
Boundary for River Rch & Prof#=NASH TRIBUTARY 2,Reach-1,5
Up Type=0
Dn Type=3
Dn Slope=0.005
Boundary for River Rch & Prof#=NASH TRIBUTARY 2,Reach-1,6
Up Type=0
Dn Type=3
Dn Slope=0.005
Boundary for River Rch & Prof#=NASH TRIBUTARY 2,Reach-1,7
Up Type=0
Dn Type=3
Dn Slope=0.005

--- NASH TRIBUTARY 2.g01 (geometry) ---

Geom Title=Existing Conditions

River Reach=NASH TRIBUTARY 2,Reach-1
Reach XY= 30
      2377825.00     13753325.00      2377769.22     13753373.11
      2377572.55     13753380.46      2377319.11     13753623.04
      2377226.50     13753621.52      2377128.41     13753532.81
      2377069.11     13753572.63      2376980.90     13753573.02
      2376877.29     13753480.85      2376707.95     13753408.51
      2376619.41     13753230.61      2376558.52     13753208.27
      2376188.21     13752838.63      2376118.95     13752816.84
      2375934.66     13752635.79      2375857.95     13752608.50
      2375814.22     13752515.31      2375723.36     13752428.09
      2375672.72     13752430.08      2375555.01     13752525.06
      2375426.47     13752521.46      2375331.18     13752432.83
      2375285.20     13752424.50      2375135.51     13752426.22
      2375054.97     13752474.93      2374540.22     13752475.52
      2374454.97     13752524.93      2373914.41     13752525.65
      2373880.23     13752519.98      2373825.00     13752425.00

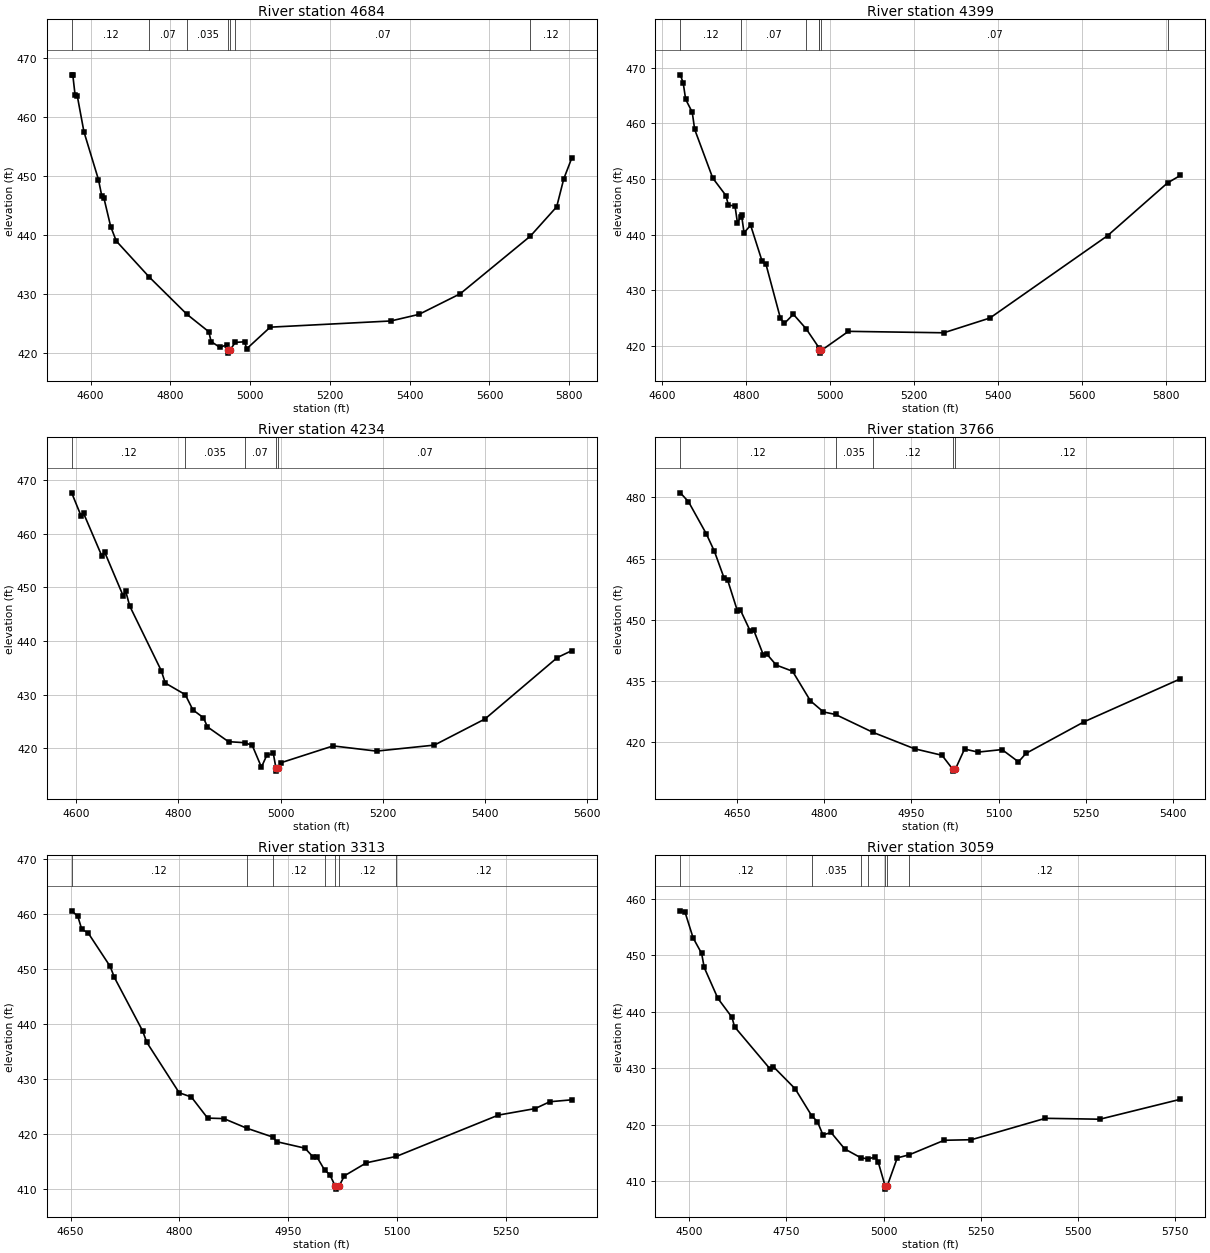
Type RM Length L Ch R = 1,4684,285,285,285
BEGIN DESCRIPTION:
NASH TRIBUTARY 2 9.0
END DESCRIPTION:
XS GIS Cut Line= 3
      2377275.01     13753175.00      2377675.00     13753375.00
      2377775.00     13754174.97
#Sta/Elev= 30
  4552.8  467.08  4555.6  467.08  4561.2  463.74  4566.8  463.54  4583.5  457.44
  4619.9  449.33  4628.3  446.54  4633.9  446.12  4650.6  441.36  4664.6  438.91
  4747.0  432.82  4841.7  426.49  4896.6  423.53  4902.2  421.88  4924.5  420.87
  4941.3  421.33  4944.6  420.41  4944.9  419.91  4949.3  420.41  4963.0  421.73
  4986.0  421.83  4991.6  420.65  5050.4  424.31  5352.7  425.36  5423.3  426.48
  5526.6  429.97  5702.4  439.74  5768.4  444.71  5786.1  449.44  5806.2  452.97
#Mann=7,-1,0
  4552.8    0.12       0  4747.0    0.07       0  4841.7   0.035       0
  4944.6    0.05       0  4949.3   0.035       0  4963.0    0.07       0
  5702.4    0.12       0
Bank Sta=4944.6,4949.3
Exp/Cntr=0.3,0.1

Type RM Length L Ch R = 1,4399,165,165,165
BEGIN DESCRIPTION:
B19782
END DESCRIPTION:
XS GIS Cut Line= 3
      2377263.79     13753198.73      2377528.56     13753654.48
      2377541.58     13754318.58
#Sta/Elev= 30
  4643.4  468.75  4650.3  467.29  4656.1  464.34  4671.8  462.02  4677.6  458.93
  4720.6  450.18  4752.1  447.02  4757.9  445.29  4773.6  445.17  4779.4  442.16
  4787.0  443.13  4789.4  443.44  4795.2  440.34  4810.9  441.68  4838.2  435.22
  4847.3  434.70  4881.9  424.93  4891.2  424.01  4912.7  425.66  4943.0  423.06
  4973.7  419.64  4974.9  419.17  4975.3  418.67  4979.6  419.17  5043.9  422.59
  5271.0  422.33  5381.0  424.99  5661.1  439.80  5804.0  449.30  5834.7  450.65
#Mann=7,-1,0
  4643.4    0.12       0  4787.0    0.07       0  4943.0   0.035       0
  4973.7    0.07       0  4974.9    0.05       0  4979.6    0.07       0
  5804.0    0.12       0
Bank Sta=4974.9,4979.6
Exp/Cntr=0.3,0.1

Type RM Length L Ch R = 1,4234,468,468,468
BEGIN DESCRIPTION:
NASH TRIBUTARY 2 8.0
END DESCRIPTION:
XS GIS Cut Line= 3
      2377224.99     13753224.96      2377325.00     13753625.00
      2376925.03     13754024.97
#Sta/Elev= 30
  4591.5  467.64  4609.6  463.40  4614.7  463.84  4650.8  455.80  4656.0  456.59
  4692.0  448.49  4697.2  449.30  4704.9  446.57  4766.8  434.48  4774.5  432.19
  4813.6  430.03  4828.6  427.18  4849.2  425.72  4857.0  424.02  4898.2  421.26
  4929.7  421.07  4944.6  420.58  4962.6  416.51  4972.9  418.69  4985.8  419.10
  4991.1  416.27  4991.5  415.77  4995.9  416.27  5001.3  417.35  5102.8  420.47
  5187.7  419.50  5300.8  420.62  5399.8  425.49  5541.3  436.94  5569.5  438.22
#Mann=5,-1,0
  4591.5    0.12       0  4813.6   0.035       0  4929.7    0.07       0
  4991.1    0.05       0  4995.9    0.07       0
Bank Sta=4991.1,4995.9
Exp/Cntr=0.3,0.1

Type RM Length L Ch R = 1,3766,453,453,453
BEGIN DESCRIPTION:
NASH TRIBUTARY 2 7.0
END DESCRIPTION:
XS GIS Cut Line= 3
      2377125.01     13753124.98      2376925.00     13753525.00
      2376825.01     13753924.95
#Sta/Elev= 30
  4552.7  481.12  4566.7  478.95  4597.4  471.07  4611.4  466.75  4628.2  460.14
  4633.8  459.85  4650.6  452.29  4656.1  452.36  4672.9  447.25  4678.5  447.62
  4695.3  441.44  4700.9  441.69  4717.6  438.92  4745.6  437.41  4776.3  430.16
  4798.7  427.44  4819.5  426.82  4883.8  422.44  4955.2  418.42  5002.5  416.82
  5020.7  413.44  5021.1  412.94  5025.5  413.44  5041.2  418.35  5064.4  417.60
  5105.6  418.22  5133.9  415.21  5146.8  417.29  5247.3  425.07  5412.2  435.55
#Mann=5,-1,0
  4552.7    0.12       0  4819.5   0.035       0  4883.8    0.12       0
  5020.7    0.05       0  5025.5    0.12       0
Bank Sta=5020.7,5025.5
Exp/Cntr=0.3,0.1

Type RM Length L Ch R = 1,3313,254,254,254
BEGIN DESCRIPTION:
NASH TRIBUTARY 2 6.0
END DESCRIPTION:
XS GIS Cut Line= 3
      2376775.00     13752924.99      2376625.00     13753225.00
      2376575.00     13753575.03
#Sta/Elev= 30
  4651.5  460.60  4659.9  459.62  4665.5  457.20  4673.9  456.63  4704.6  450.46
  4710.2  448.50  4749.3  438.71  4754.9  436.66  4799.6  427.46  4816.4  426.68
  4838.8  422.84  4861.1  422.75  4892.7  421.00  4928.7  419.38  4933.8  418.55
  4972.9  417.36  4984.1  415.76  4989.4  415.76  4999.9  413.39  5007.1  412.55
  5014.8  410.40  5015.1  409.90  5019.7  410.40  5027.3  412.33  5057.6  414.70
  5099.0  415.87  5239.5  423.39  5290.0  424.57  5310.2  425.82  5340.5  426.17
#Mann=7,-1,0
  4651.5    0.12       0  4892.7   0.035       0  4928.7    0.12       0
  4999.9    0.12       0  5014.8    0.05       0  5019.7    0.12       0
  5099.0    0.12       0
Bank Sta=5014.8,5019.7
Exp/Cntr=0.3,0.1

Type RM Length L Ch R = 1,3059,286,286,286
BEGIN DESCRIPTION:
B19781
END DESCRIPTION:
XS GIS Cut Line= 3
      2376768.99     13752682.28      2376369.70     13753155.35
      2376404.33     13753821.90
#Sta/Elev= 30
  4477.2  457.91  4489.2  457.70  4510.1  453.12  4532.1  450.36  4538.6  447.89
  4573.8  442.41  4610.1  439.05  4616.7  437.38  4709.0  429.84  4716.3  430.33
  4772.7  426.39  4815.1  421.63  4829.9  420.58  4844.2  418.22  4865.0  418.66
  4900.1  415.75  4940.8  414.21  4959.9  413.97  4978.2  414.32  4985.9  413.52
  5004.3  409.13  5004.6  408.63  5009.2  409.13  5035.3  414.16  5066.5  414.72
  5156.0  417.28  5226.1  417.38  5416.3  421.17  5556.5  421.01  5763.7  424.54
#Mann=7,-1,0
  4477.2    0.12       0  4815.1   0.035       0  4940.8    0.12       0
  4959.9    0.12       0  5004.3    0.05       0  5009.2    0.12       0
  5066.5    0.12       0
Bank Sta=5004.3,5009.2
Exp/Cntr=0.3,0.1

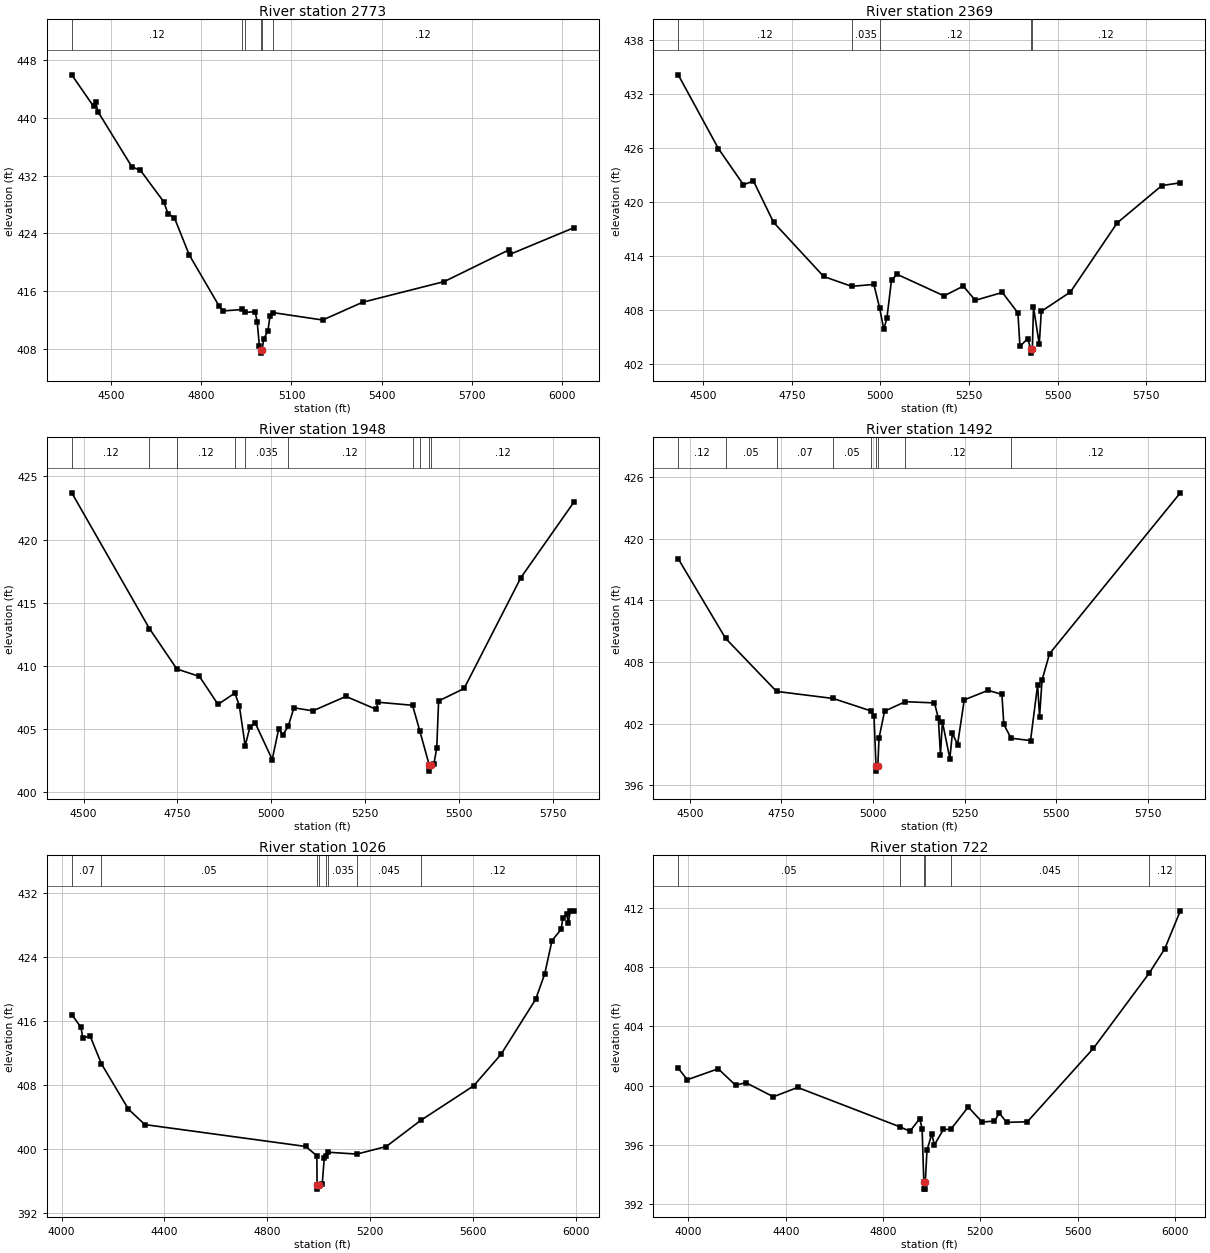
Type RM Length L Ch R = 1,2773,404,404,404
BEGIN DESCRIPTION:
NASH TRIBUTARY 2 5.0
END DESCRIPTION:
XS GIS Cut Line= 3
      2376669.15     13752426.21      2376113.63     13752999.10
      2376347.84     13753840.51
#Sta/Elev= 30
  4368.7  445.97  4441.5  441.58  4448.6  442.14  4455.6  440.88  4568.8  433.22
  4597.1  432.74  4674.8  428.37  4688.9  426.74  4710.3  426.16  4759.7  421.01
  4858.7  413.95  4872.8  413.24  4936.7  413.44  4946.7  413.04  4979.1  413.13
  4986.0  411.73  4993.2  408.39  4997.7  407.89  4998.1  407.39  5002.6  407.89
  5007.4  409.32  5021.5  410.46  5028.5  412.47  5037.6  413.01  5204.0  411.98
  5336.7  414.44  5608.8  417.31  5823.0  421.68  5828.2  421.10  6040.1  424.77
#Mann=6,-1,0
  4368.7    0.12       0  4936.7   0.035       0  4946.7    0.12       0
  4997.7    0.05       0  5002.6    0.12       0  5037.6    0.12       0
Bank Sta=4997.7,5002.6
Exp/Cntr=0.3,0.1

Type RM Length L Ch R = 1,2369,421,421,421
BEGIN DESCRIPTION:
NASH TRIBUTARY 2 4.0
END DESCRIPTION:
XS GIS Cut Line= 3
      2376325.03     13752224.97      2375925.00     13752625.00
      2375525.01     13753374.98
#Sta/Elev= 30
  4429.9  434.11  4543.1  425.93  4613.8  421.92  4642.1  422.33  4698.6  417.75
  4840.1  411.74  4918.9  410.65  4981.5  410.86  4997.8  408.25  5009.4  405.88
  5018.3  407.12  5031.4  411.40  5047.7  411.97  5179.4  409.59  5233.6  410.67
  5267.6  409.10  5343.8  409.97  5387.7  407.70  5393.4  403.99  5415.3  404.85
  5423.5  403.74  5423.8  403.24  5428.4  403.74  5431.6  408.32  5447.9  404.24
  5453.6  407.87  5535.7  410.02  5667.5  417.68  5793.6  421.83  5845.6  422.13
#Mann=5,-1,0
  4429.9    0.12       0  4918.9   0.035       0  4997.8    0.12       0
  5423.5    0.05       0  5428.4    0.12       0
Bank Sta=5423.5,5428.4
Exp/Cntr=0.3,0.1

Type RM Length L Ch R = 1,1948,456,456,456
BEGIN DESCRIPTION:
NASH TRIBUTARY 2 3.0
END DESCRIPTION:
XS GIS Cut Line= 3
      2375974.97     13752075.03      2375625.00     13752475.00
      2375525.00     13753275.01
#Sta/Elev= 30
  4468.6  423.70  4675.5  412.96  4748.6  409.76  4808.8  409.17  4858.2  406.96
  4903.3  407.86  4915.1  406.85  4930.6  403.69  4943.6  405.20  4957.8  405.46
  5002.6  402.60  5020.2  405.05  5030.3  404.52  5045.1  405.22  5060.5  406.69
  5110.9  406.45  5199.1  407.59  5279.7  406.57  5284.8  407.13  5376.6  406.89
  5395.8  404.87  5420.8  402.18  5421.2  401.68  5425.8  402.18  5433.4  402.25
  5441.0  403.50  5446.0  407.23  5514.0  408.22  5665.2  416.99  5806.3  422.96
#Mann=10,-1,0
  4468.6    0.12       0  4675.5    0.07       0  4748.6    0.12       0
  4903.3    0.07       0  4930.6   0.035       0  5045.1    0.12       0
  5376.6    0.12       0  5395.8    0.12       0  5420.8   0.035       0
  5425.8    0.12       0
Bank Sta=5420.8,5425.8
Exp/Cntr=0.3,0.1

Type RM Length L Ch R = 1,1492,466,466,466
BEGIN DESCRIPTION:
NASH TRIBUTARY 2 2.0
END DESCRIPTION:
XS GIS Cut Line= 3
      2375575.00     13752025.00      2375225.00     13752425.00
      2375475.01     13753225.04
#Sta/Elev= 30
  4468.7  418.03  4597.8  410.30  4736.8  405.14  4891.5  404.45  4993.8  403.25
  5002.8  402.74  5008.2  397.89  5008.5  397.39  5013.2  397.89  5016.4  400.59
  5031.6  403.22  5088.2  404.14  5167.8  404.02  5178.3  402.52  5184.1  398.99
  5189.3  402.19  5209.7  398.61  5216.6  401.06  5230.7  399.97  5249.0  404.32
  5314.0  405.24  5351.7  404.85  5356.9  401.93  5376.7  400.59  5429.8  400.36
  5449.1  405.77  5454.4  402.67  5461.2  406.24  5481.6  408.80  5838.4  424.44
#Mann=9,-1,0
  4468.7    0.12       0  4597.8    0.05       0  4736.8    0.07       0
  4891.5    0.05       0  4993.8   0.035       0  5008.2   0.035       0
  5013.2   0.035       0  5088.2    0.12       0  5376.7    0.12       0
Bank Sta=5008.2,5013.2
Exp/Cntr=0.3,0.1

Type RM Length L Ch R = 1,1026,304,304,304
BEGIN DESCRIPTION:
NASH TRIBUTARY 2 1.0
END DESCRIPTION:
XS GIS Cut Line= 3
      2375375.03     13751724.96      2374775.00     13752475.00
      2375425.01     13753225.01
#Sta/Elev= 30
  4039.5  416.80  4075.6  415.20  4082.0  413.88  4110.8  414.13  4155.0  410.65
  4259.7  405.01  4323.7  403.08  4949.6  400.35  4992.8  399.19  4993.7  395.53
  4994.2  395.03  4999.9  395.53  5013.8  395.66  5021.4  398.85  5027.3  399.17
  5037.6  399.63  5148.2  399.40  5262.6  400.34  5397.7  403.62  5602.6  407.91
  5709.0  411.83  5843.9  418.70  5879.0  421.85  5907.5  426.02  5942.6  427.42
  5950.2  428.86  5964.5  429.30  5971.1  428.23  5978.7  429.73  5992.5  429.74
#Mann=8,-1,0
  4039.5    0.07       0  4155.0    0.05       0  4993.7    0.05       0
  4999.9    0.05       0  5027.3    0.07       0  5037.6   0.035       0
  5148.2   0.045       0  5397.7    0.12       0
Bank Sta=4993.7,4999.9
Exp/Cntr=0.3,0.1

Type RM Length L Ch R = 1,722,387,387,387
BEGIN DESCRIPTION:
B19780
END DESCRIPTION:
XS GIS Cut Line= 4
      2375093.69     13751701.32      2374481.68     13752404.48
      2374486.02     13752565.07      2375063.27     13753346.30
#Sta/Elev= 30
  3958.1  401.17  3995.2  400.39  4122.4  401.13  4193.6  400.02  4236.3  400.19
  4349.3  399.24  4449.0  399.87  4869.2  397.21  4910.8  396.91  4950.8  397.76
  4960.8  397.08  4967.7  393.50  4968.2  393.00  4973.4  393.00  4973.9  393.50
  4980.8  395.63  5000.9  396.74  5010.9  395.98  5048.4  397.03  5078.9  397.04
  5150.3  398.55  5207.7  397.53  5257.8  397.60  5278.6  398.13  5307.9  397.51
  5393.5  397.55  5664.9  402.51  5894.4  407.59  5958.5  409.24  6022.3  411.80
#Mann=6,-1,0
  3958.1    0.05       0  4869.2   0.035       0  4967.7    0.05       0
  4973.9   0.035       0  5078.9   0.045       0  5894.4    0.12       0
Bank Sta=4967.7,4973.9
Exp/Cntr=0.3,0.1

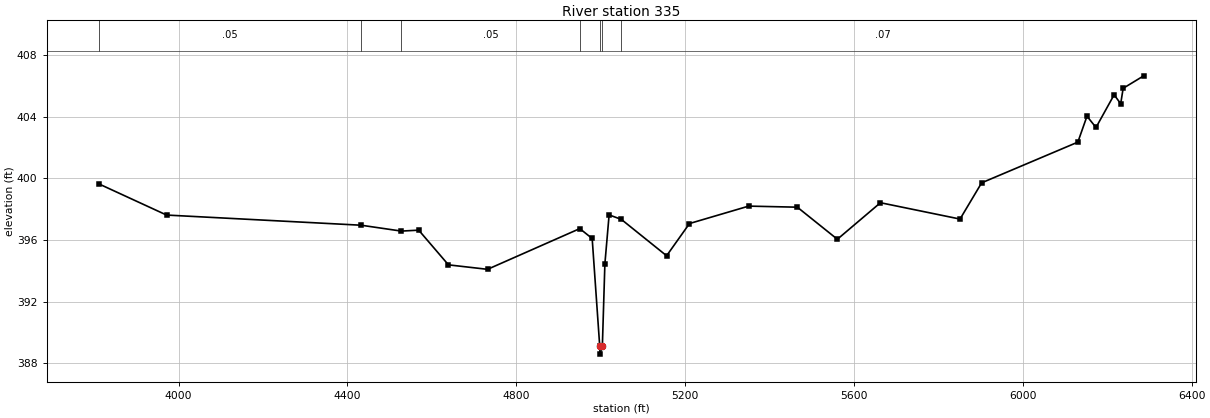
Type RM Length L Ch R = 1,335,0,0,0
BEGIN DESCRIPTION:
B19779
END DESCRIPTION:
XS GIS Cut Line= 4
      2374872.28     13751697.04      2374112.76     13752317.67
      2374073.70     13752942.67      2374516.41     13753689.21
#Sta/Elev= 30
  3811.4  399.64  3971.7  397.62  4432.8  396.96  4527.8  396.58  4569.0  396.64
  4639.4  394.39  4732.0  394.10  4950.5  396.74  4979.9  396.10  4997.8  389.10
  4998.3  388.60  5004.0  389.10  5010.0  394.46  5020.0  397.63  5048.9  397.34
  5156.2  394.98  5210.4  397.07  5350.7  398.20  5465.9  398.13  5560.7  396.05
  5662.8  398.42  5851.3  397.36  5902.5  399.71  6130.4  402.35  6152.0  404.03
  6173.4  403.30  6216.3  405.42  6231.9  404.84  6237.7  405.84  6286.4  406.65
#Mann=7,-1,0
  3811.4    0.05       0  4432.8   0.035       0  4527.8    0.05       0
  4950.5   0.035       0  4997.8   0.035       0  5004.0   0.035       0
  5048.9    0.07       0
Bank Sta=4997.8,5004
Exp/Cntr=0.3,0.1

Chan Stop Cuts=-1