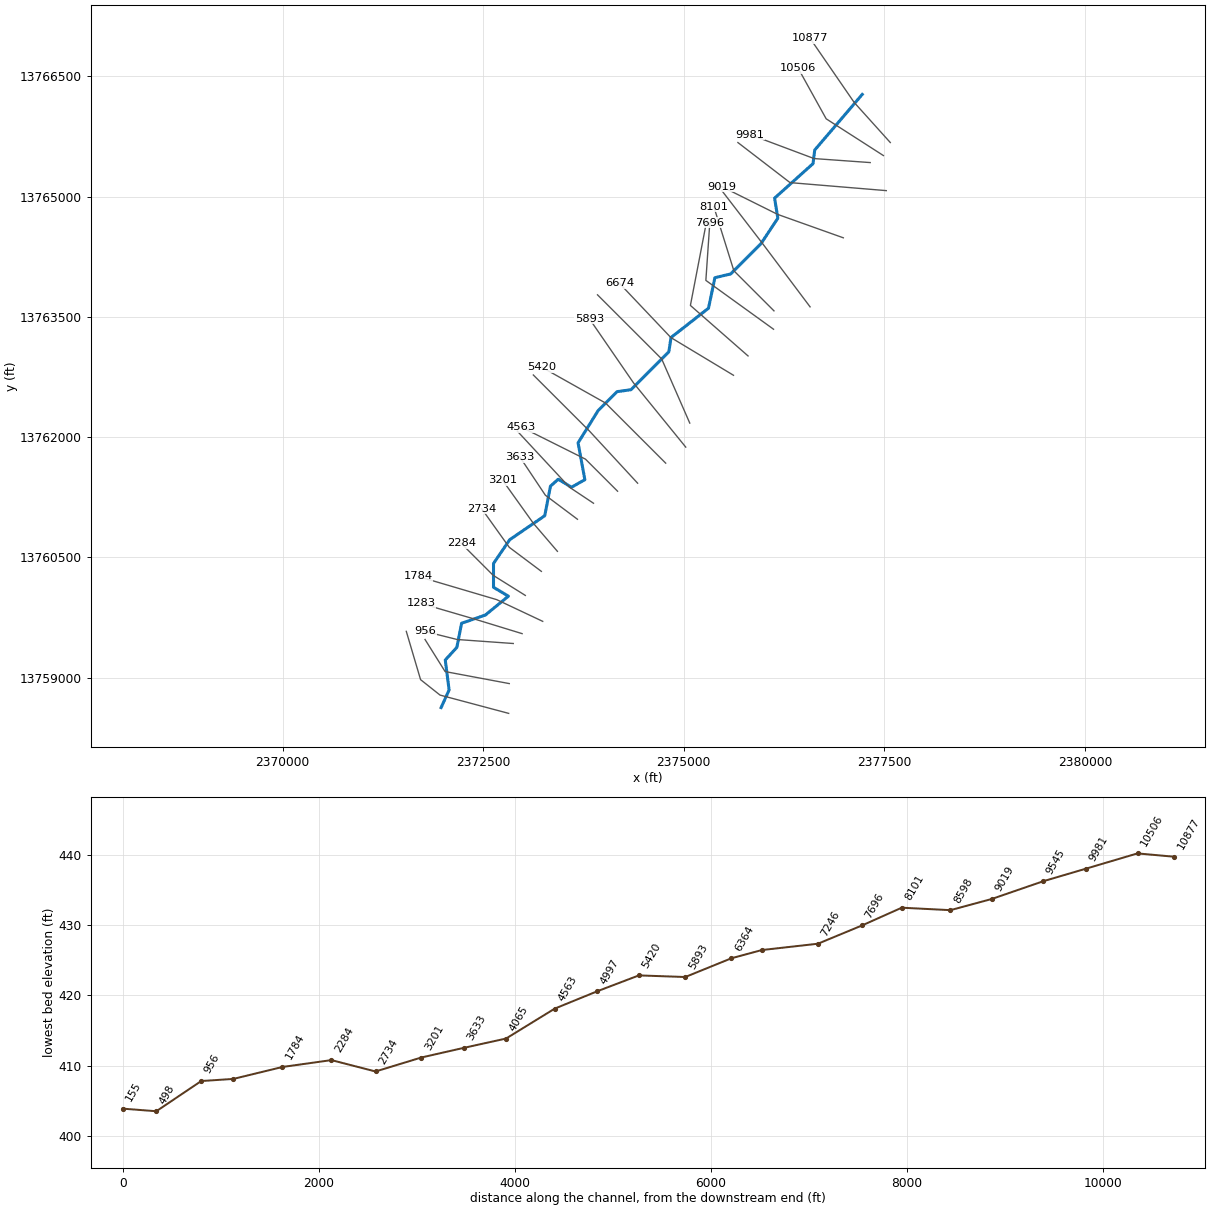
--- NASH TRIBUTARY 3.prj (project) ---

Proj Title=NASH TRIBUTARY 3 Base Level Engineering
Current Plan=p01
Default Exp/Contr=0.3,0.1
English Units
Geom File=g01
Flow File=f01
Plan File=p01
Y Axis Title=Elevation
X Axis Title(PF)=Main Channel Distance
X Axis Title(XS)=Station
BEGIN DESCRIPTION:
NASH TRIBUTARY 3
END DESCRIPTION:
DSS Export Rating Curves= 0
DSS Export Rating Curve Sorted= 0
DSS Export Volume Flow Curves= 0
DXF OffsetX= 0
DXF OffsetY= 0
DXF ScaleX= 1
DXF ScaleY= 10

--- NASH TRIBUTARY 3.p01 (plan) ---

Plan Title=Multiple Run
Short Identifier=Multiple
Geom File=g01
Flow File=f01
Subcritical Flow
K Sum by GR= 0
Std Step Tol= 0.01
Critical Tol= 0.01
Num of Std Step Trials= 20
Max Error Tol= 0.3
Flow Tol Ratio= 0.001
Split Flow NTrial= 30
Split Flow Tol= 0.02
Split Flow Ratio= 0.02
Log Output Level= 0
Friction Slope Method= 1
Unsteady Friction Slope Method= 2
Unsteady Bridges Friction Slope Method= 1
Parabolic Critical Depth
Global Vel Dist=  1 , 1 , 1
Global Log Level= 0
CheckData=True
Encroach Param= -1, 0, 0, 0
BEGIN DESCRIPTION:
Multiple Run
END DESCRIPTION:

--- NASH TRIBUTARY 3.f01 (steady flow) ---

Flow Title=Multiple
Number of Profiles=7
Profile Names=10-year,25-year,50-year,1pct_min,100-year,1pct_plu,500-year
River Rch & RM= NASH TRIBUTARY 3,Reach-1,10877
     555     875    1157     740    1477    2947    2383
River Rch & RM= NASH TRIBUTARY 3,Reach-1,8598
     708    1134    1514     978    1951    3894    3210
River Rch & RM= NASH TRIBUTARY 3,Reach-1,6674
    1483    2470    3387    2242    4473    8924    7731
River Rch & RM= NASH TRIBUTARY 3,Reach-1,3201
    1629    2724    3746    2485    4958    9893    8611
Boundary for River Rch & Prof#=NASH TRIBUTARY 3,Reach-1,1
Up Type=0
Dn Type=3
Dn Slope=0.005
Boundary for River Rch & Prof#=NASH TRIBUTARY 3,Reach-1,2
Up Type=0
Dn Type=3
Dn Slope=0.005
Boundary for River Rch & Prof#=NASH TRIBUTARY 3,Reach-1,3
Up Type=0
Dn Type=3
Dn Slope=0.005
Boundary for River Rch & Prof#=NASH TRIBUTARY 3,Reach-1,4
Up Type=0
Dn Type=3
Dn Slope=0.005
Boundary for River Rch & Prof#=NASH TRIBUTARY 3,Reach-1,5
Up Type=0
Dn Type=3
Dn Slope=0.005
Boundary for River Rch & Prof#=NASH TRIBUTARY 3,Reach-1,6
Up Type=0
Dn Type=3
Dn Slope=0.005
Boundary for River Rch & Prof#=NASH TRIBUTARY 3,Reach-1,7
Up Type=0
Dn Type=3
Dn Slope=0.005

--- NASH TRIBUTARY 3.g01 (geometry) ---

Geom Title=Existing Conditions
Program Version=4.10

River Reach=NASH TRIBUTARY 3,Reach-1
Reach XY= 30
        2377225.       13766275.      2376632.82     13765581.19
      2376611.63     13765411.68      2376132.64     13764981.45
      2376173.04     13764730.89      2375964.24     13764415.32
       2375584.8     13764035.48      2375388.47     13763988.76
      2375308.71     13763608.26      2374841.09     13763242.06
      2374814.52      13763065.2      2374342.14     13762591.28
      2374168.81     13762567.18      2373932.86     13762331.17
      2373682.79     13761928.42      2373767.31     13761468.52
      2373599.97      13761374.5      2373435.63     13761474.45
      2373338.61     13761388.25       2373267.2     13761018.79
      2372830.14     13760719.82      2372628.55     13760423.53
      2372628.44     13760126.22      2372814.11     13760015.14
      2372527.45     13759780.47      2372230.52     13759677.44
      2372171.46     13759376.47      2372027.06     13759219.15
      2372075.11     13758845.09        2371975.       13758625.

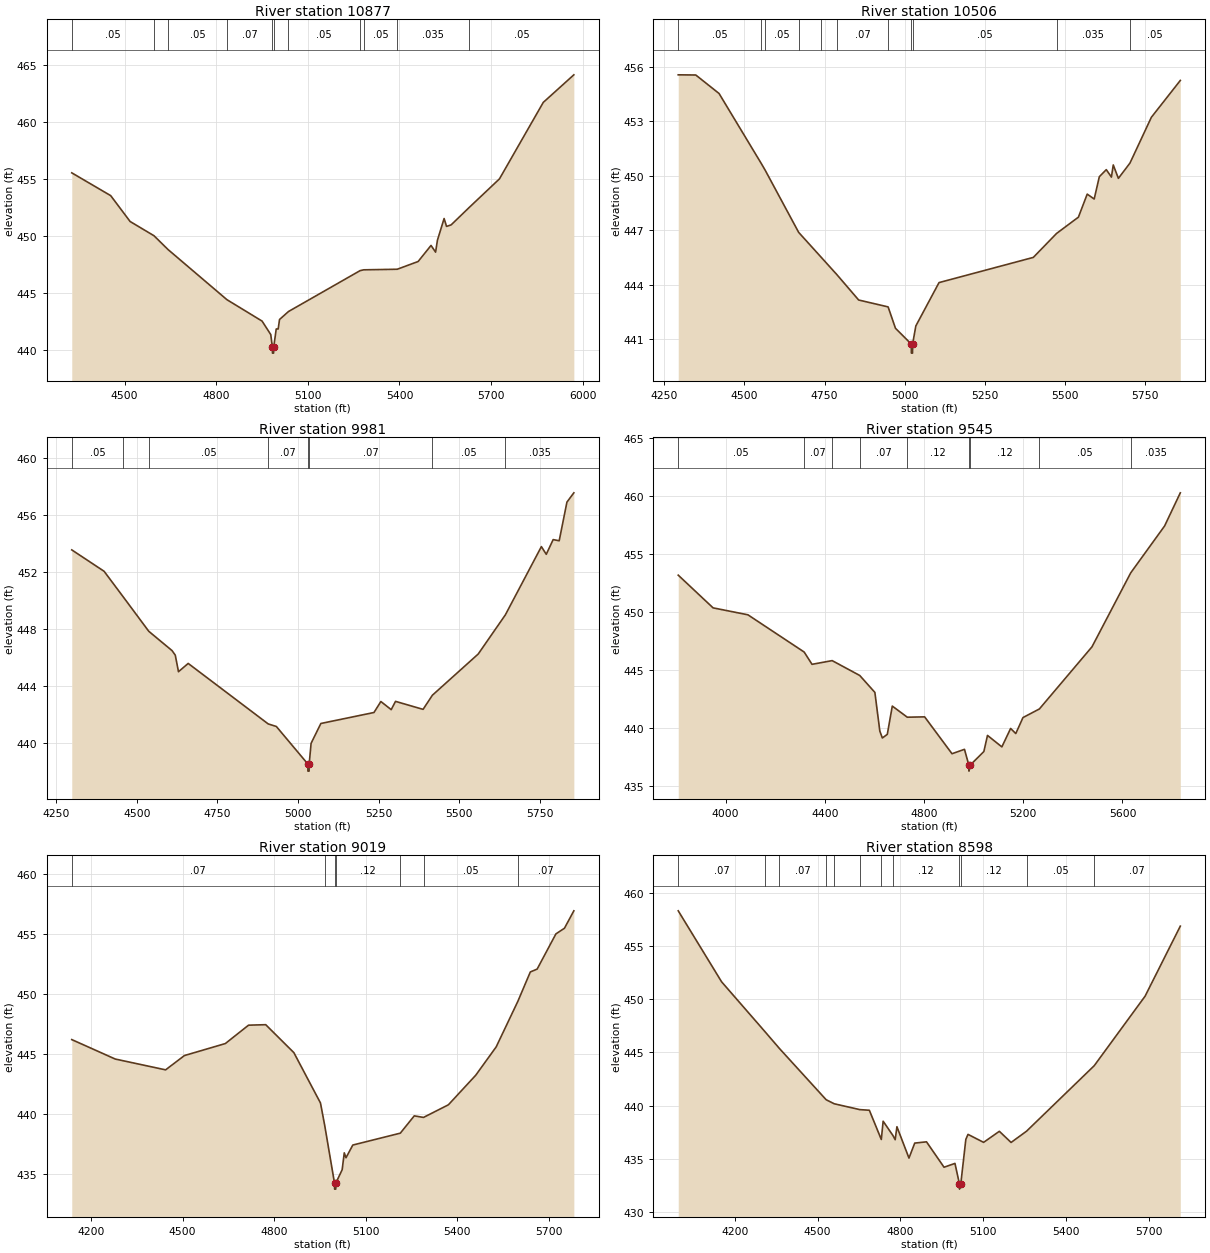
Type RM Length L Ch R = 1 ,10877   ,371,371,371
BEGIN DESCRIPTION:
NASH TRIBUTARY 3 22.0
END DESCRIPTION:
XS GIS Cut Line= 3
        2377575.       13765675.        2377125.       13766175.
        2376575.     13766974.99
#Sta/Elev= 30
  4327.3  455.57  4454.7  453.57  4518.3   451.3  4596.5  450.05  4642.4  448.84
  4835.2  444.44  4950.3  442.56  4978.7  441.38  4984.1  440.25  4984.4  439.75
  4987.9  439.75  4988.2  440.25  4996.6  441.87    5003  441.87  5007.4   442.7
  5036.7   443.4  5271.2  446.99  5283.1  447.06  5392.6  447.11  5461.1  447.79
  5503.3   449.2  5518.2  448.61  5524.3  449.66  5546.1  451.56  5554.1  450.87
    5569     451  5628.6  452.54  5727.3  455.04  5870.7  461.75  5970.8  464.17
#Mann= 11 ,-1 , 0
  4327.3     .05       0  4596.5     .07       0  4642.4     .05       0
  4835.2     .07       0  4984.1     .05       0  4988.2     .07       0
  5036.7     .05       0  5271.2    .035       0  5283.1     .05       0
  5392.6    .035       0  5628.6     .05       0
Bank Sta=4984.1,4988.2
XS Rating Curve= 0 ,0
Exp/Cntr=0.3,0.1

Type RM Length L Ch R = 1 ,10506   ,525,525,525
BEGIN DESCRIPTION:
NASH TRIBUTARY 3 21.0
END DESCRIPTION:
XS GIS Cut Line= 3
      2377489.34     13765512.46      2376775.76     13765970.82
      2376427.08     13766600.52
#Sta/Elev= 30
  4293.1  455.57  4347.9  455.56  4420.6  454.54  4553.1  450.66  4565.2  450.29
  4669.2  446.88  4739.4  445.51  4788.5  444.55  4856.5  443.15  4948.5  442.77
  4971.5  441.59  5020.9  440.72  5021.2  440.22  5024.8  440.22    5025  440.72
  5035.1  441.72  5107.5  444.11    5402   445.5  5474.5  446.82  5542.8  447.72
  5570.3  448.99  5592.1  448.72  5608.1  449.95  5629.8  450.34  5645.9  449.93
  5651.6   450.6  5667.6  449.86  5703.7   450.7  5770.7  453.23    5861  455.26
#Mann= 11 ,-1 , 0
  4293.1     .05       0  4553.1     .07       0  4565.2     .05       0
  4669.2     .07       0  4739.4     .05       0  4788.5     .07       0
  4948.5     .05       0  5020.9     .05       0    5025     .05       0
  5474.5    .035       0  5703.7     .05       0
Bank Sta=5020.9,5025
XS Rating Curve= 0 ,0
Exp/Cntr=0.3,0.1

Type RM Length L Ch R = 1 ,9981    ,436,436,436
BEGIN DESCRIPTION:
NASH TRIBUTARY 3 20.0
END DESCRIPTION:
XS GIS Cut Line= 3
      2377324.98       13765425.        2376625.       13765475.
      2375824.96     13765775.01
#Sta/Elev= 30
  4298.6  453.56  4398.8  452.06  4457.3  450.29  4537.4  447.85  4609.4   446.5
  4619.4  446.18  4629.4  445.02  4659.5   445.6  4907.4  441.36  4932.7  441.18
  5030.3  438.55  5030.6  438.05  5034.2  438.05  5034.5  438.55  5040.4     440
  5070.7  441.39  5235.3  442.16  5256.7  442.93  5288.7  442.36  5302.1  442.94
  5387.5  442.38  5416.3  443.37  5558.4  446.26  5642.4     449  5754.2  453.79
  5769.3  453.25  5790.7  454.28  5809.4   454.2  5833.4  456.91  5854.8  457.56
#Mann= 8 ,-1 , 0
  4298.6     .05       0  4457.3     .07       0  4537.4     .05       0
  4907.4     .07       0  5030.3     .05       0  5034.5     .07       0
  5416.3     .05       0  5642.4    .035       0
Bank Sta=5030.3,5034.5
XS Rating Curve= 0 ,0
Exp/Cntr=0.3,0.1

Type RM Length L Ch R = 1 ,9545    ,526,526,526
BEGIN DESCRIPTION:
NASH TRIBUTARY 3 19.0
END DESCRIPTION:
XS GIS Cut Line= 3
      2377525.01       13765075.        2376325.       13765175.
      2375675.03     13765674.98
#Sta/Elev= 30
  3809.1  453.16  3949.6  450.34  4090.1  449.74  4316.8  446.53  4348.5  445.47
  4429.7  445.79  4540.8  444.51  4601.9  443.05  4621.9  439.71    4632  439.12
    4652  439.43  4672.1  441.87  4732.6  440.91  4802.5  440.94  4912.9  437.76
  4963.1  438.14    4981  436.76  4981.3  436.26  4985.3  436.76  5041.3  437.95
  5055.9  439.34  5113.9  438.35  5149.2  439.94    5170   439.5    5199  440.88
  5265.1  441.62  5477.2  446.98  5633.4  453.36  5769.9   457.4  5833.3  460.26
#Mann= 9 ,-1 , 0
  3809.1     .05       0  4316.8     .07       0  4429.7     .05       0
  4540.8     .07       0  4732.6     .12       0    4981     .05       0
  4985.3     .12       0  5265.1     .05       0  5633.4    .035       0
Bank Sta=4981,4985.3
XS Rating Curve= 0 ,0
Exp/Cntr=0.3,0.1

Type RM Length L Ch R = 1 ,9019    ,421,421,421
BEGIN DESCRIPTION:
NASH TRIBUTARY 3 18.0
END DESCRIPTION:
XS GIS Cut Line= 3
      2376989.34     13764486.43      2376171.59     13764778.11
        2375475.       13765125.
#Sta/Elev= 30
  4136.3  446.18  4278.9  444.56    4444  443.66  4505.7  444.85  4639.9  445.85
    4716  447.38  4772.3  447.42  4864.7  445.09  4951.9   440.9  4965.9  439.01
  4997.9  434.23  4998.2  433.73  5001.9  433.73  5002.2  434.23    5023  435.35
  5029.9  436.75  5035.5  436.34  5057.9   437.4  5213.7  438.39  5259.4  439.83
  5289.7   439.7  5371.3  440.75  5460.9  443.21    5528  445.57  5599.2  449.37
    5640  451.81  5662.4  452.05  5723.9  454.98  5751.9  455.45  5782.7   456.9
#Mann= 7 ,-1 , 0
  4136.3     .07       0  4965.9     .12       0  4997.9     .05       0
  5002.2     .12       0  5213.7     .07       0  5289.7     .05       0
  5599.2     .07       0
Bank Sta=4997.9,5002.2
XS Rating Curve= 0 ,0
Exp/Cntr=0.3,0.1

Type RM Length L Ch R = 1 ,8598    ,497,497,497
BEGIN DESCRIPTION:
NASH TRIBUTARY 3 17.0
END DESCRIPTION:
XS GIS Cut Line= 3
      2376575.03     13763624.96        2375975.       13764425.
      2375475.01     13765074.99
#Sta/Elev= 30
  3994.8  458.32  4152.1  451.64    4308  446.99  4361.7  445.37    4531  440.55
  4560.2  440.17  4653.1  439.62  4687.6  439.56    4731  436.81  4737.6  438.53
  4773.5  437.17  4781.3  436.79  4787.6  438.01  4831.3  435.06  4852.1  436.47
  4894.8  436.59  4958.4   434.2    4998  434.56  5014.1  432.64  5014.5  432.14
  5019.1  432.64  5037.4  436.82  5045.3  437.29  5101.8  436.54  5158.9  437.58
  5201.4  436.53  5257.5  437.59  5502.8  443.75  5687.2  450.29  5814.9  456.88
#Mann= 12 ,-1 , 0
  3994.8     .07       0    4308    .035       0  4361.7     .07       0
    4531     .12       0  4560.2     .07       0  4653.1     .12       0
    4731     .07       0  4773.5     .12       0  5014.1     .05       0
  5019.1     .12       0  5257.5     .05       0  5502.8     .07       0
Bank Sta=5014.1,5019.1
XS Rating Curve= 0 ,0
Exp/Cntr=0.3,0.1

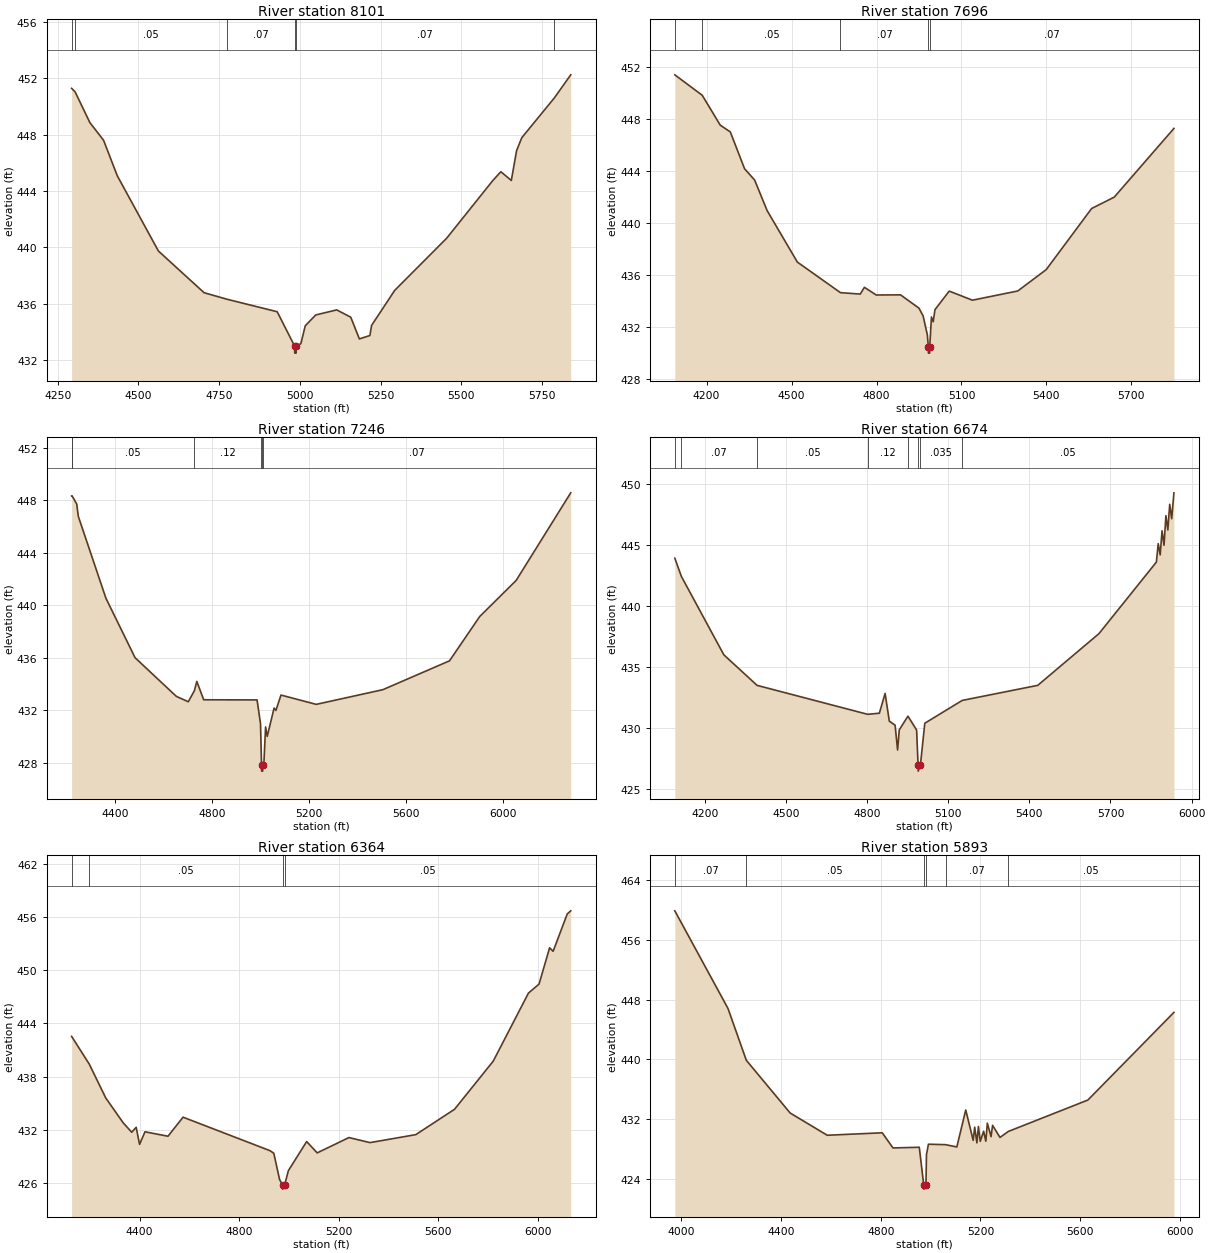
Type RM Length L Ch R = 1 ,8101    ,405,405,405
BEGIN DESCRIPTION:
NASH TRIBUTARY 3 16.0
END DESCRIPTION:
XS GIS Cut Line= 3
      2376124.97     13763575.03        2375625.       13764075.
      2375375.01     13764874.98
#Sta/Elev= 30
  4293.2  451.29    4304  451.04  4349.7  448.86  4392.2   447.6  4434.6  445.08
  4561.9  439.74  4703.3  436.78  4775.3  436.31  4929.6  435.43  4983.6  432.99
    4984  432.49  4988.2  432.49  4988.6  432.99  5002.9  433.16  5016.5  434.43
    5049   435.2  5113.9  435.56  5157.4  435.04  5184.1   433.5  5216.6  433.74
  5221.9  434.46  5293.6  436.95  5454.4  440.65  5597.4  444.75  5622.1  445.37
  5654.5  444.75  5670.8  446.87    5687  447.79  5787.7  450.61  5838.4  452.25
#Mann= 6 ,-1 , 0
  4293.2     .07       0    4304     .05       0  4775.3     .07       0
  4983.6     .05       0  4988.6     .07       0  5787.7    .035       0
Bank Sta=4983.6,4988.6
XS Rating Curve= 0 ,0
Exp/Cntr=0.3,0.1

Type RM Length L Ch R = 1 ,7696    ,450,450,450
BEGIN DESCRIPTION:
NASH TRIBUTARY 3 15.0
END DESCRIPTION:
XS GIS Cut Line= 3
      2376119.54     13763345.79      2375275.76     13763955.19
        2375325.     13764674.97
#Sta/Elev= 30
  4087.9  451.36  4184.6  449.79  4248.3  447.49  4283.8  446.97  4334.1  444.14
  4369.7  443.27  4413.8  440.92  4520.6  436.96  4672.8  434.61  4742.6   434.5
  4757.3  435.02  4799.1  434.43  4884.9  434.44  4949.9  433.42  4964.6  432.82
  4979.4  431.38    4983  430.46  4983.4  429.96  4987.7  429.96    4988  430.46
    4994  432.74  5000.2  432.37  5006.4   433.3  5056.7  434.73  5138.6  434.03
  5298.9  434.74  5399.2  436.38  5559.6  441.08  5639.7  441.96  5850.2  447.24
#Mann= 5 ,-1 , 0
  4087.9     .07       0  4184.6     .05       0  4672.8     .07       0
    4983     .05       0    4988     .07       0
Bank Sta=4983,4988
XS Rating Curve= 0 ,0
Exp/Cntr=0.3,0.1

Type RM Length L Ch R = 1 ,7246    ,572,572,572
BEGIN DESCRIPTION:
B19785
END DESCRIPTION:
XS GIS Cut Line= 3
      2375801.77     13763012.51      2375083.05     13763642.69
      2375291.39     13764726.07
#Sta/Elev= 30
  4220.5  448.34  4222.4  448.35  4241.6  447.73  4248.2  446.78  4362.1  440.54
  4482.2  436.01  4652.5  433.06  4701.9  432.65  4726.9  433.49    4737   434.2
  4765.4   432.8  4985.6  432.79  4999.8  430.97  5003.6  428.09  5003.9  427.86
  5004.3  427.36  5008.6  427.36    5009  427.86  5014.1  428.11  5020.7  430.73
  5027.5  430.01  5055.8  432.17  5063.4  431.99  5084.3  433.16  5229.6  432.45
  5504.6  433.57  5779.5  435.77  5904.2  439.15  6054.5   441.9  6279.6  448.58
#Mann= 6 ,-1 , 0
  4220.5     .07       0  4222.4     .05       0  4726.9     .12       0
  5003.6     .07       0  5003.9     .05       0    5009     .07       0
Bank Sta=5003.9,5009
XS Rating Curve= 0 ,0
Exp/Cntr=0.3,0.1

Type RM Length L Ch R = 1 ,6674    ,310,310,310
BEGIN DESCRIPTION:
B19784
END DESCRIPTION:
XS GIS Cut Line= 3
      2375620.17     13762771.38       2374839.3     13763242.04
      2374197.53     13763919.47
#Sta/Elev= 30
  4089.6  443.89  4113.8   442.4  4270.8  435.98  4393.6  433.48  4802.4  431.11
  4845.6   431.2  4866.9  432.82  4882.5  430.55  4903.8  430.22    4913  428.19
  4919.3  429.84  4951.3  430.96  4983.4  429.82  4988.8  426.96  4989.3  426.46
  4997.4  426.96  5013.6  430.38  5152.2  432.25    5431  433.48  5657.2  437.71
  5869.6  443.57  5876.4  445.08  5883.7  444.16  5890.6  446.13  5897.9  444.95
  5904.8  447.37    5912   446.2  5918.9   448.3  5926.2  447.12  5934.5  449.24
#Mann= 8 ,-1 , 0
  4089.6     .05       0  4113.8     .07       0  4393.6     .05       0
  4802.4     .12       0  4951.3    .035       0  4988.8    .035       0
  4997.4    .035       0  5152.2     .05       0
Bank Sta=4988.8,4997.4
XS Rating Curve= 0 ,0
Exp/Cntr=0.3,0.1

Type RM Length L Ch R = 1 ,6364    ,471,471,471
BEGIN DESCRIPTION:
NASH TRIBUTARY 3 14.0
END DESCRIPTION:
XS GIS Cut Line= 3
      2375075.01     13762174.98        2374725.       13762975.
      2373925.01     13763774.99
#Sta/Elev= 30
  4126.8  442.53  4197.7   439.4  4263.7  435.59  4333.8  432.78  4368.1  431.71
  4386.1  432.27  4399.7  430.34  4421.5  431.76  4513.9  431.26  4574.3  433.41
  4923.6  429.63  4938.8  429.34  4962.2  426.36  4973.9  425.79  4974.4  425.29
  4982.6  425.79  4997.3  427.37  5070.8  430.66  5113.2  429.38  5240.5  431.11
  5325.3  430.54  5509.2  431.44  5664.7   434.3  5820.3  439.74  5961.7  447.42
  6004.1  448.43  6046.6  452.53  6060.7  452.13  6117.3  456.34  6131.4   456.7
#Mann= 4 ,-1 , 0
  4126.8     .07       0  4197.7     .05       0  4973.9     .05       0
  4982.6     .05       0
Bank Sta=4973.9,4982.6
XS Rating Curve= 0 ,0
Exp/Cntr=0.3,0.1

Type RM Length L Ch R = 1 ,5893    ,473,473,473
BEGIN DESCRIPTION:
NASH TRIBUTARY 3 13.0
END DESCRIPTION:
XS GIS Cut Line= 3
      2375024.97     13761875.03        2374375.       13762675.
      2373824.98     13763475.03
#Sta/Elev= 30
  3974.4  459.92  4187.7  446.83  4261.1  439.89    4437  432.82  4585.6  429.84
  4806.2  430.17  4849.3  428.14  4954.8  428.23  4972.8  423.12  4973.3  422.62
  4981.5  423.12  4983.6  427.27  4991.5  428.64    5060  428.58  5105.3  428.27
  5141.1  433.23  5170.9  429.16    5177  430.92  5185.8  428.82  5191.9  431.01
  5199.3  429.03  5212.8  430.38  5221.6  429.04  5227.7  431.46  5242.6  429.65
  5248.7  431.17  5278.5  429.55  5311.8  430.35  5630.9  434.56    5976  446.31
#Mann= 6 ,-1 , 0
  3974.4     .07       0  4261.1     .05       0  4972.8     .05       0
  4981.5     .05       0    5060     .07       0  5311.8     .05       0
Bank Sta=4972.8,4981.5
XS Rating Curve= 0 ,0
Exp/Cntr=0.3,0.1

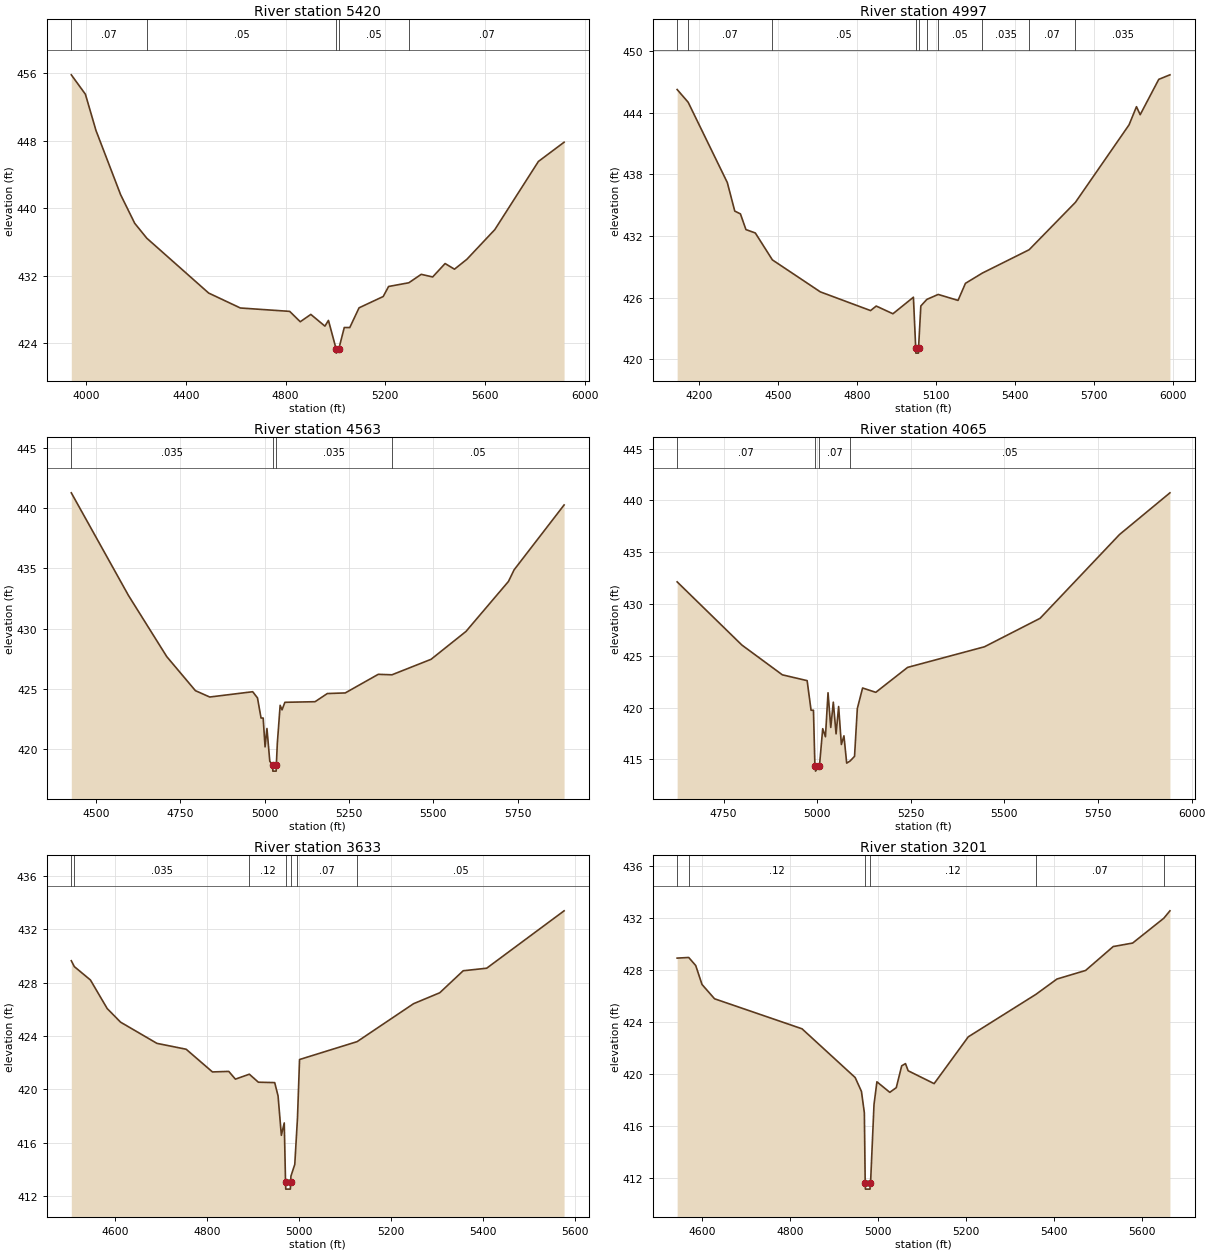
Type RM Length L Ch R = 1 ,5420    ,423,423,423
BEGIN DESCRIPTION:
NASH TRIBUTARY 3 12.0
END DESCRIPTION:
XS GIS Cut Line= 3
        2374775.       13761675.        2374025.       13762425.
      2373225.03     13762874.98
#Sta/Elev= 30
  3939.3  455.84  3995.9  453.54  4038.3  449.25  4137.3  441.63  4193.9  438.24
  4242.5  436.47  4490.8  429.97  4618.1   428.2  4816.1   427.8  4858.5  426.57
    4901  427.44  4957.5  426.05  4971.7  426.73  5002.5  423.35    5003  422.85
  5013.3  423.35  5035.3  425.89  5057.3  425.88  5094.6  428.22  5191.5  429.56
  5213.2  430.75  5294.4  431.19  5344.2  432.19  5390.1  431.88  5440.1  433.47
  5477.7   432.8  5527.7  433.98  5639.6  437.49  5814.6  445.57  5917.8  447.85
#Mann= 5 ,-1 , 0
  3939.3     .07       0  4242.5     .05       0  5002.5     .05       0
  5013.3     .05       0  5294.4     .07       0
Bank Sta=5002.5,5013.3
XS Rating Curve= 0 ,0
Exp/Cntr=0.3,0.1

Type RM Length L Ch R = 1 ,4997    ,434,434,434
BEGIN DESCRIPTION:
NASH TRIBUTARY 3 11.0
END DESCRIPTION:
XS GIS Cut Line= 3
      2374425.01     13761424.98        2373825.       13762075.
      2373124.97     13762775.03
#Sta/Elev= 30
  4115.6  446.25  4157.5  445.01  4306.4   437.2  4334.8  434.42  4356.3  434.15
  4377.3  432.62    4413  432.29    4478  429.67  4660.3  426.56  4851.4  424.74
  4872.9  425.18  4936.4  424.43  5014.4  426.04  5023.1   421.1  5023.6   420.6
  5033.4   420.6  5033.9   421.1  5042.6  425.19  5065.7  425.83  5108.7  426.31
  5184.1  425.73  5212.3  427.39  5276.7  428.39  5454.6  430.66  5630.6  435.27
  5834.6  442.81  5862.9  444.58    5877   443.8  5947.7  447.24  5990.2  447.68
#Mann= 10 ,-1 , 0
  4115.6    .035       0  4157.5     .07       0    4478     .05       0
  5023.1     .05       0  5033.9     .05       0  5065.7    .035       0
  5108.7     .05       0  5276.7    .035       0  5454.6     .07       0
  5630.6    .035       0
Bank Sta=5023.1,5033.9
XS Rating Curve= 0 ,0
Exp/Cntr=0.3,0.1

Type RM Length L Ch R = 1 ,4563    ,498,498,498
BEGIN DESCRIPTION:
NASH TRIBUTARY 3 10.0
END DESCRIPTION:
XS GIS Cut Line= 3
      2374175.02     13761324.98        2373775.       13761725.
      2372975.03     13762124.98
#Sta/Elev= 30
  4427.3   441.3    4597  432.74  4710.2  427.66    4795  424.83  4837.4   424.3
  4964.7  424.74  4978.9  424.23  4989.5  422.55  4995.8  422.55  5001.4  420.15
    5007  421.68  5015.4  418.95  5023.9  418.63  5024.4  418.13  5034.3  418.13
  5034.8  418.63  5037.7  420.43  5046.1  423.61  5051.7  423.23  5060.1  423.86
  5149.5  423.91  5185.9  424.59    5239  424.64  5336.8  426.19  5377.3  426.15
  5493.3  427.44  5596.7  429.76  5722.5  433.92  5739.3  434.89  5887.4  440.29
#Mann= 4 ,-1 , 0
  4427.3    .035       0  5023.9    .035       0  5034.8    .035       0
  5377.3     .05       0
Bank Sta=5023.9,5034.8
XS Rating Curve= 0 ,0
Exp/Cntr=0.3,0.1

Type RM Length L Ch R = 1 ,4065    ,432,432,432
BEGIN DESCRIPTION:
NASH TRIBUTARY 3 9.0
END DESCRIPTION:
XS GIS Cut Line= 3
      2373875.04     13761174.97        2373575.       13761375.
      2372924.97     13762075.04
#Sta/Elev= 30
  4626.1  432.14  4798.9  426.04  4907.1  423.16  4973.2   422.6  4983.7  419.74
  4990.1  419.74  4993.8  414.58  4995.1  414.36  4995.6  413.86  5006.1  414.36
  5014.8  417.96  5022.1  417.18    5029  421.43  5036.3  418.08  5043.1  420.52
  5050.5  417.46  5057.3   420.1  5064.6  416.43  5071.5  417.27  5078.8  414.63
    5088  414.84  5099.8  415.29  5107.2   419.9  5121.3  421.89  5156.5  421.47
  5241.5  423.88  5446.7  425.87  5595.3  428.62  5807.3  436.71    5942  440.74
#Mann= 4 ,-1 , 0
  4626.1     .07       0  4995.1     .05       0  5006.1     .07       0
    5088     .05       0
Bank Sta=4995.1,5006.1
XS Rating Curve= 0 ,0
Exp/Cntr=0.3,0.1

Type RM Length L Ch R = 1 ,3633    ,432,432,432
BEGIN DESCRIPTION:
NASH TRIBUTARY 3 8.0
END DESCRIPTION:
XS GIS Cut Line= 4
      2373674.96     13760975.03        2373275.       13761275.
        2373075.       13761575.      2372957.35     13761751.47
#Sta/Elev= 30
  4504.3  429.64  4510.9   429.2  4545.9   428.2  4582.4  426.06  4611.5  425.04
  4690.7  423.45  4754.3  423.01  4811.5  421.31    4847  421.35  4861.5  420.77
  4891.8  421.14  4911.5  420.54    4947  420.51  4954.3  419.52  4961.5  416.56
  4967.8  417.49  4970.6  413.03  4971.1  412.53  4981.1  412.53  4981.6  413.03
  4982.4  413.51  4990.7  414.38  4996.6  417.86  5001.1  422.24  5126.4  423.58
  5249.1  426.42  5306.2  427.24  5357.3  428.89  5408.4  429.08  5576.9  433.38
#Mann= 7 ,-1 , 0
  4504.3     .07       0  4510.9    .035       0  4891.8     .12       0
  4970.6     .05       0  4981.6     .12       0  4996.6     .07       0
  5126.4     .05       0
Bank Sta=4970.6,4981.6
XS Rating Curve= 0 ,0
Exp/Cntr=0.3,0.1

Type RM Length L Ch R = 1 ,3201    ,467,467,467
BEGIN DESCRIPTION:
NASH TRIBUTARY 3 7.0
END DESCRIPTION:
XS GIS Cut Line= 4
      2373424.98     13760575.02        2373125.       13760925.
        2372875.       13761275.      2372742.22     13761460.89
#Sta/Elev= 30
  4543.7  428.94    4570  428.99  4585.9  428.37  4600.2  426.91  4628.7  425.81
  4827.4   423.5  4948.1  419.75  4962.4  418.68    4969  417.03  4970.9  411.66
  4971.4  411.16  4981.9  411.16  4982.4  411.66  4983.2  411.72  4990.9  417.66
  4997.5  419.42  5026.8  418.61  5041.5  418.97  5053.8  420.65  5062.4  420.82
  5068.5  420.27  5127.5  419.28    5205  422.88  5358.7  426.15  5406.5  427.33
  5471.6  427.99  5534.3  429.83  5578.5   430.1  5649.3  432.01  5663.2  432.58
#Mann= 6 ,-1 , 0
  4543.7     .07       0    4570     .12       0  4970.9     .05       0
  4982.4     .12       0  5358.7     .07       0  5649.3     .12       0
Bank Sta=4970.9,4982.4
XS Rating Curve= 0 ,0
Exp/Cntr=0.3,0.1

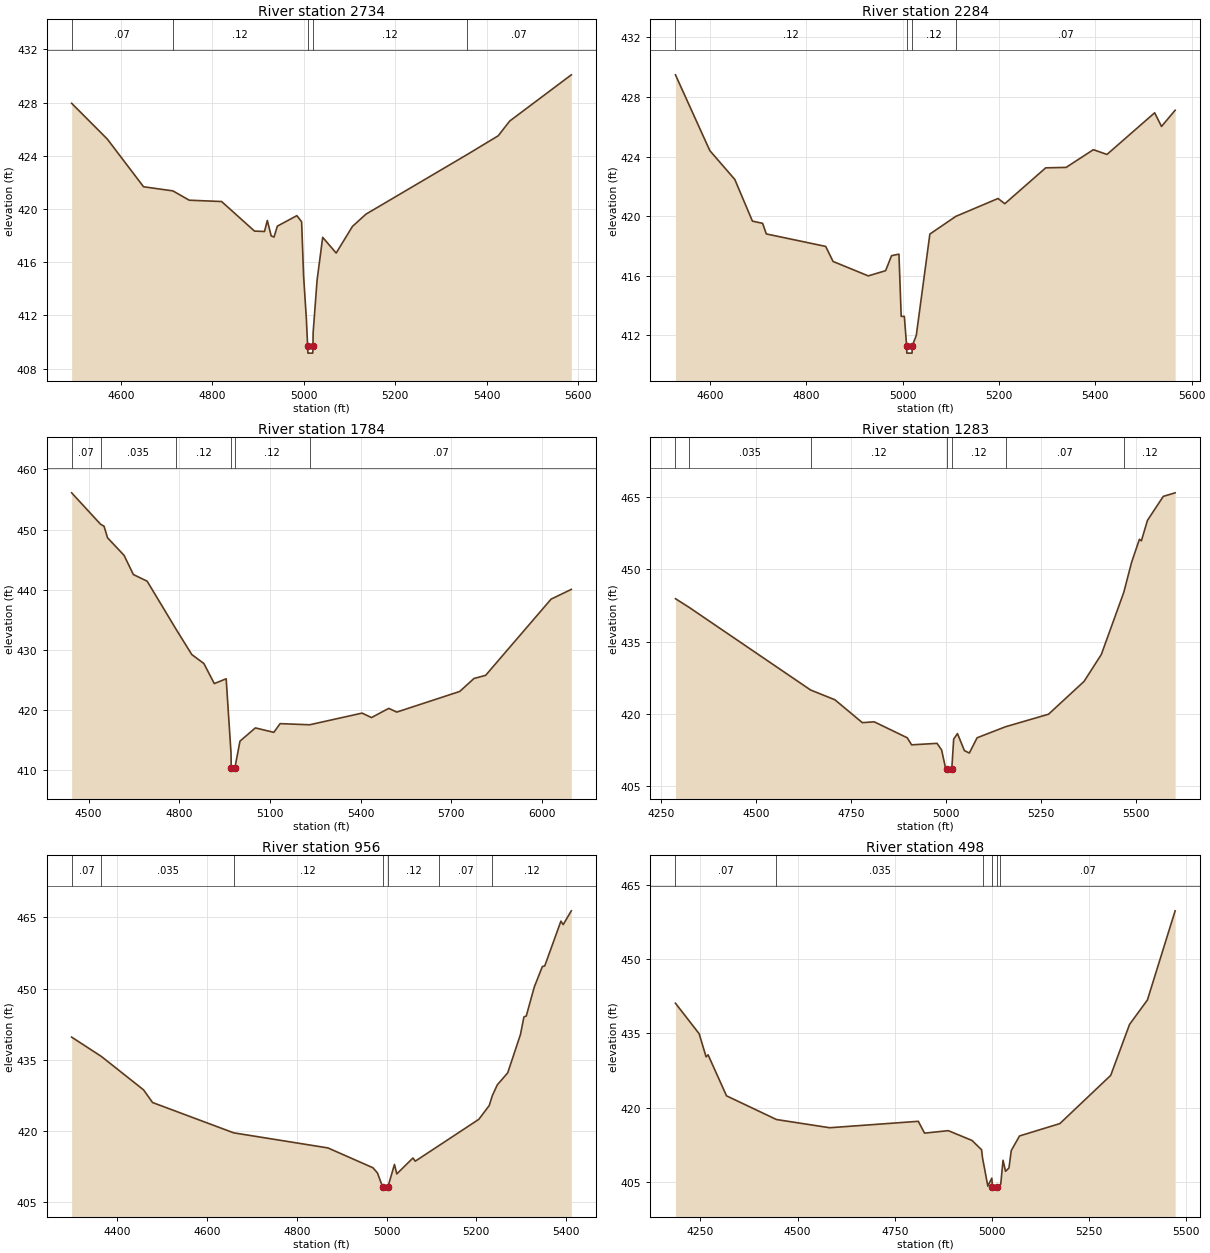
Type RM Length L Ch R = 1 ,2734    ,450,450,450
BEGIN DESCRIPTION:
NASH TRIBUTARY 3 6.0
END DESCRIPTION:
XS GIS Cut Line= 4
      2373225.01     13760324.99        2372825.       13760625.
        2372575.       13760975.      2372480.27     13761107.62
#Sta/Elev= 30
    4492  427.94  4570.1  425.25  4649.3  421.67  4713.5  421.36  4749.3  420.66
  4820.1  420.56    4892  418.34  4913.9  418.31  4920.1  419.14  4928.5  417.98
  4934.7  417.89    4942  418.71  4984.7   419.5  4995.1  419.04  4999.4  414.99
  5005.5  411.74  5008.3  409.67  5008.8  409.17  5019.4  409.17  5019.9  409.67
  5020.3  410.71  5028.9  414.64  5041.2  417.87  5070.7  416.69  5106.3  418.69
  5135.8  419.61  5357.2  424.09  5425.2   425.5  5450.4  426.61  5585.1  430.08
#Mann= 5 ,-1 , 0
    4492     .07       0  4713.5     .12       0  5008.3     .05       0
  5019.9     .12       0  5357.2     .07       0
Bank Sta=5008.3,5019.9
XS Rating Curve= 0 ,0
Exp/Cntr=0.3,0.1

Type RM Length L Ch R = 1 ,2284    ,500,500,500
BEGIN DESCRIPTION:
NASH TRIBUTARY 3 5.0
END DESCRIPTION:
XS GIS Cut Line= 3
      2373024.97     13760025.02        2372625.       13760275.
      2372224.97     13760675.03
#Sta/Elev= 30
  4528.3  429.49  4599.6   424.4  4651.5  422.46  4688.1  419.66  4709.3  419.51
  4716.9   418.8  4840.2  417.96  4855.5  416.95  4928.6  415.98  4964.6  416.33
    4977  417.34  4992.3  417.44    4997  413.26  5003.5  413.26  5008.2  411.29
  5008.7  410.79  5019.5  410.79    5020  411.29  5028.3  411.98  5056.5  418.79
  5110.4  419.98    5198  421.18  5212.1  420.83    5297  423.24  5339.4  423.27
  5395.9  424.46  5424.2  424.14  5523.2  426.94  5537.4  426.02  5565.7  427.11
#Mann= 4 ,-1 , 0
  4528.3     .12       0  5008.2     .05       0    5020     .12       0
  5110.4     .07       0
Bank Sta=5008.2,5020
XS Rating Curve= 0 ,0
Exp/Cntr=0.3,0.1

Type RM Length L Ch R = 1 ,1784    ,501,501,501
BEGIN DESCRIPTION:
NASH TRIBUTARY 3 4.0
END DESCRIPTION:
XS GIS Cut Line= 3
      2373241.93     13759701.43      2372667.87     13759972.42
      2371690.87     13760261.24
#Sta/Elev= 30
  4443.9   456.1  4539.5  450.88  4551.1  450.55  4562.7  448.62  4617.4   445.7
  4648.2  442.51  4693.8   441.4    4790  433.37  4841.5   429.2  4881.5  427.71
    4916  424.37  4955.3  425.17  4971.3  412.82  4972.1  410.31  4972.6  409.81
    4984  410.31  5000.9  414.79  5051.9     417    5113  416.26  5133.8  417.71
  5231.6  417.52    5405  419.46  5436.2  418.72  5493.5  420.25  5519.7  419.63
  5728.2  423.06  5775.4  425.22  5813.9  425.74  6030.6  438.42  6097.5  440.04
#Mann= 6 ,-1 , 0
  4443.9     .07       0  4539.5    .035       0    4790     .12       0
  4972.1     .05       0    4984     .12       0  5231.6     .07       0
Bank Sta=4972.1,4984
XS Rating Curve= 0 ,0
Exp/Cntr=0.3,0.1

Type RM Length L Ch R = 1 ,1283    ,327,327,327
BEGIN DESCRIPTION:
NASH TRIBUTARY 3 3.0
END DESCRIPTION:
XS GIS Cut Line= 3
      2372985.25      13759548.1      2372404.02     13759726.39
      2371725.03     13759924.99
#Sta/Elev= 30
  4288.7  443.93  4323.9  442.17  4644.3  424.97  4708.5  422.93  4780.6  418.18
    4812  418.35  4898.8  415.04  4910.4  413.57  4977.3  413.88  4989.4   412.5
  4999.8  408.72  5004.3  408.61  5004.8  408.11  5016.2  408.61  5021.1  414.75
  5031.1  415.91  5049.4  412.37  5062.3  411.87  5082.8  415.04  5157.7  417.33
  5270.8  419.93  5364.5  426.76  5409.8  432.34  5468.9  445.24  5489.5  451.49
  5510.1  456.27  5515.3  455.95  5531.2  460.19  5572.9  465.18  5604.1  465.92
#Mann= 7 ,-1 , 0
  4288.7     .07       0  4323.9    .035       0  4644.3     .12       0
  5004.3     .05       0  5016.2     .12       0  5157.7     .07       0
  5468.9     .12       0
Bank Sta=5004.3,5016.2
XS Rating Curve= 0 ,0
Exp/Cntr=0.3,0.1

Type RM Length L Ch R = 1 ,956     ,458,458,458
BEGIN DESCRIPTION:
NASH TRIBUTARY 3 2.0
END DESCRIPTION:
XS GIS Cut Line= 3
      2372874.98       13759425.        2372175.       13759475.
      2371774.97     13759575.01
#Sta/Elev= 30
  4297.9  439.79  4364.1  435.73  4458.3  428.69  4478.3  426.03  4659.3  419.65
  4869.3  416.48  4969.6  412.31  4979.6  411.24  4991.2  408.31  4991.7  407.81
  5003.2  408.31  5017.7  413.01  5022.9  411.01  5058.9  414.36  5064.1  413.69
  5117.7  417.02  5205.8   422.5    5229   425.4  5235.8  427.46    5247  429.75
  5270.2  432.28  5298.6  440.33  5306.3  444.04  5311.5  444.22  5329.5  450.35
  5347.5  454.65  5352.7  454.75  5388.8  464.19  5393.9  463.46    5412  466.36
#Mann= 7 ,-1 , 0
  4297.9     .07       0  4364.1    .035       0  4659.3     .12       0
  4991.2     .05       0  5003.2     .12       0  5117.7     .07       0
  5235.8     .12       0
Bank Sta=4991.2,5003.2
XS Rating Curve= 0 ,0
Exp/Cntr=0.3,0.1

Type RM Length L Ch R = 1 ,498     ,343,343,343
BEGIN DESCRIPTION:
NASH TRIBUTARY 3 1.0
END DESCRIPTION:
XS GIS Cut Line= 3
      2372824.97     13758925.01        2372025.       13759075.
        2371775.     13759474.99
#Sta/Elev= 30
  4185.9  441.09  4246.9  434.92  4264.7  430.25  4269.8  430.66  4317.3  422.37
  4445.8  417.58  4582.7  415.92  4810.7  417.22  4826.8  414.83  4887.9  415.33
  4948.9  413.35  4973.5  411.47  4975.9  409.85  4989.6  404.12  4999.8  405.73
  5001.5  404.01    5002  403.51  5013.5  404.01  5019.9  404.35  5022.8  404.51
  5028.7  409.35  5035.2  407.11    5044  407.79  5049.9  411.32  5071.2  414.26
  5174.9  416.76  5305.8  426.51  5354.2   436.8  5400.2  441.75  5471.5  459.77
#Mann= 6 ,-1 , 0
  4185.9     .07       0  4445.8    .035       0  4975.9     .12       0
  5001.5     .05       0  5013.5     .12       0  5019.9     .07       0
Bank Sta=5001.5,5013.5
XS Rating Curve= 0 ,0
Exp/Cntr=0.3,0.1

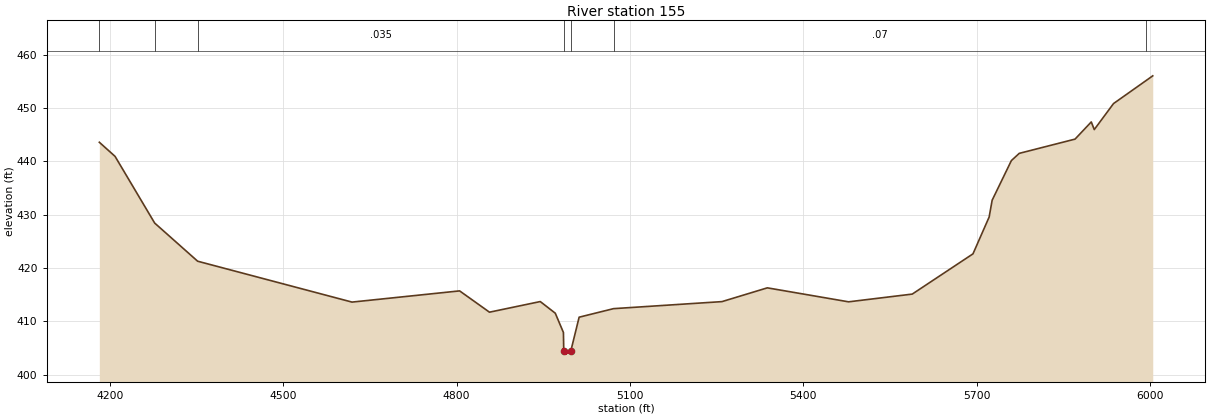
Type RM Length L Ch R = 1 ,155     ,0,0,0
BEGIN DESCRIPTION:
B19783
END DESCRIPTION:
XS GIS Cut Line= 4
       2372817.6     13758553.33      2371961.89     13758781.52
      2371719.43     13758974.06      2371541.16     13759576.61
#Sta/Elev= 30
  4181.4  443.58  4208.6  440.94  4277.2  428.44  4351.6  421.29  4618.8  413.63
  4805.1  415.73  4856.8  411.74  4944.7  413.73  4970.7  411.55  4984.8  407.94
  4985.4  404.38  4985.9  403.88  4997.4  404.38    5012   410.8  5071.5   412.4
  5259.3  413.72  5337.8   416.3  5478.5  413.68  5588.7  415.13  5693.8  422.67
  5721.8  429.57    5727  432.72  5760.3  440.15  5773.9   441.5  5870.5  444.17
  5898.6  447.39  5903.8  445.96  5937.1  450.83  5994.1  455.19    6005  456.03
#Mann= 7 ,-1 , 0
  4181.4     .07       0  4277.2     .12       0  4351.6    .035       0
  4985.4    .035       0  4997.4    .035       0  5071.5     .07       0
  5994.1     .12       0
Bank Sta=4985.4,4997.4
XS Rating Curve= 0 ,0
Exp/Cntr=0.3,0.1

Chan Stop Cuts=-1
Use User Specified Reach Order=0
Composite Channel Slope=5