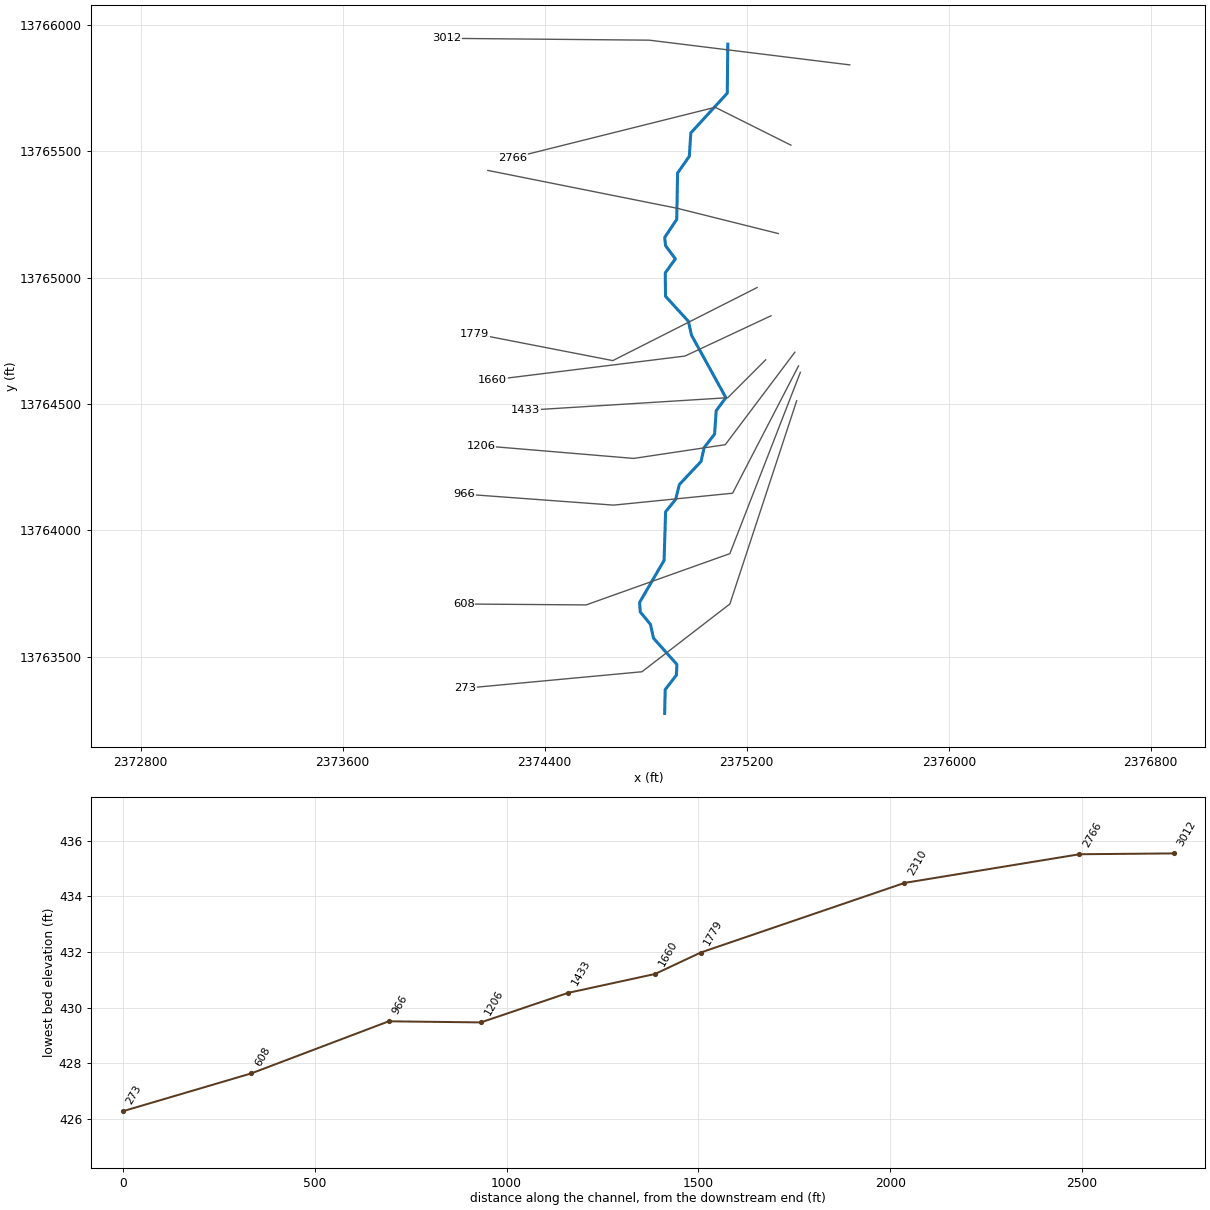
--- NASH TRIBUTARY 4.prj (project) ---

Proj Title=NASH TRIBUTARY 4 Base Level Engineering
Current Plan=p01
Default Exp/Contr=0.3,0.1
English Units
Geom File=g01
Flow File=f01
Plan File=p01
BEGIN DESCRIPTION:
NASH TRIBUTARY 4
END DESCRIPTION:

--- NASH TRIBUTARY 4.p01 (plan) ---

Plan Title=Multiple Run
Short Identifier=Multiple
Geom File=g01
Flow File=f01
Subcritical Flow
K Sum by GR= 0
Std Step Tol= 0.01
Critical Tol= 0.01
Num of Std Step Trials= 20
Max Error Tol= 0.3
Flow Tol Ratio= 0.001
Split Flow NTrial= 30
Split Flow Tol= 0.02
Split Flow Ratio= 0.02
Log Output Level= 0
Friction Slope Method= 1
Unsteady Friction Slope Method= 2
Unsteady Bridges Friction Slope Method= 1
Parabolic Critical Depth
Global Vel Dist=  1 , 1 , 1
Global Log Level= 0
CheckData=True
Encroach Param= -1, 0, 0, 0
BEGIN DESCRIPTION:
Multiple Run
END DESCRIPTION:

--- NASH TRIBUTARY 4.f01 (steady flow) ---

Flow Title=Multiple
Number of Profiles=7
Profile Names=10-year,25-year,50-year,1pct_min,100-year,1pct_plu,500-year
River Rch & RM= NASH TRIBUTARY 4,Reach-1,3012
     807    1313    1774    1159    2312    4614    3894
Boundary for River Rch & Prof#=NASH TRIBUTARY 4,Reach-1,1
Up Type=0
Dn Type=3
Dn Slope=0.005
Boundary for River Rch & Prof#=NASH TRIBUTARY 4,Reach-1,2
Up Type=0
Dn Type=3
Dn Slope=0.005
Boundary for River Rch & Prof#=NASH TRIBUTARY 4,Reach-1,3
Up Type=0
Dn Type=3
Dn Slope=0.005
Boundary for River Rch & Prof#=NASH TRIBUTARY 4,Reach-1,4
Up Type=0
Dn Type=3
Dn Slope=0.005
Boundary for River Rch & Prof#=NASH TRIBUTARY 4,Reach-1,5
Up Type=0
Dn Type=3
Dn Slope=0.005
Boundary for River Rch & Prof#=NASH TRIBUTARY 4,Reach-1,6
Up Type=0
Dn Type=3
Dn Slope=0.005
Boundary for River Rch & Prof#=NASH TRIBUTARY 4,Reach-1,7
Up Type=0
Dn Type=3
Dn Slope=0.005

--- NASH TRIBUTARY 4.g01 (geometry) ---

Geom Title=Existing Conditions

River Reach=NASH TRIBUTARY 4,Reach-1
Reach XY= 30
      2375125.00     13765925.00      2375122.95     13765730.85
      2374978.61     13765573.50      2374972.64     13765480.98
      2374926.22     13765414.50      2374922.71     13765230.93
      2374875.15     13765159.58      2374878.61     13765126.64
      2374917.40     13765075.01      2374877.36     13765019.10
      2374878.47     13764926.50      2374969.15     13764827.29
      2374981.10     13764772.81      2375117.47     13764525.01
      2375079.09     13764473.50      2375072.67     13764380.97
      2375031.14     13764327.17      2375019.16     13764272.71
      2374933.16     13764181.05      2374918.86     13764122.83
      2374878.75     13764073.45      2374872.76     13763880.93
      2374775.74     13763714.31      2374778.34     13763676.72
      2374818.82     13763627.19      2374830.84     13763572.71
      2374923.38     13763468.96      2374921.70     13763426.74
      2374877.13     13763369.14      2374875.00     13763275.00

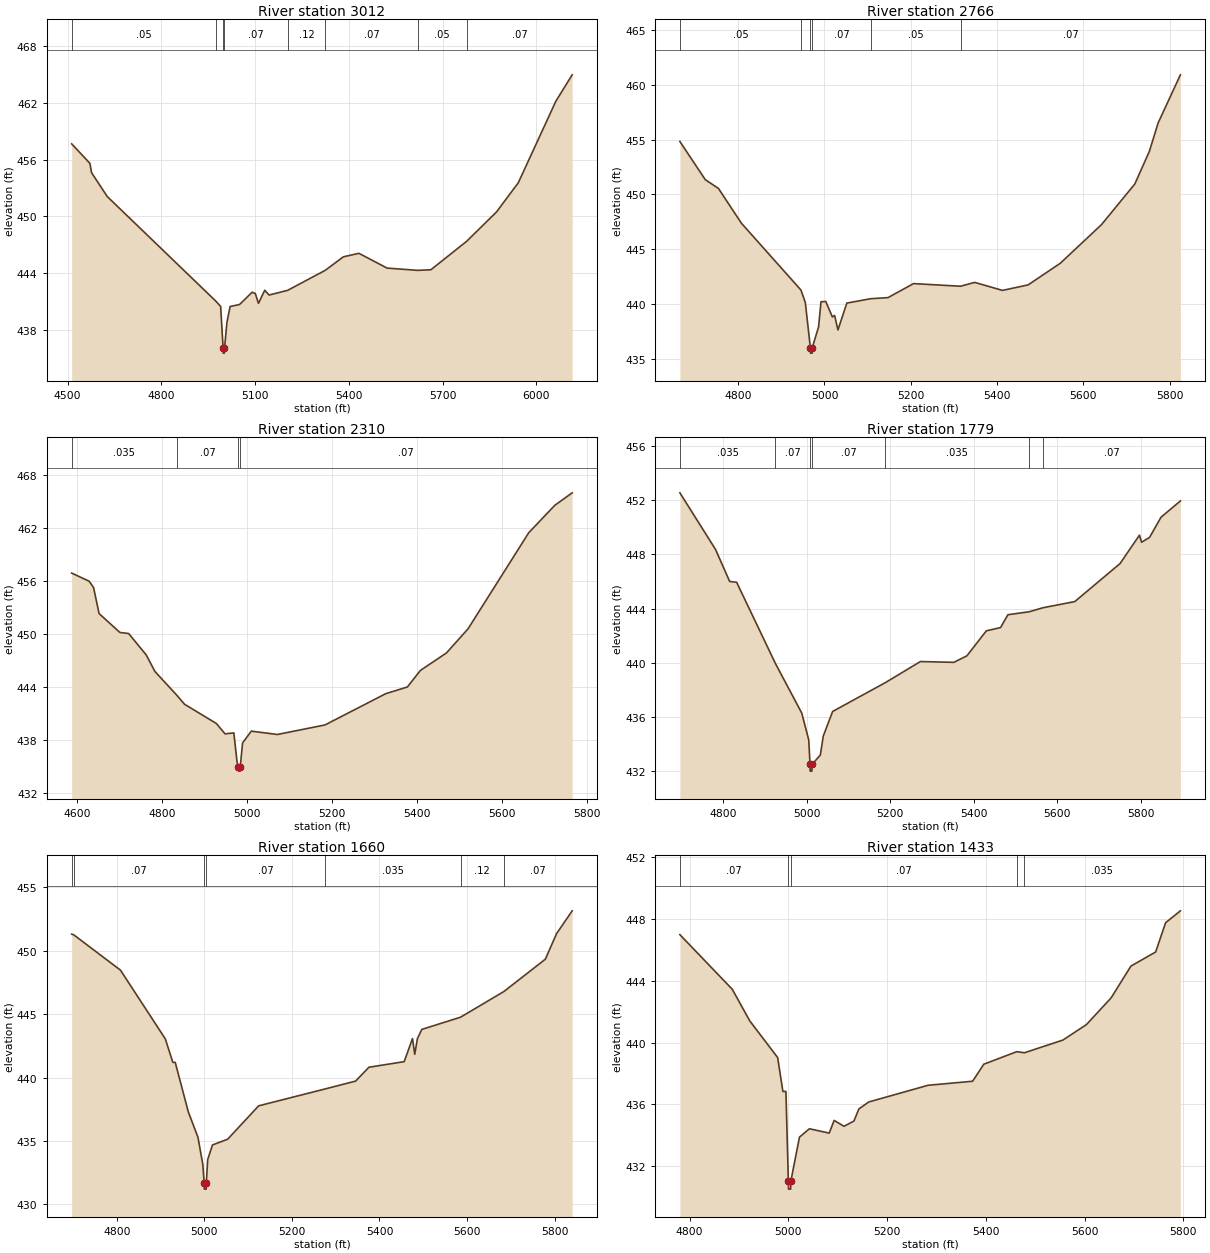
Type RM Length L Ch R = 1,3012,246,246,246
BEGIN DESCRIPTION:
B19791
END DESCRIPTION:
XS GIS Cut Line= 3
      2375608.06     13765842.87      2374814.08     13765940.75
      2374012.80     13765948.01
#Sta/Elev= 30
  4513.3  457.66  4571.7  455.60  4576.8  454.62  4627.2  452.09  4974.7  441.03
  4989.9  440.47  4997.8  436.04  4998.1  435.54  5001.9  435.54  5002.2  436.04
  5010.1  438.81  5020.2  440.47  5050.4  440.68  5090.7  441.98  5100.8  441.84
  5110.9  440.80  5131.0  442.19  5144.9  441.68  5204.5  442.18  5324.4  444.29
  5382.4  445.72  5432.4  446.09  5522.4  444.53  5619.9  444.29  5662.4  444.35
  5776.6  447.35  5872.4  450.46  5942.4  453.56  6062.4  462.17  6114.6  464.96
#Mann=8,-1,0
  4513.3    0.05       0  4974.7    0.07       0  4997.8    0.05       0
  5002.2    0.07       0  5204.5    0.12       0  5324.4    0.07       0
  5619.9    0.05       0  5776.6    0.07       0
Bank Sta=4997.8,5002.2
Exp/Cntr=0.3,0.1

Type RM Length L Ch R = 1,2766,456,456,456
BEGIN DESCRIPTION:
NASH TRIBUTARY 4 4.0
END DESCRIPTION:
XS GIS Cut Line= 3
      2375374.98     13765525.01      2375075.00     13765675.00
      2374275.01     13765475.00
#Sta/Elev= 30
  4664.9  454.84  4723.6  451.36  4754.3  450.55  4807.4  447.38  4945.5  441.27
  4955.6  440.13  4967.3  436.01  4967.6  435.51  4971.4  435.51  4971.7  436.01
  4986.3  437.90  4991.9  440.20  5002.9  440.23  5018.3  438.82  5023.5  438.95
  5031.2  437.63  5051.8  440.08  5107.1  440.48  5147.2  440.58  5206.4  441.86
  5315.4  441.62  5348.2  441.97  5412.6  441.24  5471.9  441.74  5546.6  443.72
  5641.9  447.24  5719.3  450.96  5752.8  453.92  5773.4  456.54  5824.9  460.93
#Mann=6,-1,0
  4664.9    0.05       0  4945.5    0.07       0  4967.3    0.05       0
  4971.7    0.07       0  5107.1    0.05       0  5315.4    0.07       0
Bank Sta=4967.3,4971.7
Exp/Cntr=0.3,0.1

Type RM Length L Ch R = 1,2310,531,531,531
BEGIN DESCRIPTION:
NASH TRIBUTARY 4 3.0
END DESCRIPTION:
XS GIS Cut Line= 3
      2375324.99     13765175.00      2374925.00     13765275.00
      2374174.95     13765425.01
#Sta/Elev= 30
  4588.1  456.86  4629.3  455.94  4639.6  455.22  4652.5  452.29  4701.5  450.15
  4722.1  450.03  4763.3  447.62  4783.9  445.74  4835.0  443.08  4853.5  442.04
  4928.2  439.87  4948.9  438.69  4969.5  438.80  4977.2  435.47  4980.2  434.98
  4980.5  434.48  4984.3  434.48  4984.6  434.98  4990.1  437.67  5010.6  439.00
  5071.8  438.62  5184.0  439.70  5326.7  443.23  5377.7  443.99  5408.3  445.86
  5469.5  447.83  5520.5  450.57  5663.3  461.43  5724.5  464.52  5765.3  465.93
#Mann=4,-1,0
  4588.1   0.035       0  4835.0    0.07       0  4980.2    0.05       0
  4984.6    0.07       0
Bank Sta=4980.2,4984.6
Exp/Cntr=0.3,0.1

Type RM Length L Ch R = 1,1779,119,119,119
BEGIN DESCRIPTION:
NASH TRIBUTARY 4 2.0
END DESCRIPTION:
XS GIS Cut Line= 3
      2375241.19     13764961.28      2374669.72     13764671.91
      2374122.45     13764778.46
#Sta/Elev= 30
  4696.7  452.55  4782.1  448.36  4815.8  446.00  4832.5  445.94  4925.3  439.94
  4988.4  436.27  5005.1  434.29  5008.2  432.48  5008.6  431.98  5012.7  431.98
  5013.1  432.48  5032.9  433.17  5039.9  434.57  5062.3  436.39  5188.5  438.52
  5272.4  440.08  5352.3  440.02  5383.7  440.50  5430.3  442.35  5464.3  442.59
  5481.9  443.54  5533.0  443.76  5566.5  444.06  5641.9  444.51  5750.3  447.32
  5796.8  449.42  5801.9  448.90  5820.9  449.25  5848.5  450.75  5894.8  451.95
#Mann=7,-1,0
  4696.7   0.035       0  4925.3    0.07       0  5008.2    0.05       0
  5013.1    0.07       0  5188.5   0.035       0  5533.0    0.12       0
  5566.5    0.07       0
Bank Sta=5008.2,5013.1
Exp/Cntr=0.3,0.1

Type RM Length L Ch R = 1,1660,227,227,227
BEGIN DESCRIPTION:
B19790
END DESCRIPTION:
XS GIS Cut Line= 3
      2375296.25     13764849.43      2374955.48     13764689.92
      2374194.15     13764595.66
#Sta/Elev= 30
  4696.8  451.29  4701.1  451.25  4808.2  448.46  4910.6  443.05  4927.9  441.20
  4933.4  441.19  4963.2  437.30  4985.3  435.29  4996.3  433.17  4999.5  431.71
  4999.9  431.21  5004.1  431.21  5004.4  431.71  5007.5  433.53  5018.4  434.69
  5053.1  435.14  5123.9  437.77  5275.7  439.10  5345.6  439.72  5375.8  440.81
  5456.4  441.25  5475.4  443.07  5480.5  441.83  5486.7  443.07  5496.7  443.79
  5585.1  444.75  5684.0  446.77  5778.9  449.32  5804.5  451.33  5840.2  453.13
#Mann=7,-1,0
  4696.8   0.035       0  4701.1    0.07       0  4999.5    0.05       0
  5004.4    0.07       0  5275.7   0.035       0  5585.1    0.12       0
  5684.0    0.07       0
Bank Sta=4999.5,5004.4
Exp/Cntr=0.3,0.1

Type RM Length L Ch R = 1,1433,227,227,227
BEGIN DESCRIPTION:
NASH TRIBUTARY 4 1.0
END DESCRIPTION:
XS GIS Cut Line= 3
      2375275.03     13764675.03      2375125.00     13764525.00
      2374325.04     13764475.00
#Sta/Elev= 30
  4780.2  446.97  4886.3  443.44  4921.7  441.40  4978.2  439.03  4988.8  436.84
  4994.9  436.84  4999.9  431.03  5000.3  430.53  5004.5  430.53  5004.8  431.03
  5022.4  433.89  5042.5  434.43  5082.6  434.15  5092.6  434.97  5112.6  434.59
  5132.7  434.93  5142.7  435.71  5162.7  436.16  5282.9  437.24  5373.1  437.50
  5395.7  438.60  5462.4  439.41  5478.0  439.34  5556.0  440.16  5603.6  441.16
  5653.7  442.89  5693.7  444.94  5743.8  445.85  5763.9  447.74  5793.9  448.51
#Mann=5,-1,0
  4780.2    0.07       0  4999.9    0.05       0  5004.8    0.07       0
  5462.4    0.12       0  5478.0   0.035       0
Bank Sta=4999.9,5004.8
Exp/Cntr=0.3,0.1

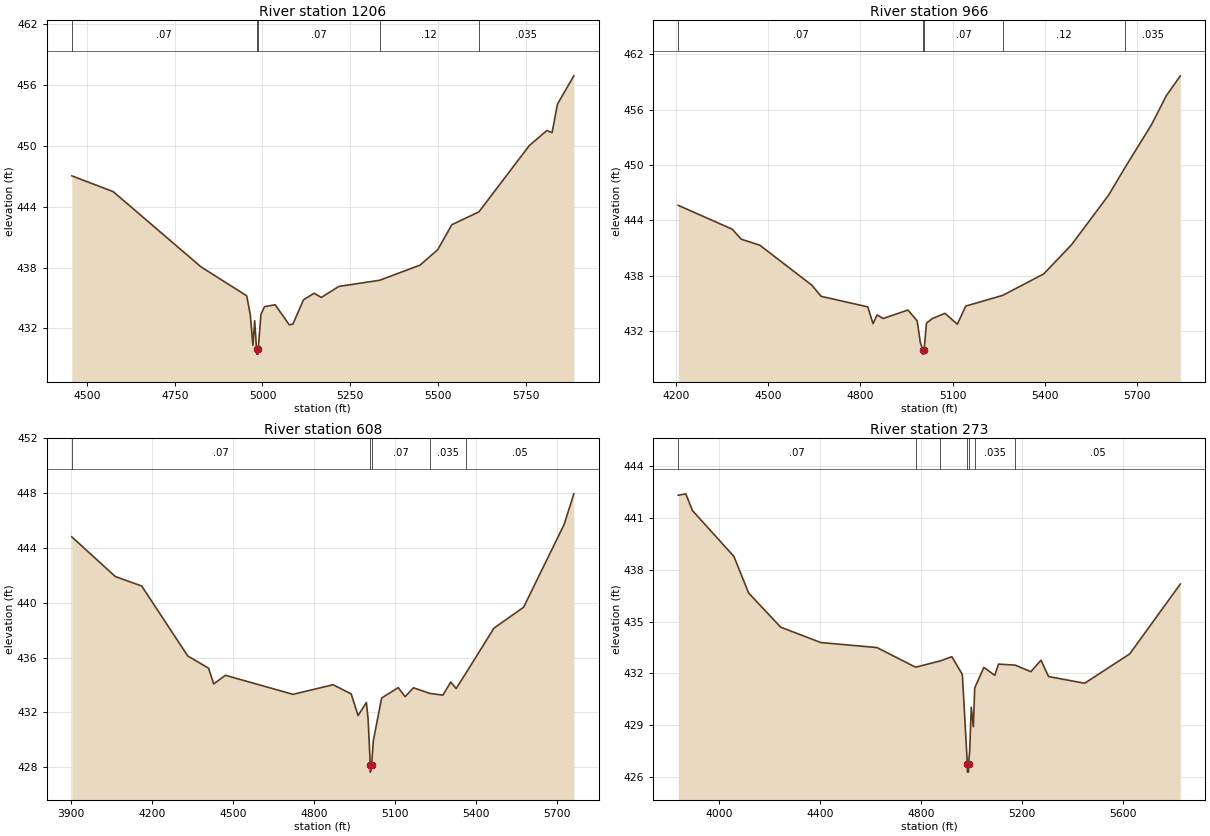
Type RM Length L Ch R = 1,1206,240,240,240
BEGIN DESCRIPTION:
B19789
END DESCRIPTION:
XS GIS Cut Line= 4
      2375390.55     13764705.13      2375115.01     13764338.96
      2374752.45     13764284.57      2374148.45     13764335.21
#Sta/Elev= 30
  4456.5  447.05  4574.7  445.49  4824.6  438.08  4955.2  435.22  4965.3  433.35
  4972.8  430.34  4977.8  432.77  4983.1  429.97  4983.5  429.47  4987.7  429.47
  4988.0  429.97  4995.7  433.39  5005.8  434.15  5036.1  434.34  5076.6  432.36
  5086.7  432.42  5117.0  434.83  5147.3  435.47  5167.6  435.06  5218.1  436.15
  5333.7  436.75  5449.4  438.25  5499.6  439.77  5539.7  442.23  5617.0  443.50
  5760.5  450.03  5810.7  451.52  5825.5  451.31  5840.8  454.12  5887.5  456.91
#Mann=5,-1,0
  4456.5    0.07       0  4983.1    0.05       0  4988.0    0.07       0
  5333.7    0.12       0  5617.0   0.035       0
Bank Sta=4983.1,4988
Exp/Cntr=0.3,0.1

Type RM Length L Ch R = 1,966,358,358,358
BEGIN DESCRIPTION:
B19788
END DESCRIPTION:
XS GIS Cut Line= 4
      2375405.07     13764650.77      2375144.01     13764146.80
      2374672.68     13764099.66      2374081.74     13764143.17
#Sta/Elev= 30
  4206.9  445.63  4382.3  443.05  4412.0  441.96  4472.4  441.31  4641.4  436.99
  4672.0  435.77  4823.7  434.63  4840.8  432.81  4853.9  433.76  4874.0  433.37
  4954.4  434.29  4984.5  433.11  4994.6  430.78  5002.2  430.01  5002.5  429.51
  5006.7  429.51  5007.1  430.01  5014.7  432.88  5034.8  433.38  5075.0  433.93
  5115.2  432.75  5142.3  434.71  5263.1  435.88  5396.2  438.20  5486.5  441.35
  5606.8  446.71  5661.1  449.74  5747.2  454.38  5794.9  457.49  5840.7  459.66
#Mann=5,-1,0
  4206.9    0.07       0  5002.2    0.05       0  5007.1    0.07       0
  5263.1    0.12       0  5661.1   0.035       0
Bank Sta=5002.2,5007.1
Exp/Cntr=0.3,0.1

Type RM Length L Ch R = 1,608,335,335,335
BEGIN DESCRIPTION:
B19787
END DESCRIPTION:
XS GIS Cut Line= 4
      2375412.32     13764625.41      2375133.14     13763907.51
      2374563.91     13763704.47      2374079.05     13763708.09
#Sta/Elev= 30
  3902.3  444.82  4063.7  441.92  4161.3  441.23  4331.9  436.12  4408.9  435.23
  4428.0  434.08  4471.4  434.71  4721.5  433.32  4870.3  434.02  4937.2  433.35
  4962.7  431.77  4993.5  432.73  4999.7  431.54  5007.9  428.14  5008.2  427.64
  5012.8  428.14  5019.0  429.91  5049.8  433.05  5111.4  433.81  5136.9  433.15
  5167.7  433.80  5227.9  433.39  5276.9  433.26  5305.8  434.22  5325.8  433.74
  5363.7  434.92  5465.8  438.15  5575.8  439.68  5725.8  445.72  5761.8  447.96
#Mann=5,-1,0
  3902.3    0.07       0  5007.9    0.05       0  5012.8    0.07       0
  5227.9   0.035       0  5363.7    0.05       0
Bank Sta=5007.9,5012.8
Exp/Cntr=0.3,0.1

Type RM Length L Ch R = 1,273,0,0,0
BEGIN DESCRIPTION:
B19786
END DESCRIPTION:
XS GIS Cut Line= 4
      2375397.82     13764513.01      2375133.14     13763708.10
      2374785.08     13763439.80      2374085.29     13763374.54
#Sta/Elev= 30
  3838.3  442.33  3868.2  442.41  3894.7  441.44  4059.0  438.78  4117.3  436.66
  4244.5  434.68  4403.5  433.79  4625.7  433.50  4779.2  432.36  4877.5  432.73
  4922.5  432.97  4964.2  431.94  4983.8  426.78  4984.2  426.28  4988.4  426.28
  4988.7  426.78  4993.2  427.47  4999.5  430.04  5007.7  428.91  5013.2  431.16
  5049.4  432.35  5092.8  431.89  5107.3  432.54  5173.9  432.48  5235.6  432.10
  5275.8  432.77  5305.9  431.82  5448.8  431.43  5627.3  433.13  5827.9  437.18
#Mann=7,-1,0
  3838.3    0.07       0  4779.2    0.12       0  4877.5    0.07       0
  4983.8    0.05       0  4988.7    0.07       0  5013.2   0.035       0
  5173.9    0.05       0
Bank Sta=4983.8,4988.7
Exp/Cntr=0.3,0.1

Chan Stop Cuts=-1