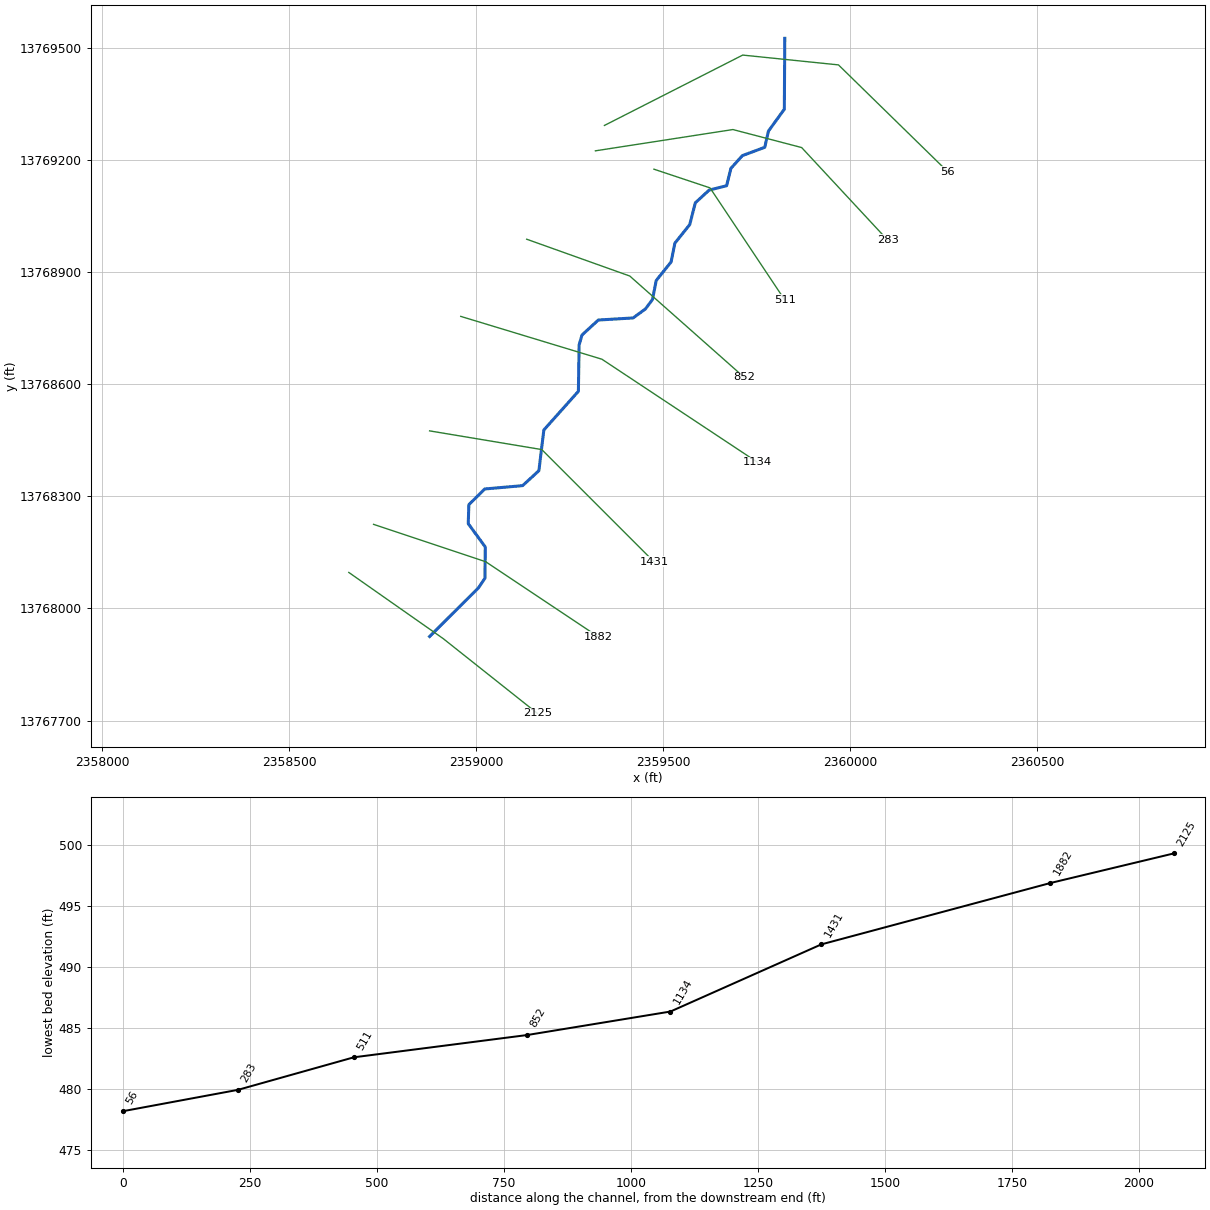
--- NASH TRIBUTARY 5.prj (project) ---

Proj Title=NASH TRIBUTARY 5 Base Level Engineering
Current Plan=p01
Default Exp/Contr=0.3,0.1
English Units
Geom File=g01
Flow File=f01
Plan File=p01
BEGIN DESCRIPTION:
NASH TRIBUTARY 5
END DESCRIPTION:

--- NASH TRIBUTARY 5.p01 (plan) ---

Plan Title=Multiple Run
Short Identifier=Multiple
Geom File=g01
Flow File=f01
Subcritical Flow
K Sum by GR= 0
Std Step Tol= 0.01
Critical Tol= 0.01
Num of Std Step Trials= 20
Max Error Tol= 0.3
Flow Tol Ratio= 0.001
Split Flow NTrial= 30
Split Flow Tol= 0.02
Split Flow Ratio= 0.02
Log Output Level= 0
Friction Slope Method= 1
Unsteady Friction Slope Method= 2
Unsteady Bridges Friction Slope Method= 1
Parabolic Critical Depth
Global Vel Dist=  1 , 1 , 1
Global Log Level= 0
CheckData=True
Encroach Param= -1, 0, 0, 0
BEGIN DESCRIPTION:
Multiple Run
END DESCRIPTION:

--- NASH TRIBUTARY 5.f01 (steady flow) ---

Flow Title=Multiple
Number of Profiles=7
Profile Names=10-year,25-year,50-year,1pct_min,100-year,1pct_plu,500-year
River Rch & RM= NASH TRIBUTARY 5,Reach-1,2125
     513     828    1112     725    1447    2888    2426
Boundary for River Rch & Prof#=NASH TRIBUTARY 5,Reach-1,1
Up Type=0
Dn Type=3
Dn Slope=0.005
Boundary for River Rch & Prof#=NASH TRIBUTARY 5,Reach-1,2
Up Type=0
Dn Type=3
Dn Slope=0.005
Boundary for River Rch & Prof#=NASH TRIBUTARY 5,Reach-1,3
Up Type=0
Dn Type=3
Dn Slope=0.005
Boundary for River Rch & Prof#=NASH TRIBUTARY 5,Reach-1,4
Up Type=0
Dn Type=3
Dn Slope=0.005
Boundary for River Rch & Prof#=NASH TRIBUTARY 5,Reach-1,5
Up Type=0
Dn Type=3
Dn Slope=0.005
Boundary for River Rch & Prof#=NASH TRIBUTARY 5,Reach-1,6
Up Type=0
Dn Type=3
Dn Slope=0.005
Boundary for River Rch & Prof#=NASH TRIBUTARY 5,Reach-1,7
Up Type=0
Dn Type=3
Dn Slope=0.005

--- NASH TRIBUTARY 5.g01 (geometry) ---

Geom Title=Existing Conditions

River Reach=NASH TRIBUTARY 5,Reach-1
Reach XY= 30
      2358875.00     13767925.00      2359005.43     13768054.84
      2359023.04     13768080.89      2359023.88     13768164.45
      2358978.33     13768226.78      2358979.97     13768277.58
      2359022.25     13768319.58      2359123.74     13768328.52
      2359167.27     13768368.50      2359180.54     13768477.42
      2359272.92     13768580.86      2359274.93     13768705.12
      2359282.68     13768731.52      2359326.25     13768771.49
      2359419.29     13768777.08      2359452.19     13768801.05
      2359471.15     13768826.39      2359481.12     13768877.16
      2359520.84     13768926.72      2359531.08     13768977.20
      2359570.80     13769026.76      2359585.69     13769084.98
      2359622.79     13769119.11      2359669.34     13769130.66
      2359680.92     13769177.19      2359711.69     13769211.35
      2359771.47     13769233.49      2359781.28     13769276.84
      2359823.82     13769335.47      2359825.00     13769525.00

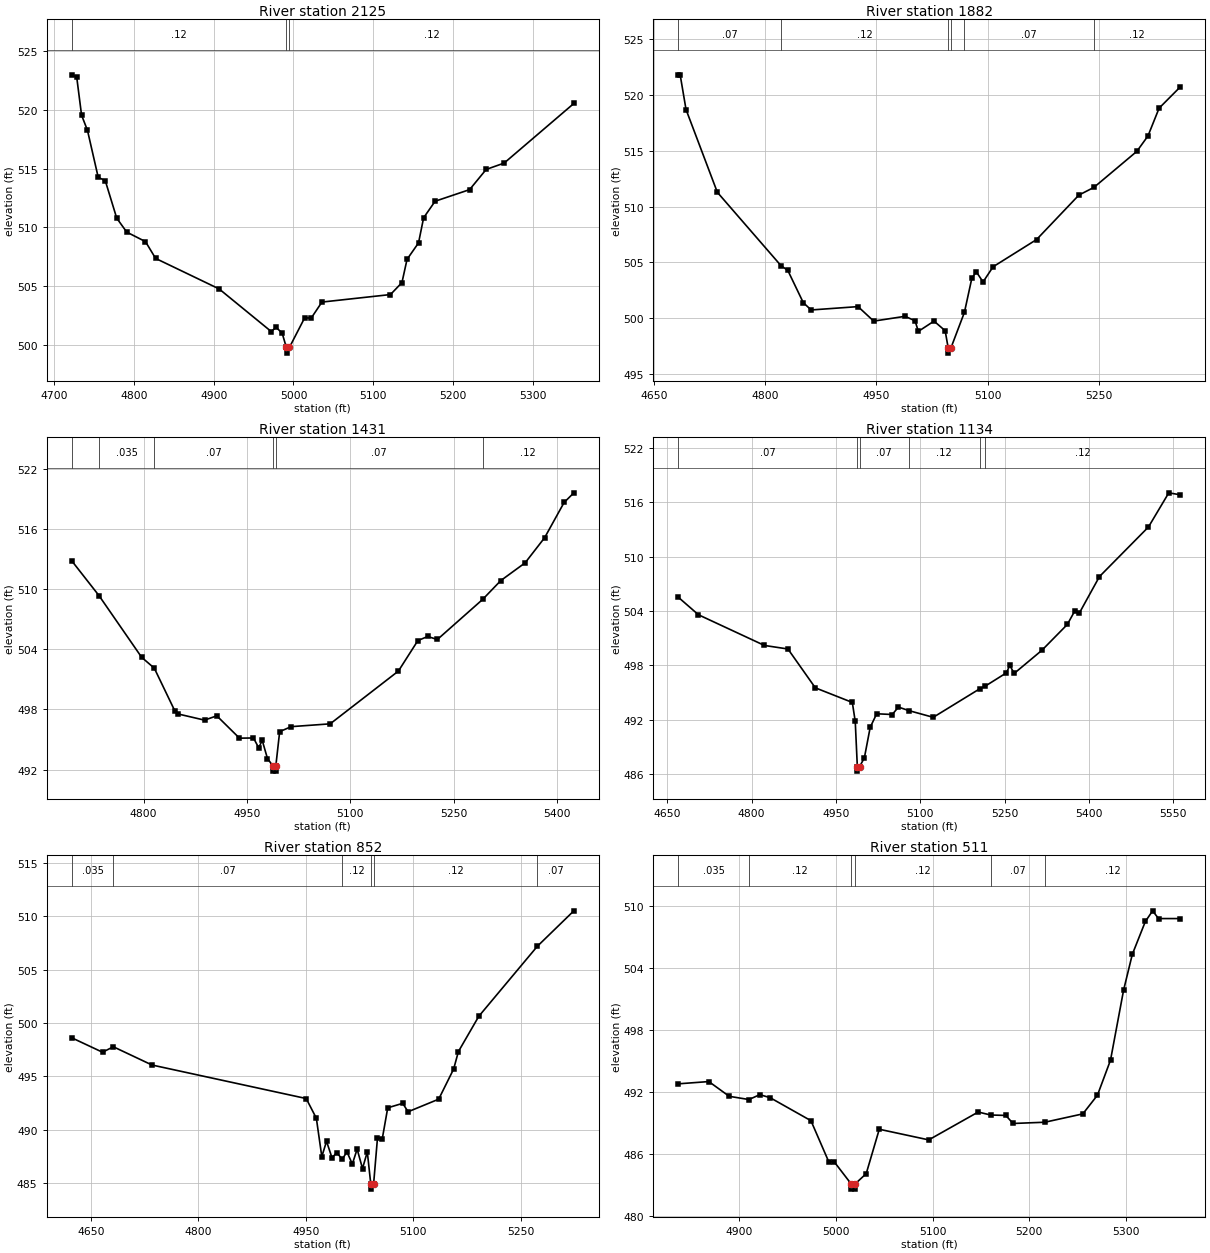
Type RM Length L Ch R = 1,2125,243,243,243
BEGIN DESCRIPTION:
B19795
END DESCRIPTION:
XS GIS Cut Line= 3
      2358658.85     13768096.33      2358911.43     13767919.27
      2359163.27     13767719.36
#Sta/Elev= 30
  4721.8  522.99  4728.0  522.80  4734.1  519.55  4741.5  518.26  4755.0  514.25
  4763.8  513.98  4778.2  510.78  4790.8  509.59  4814.3  508.78  4827.0  507.35
  4906.7  504.75  4972.1  501.12  4978.2  501.48  4985.8  500.98  4991.0  499.78
  4991.3  499.28  4995.0  499.78  5013.9  502.27  5022.4  502.28  5035.7  503.63
  5121.7  504.27  5136.1  505.29  5142.5  507.27  5156.9  508.67  5163.3  510.81
  5177.7  512.22  5221.0  513.21  5241.8  514.93  5264.3  515.47  5351.8  520.55
#Mann=3,-1,0
  4721.8    0.12       0  4991.0    0.05       0  4995.0    0.12       0
Bank Sta=4991,4995
Exp/Cntr=0.3,0.1

Type RM Length L Ch R = 1,1882,451,451,451
BEGIN DESCRIPTION:
NASH TRIBUTARY 5 4.0
END DESCRIPTION:
XS GIS Cut Line= 3
      2358725.02     13768224.99      2359025.00     13768125.00
      2359325.03     13767924.98
#Sta/Elev= 30
  4682.8  521.81  4685.4  521.81  4693.3  518.70  4735.5  511.28  4821.6  504.68
  4830.4  504.29  4851.4  501.38  4862.0  500.73  4925.2  501.03  4946.3  499.73
  4988.5  500.16  5002.0  499.76  5006.5  498.81  5027.6  499.73  5042.6  498.87
  5046.6  497.36  5046.8  496.86  5050.6  497.36  5068.6  500.52  5078.6  503.58
  5084.6  504.15  5093.7  503.24  5107.2  504.60  5165.8  507.04  5222.9  511.03
  5243.2  511.72  5301.0  514.95  5316.0  516.33  5331.0  518.82  5359.6  520.73
#Mann=6,-1,0
  4682.8    0.07       0  4821.6    0.12       0  5046.6    0.05       0
  5050.6    0.12       0  5068.6    0.07       0  5243.2    0.12       0
Bank Sta=5046.6,5050.6
Exp/Cntr=0.3,0.1

Type RM Length L Ch R = 1,1431,297,297,297
BEGIN DESCRIPTION:
NASH TRIBUTARY 5 3.0
END DESCRIPTION:
XS GIS Cut Line= 3
      2358874.98     13768475.00      2359175.00     13768425.00
      2359474.99     13768125.01
#Sta/Elev= 30
  4695.8  512.83  4735.4  509.35  4797.2  503.20  4815.5  502.12  4845.4  497.84
  4850.4  497.54  4888.4  496.93  4906.2  497.36  4939.1  495.13  4959.4  495.15
  4967.0  494.17  4972.1  494.91  4979.7  493.10  4987.8  492.34  4988.1  491.84
  4991.6  491.84  4991.8  492.34  4997.4  495.78  5014.1  496.28  5070.7  496.56
  5169.7  501.83  5197.9  504.87  5212.1  505.28  5226.2  504.98  5291.9  508.98
  5318.2  510.86  5353.5  512.63  5381.8  515.14  5410.1  518.66  5424.2  519.62
#Mann=6,-1,0
  4695.8    0.07       0  4735.4   0.035       0  4815.5    0.07       0
  4987.8    0.05       0  4991.8    0.07       0  5291.9    0.12       0
Bank Sta=4987.8,4991.8
Exp/Cntr=0.3,0.1

Type RM Length L Ch R = 1,1134,282,282,282
BEGIN DESCRIPTION:
NASH TRIBUTARY 5 2.0
END DESCRIPTION:
XS GIS Cut Line= 3
      2358958.27     13768781.26      2359335.91     13768666.67
      2359751.28     13768391.48
#Sta/Elev= 30
  4669.5  505.52  4705.5  503.58  4822.8  500.20  4864.6  499.81  4913.3  495.53
  4979.1  493.92  4984.3  491.82  4988.0  486.85  4988.3  486.35  4992.0  486.85
  5000.5  487.81  5010.9  491.18  5022.4  492.67  5050.1  492.59  5061.1  493.41
  5079.6  493.02  5123.0  492.28  5205.6  495.42  5214.8  495.69  5253.1  497.18
  5259.1  498.00  5267.0  497.12  5316.3  499.67  5361.4  502.51  5374.9  504.02
  5382.5  503.73  5418.6  507.79  5505.8  513.26  5541.9  517.02  5562.4  516.80
#Mann=6,-1,0
  4669.5    0.07       0  4988.0    0.05       0  4992.0    0.07       0
  5079.6    0.12       0  5205.6    0.07       0  5214.8    0.12       0
Bank Sta=4988,4992
Exp/Cntr=0.3,0.1

Type RM Length L Ch R = 1,852,341,341,341
BEGIN DESCRIPTION:
B19794
END DESCRIPTION:
XS GIS Cut Line= 3
      2359134.61     13768987.69      2359410.43     13768889.18
      2359715.64     13768618.85
#Sta/Elev= 30
  4623.3  498.61  4666.2  497.26  4681.3  497.77  4735.3  496.06  4950.4  492.92
  4964.6  491.07  4972.2  487.48  4978.8  488.91  4986.4  487.37  4993.1  487.85
  5000.7  487.23  5007.3  487.92  5014.8  486.78  5021.5  488.18  5029.0  486.36
  5035.7  487.92  5040.5  484.93  5040.8  484.43  5044.5  484.93  5049.9  489.23
  5056.6  489.16  5064.2  492.05  5085.1  492.47  5092.6  491.68  5135.3  492.86
  5156.2  495.69  5162.8  497.32  5191.3  500.63  5273.0  507.19  5323.9  510.51
#Mann=6,-1,0
  4623.3   0.035       0  4681.3    0.07       0  5000.7    0.12       0
  5040.5    0.05       0  5044.5    0.12       0  5273.0    0.07       0
Bank Sta=5040.5,5044.5
Exp/Cntr=0.3,0.1

Type RM Length L Ch R = 1,511,228,228,228
BEGIN DESCRIPTION:
NASH TRIBUTARY 5 1.0
END DESCRIPTION:
XS GIS Cut Line= 3
      2359474.98     13769175.01      2359625.00     13769125.00
      2359825.01     13768824.99
#Sta/Elev= 30
  4837.3  492.81  4868.9  493.03  4890.0  491.60  4910.3  491.29  4921.6  491.76
  4932.2  491.47  4974.4  489.24  4992.8  485.26  4998.4  485.26  5016.0  483.11
  5016.2  482.61  5019.7  482.61  5020.0  483.11  5031.5  484.11  5045.0  488.41
  5096.1  487.38  5147.2  490.08  5160.0  489.79  5175.7  489.75  5183.2  488.97
  5216.0  489.09  5255.3  489.90  5270.4  491.71  5283.9  495.11  5297.4  501.89
  5306.4  505.35  5319.9  508.54  5327.4  509.57  5333.5  508.82  5356.0  508.82
#Mann=6,-1,0
  4837.3   0.035       0  4910.3    0.12       0  5016.0    0.05       0
  5020.0    0.12       0  5160.0    0.07       0  5216.0    0.12       0
Bank Sta=5016,5020
Exp/Cntr=0.3,0.1

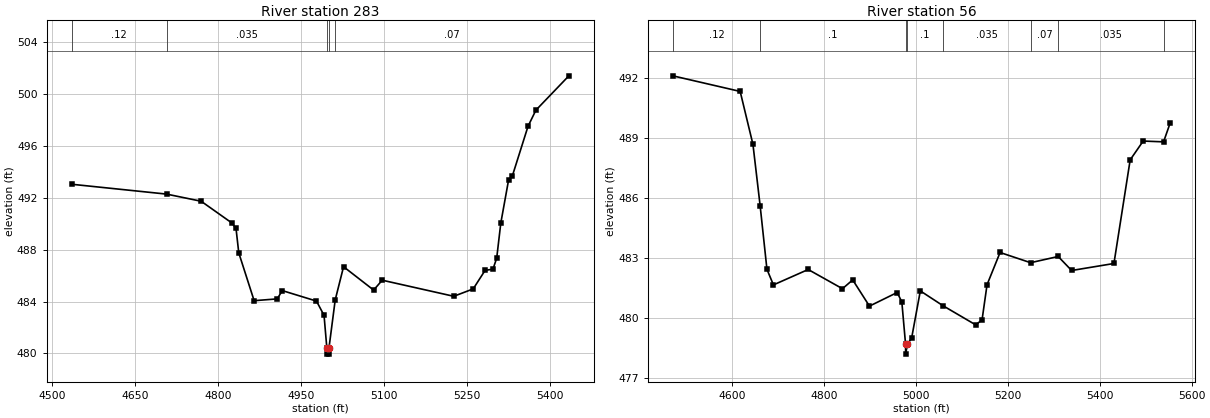
Type RM Length L Ch R = 1,283,227,227,227
BEGIN DESCRIPTION:
B19793
END DESCRIPTION:
XS GIS Cut Line= 4
      2359318.46     13769224.10      2359686.25     13769281.02
      2359870.13     13769232.86      2360099.97     13768985.51
#Sta/Elev= 30
  4535.1  493.05  4707.0  492.29  4769.6  491.74  4825.0  490.07  4832.7  489.65
  4837.7  487.76  4865.5  484.07  4907.3  484.21  4916.4  484.85  4978.3  484.04
  4992.0  482.94  4997.0  480.45  4997.3  479.95  5000.8  479.95  5001.0  480.45
  5012.2  484.13  5027.3  486.69  5081.7  484.89  5097.3  485.65  5226.7  484.41
  5261.9  484.98  5283.4  486.41  5297.6  486.50  5304.4  487.35  5311.8  490.05
  5325.9  493.38  5332.8  493.70  5361.1  497.52  5375.3  498.76  5435.0  501.41
#Mann=5,-1,0
  4535.1    0.12       0  4707.0   0.035       0  4997.0   0.035       0
  5001.0   0.035       0  5012.2    0.07       0
Bank Sta=4997,5001
Exp/Cntr=0.3,0.1

Type RM Length L Ch R = 1,56,0,0,0
BEGIN DESCRIPTION:
B19792
END DESCRIPTION:
XS GIS Cut Line= 4
      2359342.58     13769291.97      2359712.52     13769480.22
      2359968.64     13769453.96      2360260.99     13769168.14
#Sta/Elev= 30
  4471.8  492.11  4618.3  491.33  4646.1  488.68  4661.7  485.62  4676.5  482.44
  4690.6  481.66  4766.2  482.43  4840.7  481.47  4863.0  481.91  4899.4  480.60
  4959.7  481.28  4969.8  480.81  4977.9  478.70  4978.1  478.20  4981.9  478.70
  4991.0  478.99  5010.0  481.36  5059.3  480.62  5130.6  479.66  5144.3  479.92
  5155.1  481.67  5183.4  483.28  5249.8  482.77  5309.8  483.08  5339.0  482.38
  5431.0  482.73  5466.3  487.91  5494.6  488.85  5538.9  488.81  5553.2  489.75
#Mann=8,-1,0
  4471.8    0.12       0  4661.7     0.1       0  4977.9    0.05       0
  4981.9     0.1       0  5059.3   0.035       0  5249.8    0.07       0
  5309.8   0.035       0  5538.9    0.07       0
Bank Sta=4977.9,4981.9
Exp/Cntr=0.3,0.1

Chan Stop Cuts=-1