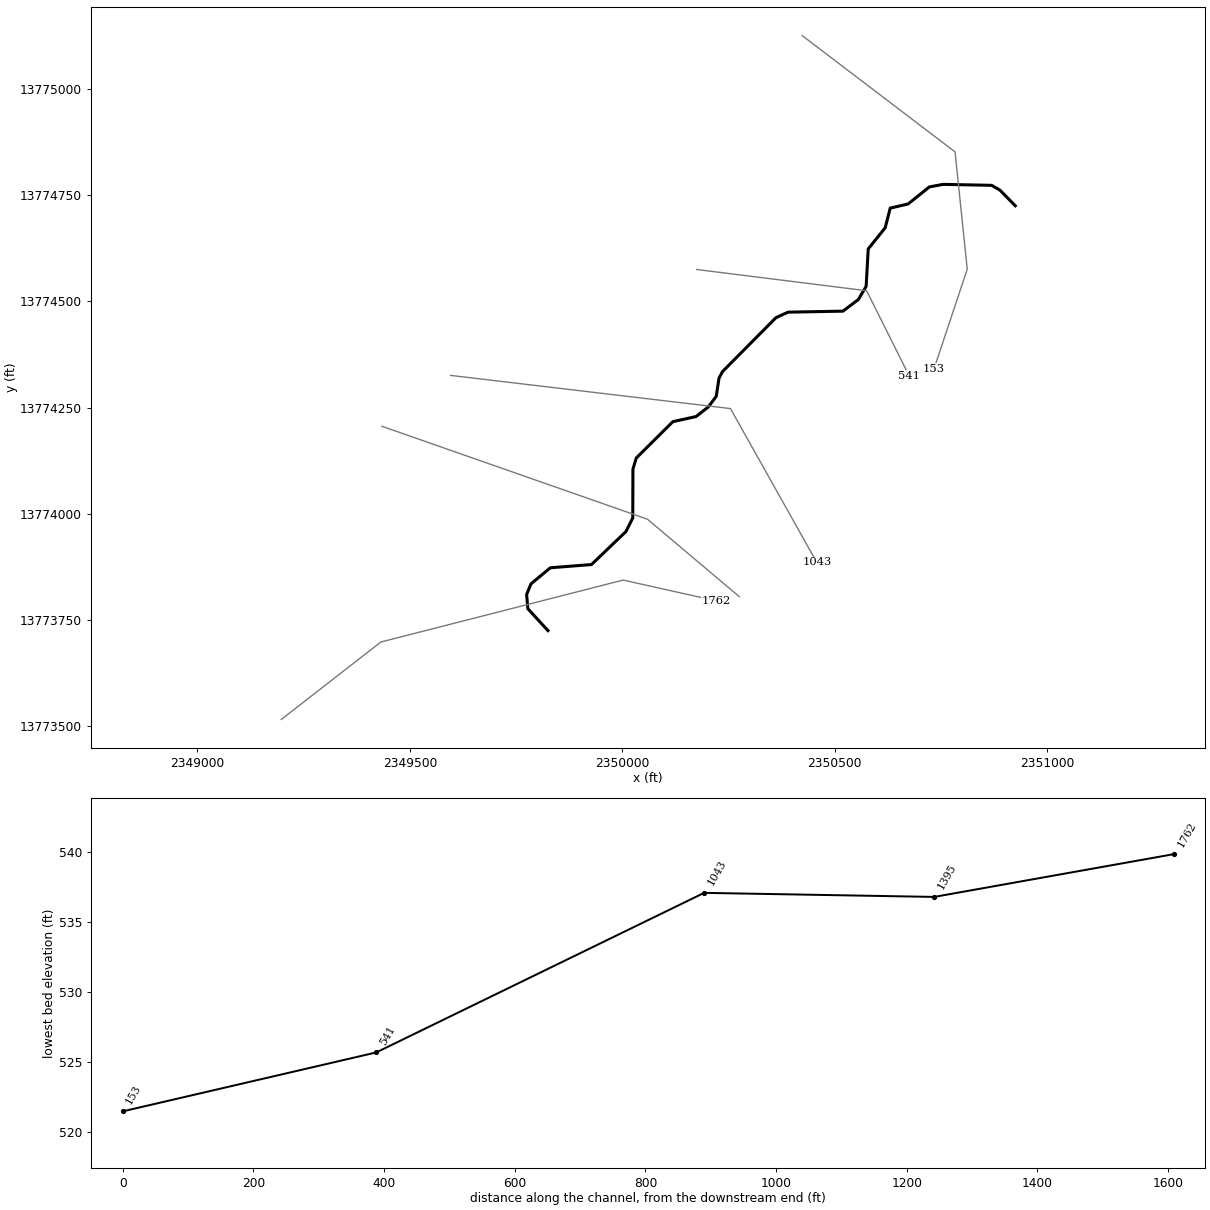
--- NASH TRIBUTARY 5D.prj (project) ---

Proj Title=NASH TRIBUTARY 5D Base Level Engineering
Current Plan=p01
Default Exp/Contr=0.3,0.1
English Units
Geom File=g01
Flow File=f01
Plan File=p01
BEGIN DESCRIPTION:
NASH TRIBUTARY 5D
END DESCRIPTION:

--- NASH TRIBUTARY 5D.p01 (plan) ---

Plan Title=Multiple Run
Short Identifier=Multiple
Geom File=g01
Flow File=f01
Subcritical Flow
K Sum by GR= 0
Std Step Tol= 0.01
Critical Tol= 0.01
Num of Std Step Trials= 20
Max Error Tol= 0.3
Flow Tol Ratio= 0.001
Split Flow NTrial= 30
Split Flow Tol= 0.02
Split Flow Ratio= 0.02
Log Output Level= 0
Friction Slope Method= 1
Unsteady Friction Slope Method= 2
Unsteady Bridges Friction Slope Method= 1
Parabolic Critical Depth
Global Vel Dist=  1 , 1 , 1
Global Log Level= 0
CheckData=True
Encroach Param= -1, 0, 0, 0
BEGIN DESCRIPTION:
Multiple Run
END DESCRIPTION:

--- NASH TRIBUTARY 5D.f01 (steady flow) ---

Flow Title=Multiple
Number of Profiles=7
Profile Names=10-year,25-year,50-year,1pct_min,100-year,1pct_plu,500-year
River Rch & RM= NASH TRIBUTARY 5,Reach-1,1762
     410     650     864     558    1114    2222    1829
Boundary for River Rch & Prof#=NASH TRIBUTARY 5,Reach-1,1
Up Type=0
Dn Type=3
Dn Slope=0.005
Boundary for River Rch & Prof#=NASH TRIBUTARY 5,Reach-1,2
Up Type=0
Dn Type=3
Dn Slope=0.005
Boundary for River Rch & Prof#=NASH TRIBUTARY 5,Reach-1,3
Up Type=0
Dn Type=3
Dn Slope=0.005
Boundary for River Rch & Prof#=NASH TRIBUTARY 5,Reach-1,4
Up Type=0
Dn Type=3
Dn Slope=0.005
Boundary for River Rch & Prof#=NASH TRIBUTARY 5,Reach-1,5
Up Type=0
Dn Type=3
Dn Slope=0.005
Boundary for River Rch & Prof#=NASH TRIBUTARY 5,Reach-1,6
Up Type=0
Dn Type=3
Dn Slope=0.005
Boundary for River Rch & Prof#=NASH TRIBUTARY 5,Reach-1,7
Up Type=0
Dn Type=3
Dn Slope=0.005

--- NASH TRIBUTARY 5D.g01 (geometry) ---

Geom Title=Existing Conditions

River Reach=NASH TRIBUTARY 5,Reach-1
Reach XY= 30
      2349825.00     13773725.00      2349777.65     13773776.66
      2349774.75     13773809.90      2349785.03     13773835.11
      2349830.67     13773872.93      2349927.44     13773880.52
      2350008.58     13773958.20      2350024.61     13773990.16
      2350024.98     13774105.01      2350032.81     13774131.21
      2350118.95     13774216.84      2350173.57     13774228.89
      2350202.14     13774251.16      2350221.11     13774276.43
      2350227.55     13774318.91      2350235.79     13774334.66
      2350361.68     13774461.63      2350390.16     13774474.60
      2350519.35     13774476.98      2350555.58     13774504.35
      2350573.91     13774535.31      2350578.82     13774623.44
      2350618.72     13774673.16      2350630.58     13774719.42
      2350672.89     13774729.37      2350722.62     13774769.31
      2350754.85     13774775.40      2350869.21     13774773.12
      2350888.50     13774762.09      2350925.00     13774725.00

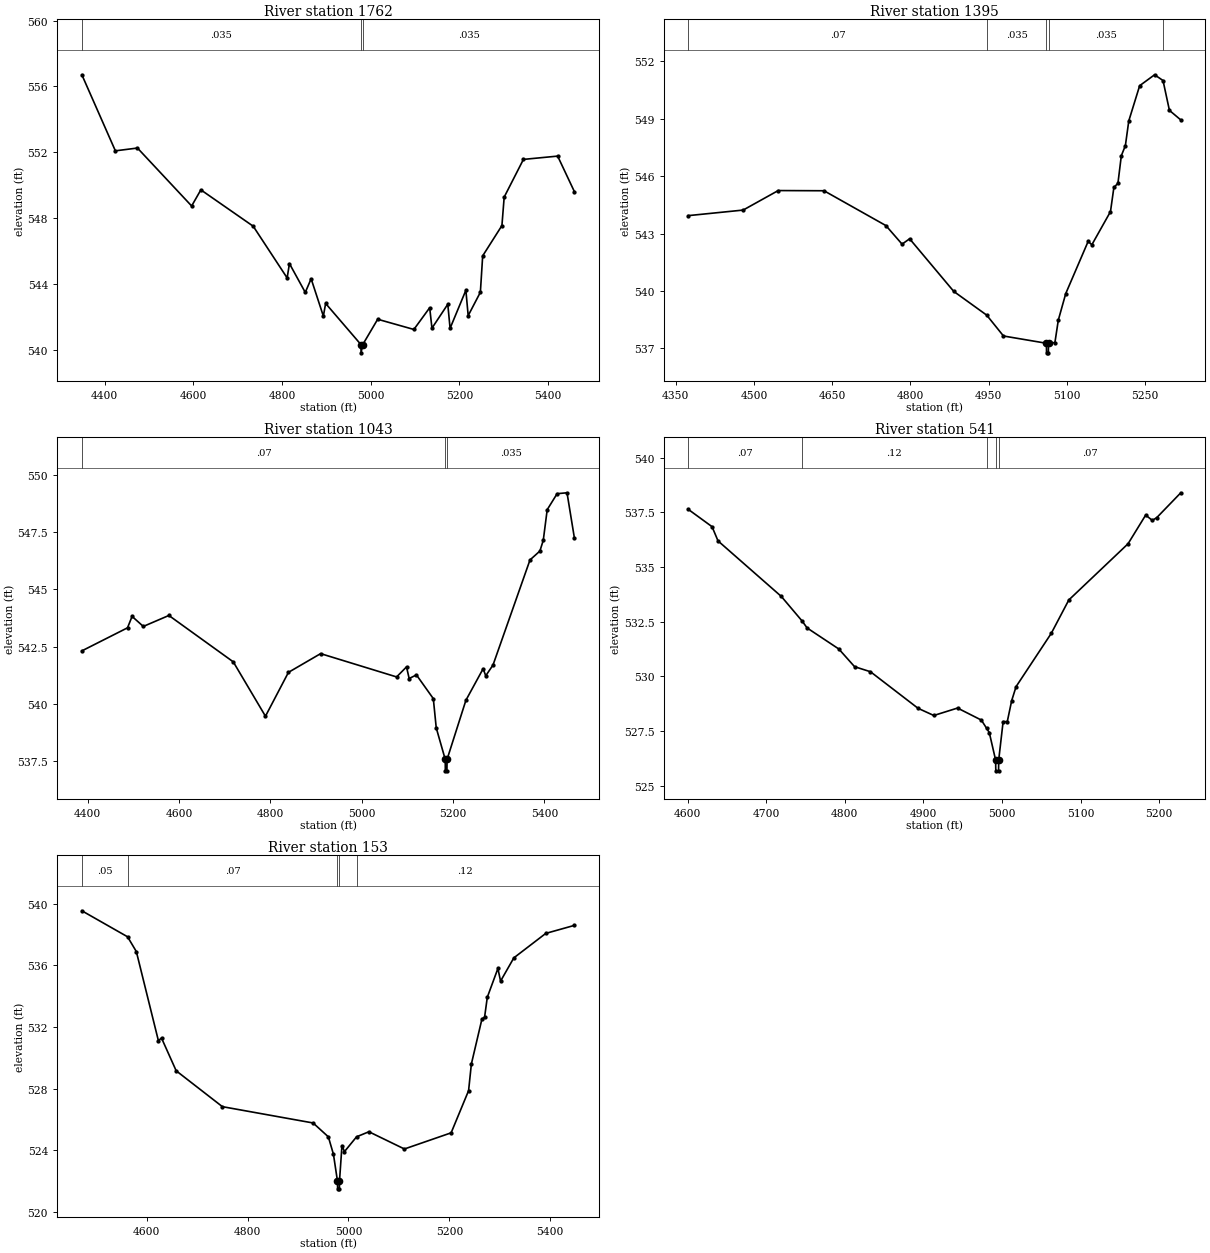
Type RM Length L Ch R = 1,1762,367,367,367
BEGIN DESCRIPTION:
B19797
END DESCRIPTION:
XS GIS Cut Line= 4
      2349197.30     13773515.90      2349431.65     13773698.17
      2350001.96     13773844.00      2350221.69     13773794.89
#Sta/Elev= 30
  4348.5  556.71  4424.1  552.09  4473.9  552.26  4596.1  548.74  4616.9  549.72
  4735.0  547.51  4811.5  544.37  4816.7  545.24  4852.4  543.49  4865.6  544.32
  4893.2  542.05  4898.3  542.82  4978.0  540.32  4978.2  539.82  4982.0  540.32
  5015.7  541.86  5097.3  541.24  5133.0  542.56  5138.1  541.32  5173.8  542.77
  5179.0  541.31  5214.6  543.62  5219.8  542.08  5247.3  543.50  5252.5  545.71
  5295.9  547.55  5301.0  549.28  5344.4  551.57  5421.6  551.77  5459.2  549.62
#Mann=3,-1,0
  4348.5   0.035       0  4978.0   0.035       0  4982.0   0.035       0
Bank Sta=4978,4982
Exp/Cntr=0.3,0.1

Type RM Length L Ch R = 1,1395,352,352,352
BEGIN DESCRIPTION:
NASH TRIBUTARY 5D 3.0
END DESCRIPTION:
XS GIS Cut Line= 3
      2349434.28     13774205.97      2350059.25     13773987.23
      2350275.40     13773804.94
#Sta/Elev= 30
  4373.9  543.94  4479.1  544.23  4546.4  545.25  4634.2  545.24  4753.0  543.42
  4784.0  542.45  4798.5  542.73  4883.2  539.98  4946.4  538.74  4978.6  537.65
  5061.0  537.27  5061.2  536.77  5064.7  536.77  5065.0  537.27  5077.3  537.31
  5083.8  538.48  5098.1  539.87  5141.0  542.59  5148.2  542.42  5183.9  544.15
  5190.4  545.41  5198.2  545.63  5204.7  547.07  5212.5  547.60  5219.0  548.89
  5239.9  550.73  5268.5  551.30  5284.7  551.00  5297.0  549.44  5318.8  548.94
#Mann=5,-1,0
  4373.9    0.07       0  4946.4   0.035       0  5061.0   0.035       0
  5065.0   0.035       0  5284.7   0.063       0
Bank Sta=5061,5065
Exp/Cntr=0.3,0.1

Type RM Length L Ch R = 1,1043,502,502,502
BEGIN DESCRIPTION:
NASH TRIBUTARY 5D 2.0
END DESCRIPTION:
XS GIS Cut Line= 3
      2349595.73     13774325.77      2350254.56     13774247.65
      2350457.68     13773885.69
#Sta/Elev= 30
  4387.0  542.31  4487.0  543.32  4497.0  543.82  4521.6  543.38  4577.6  543.86
  4718.6  541.83  4789.1  539.45  4839.4  541.37  4909.9  542.19  5076.3  541.17
  5098.0  541.61  5103.8  541.10  5119.7  541.26  5156.7  540.22  5163.1  538.94
  5182.8  537.56  5183.0  537.06  5186.5  537.06  5186.8  537.56  5228.1  540.15
  5265.8  541.53  5271.5  541.22  5287.4  541.69  5368.4  546.29  5390.1  546.68
  5397.5  547.15  5406.1  548.49  5427.8  549.19  5449.5  549.23  5465.5  547.27
#Mann=3,-1,0
  4387.0    0.07       0  5182.8    0.05       0  5186.8   0.035       0
Bank Sta=5182.8,5186.8
Exp/Cntr=0.3,0.1

Type RM Length L Ch R = 1,541,388,388,388
BEGIN DESCRIPTION:
NASH TRIBUTARY 5D 1.0
END DESCRIPTION:
XS GIS Cut Line= 3
      2350175.01     13774575.00      2350575.00     13774525.00
      2350674.99     13774325.01
#Sta/Elev= 30
  4600.8  537.63  4631.0  536.84  4638.6  536.19  4719.2  533.65  4745.8  532.52
  4752.0  532.21  4792.3  531.25  4812.4  530.44  4832.6  530.21  4893.1  528.54
  4913.2  528.21  4943.4  528.55  4973.7  528.00  4980.3  527.63  4983.8  527.43
  4991.8  526.18  4992.1  525.68  4995.6  525.68  4995.8  526.18  5001.4  527.93
  5006.7  527.93  5012.3  528.89  5017.9  529.53  5062.6  531.96  5085.0  533.49
  5160.4  536.06  5182.8  537.37  5191.2  537.13  5196.8  537.25  5227.5  538.39
#Mann=5,-1,0
  4600.8    0.07       0  4745.8    0.12       0  4980.3    0.07       0
  4991.8    0.05       0  4995.8    0.07       0
Bank Sta=4991.8,4995.8
Exp/Cntr=0.3,0.1

Type RM Length L Ch R = 1,153,0,0,0
BEGIN DESCRIPTION:
B19796
END DESCRIPTION:
XS GIS Cut Line= 4
      2350423.82     13775125.26      2350783.21     13774851.82
      2350811.86     13774575.78      2350733.72     13774341.37
#Sta/Elev= 30
  4471.6  539.55  4562.2  537.86  4579.6  536.90  4623.3  531.11  4629.5  531.28
  4658.6  529.15  4750.2  526.82  4930.0  525.76  4960.2  524.86  4970.3  523.73
  4978.3  521.98  4978.6  521.48  4982.1  521.48  4982.3  521.98  4987.2  524.29
  4992.2  523.90  5016.1  524.86  5040.6  525.19  5111.0  524.07  5203.6  525.12
  5238.2  527.86  5243.7  529.59  5264.7  532.52  5269.9  532.63  5275.3  533.93
  5296.3  535.80  5301.6  534.98  5327.9  536.49  5391.2  538.08  5447.8  538.60
#Mann=5,-1,0
  4471.6    0.05       0  4562.2    0.07       0  4978.3    0.05       0
  4982.3    0.07       0  5016.1    0.12       0
Bank Sta=4978.3,4982.3
Exp/Cntr=0.3,0.1

Chan Stop Cuts=-1