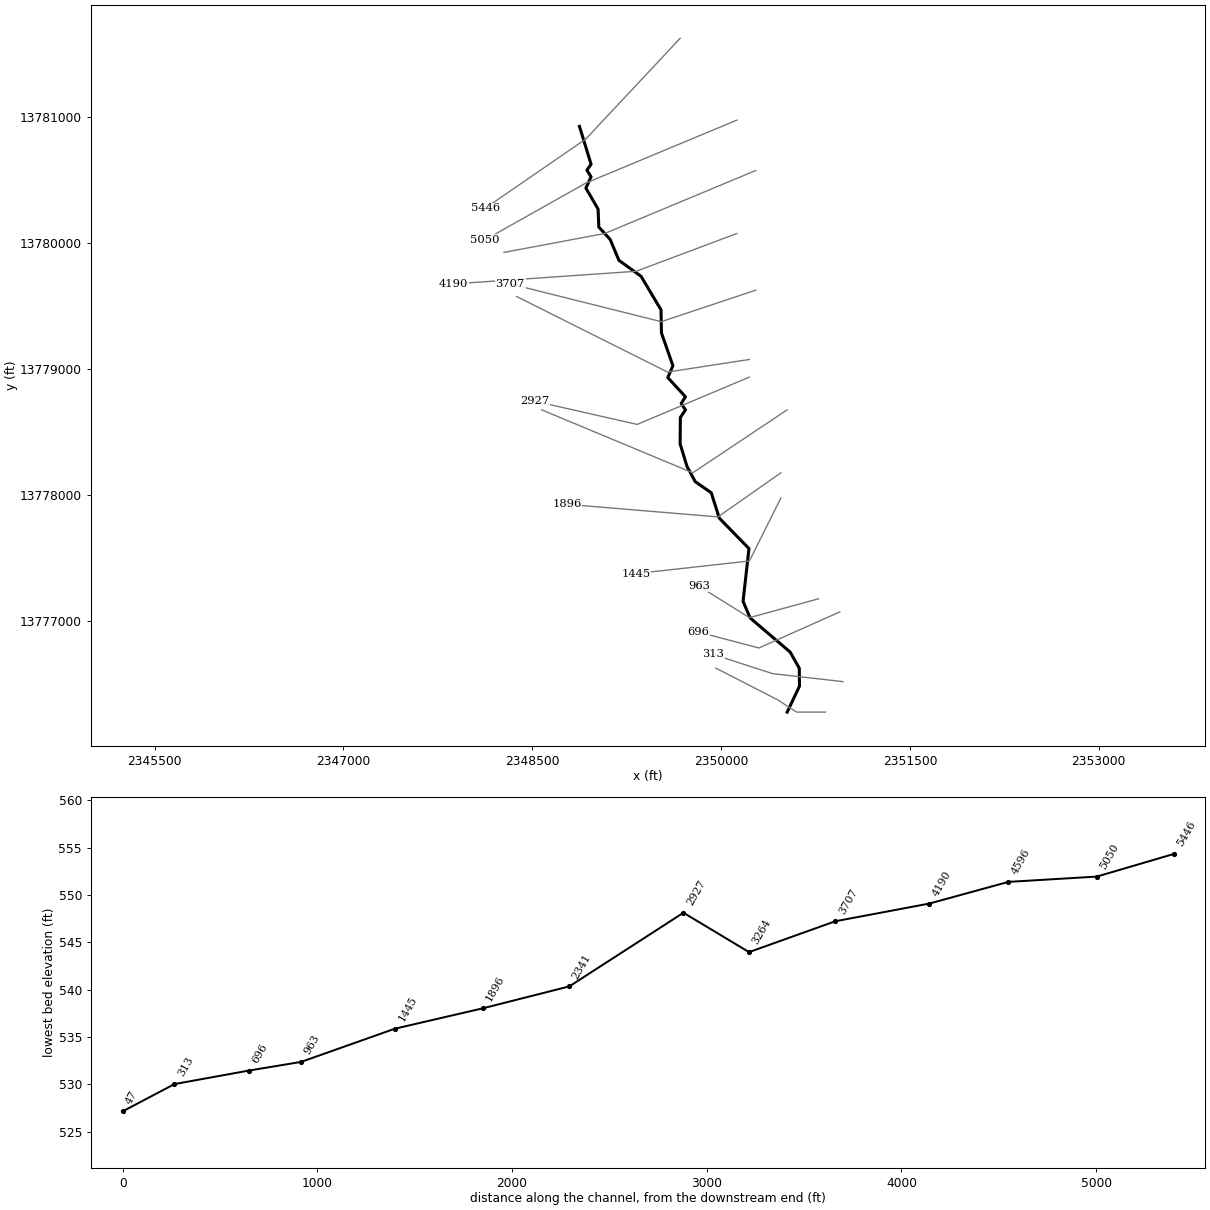
--- NASH TRIBUTARY 7.prj (project) ---

Proj Title=NASH TRIBUTARY 7 Base Level Engineering
Current Plan=p01
Default Exp/Contr=0.3,0.1
English Units
Geom File=g01
Flow File=f01
Plan File=p01
BEGIN DESCRIPTION:
NASH TRIBUTARY 7
END DESCRIPTION:

--- NASH TRIBUTARY 7.p01 (plan) ---

Plan Title=Multiple Run
Short Identifier=Multiple
Geom File=g01
Flow File=f01
Subcritical Flow
K Sum by GR= 0
Std Step Tol= 0.01
Critical Tol= 0.01
Num of Std Step Trials= 20
Max Error Tol= 0.3
Flow Tol Ratio= 0.001
Split Flow NTrial= 30
Split Flow Tol= 0.02
Split Flow Ratio= 0.02
Log Output Level= 0
Friction Slope Method= 1
Unsteady Friction Slope Method= 2
Unsteady Bridges Friction Slope Method= 1
Parabolic Critical Depth
Global Vel Dist=  1 , 1 , 1
Global Log Level= 0
CheckData=True
Encroach Param= -1, 0, 0, 0
BEGIN DESCRIPTION:
Multiple Run
END DESCRIPTION:

--- NASH TRIBUTARY 7.f01 (steady flow) ---

Flow Title=Multiple
Number of Profiles=7
Profile Names=10-year,25-year,50-year,1pct_min,100-year,1pct_plu,500-year
River Rch & RM= NASH TRIBUTARY 7,Reach-1,5446
     612     979    1308     845    1686    3365    2779
River Rch & RM= NASH TRIBUTARY 7,Reach-1,3707
     886    1446    1957    1279    2553    5093    4308
Boundary for River Rch & Prof#=NASH TRIBUTARY 7,Reach-1,1
Up Type=0
Dn Type=3
Dn Slope=0.005
Boundary for River Rch & Prof#=NASH TRIBUTARY 7,Reach-1,2
Up Type=0
Dn Type=3
Dn Slope=0.005
Boundary for River Rch & Prof#=NASH TRIBUTARY 7,Reach-1,3
Up Type=0
Dn Type=3
Dn Slope=0.005
Boundary for River Rch & Prof#=NASH TRIBUTARY 7,Reach-1,4
Up Type=0
Dn Type=3
Dn Slope=0.005
Boundary for River Rch & Prof#=NASH TRIBUTARY 7,Reach-1,5
Up Type=0
Dn Type=3
Dn Slope=0.005
Boundary for River Rch & Prof#=NASH TRIBUTARY 7,Reach-1,6
Up Type=0
Dn Type=3
Dn Slope=0.005
Boundary for River Rch & Prof#=NASH TRIBUTARY 7,Reach-1,7
Up Type=0
Dn Type=3
Dn Slope=0.005

--- NASH TRIBUTARY 7.g01 (geometry) ---

Geom Title=Existing Conditions

River Reach=NASH TRIBUTARY 7,Reach-1
Reach XY= 30
      2348875.00     13780925.00      2348967.22     13780624.90
      2348933.55     13780578.33      2348967.19     13780525.09
      2348925.80     13780435.70      2349022.75     13780269.07
      2349028.55     13780126.47      2349119.15     13780027.29
      2349188.61     13779861.76      2349364.35     13779735.00
      2349522.76     13779469.07      2349526.22     13779285.51
      2349617.41     13779024.99      2349576.66     13778931.05
      2349717.02     13778778.33      2349683.04     13778725.01
      2349717.22     13778675.10      2349676.38     13778614.57
      2349674.64     13778404.85      2349728.82     13778226.58
      2349794.77     13778104.87      2349921.83     13778016.66
      2349985.76     13777815.32      2350221.47     13777573.53
      2350174.64     13777154.85      2350230.83     13777022.70
      2350548.73     13776751.88      2350621.26     13776623.44
      2350622.77     13776480.93      2350525.00     13776275.00

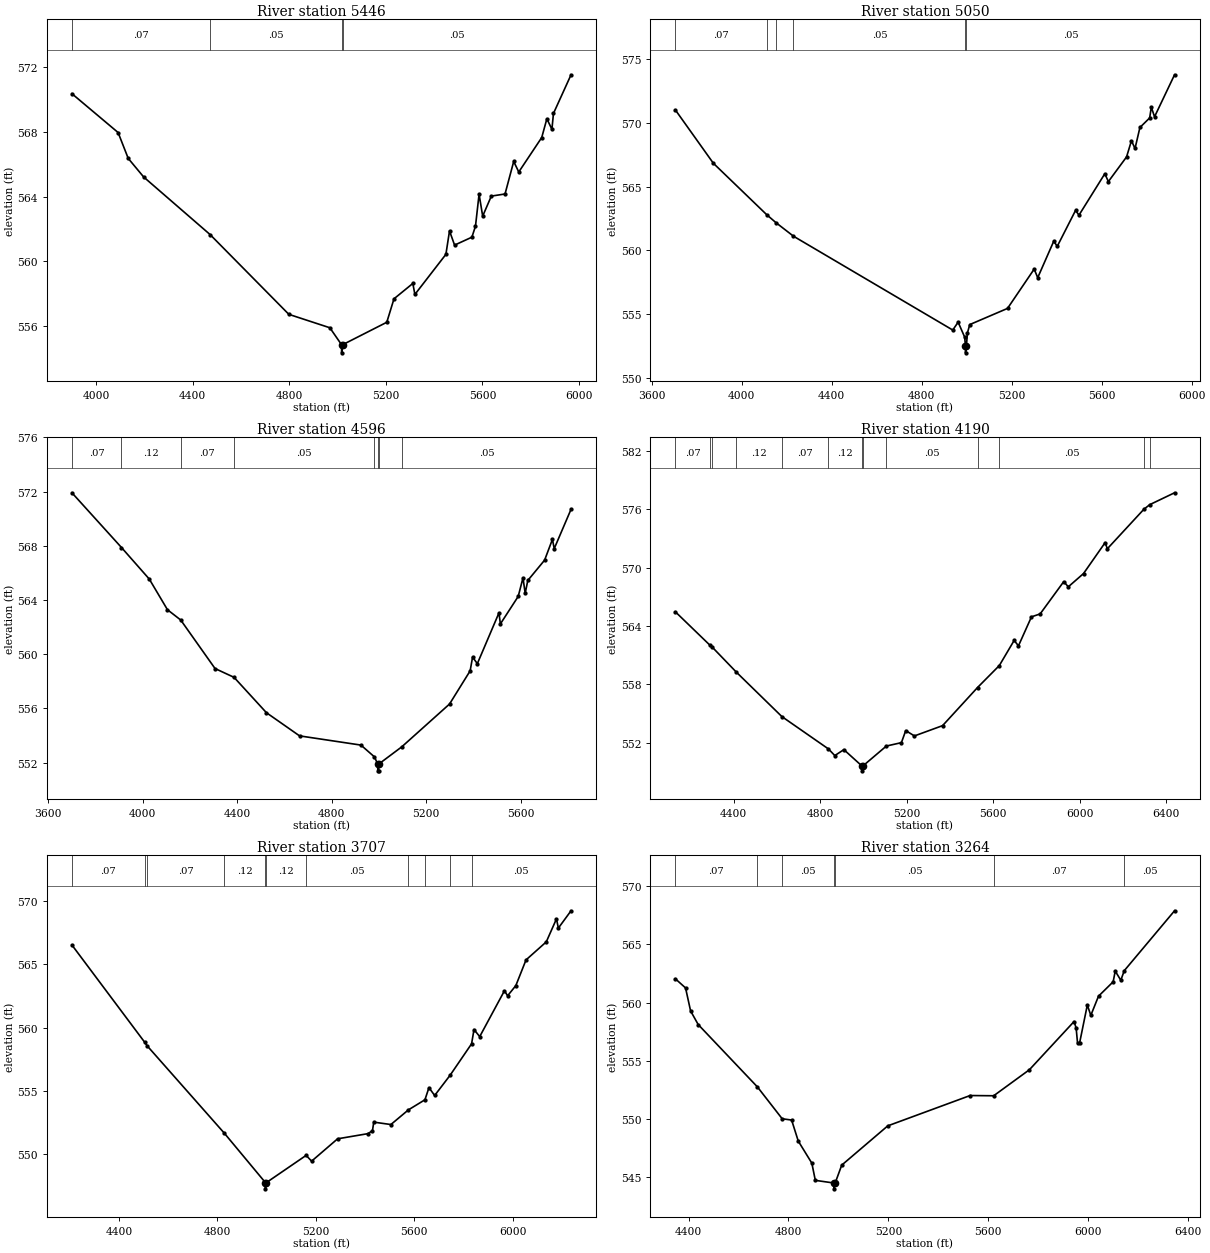
Type RM Length L Ch R = 1,5446,396,396,396
BEGIN DESCRIPTION:
NASH TRIBUTARY 7 11.0
END DESCRIPTION:
XS GIS Cut Line= 3
      2349674.97     13781624.97      2348925.00     13780825.00
      2348124.97     13780274.98
#Sta/Elev= 30
  3899.4  570.36  4090.6  567.96  4132.6  566.36  4196.6  565.21  4471.8  561.65
  4797.9  556.72  4967.8  555.89  5016.3  554.84  5016.5  554.34  5020.3  554.84
  5203.6  556.23  5233.4  557.68  5311.5  558.63  5320.0  557.95  5448.5  560.43
  5463.4  561.88  5484.4  561.00  5556.1  561.49  5571.0  562.17  5585.9  564.15
  5600.8  562.79  5636.6  564.03  5693.4  564.16  5729.3  566.17  5750.3  565.52
  5845.4  567.65  5866.7  568.81  5887.6  568.16  5894.0  569.14  5966.8  571.53
#Mann=4,-1,0
  3899.4    0.07       0  4471.8    0.05       0  5016.3    0.05       0
  5020.3    0.05       0
Bank Sta=5016.3,5020.3
Exp/Cntr=0.3,0.1

Type RM Length L Ch R = 1,5050,454,454,454
BEGIN DESCRIPTION:
NASH TRIBUTARY 7 10.0
END DESCRIPTION:
XS GIS Cut Line= 3
      2350125.04     13780975.02      2348925.00     13780475.00
      2348125.02     13780025.01
#Sta/Elev= 30
  3706.1  571.02  3874.6  566.84  4112.9  562.78  4153.2  562.17  4230.7  561.11
  4938.4  553.74  4962.3  554.36  4991.5  553.18  4994.8  552.45  4995.1  551.95
  4999.0  552.45  5003.4  553.51  5014.1  554.17  5181.8  555.44  5300.3  558.53
  5315.9  557.85  5387.0  560.71  5402.9  560.32  5483.9  563.13  5499.5  562.77
  5614.2  566.02  5629.9  565.40  5710.8  567.34  5732.5  568.61  5748.4  568.00
  5770.1  569.65  5813.4  570.40  5820.8  571.25  5835.1  570.49  5924.0  573.79
#Mann=6,-1,0
  3706.1    0.07       0  4112.9   0.035       0  4153.2    0.07       0
  4230.7    0.05       0  4994.8    0.05       0  4999.0    0.05       0
Bank Sta=4994.8,4999
Exp/Cntr=0.3,0.1

Type RM Length L Ch R = 1,4596,406,406,406
BEGIN DESCRIPTION:
NASH TRIBUTARY 7 9.0
END DESCRIPTION:
XS GIS Cut Line= 3
      2350274.97     13780574.99      2349075.00     13780075.00
      2348275.01     13779925.00
#Sta/Elev= 30
  3700.0  571.91  3909.9  567.87  4027.7  565.54  4104.6  563.28  4160.8  562.52
  4306.1  558.94  4386.6  558.29  4523.8  555.68  4664.1  553.97  4924.1  553.29
  4981.2  552.42  4995.1  551.89  4995.4  551.39  4999.2  551.39  4999.5  551.89
  5096.9  553.16  5299.3  556.32  5386.6  558.77  5396.8  559.78  5417.1  559.30
  5508.7  563.05  5514.6  562.23  5590.1  564.26  5610.4  565.63  5619.7  564.49
  5630.8  565.44  5702.0  566.94  5735.1  568.47  5742.7  567.79  5813.9  570.69
#Mann=8,-1,0
  3700.0    0.07       0  3909.9    0.12       0  4160.8    0.07       0
  4386.6    0.05       0  4981.2    0.07       0  4995.1    0.05       0
  4999.5    0.07       0  5096.9    0.05       0
Bank Sta=4995.1,4999.5
Exp/Cntr=0.3,0.1

Type RM Length L Ch R = 1,4190,483,483,483
BEGIN DESCRIPTION:
NASH TRIBUTARY 7 8.0
END DESCRIPTION:
XS GIS Cut Line= 3
      2350125.02     13780075.01      2349325.00     13779775.00
      2347874.97     13779675.00
#Sta/Elev= 30
  4131.4  565.45  4289.1  562.06  4299.1  561.88  4413.1  559.25  4623.6  554.68
  4839.0  551.35  4868.3  550.67  4910.2  551.28  4993.7  549.60  4994.0  549.10
  4998.1  549.60  5106.7  551.65  5176.3  552.00  5196.3  553.24  5236.4  552.69
  5366.7  553.75  5528.3  557.67  5629.1  559.93  5697.5  562.51  5717.6  561.96
  5777.7  564.94  5817.8  565.24  5926.8  568.56  5948.1  568.03  6018.3  569.39
  6118.5  572.58  6128.5  571.94  6297.7  576.01  6324.8  576.48  6439.3  577.70
#Mann=13,-1,0
  4131.4    0.07       0  4289.1    0.12       0  4299.1    0.07       0
  4413.1    0.12       0  4623.6    0.07       0  4839.0    0.12       0
  4993.7    0.05       0  4998.1    0.12       0  5106.7    0.05       0
  5528.3    0.07       0  5629.1    0.05       0  6297.7    0.07       0
  6324.8    0.05       0
Bank Sta=4993.7,4998.1
Exp/Cntr=0.3,0.1

Type RM Length L Ch R = 1,3707,443,443,443
BEGIN DESCRIPTION:
NASH TRIBUTARY 7 7.0
END DESCRIPTION:
XS GIS Cut Line= 3
      2350275.03     13779625.01      2349525.00     13779375.00
      2348325.03     13779674.99
#Sta/Elev= 30
  4209.4  566.53  4504.3  558.85  4515.9  558.53  4827.8  551.65  4995.1  547.73
  4995.4  547.23  4999.7  547.73  5160.9  549.88  5183.0  549.42  5288.6  551.19
  5412.3  551.60  5430.3  551.84  5435.5  552.51  5505.1  552.32  5576.2  553.48
  5643.4  554.28  5659.7  555.24  5682.9  554.62  5745.6  556.22  5832.9  558.71
  5842.7  559.84  5865.9  559.28  5966.4  562.91  5979.2  562.51  6012.7  563.32
  6054.0  565.35  6136.4  566.78  6177.7  568.60  6185.4  567.87  6236.9  569.24
#Mann=11,-1,0
  4209.4    0.07       0  4504.3   0.035       0  4515.9    0.07       0
  4827.8    0.12       0  4995.1    0.05       0  4999.7    0.12       0
  5160.9    0.05       0  5576.2    0.07       0  5643.4    0.05       0
  5745.6    0.07       0  5832.9    0.05       0
Bank Sta=4995.1,4999.7
Exp/Cntr=0.3,0.1

Type RM Length L Ch R = 1,3264,337,337,337
BEGIN DESCRIPTION:
NASH TRIBUTARY 7 6.0
END DESCRIPTION:
XS GIS Cut Line= 3
      2350225.03     13779075.00      2349575.00     13778975.00
      2348375.02     13779574.99
#Sta/Elev= 30
  4347.2  562.04  4387.7  561.26  4407.9  559.28  4438.3  558.11  4675.6  552.74
  4774.8  550.00  4812.6  549.89  4839.2  548.08  4893.6  546.18  4907.5  544.70
  4982.3  544.47  4982.6  543.97  4987.0  544.47  5013.3  546.01  5197.7  549.39
  5527.6  552.00  5622.0  551.98  5765.1  554.22  5944.0  558.37  5952.4  557.80
  5958.0  556.49  5966.4  556.55  5997.1  559.79  6011.1  558.90  6041.9  560.55
  6100.6  561.79  6108.9  562.71  6131.3  561.92  6144.9  562.74  6346.5  567.90
#Mann=7,-1,0
  4347.2    0.07       0  4675.6    0.12       0  4774.8    0.05       0
  4982.3    0.05       0  4987.0    0.05       0  5622.0    0.07       0
  6144.9    0.05       0
Bank Sta=4982.3,4987
Exp/Cntr=0.3,0.1

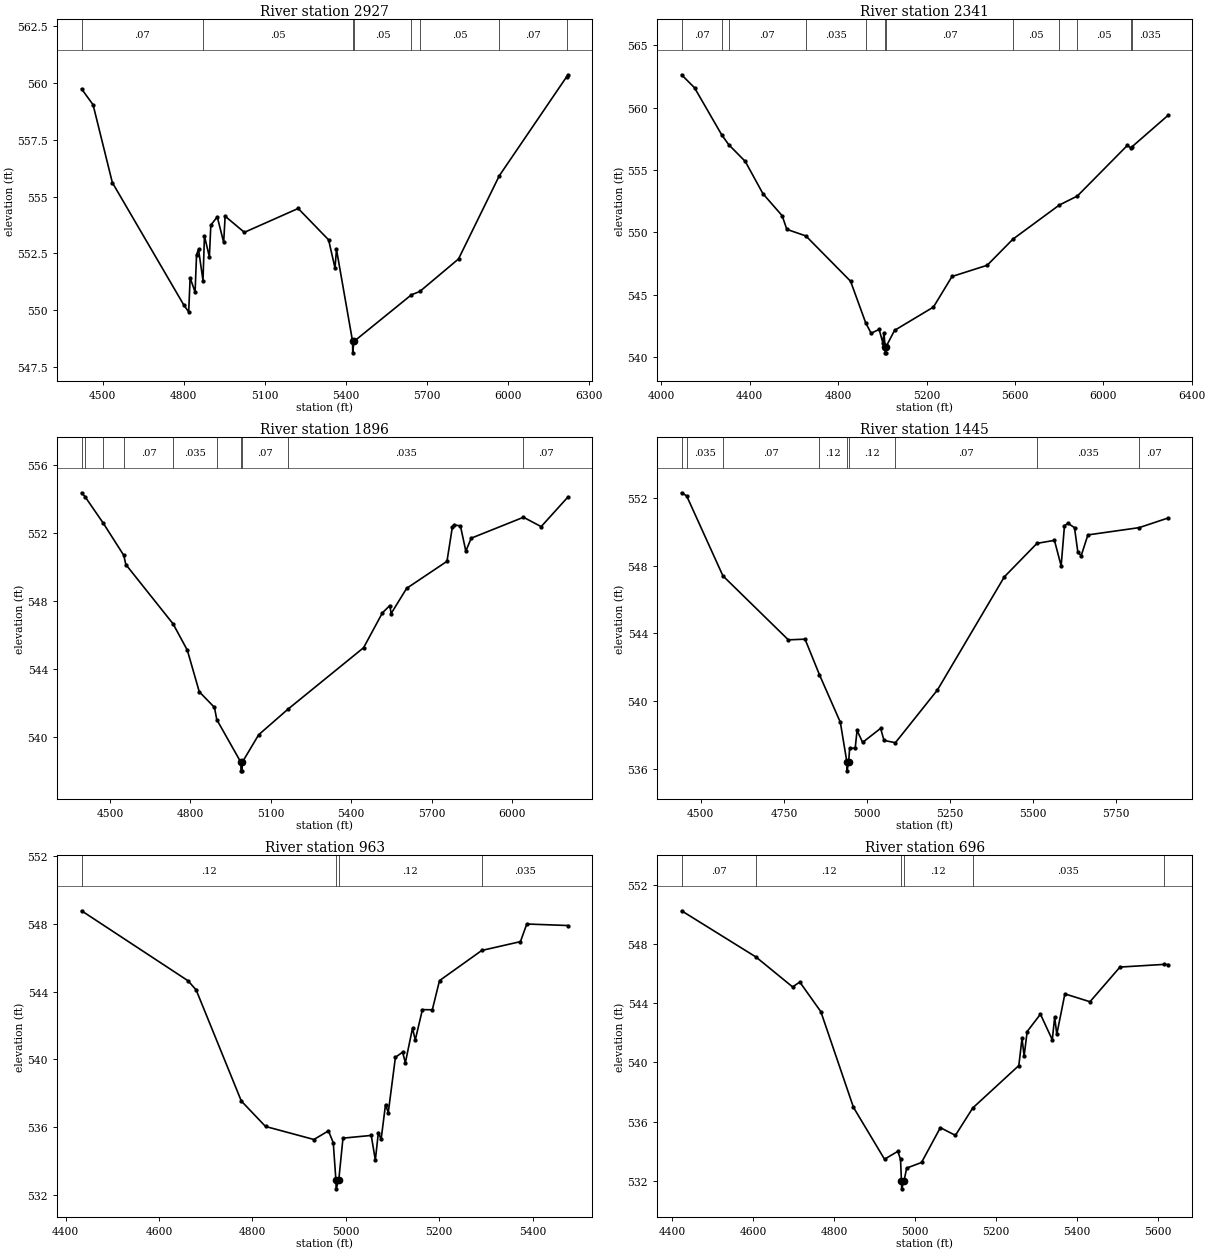
Type RM Length L Ch R = 1,2927,586,586,586
BEGIN DESCRIPTION:
NASH TRIBUTARY 7 5.0
END DESCRIPTION:
XS GIS Cut Line= 3
      2350224.00     13778934.63      2349333.34     13778559.28
      2348519.49     13778743.67
#Sta/Elev= 30
  4421.5  559.74  4464.2  559.04  4535.4  555.62  4800.2  550.23  4818.1  549.93
  4823.5  551.43  4841.8  550.80  4847.2  552.45  4854.5  552.68  4871.1  551.31
  4876.4  553.27  4894.7  552.35  4900.1  553.75  4923.9  554.11  4947.6  552.99
  4953.0  554.14  5024.2  553.43  5223.4  554.48  5336.0  553.10  5359.8  551.86
  5365.2  552.68  5424.9  548.63  5425.3  548.13  5429.7  548.63  5642.4  550.68
  5673.8  550.83  5817.0  552.26  5968.0  555.92  6217.1  560.27  6222.5  560.36
#Mann=8,-1,0
  4421.5    0.07       0  4871.1    0.05       0  5424.9    0.05       0
  5429.7    0.05       0  5642.4    0.07       0  5673.8    0.05       0
  5968.0    0.07       0  6217.1   0.035       0
Bank Sta=5424.9,5429.7
Exp/Cntr=0.3,0.1

Type RM Length L Ch R = 1,2341,445,445,445
BEGIN DESCRIPTION:
NASH TRIBUTARY 7 4.0
END DESCRIPTION:
XS GIS Cut Line= 3
      2350525.00     13778675.00      2349775.00     13778175.00
      2348574.99     13778675.00
#Sta/Elev= 30
  4091.6  562.64  4150.2  561.60  4273.4  557.82  4305.4  557.03  4380.0  555.69
  4459.7  553.11  4546.8  551.34  4567.8  550.25  4654.2  549.72  4856.3  546.09
  4924.8  542.75  4949.4  541.92  4985.5  542.23  5002.2  541.17  5007.6  541.95
  5012.2  540.85  5012.6  540.35  5016.8  540.35  5017.1  540.85  5055.3  542.15
  5231.3  544.02  5315.3  546.47  5474.5  547.37  5590.8  549.46  5800.2  552.19
  5882.4  552.92  6108.8  556.98  6123.7  556.78  6129.2  556.86  6293.0  559.39
#Mann=12,-1,0
  4091.6    0.07       0  4273.4   0.035       0  4305.4    0.07       0
  4654.2   0.035       0  4924.8    0.07       0  5012.2    0.05       0
  5017.1    0.07       0  5590.8    0.05       0  5800.2    0.07       0
  5882.4    0.05       0  6123.7    0.07       0  6129.2   0.035       0
Bank Sta=5012.2,5017.1
Exp/Cntr=0.3,0.1

Type RM Length L Ch R = 1,1896,451,451,451
BEGIN DESCRIPTION:
NASH TRIBUTARY 7 3.0
END DESCRIPTION:
XS GIS Cut Line= 3
      2350475.02     13778175.01      2349975.00     13777825.00
      2348775.01     13777925.00
#Sta/Elev= 30
  4394.1  554.38  4407.2  554.15  4475.2  552.59  4551.6  550.70  4559.3  550.16
  4735.6  546.67  4788.7  545.12  4833.1  542.68  4889.8  541.76  4898.5  541.04
  4988.4  538.53  4988.8  538.03  4993.0  538.03  4993.4  538.53  5054.6  540.15
  5163.5  541.65  5446.0  545.27  5516.2  547.32  5543.8  547.75  5548.8  547.28
  5606.5  548.76  5757.0  550.35  5777.1  552.37  5784.6  552.49  5807.2  552.43
  5827.3  550.95  5847.4  551.71  6042.3  552.94  6108.3  552.39  6208.6  554.14
#Mann=10,-1,0
  4394.1    0.12       0  4407.2    0.07       0  4475.2    0.12       0
  4551.6    0.07       0  4735.6   0.035       0  4898.5    0.07       0
  4988.4    0.05       0  4993.4    0.07       0  5163.5   0.035       0
  6042.3    0.07       0
Bank Sta=4988.4,4993.4
Exp/Cntr=0.3,0.1

Type RM Length L Ch R = 1,1445,482,482,482
BEGIN DESCRIPTION:
NASH TRIBUTARY 7 2.0
END DESCRIPTION:
XS GIS Cut Line= 3
      2350474.99     13777974.99      2350225.00     13777475.00
      2349325.04     13777375.00
#Sta/Elev= 30
  4442.0  552.31  4457.2  552.13  4566.5  547.40  4763.4  543.62  4813.7  543.66
  4857.0  541.56  4919.9  538.75  4939.8  536.38  4940.2  535.88  4944.8  536.38
  4947.9  537.20  4964.7  537.23  4970.3  538.27  4987.0  537.56  5041.2  538.39
  5051.3  537.68  5085.6  537.54  5212.3  540.66  5413.5  547.34  5511.8  549.32
  5564.4  549.50  5584.6  547.99  5594.6  550.36  5604.7  550.51  5624.8  550.25
  5634.9  548.80  5644.9  548.59  5665.1  549.82  5819.4  550.25  5906.5  550.82
#Mann=9,-1,0
  4442.0    0.07       0  4457.2   0.035       0  4566.5    0.07       0
  4857.0    0.12       0  4939.8    0.05       0  4944.8    0.12       0
  5085.6    0.07       0  5511.8   0.035       0  5819.4    0.07       0
Bank Sta=4939.8,4944.8
Exp/Cntr=0.3,0.1

Type RM Length L Ch R = 1,963,267,267,267
BEGIN DESCRIPTION:
NASH TRIBUTARY 7 1.0
END DESCRIPTION:
XS GIS Cut Line= 3
      2350775.04     13777175.01      2350225.00     13777025.00
      2349825.03     13777274.98
#Sta/Elev= 30
  4434.2  548.77  4662.3  544.64  4679.6  544.10  4776.3  537.55  4828.1  536.05
  4931.8  535.28  4962.9  535.79  4973.2  535.09  4978.9  532.87  4979.4  532.37
  4984.9  532.87  4994.0  535.36  5054.5  535.52  5063.3  534.07  5069.8  535.69
  5075.7  535.29  5085.1  537.34  5091.0  536.87  5106.3  540.13  5121.7  540.43
  5127.6  539.81  5142.9  541.84  5148.8  541.15  5164.1  542.94  5185.3  542.93
  5200.7  544.65  5291.2  546.43  5374.0  546.95  5387.6  547.99  5476.0  547.90
#Mann=4,-1,0
  4434.2    0.12       0  4978.9    0.05       0  4984.9    0.12       0
  5291.2   0.035       0
Bank Sta=4978.9,4984.9
Exp/Cntr=0.3,0.1

Type RM Length L Ch R = 1,696,383,383,383
BEGIN DESCRIPTION:
B19800
END DESCRIPTION:
XS GIS Cut Line= 3
      2350942.87     13777070.57      2350300.36     13776784.30
      2349818.46     13776911.12
#Sta/Elev= 30
  4422.7  550.23  4606.5  547.11  4697.0  545.09  4714.7  545.42  4766.7  543.42
  4847.3  536.96  4924.0  533.46  4956.8  533.99  4963.5  533.46  4965.9  531.96
  4966.4  531.46  4971.9  531.96  4978.7  532.86  5015.4  533.24  5061.9  535.59
  5099.1  535.07  5142.0  536.92  5255.7  539.78  5263.6  541.61  5268.8  540.44
  5276.4  542.08  5309.1  543.25  5338.4  541.52  5344.3  543.06  5349.5  541.89
  5369.5  544.62  5431.5  544.09  5505.6  546.43  5613.7  546.61  5624.4  546.60
#Mann=6,-1,0
  4422.7    0.07       0  4606.5    0.12       0  4965.9    0.05       0
  4971.9    0.12       0  5142.0   0.035       0  5613.7    0.07       0
Bank Sta=4965.9,4971.9
Exp/Cntr=0.3,0.1

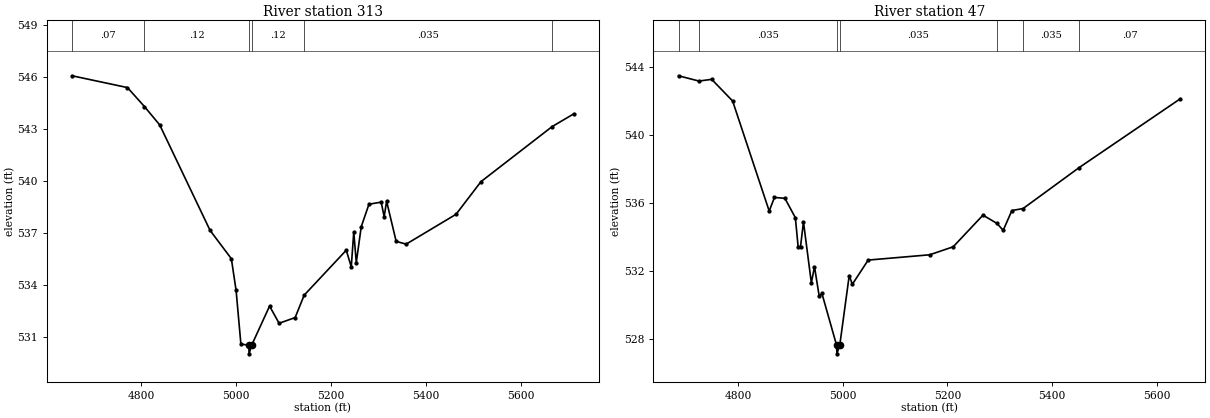
Type RM Length L Ch R = 1,313,266,266,266
BEGIN DESCRIPTION:
B19799
END DESCRIPTION:
XS GIS Cut Line= 3
      2350968.41     13776517.10      2350408.51     13776580.72
      2349938.89     13776733.03
#Sta/Elev= 30
  4654.8  546.05  4771.5  545.37  4807.2  544.28  4839.4  543.22  4945.6  537.14
  4990.4  535.51  5000.4  533.68  5010.5  530.59  5027.2  530.53  5027.7  530.03
  5033.2  530.53  5070.9  532.78  5091.0  531.79  5124.8  532.12  5143.8  533.41
  5232.5  536.00  5243.0  535.04  5248.3  537.05  5253.6  535.29  5264.0  537.35
  5280.3  538.65  5306.1  538.77  5312.3  537.93  5317.5  538.82  5337.6  536.51
  5358.7  536.35  5463.8  538.07  5516.3  539.95  5666.1  543.12  5712.0  543.86
#Mann=6,-1,0
  4654.8    0.07       0  4807.2    0.12       0  5027.2    0.05       0
  5033.2    0.12       0  5143.8   0.035       0  5666.1    0.07       0
Bank Sta=5027.2,5033.2
Exp/Cntr=0.3,0.1

Type RM Length L Ch R = 1,47,0,0,0
BEGIN DESCRIPTION:
B19798
END DESCRIPTION:
XS GIS Cut Line= 4
      2350828.40     13776275.35      2350599.37     13776275.35
      2350453.04     13776370.78      2349958.42     13776624.43
#Sta/Elev= 30
  4685.8  543.49  4724.8  543.18  4749.2  543.28  4789.2  542.01  4859.2  535.54
  4869.2  536.34  4889.2  536.29  4909.2  535.15  4914.5  533.45  4919.1  533.45
  4924.7  534.90  4939.8  531.32  4945.8  532.27  4954.9  530.52  4960.0  530.70
  4988.1  527.65  4988.6  527.15  4994.1  527.65  5012.2  531.75  5018.2  531.24
  5048.5  532.66  5166.0  532.97  5211.0  533.44  5268.0  535.30  5294.4  534.82
  5306.7  534.41  5323.3  535.57  5344.8  535.69  5451.7  538.09  5645.4  542.14
#Mann=7,-1,0
  4685.8    0.12       0  4724.8   0.035       0  4988.1   0.035       0
  4994.1   0.035       0  5294.4    0.07       0  5344.8   0.035       0
  5451.7    0.07       0
Bank Sta=4988.1,4994.1
Exp/Cntr=0.3,0.1

Chan Stop Cuts=-1