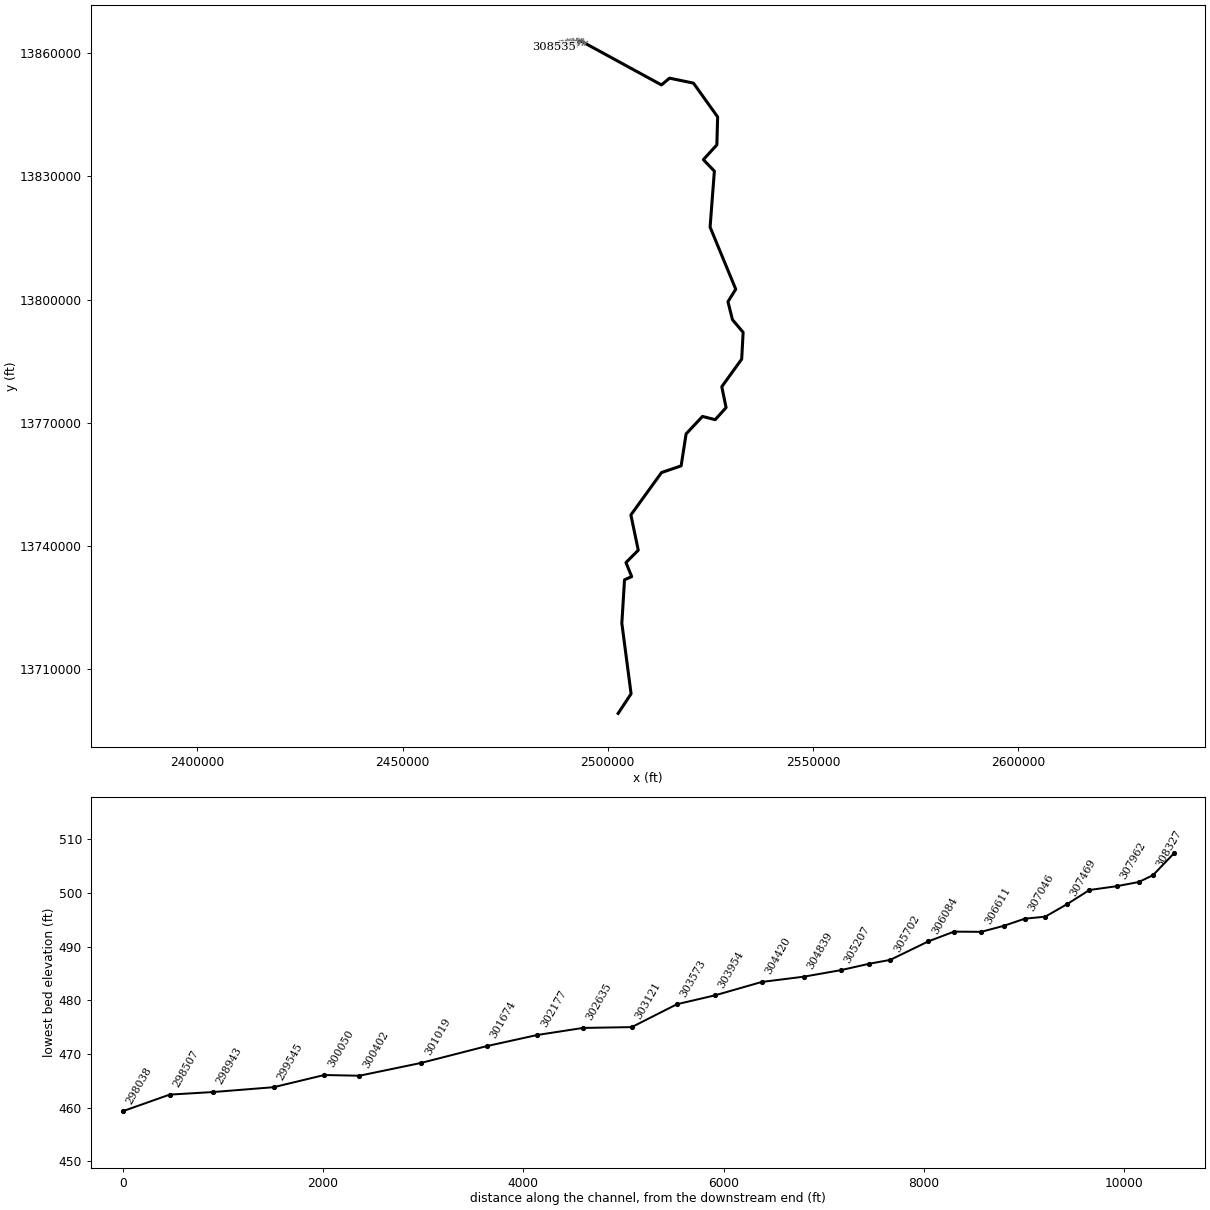
--- PEACH CREEK.prj (project) ---

Proj Title=PEACH CREEK Base Level Engineering
Current Plan=p01
Default Exp/Contr=0.3,0.1
English Units
Geom File=g01
Flow File=f01
Plan File=p01
Y Axis Title=Elevation
X Axis Title(PF)=Main Channel Distance
X Axis Title(XS)=Station
BEGIN DESCRIPTION:
PEACH CREEK
END DESCRIPTION:
DSS Export Rating Curves= 0
DSS Export Rating Curve Sorted= 0
DSS Export Volume Flow Curves= 0
DXF OffsetX= 0
DXF OffsetY= 0
DXF ScaleX= 1
DXF ScaleY= 10

--- PEACH CREEK.p01 (plan) ---

Plan Title=Multiple Run
Short Identifier=Multiple
Geom File=g01
Flow File=f01
Subcritical Flow
K Sum by GR= 0
Std Step Tol= 0.01
Critical Tol= 0.01
Num of Std Step Trials= 20
Max Error Tol= 0.3
Flow Tol Ratio= 0.001
Split Flow NTrial= 30
Split Flow Tol= 0.02
Split Flow Ratio= 0.02
Log Output Level= 0
Friction Slope Method= 1
Unsteady Friction Slope Method= 2
Unsteady Bridges Friction Slope Method= 1
Parabolic Critical Depth
Global Vel Dist=  1 , 1 , 1
Global Log Level= 0
CheckData=True
Encroach Param= -1, 0, 0, 0
BEGIN DESCRIPTION:
Multiple Run
END DESCRIPTION:

--- PEACH CREEK.f01 (steady flow) ---

Flow Title=Multiple
Number of Profiles=7
Profile Names=10-year,25-year,50-year,1pct_min,100-year,1pct_plu,500-year
River Rch & RM= PEACH CREEK,Reach-1,308535
     305     471     614     390     779    1554    1235
River Rch & RM= PEACH CREEK,Reach-1,307251
     380     593     780     499     996    1988    1603
River Rch & RM= PEACH CREEK,Reach-1,307046
     514     816    1086     701    1399    2791    2295
River Rch & RM= PEACH CREEK,Reach-1,305490
     650    1046    1404     914    1823    3638    3042
River Rch & RM= PEACH CREEK,Reach-1,304839
    1087    1797    2454    1622    3236    6458    5572
River Rch & RM= PEACH CREEK,Reach-1,301674
    1229    2034    2778    1835    3660    7304    6293
River Rch & RM= PEACH CREEK,Reach-1,298038
    1494    2494    3427    2275    4540    9058    7890
River Rch & RM= PEACH CREEK,Reach-1,296262
    1641    2745    3779    2512    5011    9999    8730
River Rch & RM= PEACH CREEK,Reach-1,295385
    1749    2919    4011    2658    5303   10581    9187
River Rch & RM= PEACH CREEK,Reach-1,292117
    1772    2951    4048    2678    5343   10661    9224
River Rch & RM= PEACH CREEK,Reach-1,290356
    2531    4278    5928    3957    7896   15755   13881
River Rch & RM= PEACH CREEK,Reach-1,288517
    2651    4483    6212    4147    8274   16509   14544
River Rch & RM= PEACH CREEK,Reach-1,287204
    2701    4566    6328    4224    8428   16816   14810
River Rch & RM= PEACH CREEK,Reach-1,285230
    2877    4876    6766    4521    9022   18000   15892
River Rch & RM= PEACH CREEK,Reach-1,284244
    2905    4914    6811    4545    9069   18095   15932
River Rch & RM= PEACH CREEK,Reach-1,279743
    3057    5180    7189    4803    9584   19122   16874
River Rch & RM= PEACH CREEK,Reach-1,278612
    3228    5480    7615    5093   10162   20275   17930
River Rch & RM= PEACH CREEK,Reach-1,276388
    3325    5653    7862    5262   10500   20949   18556
River Rch & RM= PEACH CREEK,Reach-1,272194
    3486    5934    8261    5533   11041   22029   19541
River Rch & RM= PEACH CREEK,Reach-1,270987
    3515    5978    8317    5568   11109   22165   19636
River Rch & RM= PEACH CREEK,Reach-1,266889
    3683    6275    8741    5858   11688   23320   20705
River Rch & RM= PEACH CREEK,Reach-1,265451
    3717    6324    8798    5889   11750   23443   20760
River Rch & RM= PEACH CREEK,Reach-1,261709
    5491    9454   13263    8943   17844   35604   31994
River Rch & RM= PEACH CREEK,Reach-1,259332
    5632    9688   13585    9155   18267   36446   32708
River Rch & RM= PEACH CREEK,Reach-1,251084
    5667    9741   13652    9194   18345   36602   32806
River Rch & RM= PEACH CREEK,Reach-1,248339
    5716    9799   13707    9213   18382   36676   32738
River Rch & RM= PEACH CREEK,Reach-1,240159
    5957   10218   14298    9612   19179   38266   34171
River Rch & RM= PEACH CREEK,Reach-1,232963
    6013   10308   14419    9689   19333   38575   34418
River Rch & RM= PEACH CREEK,Reach-1,230726
    5994   10258   14333    9619   19193   38295   34082
River Rch & RM= PEACH CREEK,Reach-1,220970
    6338   10843   15146   10160   20273   40449   35964
River Rch & RM= PEACH CREEK,Reach-1,211306
    6796   11637   16266   10918   21784   43465   38683
River Rch & RM= PEACH CREEK,Reach-1,202053
    6865   11755   16430   11027   22001   43898   39062
River Rch & RM= PEACH CREEK,Reach-1,200082
    6940   11882   16607   11146   22238   44372   39479
River Rch & RM= PEACH CREEK,Reach-1,196988
    6950   11892   16616   11146   22240   44375   39447
River Rch & RM= PEACH CREEK,Reach-1,192911
    6947   11877   16584   11118   22184   44262   39296
River Rch & RM= PEACH CREEK,Reach-1,188799
   11233   19392   27269   18399   36711   73248   65823
River Rch & RM= PEACH CREEK,Reach-1,185193
   11311   19488   27368   18439   36791   73407   65775
River Rch & RM= PEACH CREEK,Reach-1,159281
   14282   24657   34687   23404   46697   93173   83689
River Rch & RM= PEACH CREEK,Reach-1,146660
   14744   25434   35762   24115   48116   96005   86125
River Rch & RM= PEACH CREEK,Reach-1,140645
   15815   27158   38072   25590   51059  101876   90782
River Rch & RM= PEACH CREEK,Reach-1,117831
   16262   27925   39148   26314   52504  104759   93347
River Rch & RM= PEACH CREEK,Reach-1,108251
   16117   27626   38680   25965   51808  103370   91868
River Rch & RM= PEACH CREEK,Reach-1,106253
   16284   27899   39051   26206   52288  104328   92655
River Rch & RM= PEACH CREEK,Reach-1,94800
   25458   44165   62402   42272   84345  168290  152196
River Rch & RM= PEACH CREEK,Reach-1,93188
   25487   44111   62225   42082   83964  167531  150993
River Rch & RM= PEACH CREEK,Reach-1,74105
   25420   43944   61943   41858   83517  166638  149947
River Rch & RM= PEACH CREEK,Reach-1,70945
   26790   46269   65185   44023   87838  175260  157504
River Rch & RM= PEACH CREEK,Reach-1,46739
   27222   46940   66061   44567   88923  177424  159092
River Rch & RM= PEACH CREEK,Reach-1,31546
   27467   47358   66645   44958   89702  178979  160460
River Rch & RM= PEACH CREEK,Reach-1,22666
   27573   47525   66867   45098   89982  179538  160891
River Rch & RM= PEACH CREEK,Reach-1,19789
   27494   47349   66581   44878   89544  178663  159915
Boundary for River Rch & Prof#=PEACH CREEK,Reach-1,1
Up Type=0
Dn Type=3
Dn Slope=0.0005
Boundary for River Rch & Prof#=PEACH CREEK,Reach-1,2
Up Type=0
Dn Type=3
Dn Slope=0.0005
Boundary for River Rch & Prof#=PEACH CREEK,Reach-1,3
Up Type=0
Dn Type=3
Dn Slope=0.0005
Boundary for River Rch & Prof#=PEACH CREEK,Reach-1,4
Up Type=0
Dn Type=3
Dn Slope=0.0005
Boundary for River Rch & Prof#=PEACH CREEK,Reach-1,5
Up Type=0
Dn Type=3
Dn Slope=0.0005
Boundary for River Rch & Prof#=PEACH CREEK,Reach-1,6
Up Type=0
Dn Type=3
Dn Slope=0.0005
Boundary for River Rch & Prof#=PEACH CREEK,Reach-1,7
Up Type=0
Dn Type=3
Dn Slope=0.0005

--- PEACH CREEK.g01 (geometry) ---

Geom Title=Existing Conditions
Program Version=4.10

River Reach=PEACH CREEK     ,Reach-1
Reach XY= 30
        2486825.       13861975.      2493469.15     13862972.94
      2513076.56     13852278.76      2515045.13     13853925.18
      2520873.53     13852721.47      2526764.06     13844485.44
      2526571.57     13837676.22      2523282.18     13834075.33
      2525967.69     13831274.89      2524925.23     13817640.21
      2531173.41     13802518.95       2529274.9     13799459.79
       2530376.5     13795080.87      2532975.22     13792009.73
      2532621.38      13785476.5       2527776.1     13778764.45
      2528816.98     13773668.66      2526173.41     13770728.82
      2523068.79      13771517.2      2519080.59     13767269.39
       2517867.2     13759468.16      2513100.84      13757852.3
       2505626.9      13747519.3        2507425.       13738925.
      2504426.49     13735919.16      2505825.25     13732494.92
      2504075.54     13731713.92      2503424.12       13721125.
      2505675.37     13703945.21        2502525.       13699175.

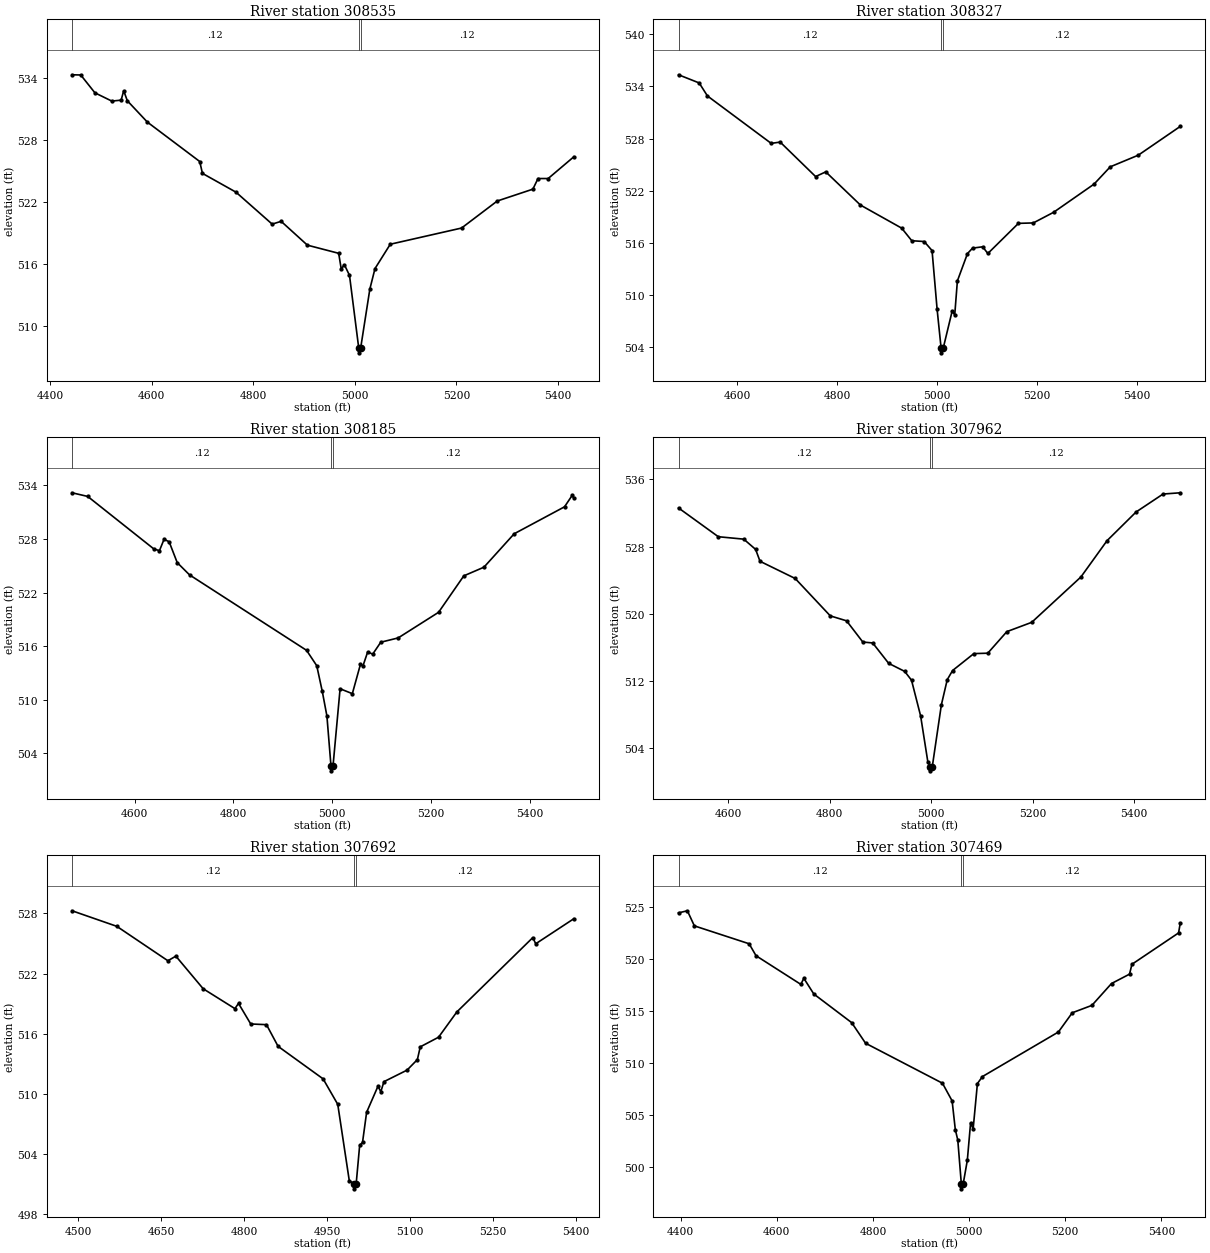
Type RM Length L Ch R = 1 ,308535  ,208,208,208
BEGIN DESCRIPTION:
B20008
END DESCRIPTION:
XS GIS Cut Line= 3
      2486760.97      13862521.8      2486858.69     13862019.23
      2486895.92     13861544.57
#Sta/Elev= 30
  4443.2  534.33  4460.3  534.31  4488.2  532.58  4521.4  531.78  4539.8  531.87
  4544.9  532.78    4552  531.81  4591.5  529.74  4694.6  525.92  4699.9  524.77
  4765.9  522.95  4837.2  519.85  4854.9  520.12  4906.6  517.81  4968.2  517.02
  4973.2  515.51  4979.5  515.91  4989.5  514.88  5007.6  507.87  5007.8  507.37
  5011.6  507.87  5029.6  513.56  5039.7  515.54  5069.8   517.9  5210.2  519.47
  5280.4  522.09  5350.6  523.24  5360.7  524.27  5380.7  524.27  5431.3  526.38
#Mann= 3 ,-1 , 0
  4443.2     .12       0  5007.6     .05       0  5011.6     .12       0
Bank Sta=5007.6,5011.6
XS Rating Curve= 0 ,0
Exp/Cntr=0.3,0.1

Type RM Length L Ch R = 1 ,308327  ,142,142,142
BEGIN DESCRIPTION:
B20007
END DESCRIPTION:
XS GIS Cut Line= 2
      2486970.38     13862535.77      2487133.26     13861544.56
#Sta/Elev= 30
  4482.6  535.34  4523.9   534.4  4540.5   532.9  4668.1  527.44  4686.1  527.59
    4757  523.62  4777.3  524.16  4846.7  520.34  4929.3  517.68  4949.5  516.23
  4974.3  516.14  4990.1   515.1  5000.2  508.35  5008.3  503.82  5008.6  503.32
  5012.3  503.82  5030.4  508.14  5035.5  507.69  5040.8   511.6    5061  514.75
  5071.2  515.38  5091.4  515.53  5101.8  514.76    5163  518.23  5192.8  518.28
  5233.3   519.5  5314.4  522.75  5346.8  524.74  5402.9  526.08  5487.1   529.4
#Mann= 3 ,-1 , 0
  4482.6     .12       0  5008.3     .05       0  5012.3     .12       0
Bank Sta=5008.3,5012.3
XS Rating Curve= 0 ,0
Exp/Cntr=0.3,0.1

Type RM Length L Ch R = 1 ,308185  ,223,223,223
BEGIN DESCRIPTION:
B20006
END DESCRIPTION:
XS GIS Cut Line= 3
      2487068.11     13862535.78      2487235.64     13861865.66
      2487300.39      13861546.5
#Sta/Elev= 30
  4473.3  533.17    4505  532.76    4639  526.88  4650.3  526.69  4659.6  527.96
  4669.9  527.69  4686.3  525.35  4711.2  523.98  4948.3  515.53  4968.9  513.81
  4980.1  510.94  4989.5  508.18  4997.8  502.54    4998  502.04  5001.8  502.54
  5016.2  511.23    5041  510.68  5057.4  513.96  5062.6   513.8    5072  515.34
  5082.3  515.11  5098.6  516.44  5133.8  516.92  5215.7  519.79  5266.8  523.87
  5307.6  524.84  5368.8  528.58  5470.8   531.6  5486.9  532.93  5489.7  532.53
#Mann= 3 ,-1 , 0
  4473.3     .12       0  4997.8     .05       0  5001.8     .12       0
Bank Sta=4997.8,5001.8
XS Rating Curve= 0 ,0
Exp/Cntr=0.3,0.1

Type RM Length L Ch R = 1 ,307962  ,270,270,270
BEGIN DESCRIPTION:
B20005
END DESCRIPTION:
XS GIS Cut Line= 3
       2487249.6     13862549.74      2487431.09     13861986.65
      2487625.89      13861638.8
#Sta/Elev= 30
  4501.4   532.6  4579.9  529.17  4630.1  528.88  4653.5  527.66  4662.2  526.24
  4731.6  524.19  4800.9  519.73    4833  519.14  4865.1  516.61  4884.6   516.5
  4916.1  514.07  4947.7  513.11  4961.2  512.06  4979.2  507.79  4993.3  502.36
  4998.2  501.75  4998.4  501.25  5002.2  501.75  5020.1  509.12  5031.7  512.12
  5042.2  513.21  5084.2  515.23  5111.7  515.28  5149.3  517.85  5198.4  518.96
  5295.5  524.37  5347.1   528.7  5404.4  532.12  5457.6  534.26  5491.7  534.41
#Mann= 3 ,-1 , 0
  4501.4     .12       0  4998.2     .05       0  5002.2     .12       0
Bank Sta=4998.2,5002.2
XS Rating Curve= 0 ,0
Exp/Cntr=0.3,0.1

Type RM Length L Ch R = 1 ,307692  ,223,223,223
BEGIN DESCRIPTION:
B20004
END DESCRIPTION:
XS GIS Cut Line= 3
      2487361.31     13862535.76       2487631.2     13862210.03
      2487770.42     13861745.98
#Sta/Elev= 30
  4488.4  528.26  4569.3  526.71  4661.7  523.28  4676.1  523.74  4725.5  520.49
  4782.9  518.51  4789.4  519.03  4811.5  516.98    4840  516.91    4861  514.75
  4942.4  511.51  4968.9  508.97  4989.7  501.38  4998.2  501.05  4998.4  500.55
  5002.2  501.05  5008.5  504.87  5013.7  505.18  5021.1  508.18  5041.6  510.77
  5046.8  510.23  5052.4  511.23  5094.2  512.38  5112.9  513.43  5118.1   514.7
  5151.2  515.66  5184.3  518.18  5321.7  525.59  5326.9  524.97  5395.9  527.47
#Mann= 3 ,-1 , 0
  4488.4     .12       0  4998.2     .05       0  5002.2     .12       0
Bank Sta=4998.2,5002.2
XS Rating Curve= 0 ,0
Exp/Cntr=0.3,0.1

Type RM Length L Ch R = 1 ,307469  ,218,218,218
BEGIN DESCRIPTION:
B20003
END DESCRIPTION:
XS GIS Cut Line= 4
      2487454.34     13862540.46      2487845.27      13862233.3
      2487919.73     13862005.27      2487859.61     13861704.67
#Sta/Elev= 30
  4395.7  524.44  4414.1  524.64  4428.6  523.19  4542.5  521.47  4556.9  520.32
    4650  517.57  4656.3  518.15  4677.1  516.64  4755.8  513.89  4784.7  511.91
  4944.6  508.07  4964.7  506.37  4971.3  503.62  4976.5   502.6  4983.8  498.42
    4984  497.92  4987.8  498.42  4996.3  500.66  5003.1  504.26  5008.4  503.68
  5017.3  508.04  5027.8  508.71  5185.7  512.99  5214.6  514.84  5255.4  515.55
  5296.2  517.65  5333.6  518.55  5338.7   519.5  5435.6  522.51  5439.3  523.48
#Mann= 3 ,-1 , 0
  4395.7     .12       0  4983.8     .05       0  4987.8     .12       0
Bank Sta=4983.8,4987.8
XS Rating Curve= 0 ,0
Exp/Cntr=0.3,0.1

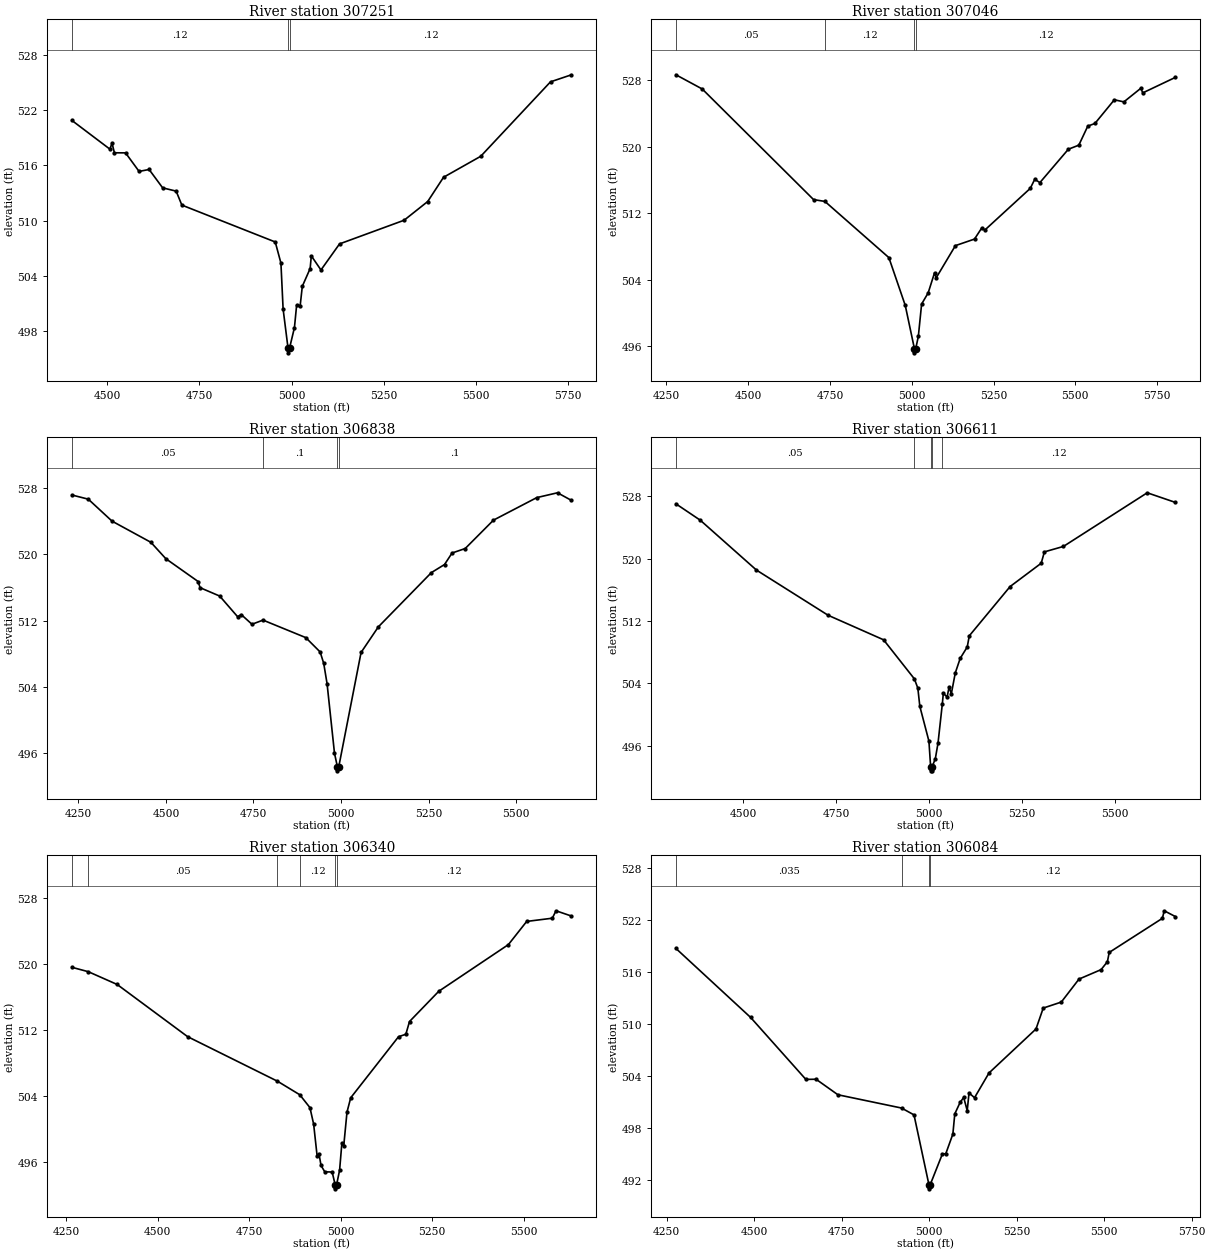
Type RM Length L Ch R = 1 ,307251  ,205,205,205
BEGIN DESCRIPTION:
B20002
END DESCRIPTION:
XS GIS Cut Line= 3
      2487556.78     13862526.46      2488110.53     13862186.76
      2488491.08     13861592.74
#Sta/Elev= 30
    4404   520.9  4506.8  517.78  4512.7  518.42  4519.2  517.38  4549.4  517.37
  4586.1  515.35  4613.3  515.56    4650  513.56  4686.7   513.2  4702.1  511.68
  4955.5  507.66  4970.9  505.36  4976.8  500.36  4990.2  496.08  4990.5  495.58
  4994.2  496.08  5007.6  498.34  5013.5  500.78  5023.1  500.71  5028.9  502.83
  5050.2  504.77  5053.3  506.15  5079.5  504.61  5129.9  507.45  5305.1  510.03
  5369.1  512.07    5412  514.71    5513     517  5702.2  525.11  5759.1  525.88
#Mann= 3 ,-1 , 0
    4404     .12       0  4990.2     .05       0  4994.2     .12       0
Bank Sta=4990.2,4994.2
XS Rating Curve= 0 ,0
Exp/Cntr=0.3,0.1

Type RM Length L Ch R = 1 ,307046  ,208,208,208
BEGIN DESCRIPTION:
B20001
END DESCRIPTION:
XS GIS Cut Line= 3
       2488194.3     13862945.35      2488231.53     13862116.96
      2488571.24     13861507.35
#Sta/Elev= 30
    4279  528.66  4359.4  526.95  4699.8  513.64  4734.5  513.42    4930  506.66
  4980.1  500.91  5008.1   495.7  5008.3   495.2  5012.1   495.7  5020.1  497.18
  5030.1  501.07  5050.1  502.41  5069.7  504.84  5074.7  504.23  5133.4   508.1
  5191.8  508.89  5213.5   510.2  5223.8  509.99  5362.3  514.99  5375.8  516.07
  5391.8  515.69  5478.7   519.7  5510.7  520.19  5538.1  522.48  5559.9   522.8
  5619.3  525.65  5648.5   525.4  5700.4  527.04  5706.2  526.48  5806.1  528.35
#Mann= 4 ,-1 , 0
    4279     .05       0  4734.5     .12       0  5008.1     .05       0
  5012.1     .12       0
Bank Sta=5008.1,5012.1
XS Rating Curve= 0 ,0
Exp/Cntr=0.3,0.1

Type RM Length L Ch R = 1 ,306838  ,227,227,227
BEGIN DESCRIPTION:
B20000
END DESCRIPTION:
XS GIS Cut Line= 3
      2488250.14     13862926.74      2488436.29     13862093.69
      2488720.08      13861595.9
#Sta/Elev= 30
  4231.6  527.13  4278.2  526.63  4346.1  523.98    4457  521.43  4499.8  519.45
    4592   516.7  4597.5  515.96  4653.5  514.95  4704.7  512.46    4715  512.72
  4745.7  511.55  4777.3  512.05  4899.4  509.94  4940.4  508.21  4950.6  506.84
  4960.2  504.39  4981.4     496  4989.6  494.38  4989.9  493.88  4993.6  494.38
  5057.3  508.15  5106.7  511.24  5258.2  517.78  5295.6  518.75  5317.2  520.14
  5354.7  520.68  5435.4   524.1  5559.2  526.82  5618.3   527.4  5658.2  526.48
#Mann= 4 ,-1 , 0
  4231.6     .05       0  4777.3      .1       0  4989.6     .04       0
  4993.6      .1       0
Bank Sta=4989.6,4993.6
XS Rating Curve= 0 ,0
Exp/Cntr=0.3,0.1

Type RM Length L Ch R = 1 ,306611  ,271,271,271
BEGIN DESCRIPTION:
B19999
END DESCRIPTION:
XS GIS Cut Line= 3
      2488352.54     13862935.97      2488659.67     13862149.53
      2488771.35     13861660.91
#Sta/Elev= 30
    4318  527.04  4383.5  524.94    4535  518.53  4727.9  512.73  4877.3  509.58
  4960.3  504.56  4969.6  503.37    4975  501.03  4999.5  496.56  5004.1  493.25
  5004.4  492.75  5007.9  492.75  5008.1  493.25  5016.8  494.33    5024  496.32
  5035.5  501.31  5038.3   502.7  5048.5  502.23  5053.8  503.52  5059.8  502.64
  5070.5  505.33  5083.7  507.19  5102.7  508.66  5108.2  510.09  5218.2  516.42
  5301.9  519.41  5310.5  520.87  5361.8  521.57  5587.5  528.46  5663.5  527.22
#Mann= 5 ,-1 , 0
    4318     .05       0  4960.3    .035       0  5004.1    .035       0
  5008.1    .035       0  5035.5     .12       0
Bank Sta=5004.1,5008.1
XS Rating Curve= 0 ,0
Exp/Cntr=0.3,0.1

Type RM Length L Ch R = 1 ,306340  ,256,256,256
BEGIN DESCRIPTION:
B19998
END DESCRIPTION:
XS GIS Cut Line= 3
      2488715.51     13863057.01      2488841.16     13862256.57
      2488836.51     13861702.73
#Sta/Elev= 30
  4266.1  519.63  4310.7   519.1  4389.6  517.55  4581.9  511.23  4827.3  505.83
  4888.2  504.19    4916  502.63  4926.1  500.63  4935.5  496.81  4940.6  497.06
  4946.3  495.62  4956.5  494.85  4976.7  494.83  4984.8  493.29  4985.1  492.79
  4988.8  493.29    4997  495.05  5003.2  498.33  5008.2  497.96  5017.2  502.09
  5027.3  503.82  5157.9  511.22  5177.9  511.52  5187.9  513.06  5267.9  516.73
  5457.9  522.38  5507.9  525.19  5577.9  525.58  5587.9  526.48  5630.2  525.84
#Mann= 6 ,-1 , 0
  4266.1    .035       0  4310.7     .05       0  4827.3    .035       0
  4888.2     .12       0  4984.8     .05       0  4988.8     .12       0
Bank Sta=4984.8,4988.8
XS Rating Curve= 0 ,0
Exp/Cntr=0.3,0.1

Type RM Length L Ch R = 1 ,306084  ,382,382,382
BEGIN DESCRIPTION:
B19997
END DESCRIPTION:
XS GIS Cut Line= 4
      2488901.66     13863070.96       2489078.5     13862433.41
      2489059.89     13862298.45      2488901.81     13861689.39
#Sta/Elev= 30
  4276.6  518.68    4490  510.73  4647.8  503.59  4676.9  503.61  4739.4  501.82
  4921.2  500.29  4956.8   499.5  4999.3  491.48  4999.6  490.98  5003.3  491.48
  5037.6  494.97  5047.7  495.04  5067.8  497.29  5073.3  499.62  5088.4  500.93
  5098.7  501.51  5108.8     500    5114  502.03  5129.7  501.48    5171  504.33
  5305.3   509.4    5326  511.81  5377.6   512.5  5428.2  515.15  5491.3  516.24
  5509.3  517.15  5514.5  518.22  5666.4  522.15  5671.6  523.02  5703.7  522.35
#Mann= 4 ,-1 , 0
  4276.6    .035       0  4921.2     .12       0  4999.3     .05       0
  5003.3     .12       0
Bank Sta=4999.3,5003.3
XS Rating Curve= 0 ,0
Exp/Cntr=0.3,0.1

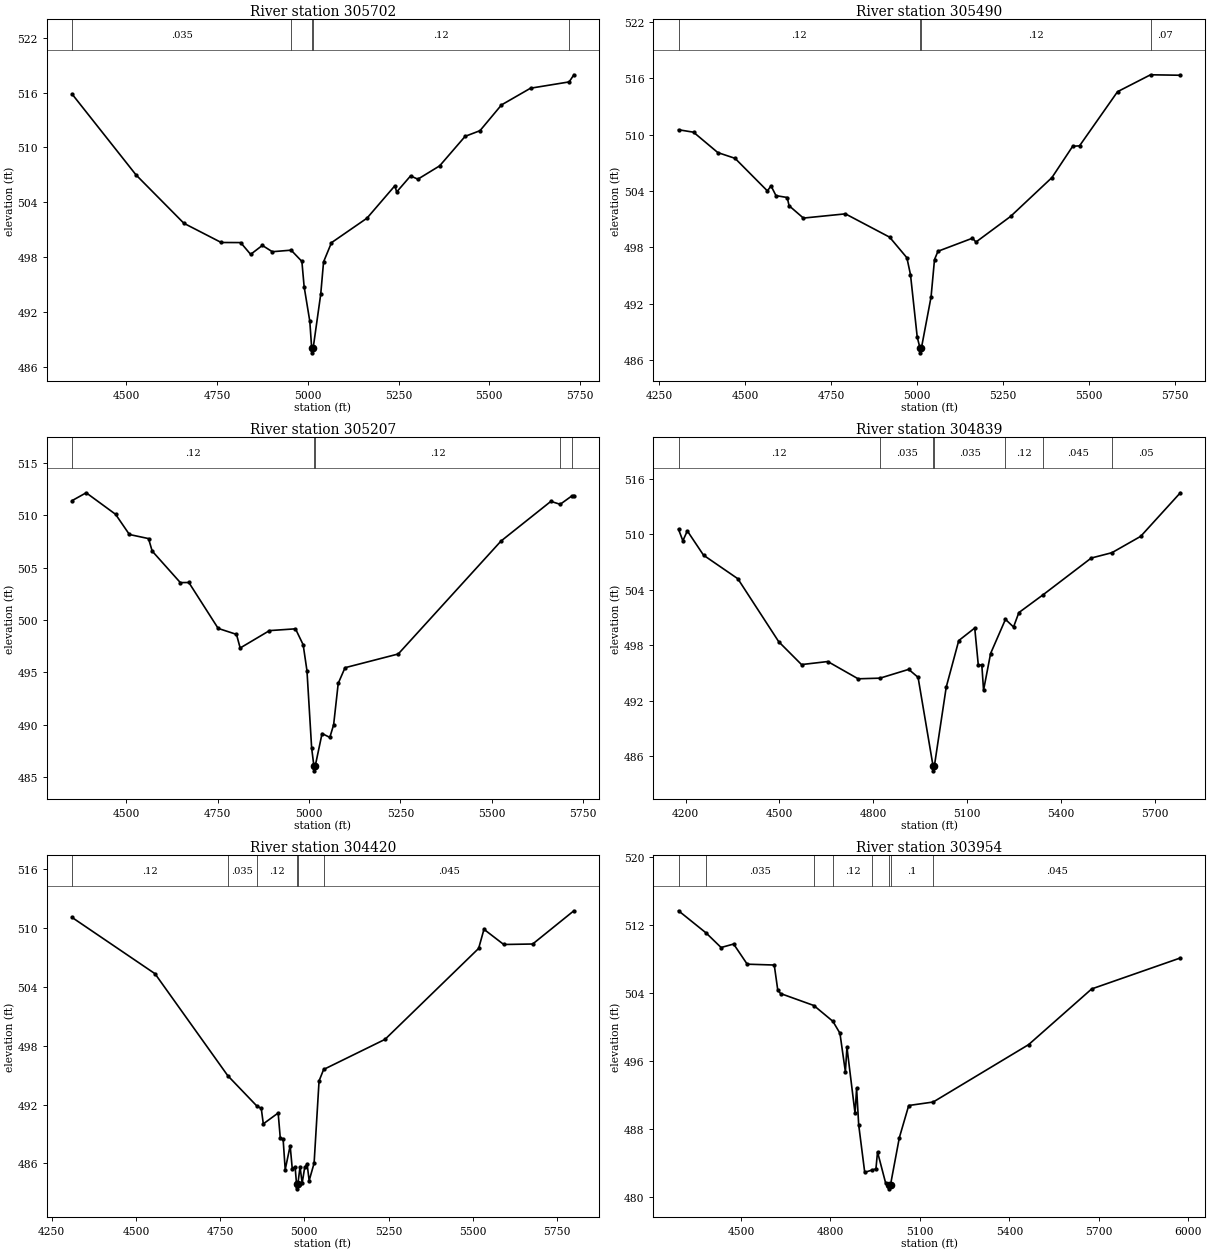
Type RM Length L Ch R = 1 ,305702  ,212,212,212
BEGIN DESCRIPTION:
B19996
END DESCRIPTION:
XS GIS Cut Line= 3
      2489055.25      13863084.9      2489413.57     13862433.41
      2489441.49     13861795.85
#Sta/Elev= 30
    4351  515.85  4527.3  506.99    4659   501.7  4761.7   499.6  4815.2  499.59
  4842.7   498.3  4874.9  499.28  4902.4  498.59  4954.2  498.76  4983.8  497.53
    4990  494.76  5005.6  490.98  5010.8  488.02  5011.1  487.52  5014.8  488.02
  5035.7  493.94  5043.5  497.48  5065.3  499.58    5163  502.26  5239.8  505.81
  5244.8  505.13  5283.1  506.89  5303.1  506.53  5363.2  507.99  5433.3  511.22
  5474.2  511.84  5533.4  514.66  5613.4  516.49  5719.8  517.18  5732.7  517.96
#Mann= 5 ,-1 , 0
    4351    .035       0  4954.2     .12       0  5010.8     .05       0
  5014.8     .12       0  5719.8     .07       0
Bank Sta=5010.8,5014.8
XS Rating Curve= 0 ,0
Exp/Cntr=0.3,0.1

Type RM Length L Ch R = 1 ,305490  ,283,283,283
BEGIN DESCRIPTION:
B19995
END DESCRIPTION:
XS GIS Cut Line= 3
      2489762.61       13863192.      2489585.76      13862614.9
      2489511.29     13861763.24
#Sta/Elev= 30
  4306.3  510.53  4349.8  510.27  4420.5   508.1  4470.5  507.49  4564.6  504.02
  4575.1  504.56  4589.5  503.52  4622.3  503.32  4627.5  502.45  4669.2  501.13
  4791.3  501.58  4919.8   499.1    4970  496.91  4980.5  495.11  5000.1  488.46
  5008.2  487.29  5008.4  486.79  5012.2  487.29  5040.3  492.74  5050.3  496.72
  5060.4   497.6  5160.7  498.99  5170.8  498.58  5271.2   501.3  5391.6  505.44
  5451.9  508.77  5471.9  508.82  5582.3  514.58  5678.2  516.38  5764.8  516.33
#Mann= 4 ,-1 , 0
  4306.3     .12       0  5008.2     .05       0  5012.2     .12       0
  5678.2     .07       0
Bank Sta=5008.2,5012.2
XS Rating Curve= 0 ,0
Exp/Cntr=0.3,0.1

Type RM Length L Ch R = 1 ,305207  ,368,368,368
BEGIN DESCRIPTION:
B19994
END DESCRIPTION:
XS GIS Cut Line= 3
      2489818.44     13863103.55      2489860.32     13862526.48
       2489641.6     13861763.29
#Sta/Elev= 30
  4351.8  511.38  4390.4  512.13  4470.7  510.08  4508.6  508.15  4560.9  507.76
  4570.9  506.57  4647.9  503.56  4671.2  503.57  4751.4  499.19  4801.5  498.62
  4811.6  497.32  4891.8  498.98  4962.9  499.15  4983.9  497.63  4994.3  495.15
  5007.1  487.77  5013.1   486.1  5013.4   485.6  5017.1   486.1  5035.6  489.16
  5056.8  488.79  5067.2  489.99  5079.8  493.95  5098.4  495.44    5244  496.75
  5524.9  507.52  5661.4  511.31  5686.9  511.03    5718  511.81  5724.3  511.87
#Mann= 5 ,-1 , 0
  4351.8     .12       0  5013.1     .05       0  5017.1     .12       0
  5686.9     .07       0    5718     .12       0
Bank Sta=5013.1,5017.1
XS Rating Curve= 0 ,0
Exp/Cntr=0.3,0.1

Type RM Length L Ch R = 1 ,304839  ,419,419,419
BEGIN DESCRIPTION:
B19993
END DESCRIPTION:
XS GIS Cut Line= 4
      2489855.66     13862991.88      2490051.13     13862340.34
      2490051.13     13862089.04       2490344.3     13861484.06
#Sta/Elev= 30
  4177.7  510.55  4191.5  509.31  4205.8  510.38  4257.6  507.75  4367.2   505.2
  4498.1  498.37  4570.8   495.9  4654.7  496.23  4751.7  494.36  4821.7  494.43
  4913.3  495.38  4943.3  494.52  4991.3  484.89  4991.5  484.39  4995.3  484.89
  5033.3  493.46  5073.3   498.5  5124.4  499.86  5135.9  495.81    5147  495.88
  5152.6  493.13  5175.1   497.1  5222.6   500.8  5248.4  499.97  5265.4  501.53
  5343.6  503.48  5496.8  507.44  5562.9  508.02  5654.8  509.79  5781.5  514.51
#Mann= 7 ,-1 , 0
  4177.7     .12       0  4821.7    .035       0  4991.3    .035       0
  4995.3    .035       0  5222.6     .12       0  5343.6    .045       0
  5562.9     .05       0
Bank Sta=4991.3,4995.3
XS Rating Curve= 0 ,0
Exp/Cntr=0.3,0.1

Type RM Length L Ch R = 1 ,304420  ,466,466,466
BEGIN DESCRIPTION:
B19992
END DESCRIPTION:
XS GIS Cut Line= 3
       2489860.3     13863024.47      2490311.73     13862400.83
       2490673.9     13861778.65
#Sta/Elev= 30
  4310.5   511.1  4556.7  505.36  4772.9  494.95  4859.7  491.84  4872.2  491.62
  4878.3  490.04  4922.4  491.15  4928.6  488.61  4937.1  488.48  4943.3  485.37
    4958  487.81  4964.2  485.47  4972.7  485.65  4976.9  483.91  4977.1  483.41
  4980.9  483.91  4987.4  485.67  4993.6  483.98  5001.2   485.6  5008.3  485.95
  5014.4  484.25  5029.1  486.03  5043.8  494.42  5057.4  495.59  5239.6  498.66
  5517.6  507.94  5533.4  509.89  5592.1  508.34  5678.1  508.39  5800.3  511.78
#Mann= 6 ,-1 , 0
  4310.5     .12       0  4772.9    .035       0  4859.7     .12       0
  4976.9     .05       0  4980.9     .12       0  5057.4    .045       0
Bank Sta=4976.9,4980.9
XS Rating Curve= 0 ,0
Exp/Cntr=0.3,0.1

Type RM Length L Ch R = 1 ,303954  ,381,381,381
BEGIN DESCRIPTION:
B19991
END DESCRIPTION:
XS GIS Cut Line= 3
      2490181.43     13863471.17       2490465.3     13862568.37
      2490711.94       13861875.
#Sta/Elev= 30
  4290.6  513.62  4383.1  511.01  4433.3   509.3  4475.3  509.71  4520.8  507.34
  4611.5  507.24  4623.2  504.32  4632.5  503.89  4744.2  502.48  4808.1  500.62
  4831.7  499.22    4850  494.68  4855.2  497.57  4882.4  489.78  4887.6  492.76
  4894.6  488.44  4914.8  482.86  4940.4  483.14  4952.4  483.27  4957.7  485.26
  4984.8  481.62  4997.4  481.42  4997.7  480.92  5001.4  481.42  5030.9  486.94
  5062.3  490.72  5144.4  491.13  5464.3  497.88  5675.7  504.43  5972.9  508.07
#Mann= 8 ,-1 , 0
  4290.6     .07       0  4383.1    .035       0  4744.2     .05       0
  4808.1     .12       0  4940.4      .1       0  4997.4     .05       0
  5001.4      .1       0  5144.4    .045       0
Bank Sta=4997.4,5001.4
XS Rating Curve= 0 ,0
Exp/Cntr=0.3,0.1

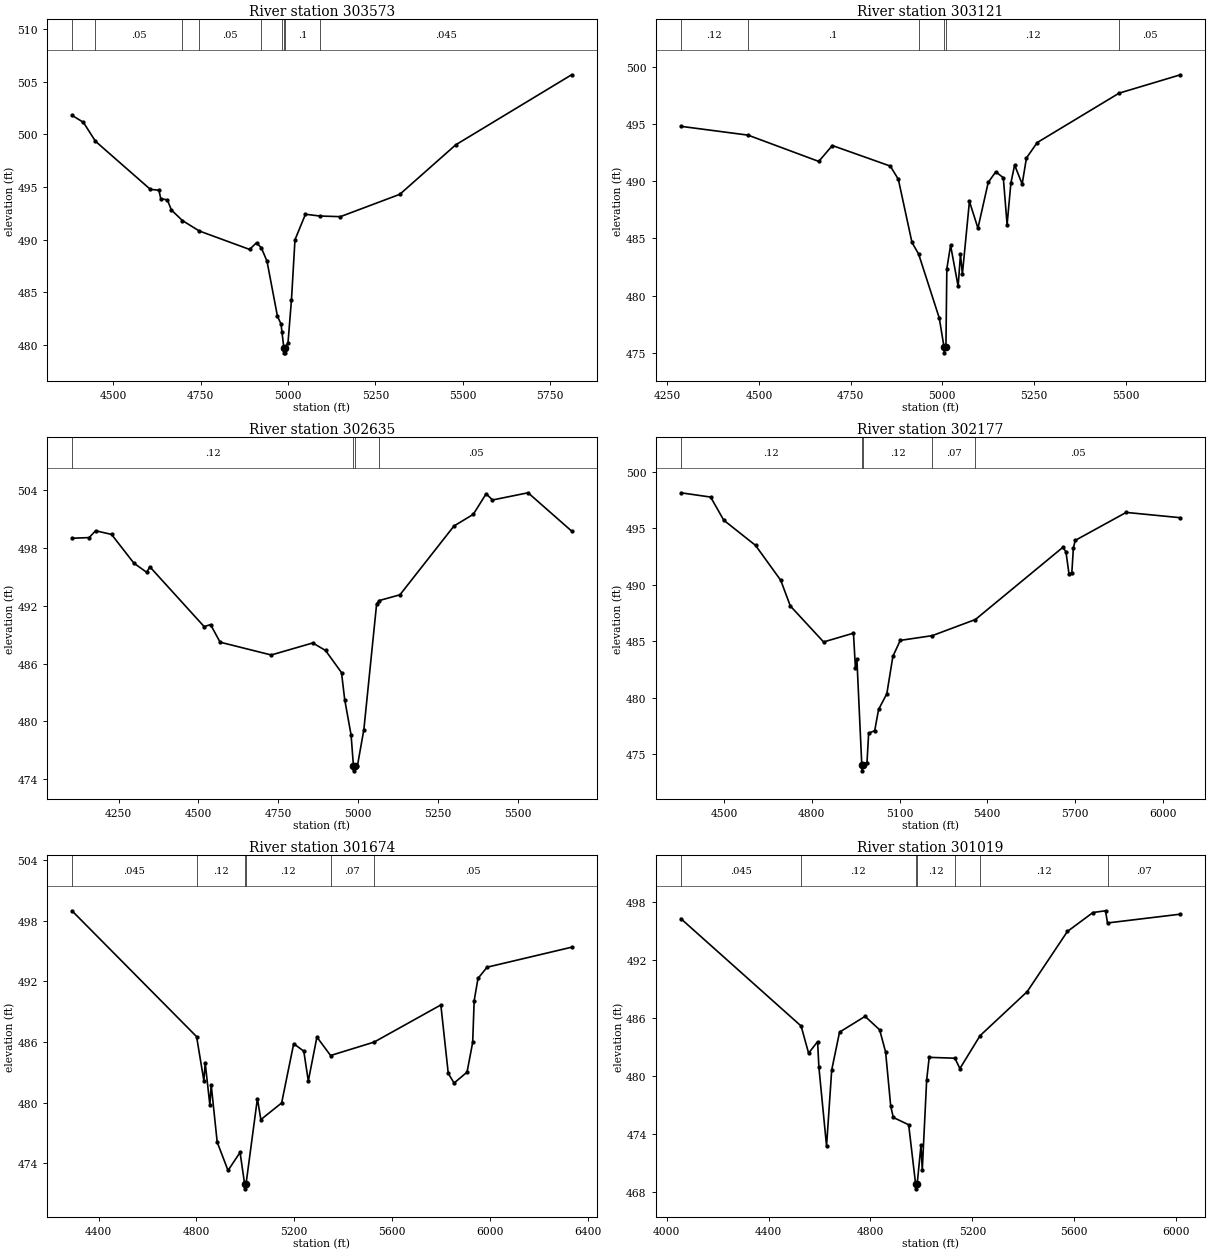
Type RM Length L Ch R = 1 ,303573  ,452,452,452
BEGIN DESCRIPTION:
B19990
END DESCRIPTION:
XS GIS Cut Line= 4
       2490567.7     13863359.46      2490744.53     13862912.74
      2490753.83     13862633.52      2490758.49     13861963.36
#Sta/Elev= 30
  4381.3  501.81  4413.9  501.15  4448.5  499.35  4605.7  494.78  4630.1   494.7
  4635.5   493.9  4654.4  493.78  4665.7  492.83  4697.4  491.82  4745.7  490.83
  4889.5  489.08  4909.5  489.71  4923.2  489.24  4939.5  487.96  4969.5  482.72
  4979.6  482.01  4982.2  481.28  4987.6  479.76  4987.8  479.26  4991.3  479.26
  4991.6  479.76  4999.6  480.21  5009.6  484.32  5019.6     490  5049.6  492.42
  5090.4  492.25  5149.6  492.19  5319.6  494.31  5479.7  499.01  5811.3  505.66
#Mann= 9 ,-1 , 0
  4381.3    .035       0  4448.5     .05       0  4697.4    .035       0
  4745.7     .05       0  4923.2     .12       0  4982.2      .1       0
  4987.6     .05       0  4991.6      .1       0  5090.4    .045       0
Bank Sta=4987.6,4991.6
XS Rating Curve= 0 ,0
Exp/Cntr=0.3,0.1

Type RM Length L Ch R = 1 ,303121  ,486,486,486
BEGIN DESCRIPTION:
B19989
END DESCRIPTION:
XS GIS Cut Line= 2
      2491005.13     13863471.18      2491316.94     13862144.84
#Sta/Elev= 30
  4286.9  494.81  4470.2  494.04  4663.1  491.74  4700.2  493.13  4858.2  491.33
  4880.1  490.18  4917.3  484.65  4935.4  483.64  4991.8  478.03  5004.7  475.49
  5005.1  474.99  5009.9  475.49  5012.4  482.35  5022.6   484.4  5043.2  480.81
  5049.6  483.62  5054.8  481.88    5074  488.24  5097.2   485.9  5125.3  489.91
  5145.9  490.83  5166.4  490.31  5176.7  486.21  5187.1  489.86  5197.2  491.42
  5217.8  489.76  5229.5  492.04  5258.9  493.39    5482  497.71  5649.4  499.32
#Mann= 6 ,-1 , 0
  4286.9     .12       0  4470.2      .1       0  4935.4     .12       0
  5004.7     .05       0  5009.9     .12       0    5482     .05       0
Bank Sta=5004.7,5009.9
XS Rating Curve= 0 ,0
Exp/Cntr=0.3,0.1

Type RM Length L Ch R = 1 ,302635  ,458,458,458
BEGIN DESCRIPTION:
B19988
END DESCRIPTION:
XS GIS Cut Line= 3
      2491526.35     13863568.91      2491526.35     13862591.64
      2491447.24     13862009.96
#Sta/Elev= 30
  4103.9  499.03  4157.8   499.1  4177.8  499.81  4227.8  499.43  4297.8  496.44
  4337.8  495.49  4347.8  496.06  4517.8  489.84  4537.8  490.05  4567.8  488.22
  4727.8  486.89  4857.8  488.14  4897.8  487.36  4947.8  485.06  4957.8  482.25
  4977.8  478.57  4985.2  475.34  4985.6  474.84  4990.5  475.34  4997.8  475.39
  5017.8  479.13  5057.8  492.21  5065.8  492.55  5130.8  493.15  5299.8   500.3
  5360.4  501.52  5400.7  503.66  5420.5  503.01  5531.9  503.76  5668.2  499.78
#Mann= 4 ,-1 , 0
  4103.9     .12       0  4985.2     .05       0  4990.5     .12       0
  5065.8     .05       0
Bank Sta=4985.2,4990.5
XS Rating Curve= 0 ,0
Exp/Cntr=0.3,0.1

Type RM Length L Ch R = 1 ,302177  ,503,503,503
BEGIN DESCRIPTION:
B19987
END DESCRIPTION:
XS GIS Cut Line= 3
      2491651.99     13863494.47      2491866.07     13862712.63
      2491568.24     13861865.69
#Sta/Elev= 30
  4352.1  498.16  4454.1  497.78    4499  495.73  4607.6   493.5  4693.7  490.41
  4726.6  488.13  4840.4  484.94  4942.5  485.72  4949.1  482.67  4954.2  483.45
    4971  474.02  4971.4  473.52  4976.3  474.02  4988.7  474.21  4994.4  476.85
  5015.1  477.08  5028.4  478.96  5056.6  480.35  5077.3  483.67  5102.6  485.08
  5211.9   485.5  5359.5  486.93  5658.2  493.32    5669  492.94  5679.6  490.94
  5689.2  491.09  5694.5  493.28  5700.8  493.94    5875  496.42  6060.5  495.95
#Mann= 5 ,-1 , 0
  4352.1     .12       0    4971     .05       0  4976.3     .12       0
  5211.9     .07       0  5359.5     .05       0
Bank Sta=4971,4976.3
XS Rating Curve= 0 ,0
Exp/Cntr=0.3,0.1

Type RM Length L Ch R = 1 ,301674  ,655,655,655
BEGIN DESCRIPTION:
B19986
END DESCRIPTION:
XS GIS Cut Line= 4
       2492466.4      13863610.8      2492238.36     13863024.43
      2492019.64     13862791.74      2491596.14     13861781.85
#Sta/Elev= 30
  4290.9     499  4800.7  486.53  4830.5  482.15  4835.9  483.92    4855  479.74
  4860.4  481.75  4884.9  476.08  4929.2  473.27  4978.5  475.06    4997  471.95
  4997.5  471.45    5003  471.95  5049.4  480.39  5063.5  478.31  5148.5  479.96
  5197.8  485.83  5239.1  485.09  5257.6  482.14  5292.8  486.49  5348.7  484.66
  5526.8  485.99  5799.7  489.67    5830  482.89  5853.8  481.93  5906.8  483.01
  5929.9  485.96    5936  490.09  5951.6   492.3  5988.9  493.41  6334.5  495.39
#Mann= 6 ,-1 , 0
  4290.9    .045       0  4800.7     .12       0    4997     .05       0
    5003     .12       0  5348.7     .07       0  5526.8     .05       0
Bank Sta=4997,5003
XS Rating Curve= 0 ,0
Exp/Cntr=0.3,0.1

Type RM Length L Ch R = 1 ,301019  ,617,617,617
BEGIN DESCRIPTION:
B19985
END DESCRIPTION:
XS GIS Cut Line= 3
       2492475.7     13863513.03      2492354.71     13862531.14
      2492447.78     13861563.22
#Sta/Elev= 30
  4055.3  496.29  4527.7  485.17  4557.1  482.36  4592.4  483.56  4597.5  480.91
  4627.6  472.75  4647.8  480.62  4678.6  484.54  4778.8  486.17    4836  484.78
  4859.4  482.49  4879.5  476.89  4889.6  475.71    4950  474.95  4977.2  468.82
  4977.7  468.32  4983.4  468.82  4998.4  472.84  5003.4  470.27  5020.6  479.57
  5030.6  481.93  5131.6  481.84  5151.2  480.77  5230.2  484.17  5415.4  488.73
  5573.2  494.96  5673.6  496.92  5722.8   497.1  5730.7  495.84    6017  496.75
#Mann= 7 ,-1 , 0
  4055.3    .045       0  4527.7     .12       0  4977.2     .05       0
  4983.4     .12       0  5131.6      .1       0  5230.2     .12       0
  5730.7     .07       0
Bank Sta=4977.2,4983.4
XS Rating Curve= 0 ,0
Exp/Cntr=0.3,0.1

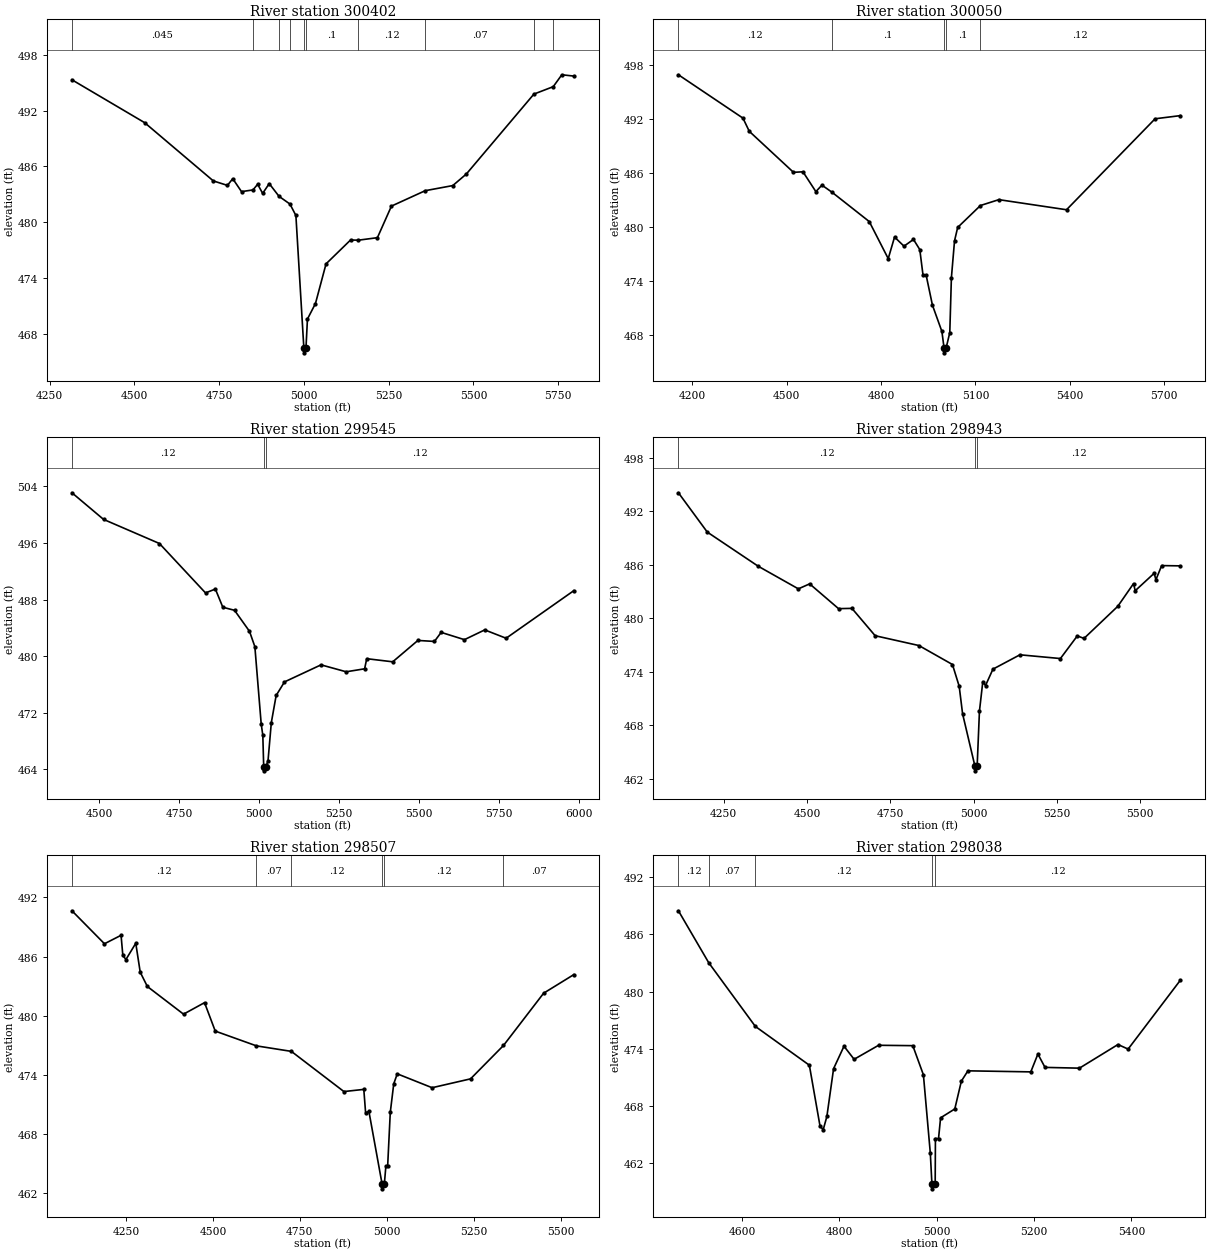
Type RM Length L Ch R = 1 ,300402  ,352,352,352
BEGIN DESCRIPTION:
B19984
END DESCRIPTION:
XS GIS Cut Line= 3
      2492522.23     13863466.56      2492740.96     13862684.71
      2492806.07     13862019.66
#Sta/Elev= 30
  4315.9  495.33  4530.4  490.71  4732.9  484.44  4774.4  483.96  4790.1  484.68
  4815.9  483.29  4849.7  483.47  4863.5  484.08  4878.3   483.1  4897.7  484.15
  4926.6  482.78  4958.8  481.95  4976.3  480.72  4999.8  466.43  5000.3  465.93
    5006  466.43  5010.4  469.57    5034  471.24  5065.2  475.51  5137.5  478.08
  5160.6  478.06  5216.7  478.33  5258.1  481.73  5357.7  483.39    5439  483.94
  5479.1  485.19  5678.2  493.79  5735.2  494.59  5760.5  495.87    5796  495.73
#Mann= 10 ,-1 , 0
  4315.9    .045       0  4849.7     .12       0  4926.6     .07       0
  4958.8      .1       0  4999.8     .05       0    5006      .1       0
  5160.6     .12       0  5357.7     .07       0  5678.2     .12       0
  5735.2     .07       0
Bank Sta=4999.8,5006
XS Rating Curve= 0 ,0
Exp/Cntr=0.3,0.1

Type RM Length L Ch R = 1 ,300050  ,505,505,505
BEGIN DESCRIPTION:
B19983
END DESCRIPTION:
XS GIS Cut Line= 3
      2492959.69     13863629.38      2493052.76     13862633.52
      2492922.47     13862051.84
#Sta/Elev= 30
  4155.3   496.9  4360.6  492.09  4380.7  490.63  4521.3  486.08  4551.4  486.14
  4592.5  483.94  4611.7  484.66  4643.9  483.87  4762.3  480.62  4822.6  476.51
  4842.7   478.9  4872.8  477.89  4902.9  478.64    4923  477.51  4933.1  474.72
  4943.1  474.69  4963.2  471.35  4993.3  468.43  5000.3  466.56  5000.8  466.06
  5006.5  466.56  5018.4  468.31  5023.5  474.39  5033.5  478.49  5043.5  479.97
  5115.9   482.4  5174.5  483.05  5389.7  481.93  5671.4  492.02  5751.6  492.37
#Mann= 5 ,-1 , 0
  4155.3     .12       0  4643.9      .1       0  5000.3     .05       0
  5006.5      .1       0  5115.9     .12       0
Bank Sta=5000.3,5006.5
XS Rating Curve= 0 ,0
Exp/Cntr=0.3,0.1

Type RM Length L Ch R = 1 ,299545  ,602,602,602
BEGIN DESCRIPTION:
B19982
END DESCRIPTION:
XS GIS Cut Line= 3
       2493611.2     13863540.96      2493429.71      13862796.4
       2492997.9     13862118.51
#Sta/Elev= 30
  4414.2  503.09    4513  499.33  4687.9  495.92    4832  488.94  4862.9  489.48
  4886.2  486.91  4922.8  486.48  4969.6  483.51  4986.4  481.34  5006.2  470.43
  5011.3  468.81  5014.1  464.29  5014.6  463.79  5020.5  464.29  5027.6  465.23
  5037.9  470.61    5053  474.44  5079.1  476.36  5193.4  478.77  5272.1  477.79
  5329.7  478.21  5336.4  479.64  5417.7   479.2  5496.4  482.22  5548.1  482.08
  5569.2  483.36    5642  482.33  5705.5  483.71  5772.4  482.53  5984.3  489.26
#Mann= 3 ,-1 , 0
  4414.2     .12       0  5014.1     .05       0  5020.5     .12       0
Bank Sta=5014.1,5020.5
XS Rating Curve= 0 ,0
Exp/Cntr=0.3,0.1

Type RM Length L Ch R = 1 ,298943  ,436,436,436
BEGIN DESCRIPTION:
B19981
END DESCRIPTION:
XS GIS Cut Line= 3
      2493978.85     13863443.27      2493899.73     13862647.48
      2493788.08     13861949.66
#Sta/Elev= 30
  4114.3  494.09  4200.9  489.68  4353.7  485.85  4474.3  483.31  4508.2  483.87
  4594.9  481.09  4635.1  481.12  4704.8  478.05  4836.1  476.95  4936.8  474.82
    4957  472.38  4967.2  469.29  5004.4  463.39  5004.9  462.89  5010.9  463.39
  5017.8  469.59  5027.9   472.9    5036  472.46  5058.3   474.3  5139.3  475.91
  5260.8  475.49  5311.5  478.03  5331.7  477.75    5433  481.35  5480.3   483.9
  5485.3   483.1  5542.3  485.06  5547.4  484.33  5564.7  485.92  5620.7  485.89
#Mann= 3 ,-1 , 0
  4114.3     .12       0  5004.4     .05       0  5010.9     .12       0
Bank Sta=5004.4,5010.9
XS Rating Curve= 0 ,0
Exp/Cntr=0.3,0.1

Type RM Length L Ch R = 1 ,298507  ,469,469,469
BEGIN DESCRIPTION:
PEACH CREEK9209
END DESCRIPTION:
XS GIS Cut Line= 3
      2494067.26     13863406.05        2494275.       13862525.
      2494309.16     13861988.29
#Sta/Elev= 30
  4094.8  490.65  4188.3   487.3    4236  488.16  4241.1  486.12    4250   485.7
  4278.3  487.35  4291.1  484.41  4311.6  482.96  4415.6  480.15    4476  481.32
  4506.8  478.43  4625.3  476.93  4725.7  476.37  4876.7  472.29  4933.9  472.51
  4939.1  470.12  4948.6  470.27  4986.4  462.91  4986.9  462.41    4993  462.91
  4997.4  464.74  5002.5  464.74    5010  470.17    5020  473.08  5030.1  474.09
  5130.3  472.68  5240.8  473.58  5335.5  476.97  5450.9  482.28  5537.8  484.17
#Mann= 6 ,-1 , 0
  4094.8     .12       0  4625.3     .07       0  4725.7     .12       0
  4986.4     .05       0    4993     .12       0  5335.5     .07       0
Bank Sta=4986.4,4993
XS Rating Curve= 0 ,0
Exp/Cntr=0.3,0.1

Type RM Length L Ch R = 1 ,298038  ,453,453,453
BEGIN DESCRIPTION:
PEACH CREEK9208
END DESCRIPTION:
XS GIS Cut Line= 3
        2495075.       13862875.        2494675.       13862525.
        2494375.     13862125.01
#Sta/Elev= 30
    4469  488.48  4531.3  483.03  4627.1  476.35  4738.1  472.28  4759.9  465.93
  4766.5   465.5  4774.1   466.9  4787.9  471.92  4809.3  474.27  4830.1   472.9
  4880.4  474.37  4950.7  474.33  4972.5  471.27  4986.7  463.05    4990  459.81
  4990.5  459.31  4996.7  459.81  4997.2  464.59  5003.6  464.59  5007.8  466.76
    5037  467.69  5050.5  470.61    5064  471.69  5193.2  471.58  5207.8  473.45
  5222.4  472.05  5293.2  471.97  5372.4  474.45  5393.2  473.97  5500.5  481.19
#Mann= 5 ,-1 , 0
    4469     .12       0  4531.3     .07       0  4627.1     .12       0
    4990     .05       0  4996.7     .12       0
Bank Sta=4990,4996.7
XS Rating Curve= 0 ,0
Exp/Cntr=0.3,0.1