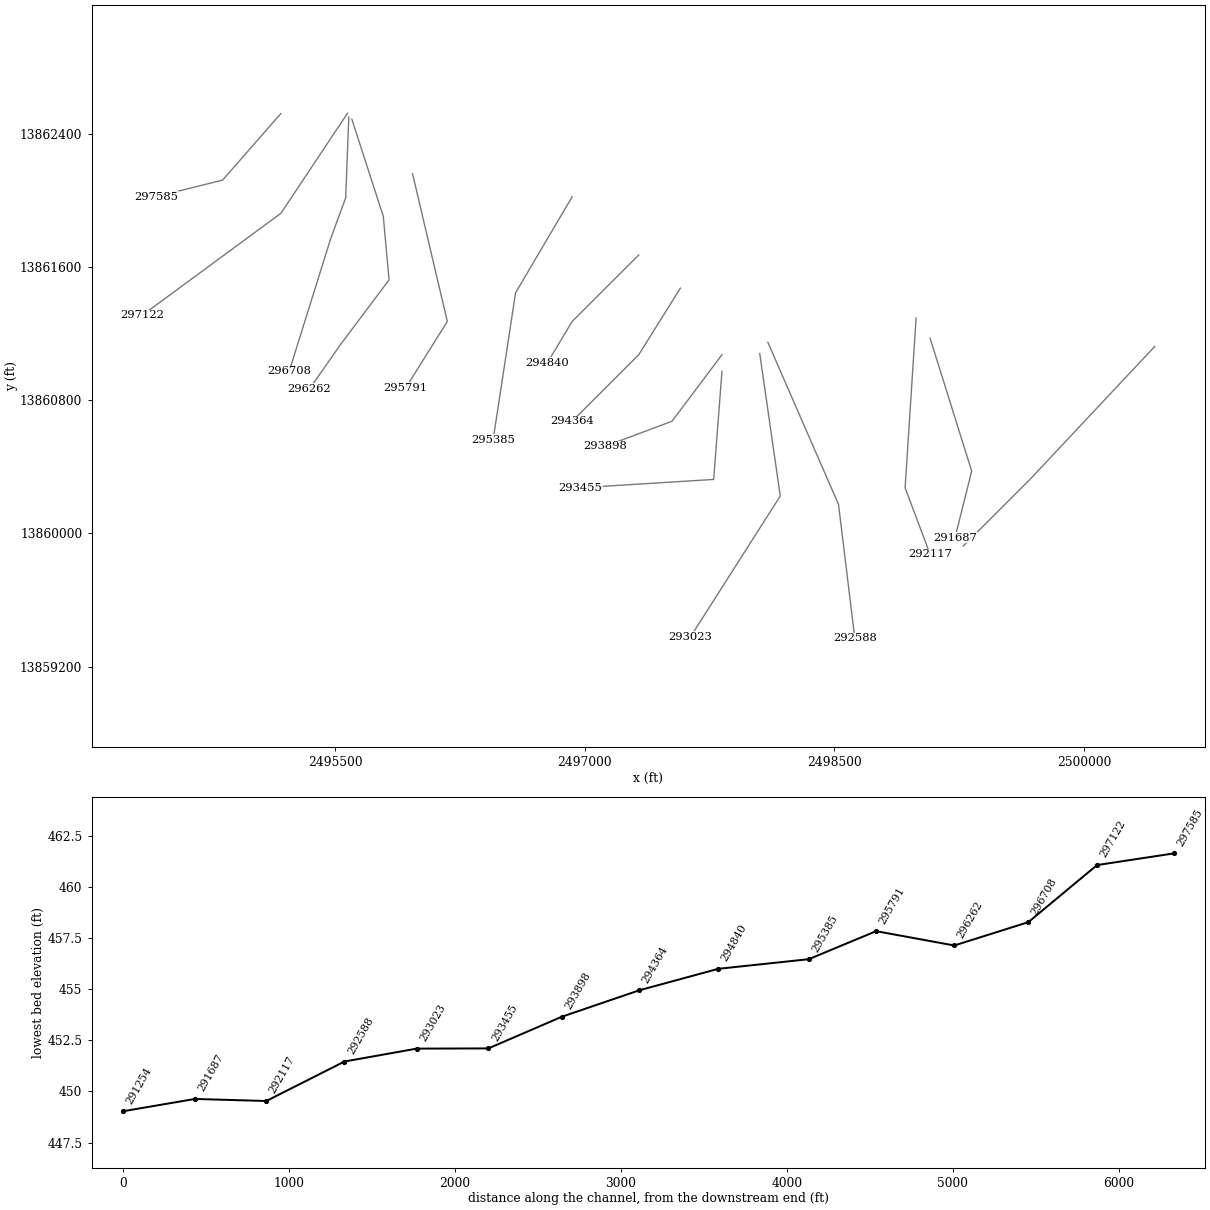
HEC-RAS study PEACH CREEK.prj: PEACH CREEK Base Level Engineering

--- PEACH CREEK.g01 (geometry) --- (continued)

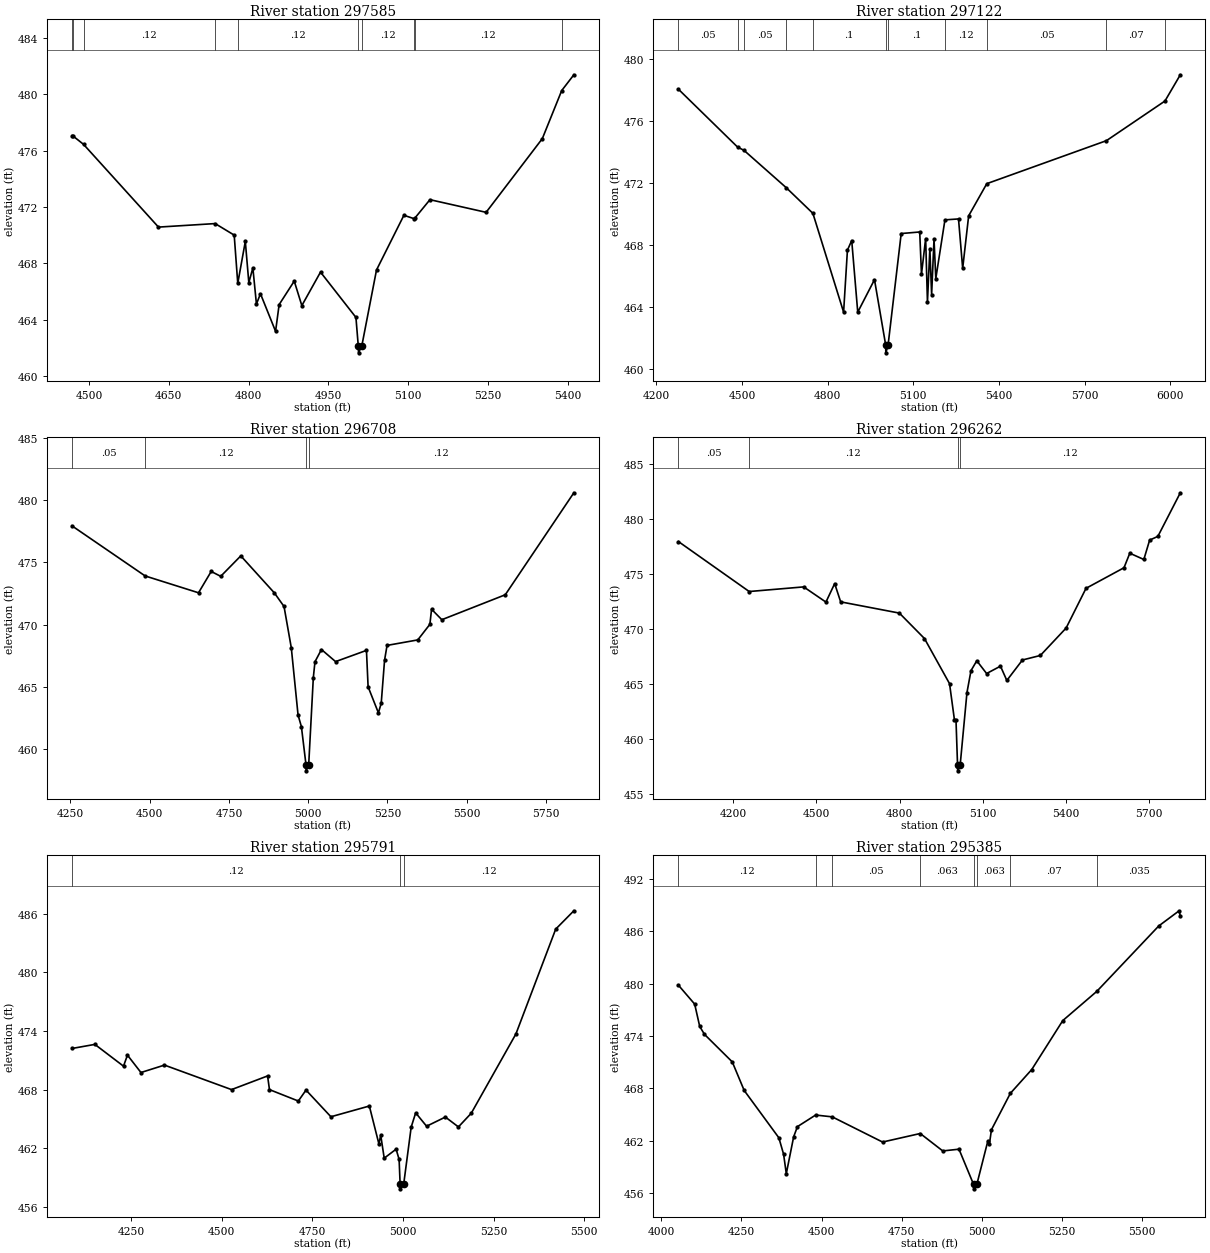
Type RM Length L Ch R = 1 ,297585  ,463,463,463
BEGIN DESCRIPTION:
PEACH CREEK9207
END DESCRIPTION:
XS GIS Cut Line= 3
      2495174.97     13862524.97        2494825.       13862125.
      2494424.97     13862024.99
#Sta/Elev= 30
  4467.9  477.07  4469.1  477.07  4489.8  476.45  4630.6  470.57  4737.2  470.82
    4773     470  4779.7  466.57  4793.9  469.55  4800.5  466.62  4808.1  467.67
  4814.8   465.1  4822.4  465.83  4850.8  463.16  4857.5  465.06  4885.9  466.73
  4900.2  464.99  4935.3  467.37  5001.9  464.15  5006.3  462.13  5006.8  461.63
    5013  462.13  5040.6  467.52  5092.1  471.41  5110.4  471.18  5112.5   471.2
  5141.1  472.52  5246.7  471.62  5352.4  476.86  5388.9  480.28  5411.7   481.4
#Mann= 10 ,-1 , 0
  4467.9     .12       0  4469.1     .05       0  4489.8     .12       0
  4737.2      .1       0  4779.7     .12       0  5006.3     .05       0
    5013     .12       0  5110.4      .1       0  5112.5     .12       0
  5388.9     .07       0
Bank Sta=5006.3,5013
XS Rating Curve= 0 ,0
Exp/Cntr=0.3,0.1

Type RM Length L Ch R = 1 ,297122  ,414,414,414
BEGIN DESCRIPTION:
PEACH CREEK9206
END DESCRIPTION:
XS GIS Cut Line= 3
      2495575.05     13862526.46        2495175.       13861925.
      2494341.84     13861311.87
#Sta/Elev= 30
  4277.6  478.03  4484.5  474.31  4507.5  474.09  4655.1  471.69  4748.3  470.04
  4855.8  463.68  4869.2  467.67  4884.2  468.29  4905.3  463.68  4963.9  465.77
  5003.1  461.56  5003.6  461.06  5011.5  461.56  5057.4  468.74  5122.2  468.84
  5128.4  466.12    5143  468.42  5149.3  464.32  5157.7  467.77  5163.9  464.81
  5172.3  468.38  5178.5  465.84  5210.5  469.62    5258  469.68  5272.6   466.5
  5293.5  469.88    5357  471.95  5775.9  474.72  5980.6  477.27  6034.4  478.96
#Mann= 11 ,-1 , 0
  4277.6     .05       0  4484.5     .07       0  4507.5     .05       0
  4655.1     .12       0  4748.3      .1       0  5003.1     .05       0
  5011.5      .1       0  5210.5     .12       0    5357     .05       0
  5775.9     .07       0  5980.6     .12       0
Bank Sta=5003.1,5011.5
XS Rating Curve= 0 ,0
Exp/Cntr=0.3,0.1

Type RM Length L Ch R = 1 ,296708  ,446,446,446
BEGIN DESCRIPTION:
PEACH CREEK9205
END DESCRIPTION:
XS GIS Cut Line= 4
      2495583.21     13862503.97       2495564.3     13862017.89
        2495475.       13861775.        2495225.     13860974.99
#Sta/Elev= 30
  4254.7  477.92  4485.6   473.9    4654  472.55    4694  474.26    4724  473.87
  4787.4  475.51  4893.3  472.54  4923.8  471.45  4946.7  468.14    4968  462.75
  4978.6  461.81    4993  458.77  4993.5  458.27  5001.6  458.77  5016.2  465.75
  5021.4  467.02  5041.8     468  5086.4  467.03  5183.8  467.93    5189  465.01
  5221.5  462.92  5230.4  463.69  5240.9  467.14  5248.8  468.33  5345.7  468.77
  5383.9  470.02  5389.2  471.23  5421.6  470.39  5621.7  472.39  5838.1  480.57
#Mann= 4 ,-1 , 0
  4254.7     .05       0  4485.6     .12       0    4993     .05       0
  5001.6     .12       0
Bank Sta=4993,5001.6
XS Rating Curve= 0 ,0
Exp/Cntr=0.3,0.1

Type RM Length L Ch R = 1 ,296262  ,471,471,471
BEGIN DESCRIPTION:
PEACH CREEK9204
END DESCRIPTION:
XS GIS Cut Line= 5
      2495601.44      13862490.9      2495790.25     13861907.23
        2495825.       13861525.      2495536.28     13861140.04
      2495346.73     13860869.24
#Sta/Elev= 30
  4002.8  477.96  4257.9  473.42  4454.3  473.84  4534.5  472.46    4566  474.14
  4587.6  472.48  4799.2  471.46  4889.6  469.15    4980  465.05  4997.5  461.79
  5003.2  461.79  5008.9  457.63  5009.4  457.13  5018.2  457.63  5042.8  464.24
  5057.3  466.23  5078.2  467.13  5113.6  465.97  5163.6  466.64  5186.5  465.34
  5242.8   467.2  5307.3  467.61  5400.1   470.1  5471.9  473.71  5608.8  475.58
  5629.7   476.9  5680.3  476.33  5701.2  478.09  5730.9  478.43  5811.8  482.39
#Mann= 4 ,-1 , 0
  4002.8     .05       0  4257.9     .12       0  5008.9     .05       0
  5018.2     .12       0
Bank Sta=5008.9,5018.2
XS Rating Curve= 0 ,0
Exp/Cntr=0.3,0.1

Type RM Length L Ch R = 1 ,295791  ,406,406,406
BEGIN DESCRIPTION:
PEACH CREEK9203
END DESCRIPTION:
XS GIS Cut Line= 3
      2495965.99     13862163.46        2496175.       13861275.
      2495925.01     13860875.01
#Sta/Elev= 30
  4087.2   472.2  4150.4  472.62  4229.4  470.39  4240.3  471.52  4277.5  469.74
  4342.4   470.5  4527.4  467.99  4626.8  469.39    4632  467.99  4711.6  466.82
  4732.8  467.94  4801.5  465.21  4907.5  466.31  4933.8  462.44  4938.9  463.32
  4948.5  460.97  4981.3  461.89  4989.6  460.85  4992.4  458.33  4992.9  457.83
  5002.3  458.33  5022.9  464.15  5035.3  465.61  5065.4  464.24  5117.2  465.18
  5153.2  464.17  5188.6  465.57  5311.8  473.69  5421.5  484.42  5471.6   486.3
#Mann= 3 ,-1 , 0
  4087.2     .12       0  4992.4     .05       0  5002.3     .12       0
Bank Sta=4992.4,5002.3
XS Rating Curve= 0 ,0
Exp/Cntr=0.3,0.1

Type RM Length L Ch R = 1 ,295385  ,545,545,545
BEGIN DESCRIPTION:
PEACH CREEK9202
END DESCRIPTION:
XS GIS Cut Line= 3
      2496924.99     13862024.99      2496584.92     13861446.83
      2496449.98     13860562.73
#Sta/Elev= 30
  4053.4  479.83  4104.1  477.66  4119.8   475.1  4134.6  474.19  4221.3  471.03
  4258.5  467.75  4366.6  462.32  4381.4  460.43  4389.8   458.2  4412.8  462.44
  4424.6   463.6  4481.3  464.93  4533.1  464.72    4690  461.83  4807.5  462.81
  4877.7  460.81  4928.3  461.01  4973.9  456.96  4974.4  456.46  4983.9  456.96
  5018.1  461.92  5023.1  461.57  5029.5  463.24  5088.5  467.42  5155.2  470.15
    5252  475.77  5358.3  479.13  5551.3  486.63  5614.8  488.37  5618.5  487.74
#Mann= 8 ,-1 , 0
  4053.4     .12       0  4481.3     .07       0  4533.1     .05       0
  4807.5    .063       0  4973.9    .063       0  4983.9    .063       0
  5088.5     .07       0  5358.3    .035       0
Bank Sta=4973.9,4983.9
XS Rating Curve= 0 ,0
Exp/Cntr=0.3,0.1

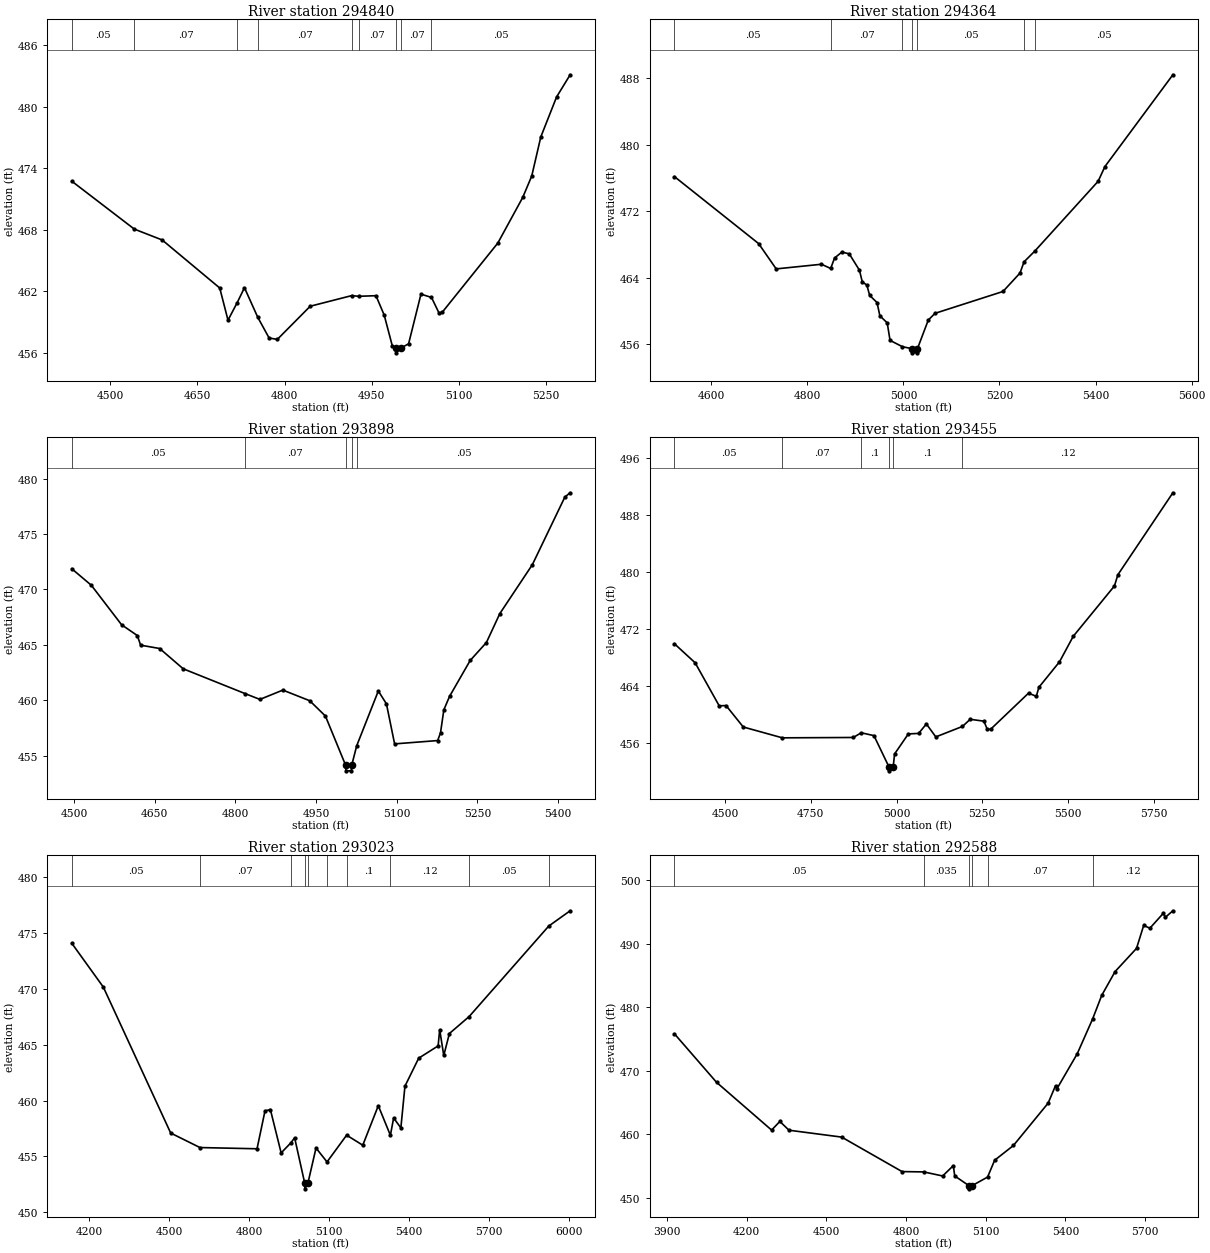
Type RM Length L Ch R = 1 ,294840  ,476,476,476
BEGIN DESCRIPTION:
PEACH CREEK9201
END DESCRIPTION:
XS GIS Cut Line= 3
      2497324.98     13861674.98        2496925.       13861275.
      2496775.01     13861025.01
#Sta/Elev= 30
  4434.1  472.75  4541.7  468.07  4589.6  467.01  4688.6  462.32  4702.8  459.18
  4718.7   460.9  4731.1  462.35    4754  459.46  4773.5  457.44  4787.6   457.3
  4844.2  460.54  4915.7  461.58  4927.5  461.51  4957.3  461.57  4971.5  459.67
  4985.6  456.63  4991.2  456.49  4991.7  455.99  5001.2  456.49  5013.4  456.87
  5034.7  461.72  5052.8   461.4  5065.8  459.87  5071.7  459.98  5166.9  466.71
  5209.7  471.16  5225.2  473.25  5240.8  477.07    5268  480.98  5291.3  483.14
#Mann= 9 ,-1 , 0
  4434.1     .05       0  4541.7     .07       0  4718.7     .12       0
    4754     .07       0  4915.7     .05       0  4927.5     .07       0
  4991.2     .05       0  5001.2     .07       0  5052.8     .05       0
Bank Sta=4991.2,5001.2
XS Rating Curve= 0 ,0
Exp/Cntr=0.3,0.1

Type RM Length L Ch R = 1 ,294364  ,466,466,466
BEGIN DESCRIPTION:
PEACH CREEK9200
END DESCRIPTION:
XS GIS Cut Line= 3
      2497575.01     13861475.02        2497325.       13861075.
        2496925.       13860675.
#Sta/Elev= 30
  4523.5  476.16  4698.6   468.1  4735.2  465.05  4829.5  465.61  4848.6   465.1
  4856.7  466.36    4872  467.08  4887.3  466.86  4908.5  464.89  4914.4  463.49
  4923.9   463.1  4929.8  461.85  4945.1     461    4951   459.4  4966.3  458.55
  4972.2  456.44  4997.9  455.68  5017.9  455.44  5018.4  454.94  5028.7  454.94
  5029.2  455.44  5051.8  458.89  5065.9   459.7  5207.3  462.33  5242.7  464.55
  5251.1   465.9  5273.6   467.2  5405.3   475.6  5419.5  477.38  5560.9  488.43
#Mann= 7 ,-1 , 0
  4523.5     .05       0  4848.6     .07       0  4997.9     .05       0
  5017.9     .05       0  5029.2     .05       0  5251.1     .07       0
  5273.6     .05       0
Bank Sta=5017.9,5029.2
XS Rating Curve= 0 ,0
Exp/Cntr=0.3,0.1

Type RM Length L Ch R = 1 ,293898  ,443,443,443
BEGIN DESCRIPTION:
PEACH CREEK9199
END DESCRIPTION:
XS GIS Cut Line= 3
      2497824.99     13861074.99        2497525.       13860675.
      2497124.98     13860524.99
#Sta/Elev= 30
  4495.5  471.87  4531.9  470.38  4588.2  466.82  4617.4  465.85  4623.6  464.98
    4659  464.68  4702.8  462.85  4817.6  460.62  4845.5  460.09  4888.2  460.93
  4938.2  459.97  4967.4  458.59    5005  454.15  5005.5  453.65  5015.8  453.65
  5016.3  454.15  5025.6  455.91  5065.8  460.85  5080.9  459.69  5096.1  456.08
  5176.2  456.38  5181.5  457.08  5187.7  459.15  5198.4  460.37  5236.7   463.6
  5266.9  465.22  5291.9  467.83  5352.4  472.24  5412.9  478.34  5422.7  478.72
#Mann= 5 ,-1 , 0
  4495.5     .05       0  4817.6     .07       0    5005     .05       0
  5016.3     .07       0  5025.6     .05       0
Bank Sta=5005,5016.3
XS Rating Curve= 0 ,0
Exp/Cntr=0.3,0.1

Type RM Length L Ch R = 1 ,293455  ,432,432,432
BEGIN DESCRIPTION:
PEACH CREEK9198
END DESCRIPTION:
XS GIS Cut Line= 3
        2497825.     13860974.98        2497775.       13860325.
      2496974.96       13860275.
#Sta/Elev= 30
  4352.3  469.92  4412.5  467.26  4482.7  461.22  4502.7  461.26  4552.9  458.25
  4666.9  456.73  4873.8  456.78    4897  457.44    4934  457.04  4978.3   452.6
  4978.8   452.1    4990   452.6  4994.2  454.47  5034.3  457.28  5064.3  457.35
  5086.9  458.68  5114.4  456.86  5192.2  458.33  5214.6  459.33  5254.7  459.07
  5264.7   457.9  5274.7  457.95  5384.9     463  5407.5  462.55    5415  463.82
  5475.1  467.39  5515.2  470.97  5635.4  478.04  5645.4  479.61  5805.8  491.11
#Mann= 6 ,-1 , 0
  4352.3     .05       0  4666.9     .07       0    4897      .1       0
  4978.3     .05       0    4990      .1       0  5192.2     .12       0
Bank Sta=4978.3,4990
XS Rating Curve= 0 ,0
Exp/Cntr=0.3,0.1

Type RM Length L Ch R = 1 ,293023  ,435,435,435
BEGIN DESCRIPTION:
PEACH CREEK9197
END DESCRIPTION:
XS GIS Cut Line= 3
      2498051.83     13861082.21        2498175.       13860225.
      2497636.09     13859378.98
#Sta/Elev= 30
  4134.3   474.1  4252.7  470.17  4505.3  457.09  4615.1  455.79  4829.1  455.68
  4858.9  459.07  4879.1   459.2  4919.5  455.31  4955.1  456.19  4970.1  456.66
    5008  452.59  5008.5  452.09  5019.8  452.59  5050.3  455.75  5091.6   454.5
  5165.1   456.9  5225.6     456  5283.9  459.54  5329.2  456.89  5341.4  458.44
  5368.5  457.55  5383.8  461.29  5435.4   463.8  5508.2   464.9  5514.1  466.35
  5529.4  464.04  5550.5  466.01  5624.6  467.53  5923.1  475.64  6003.4  477.01
#Mann= 10 ,-1 , 0
  4134.3     .05       0  4615.1     .07       0  4955.1      .1       0
    5008     .05       0  5019.8      .1       0  5091.6     .12       0
  5165.1      .1       0  5329.2     .12       0  5624.6     .05       0
  5923.1     .07       0
Bank Sta=5008,5019.8
XS Rating Curve= 0 ,0
Exp/Cntr=0.3,0.1

Type RM Length L Ch R = 1 ,292588  ,471,471,471
BEGIN DESCRIPTION:
PEACH CREEK9196
END DESCRIPTION:
XS GIS Cut Line= 3
      2498100.24     13861150.03        2498525.       13860175.
      2498623.03     13859369.18
#Sta/Elev= 30
  3928.9  475.81  4087.1   468.2  4294.3  460.69  4325.3  462.05  4359.8  460.67
  4557.9  459.59  4785.2  454.17  4866.8  454.12  4937.9  453.48    4978   455.1
  4983.4  453.48  5036.9  451.96  5037.4  451.46  5048.7  451.96    5107  453.31
  5133.5  455.95  5204.2  458.27  5334.9  464.93  5362.6  467.67  5367.6  467.16
  5444.3  472.68  5502.1  478.14  5536.4  481.85  5586.8   485.6  5667.4  489.24
  5694.4  492.85  5717.7  492.41  5768.1  494.75  5776.1  494.13  5804.2  495.15
#Mann= 6 ,-1 , 0
  3928.9     .05       0  4866.8    .035       0  5036.9    .035       0
  5048.7    .035       0    5107     .07       0  5502.1     .12       0
Bank Sta=5036.9,5048.7
XS Rating Curve= 0 ,0
Exp/Cntr=0.3,0.1

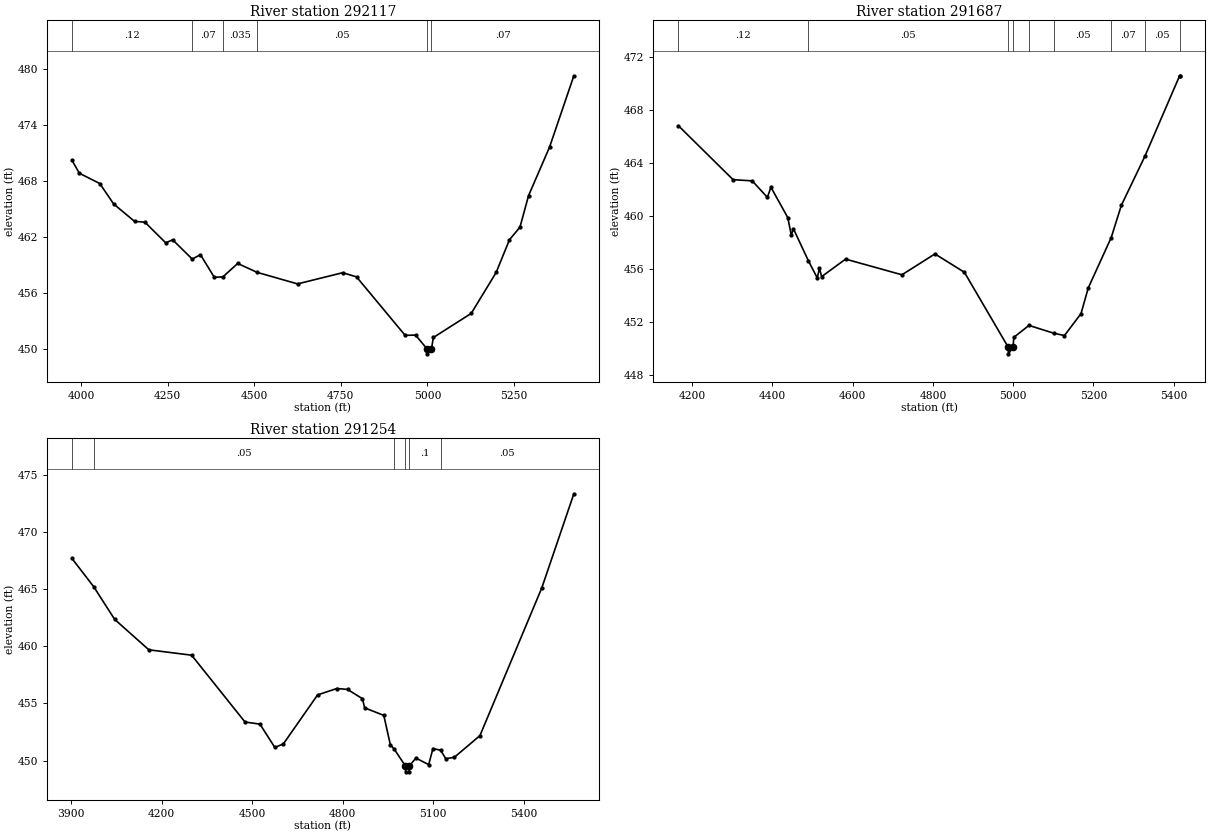
Type RM Length L Ch R = 1 ,292117  ,430,430,430
BEGIN DESCRIPTION:
PEACH CREEK9195
END DESCRIPTION:
XS GIS Cut Line= 3
      2498991.12     13861295.28        2498925.       13860275.
      2499074.99     13859875.02
#Sta/Elev= 30
  3973.3  470.27  3994.6  468.87  4053.7  467.77  4093.8  465.58    4154  463.72
    4184  463.63  4244.1  461.42  4264.2  461.74  4320.7  459.68  4344.4  460.15
  4384.4  457.73  4409.2  457.77    4452  459.21  4507.9  458.26  4624.9  457.02
  4755.2  458.22  4795.3  457.77  4935.6  451.51  4965.7  451.54  4999.5  450.03
    5000  449.53  5011.6  450.03  5017.1  451.28  5126.5  453.86  5198.6  458.25
  5236.9  461.75  5267.2  463.09  5292.1  466.48  5352.6  471.66  5422.9  479.31
#Mann= 6 ,-1 , 0
  3973.3     .12       0  4320.7     .07       0  4409.2    .035       0
  4507.9     .05       0  4999.5     .05       0  5011.6     .07       0
Bank Sta=4999.5,5011.6
XS Rating Curve= 0 ,0
Exp/Cntr=0.3,0.1

Type RM Length L Ch R = 1 ,291687  ,433,433,433
BEGIN DESCRIPTION:
PEACH CREEK9194
END DESCRIPTION:
XS GIS Cut Line= 3
      2499074.99     13861175.03        2499325.       13860375.
        2499225.       13859975.
#Sta/Elev= 30
    4166   466.8  4302.2  462.74  4349.9  462.65  4387.6  461.41  4396.5  462.17
  4438.4  459.89  4447.3  458.56  4452.6  459.04  4489.6  456.65  4511.8  455.35
  4517.5  456.06  4522.8  455.44  4582.5  456.76  4722.9  455.58  4805.1  457.15
  4878.5  455.77  4987.7  450.13  4988.2  449.63  4999.8  450.13  5001.6  450.87
  5039.4  451.77  5102.5  451.17  5127.9  451.01  5169.1  452.66  5187.1  454.59
  5244.3  458.38  5269.6  460.81  5328.5  464.52  5414.8  470.56  5416.5  470.56
#Mann= 9 ,-1 , 0
    4166     .12       0  4489.6     .05       0  4987.7     .05       0
  4999.8     .05       0  5039.4     .07       0  5102.5     .05       0
  5244.3     .07       0  5328.5     .05       0  5414.8     .07       0
Bank Sta=4987.7,4999.8
XS Rating Curve= 0 ,0
Exp/Cntr=0.3,0.1

Type RM Length L Ch R = 1 ,291254  ,436,436,436
BEGIN DESCRIPTION:
PEACH CREEK9193
END DESCRIPTION:
XS GIS Cut Line= 3
      2500424.98     13861124.97        2499675.       13860325.
      2499275.03     13859925.03
#Sta/Elev= 30
  3903.1  467.67  3975.2   465.2  4044.5  462.35  4157.8  459.69  4299.4  459.22
  4476.3  453.38  4525.6   453.2    4575  451.16  4603.3  451.47  4716.6  455.75
  4780.3  456.31  4815.7  456.23  4865.1  455.42  4872.4  454.62  4935.9  453.96
  4957.4  451.41  4970.7     451  5007.7  449.53  5008.2  449.03  5019.4  449.03
  5019.9  449.53  5042.1  450.23  5084.5  449.66  5098.6  451.06  5123.9  450.92
  5141.1  450.18  5169.4   450.3  5254.2  452.19  5459.3  465.11  5565.3  473.32
#Mann= 6 ,-1 , 0
  3903.1     .07       0  3975.2     .05       0  4970.7      .1       0
  5007.7     .05       0  5019.9      .1       0  5123.9     .05       0
Bank Sta=5007.7,5019.9
XS Rating Curve= 0 ,0
Exp/Cntr=0.3,0.1