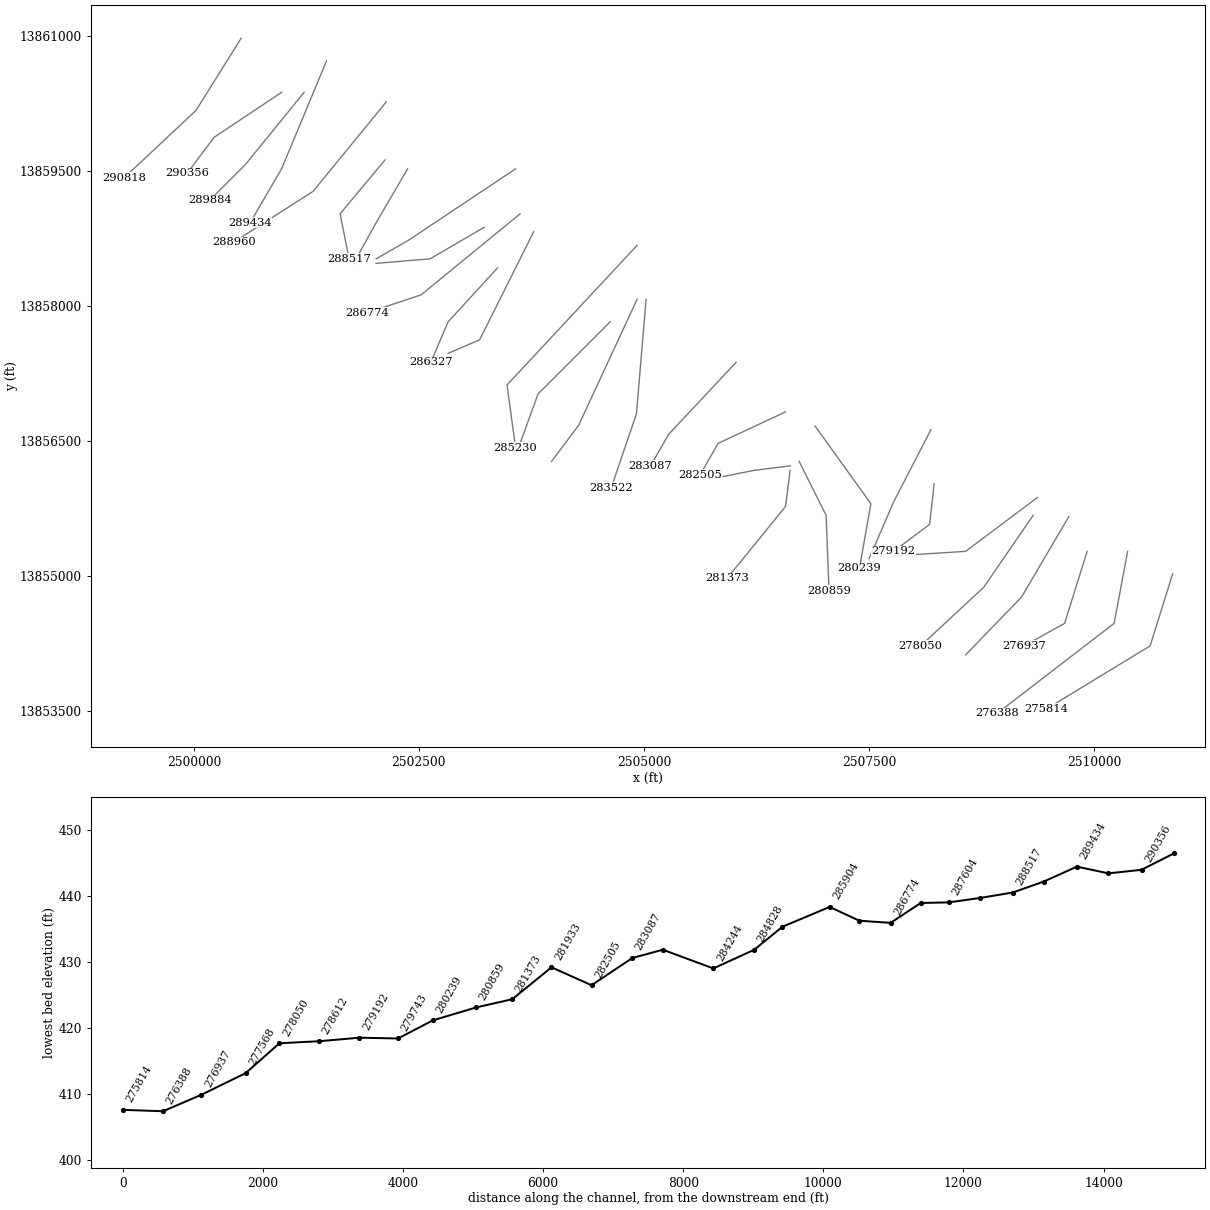
HEC-RAS study PEACH CREEK.prj: PEACH CREEK Base Level Engineering

--- PEACH CREEK.g01 (geometry) --- (continued)

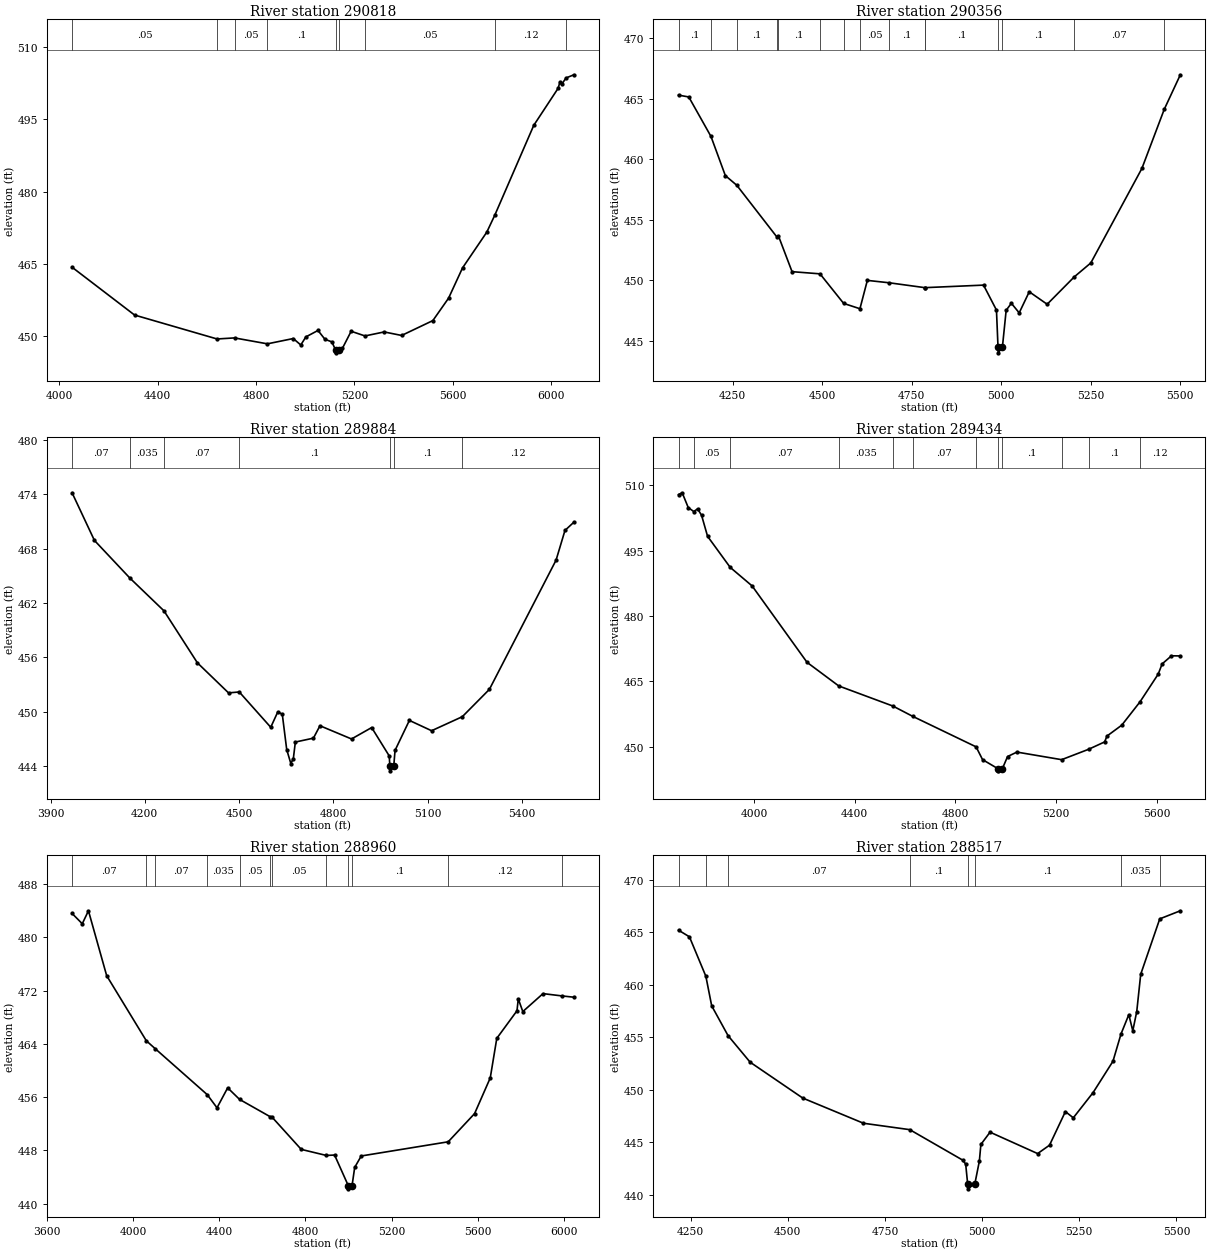
Type RM Length L Ch R = 1 ,290818  ,462,462,462
BEGIN DESCRIPTION:
PEACH CREEK9192
END DESCRIPTION:
XS GIS Cut Line= 3
      2500524.99     13860974.99        2500025.       13860175.
      2499224.98     13859424.98
#Sta/Elev= 30
  4051.9  464.28    4306  454.35  4641.4  449.38  4712.3   449.6    4846  448.37
  4951.1  449.47  4981.7  448.13  5002.4  449.81  5051.7  451.15    5080  449.31
  5108.4  448.77  5123.7     447  5124.2   446.5  5135.9     447  5150.9  447.43
  5186.5  450.98  5242.7  450.01  5320.8  450.84  5391.7  450.11  5518.7   453.2
  5582.6  457.86  5639.3  464.14    5738  471.57  5770.9  475.14    5929  493.76
  6028.1  501.46  6035.4   502.8  6042.3  502.27  6060.2  503.59  6091.9  504.25
#Mann= 9 ,-1 , 0
  4051.9     .05       0  4641.4      .1       0  4712.3     .05       0
    4846      .1       0  5123.7     .05       0  5135.9      .1       0
  5242.7     .05       0  5770.9     .12       0  6060.2     .07       0
Bank Sta=5123.7,5135.9
XS Rating Curve= 0 ,0
Exp/Cntr=0.3,0.1

Type RM Length L Ch R = 1 ,290356  ,472,472,472
BEGIN DESCRIPTION:
PEACH CREEK9191
END DESCRIPTION:
XS GIS Cut Line= 3
      2500975.03     13860375.02        2500225.       13859875.
      2499925.01     13859475.02
#Sta/Elev= 30
  4098.8  465.28  4127.4  465.13  4189.4  461.87  4229.5  458.64  4261.5  457.84
  4374.6  453.53  4377.7  453.67  4415.8  450.71  4493.9  450.53  4559.9  448.09
  4605.4  447.65  4626.1  449.99  4687.7  449.79  4786.7  449.39  4786.8  449.39
  4950.6   449.6  4986.7  447.54    4991  444.51  4991.5  444.01  5003.4  444.51
  5013.8  447.52  5028.3   448.1  5050.2  447.31  5078.3  449.05  5128.3  448.02
    5204  450.28  5250.2  451.43  5392.9  459.23  5455.3  464.11  5500.2  466.96
#Mann= 15 ,-1 , 0
  4098.8      .1       0  4189.4     .05       0  4261.5      .1       0
  4374.6     .05       0  4377.7      .1       0  4493.9     .05       0
  4559.9      .1       0  4605.4     .05       0  4687.7      .1       0
  4786.7     .05       0  4786.8      .1       0    4991     .05       0
  5003.4      .1       0    5204     .07       0  5455.3     .12       0
Bank Sta=4991,5003.4
XS Rating Curve= 0 ,0
Exp/Cntr=0.3,0.1

Type RM Length L Ch R = 1 ,289884  ,450,450,450
BEGIN DESCRIPTION:
PEACH CREEK9190
END DESCRIPTION:
XS GIS Cut Line= 3
      2501225.01     13860375.01        2500575.       13859575.
      2500174.98     13859174.98
#Sta/Elev= 30
  3968.6  474.18  4039.7  468.92  4152.5  464.76    4261  461.14  4367.3   455.4
  4466.4  452.08  4500.6  452.18  4600.7  448.28    4623  449.97  4637.4  449.73
  4651.5  445.82  4664.6  444.28  4672.6  444.82    4679  446.65  4736.5  447.08
  4757.3  448.45  4857.7  446.99  4921.8  448.25  4977.8  445.11  4979.6  443.97
  4980.1  443.47    4992  443.97  4996.2  445.73  5041.8  449.04  5112.5   447.9
  5210.2  449.45  5296.4  452.47  5508.5  466.74  5536.8  470.02  5565.1  470.93
#Mann= 7 ,-1 , 0
  3968.6     .07       0  4152.5    .035       0    4261     .07       0
  4500.6      .1       0  4979.6     .05       0    4992      .1       0
  5210.2     .12       0
Bank Sta=4979.6,4992
XS Rating Curve= 0 ,0
Exp/Cntr=0.3,0.1

Type RM Length L Ch R = 1 ,289434  ,474,474,474
BEGIN DESCRIPTION:
PEACH CREEK9189
END DESCRIPTION:
XS GIS Cut Line= 3
        2501475.       13860725.        2500975.       13859525.
      2500625.01     13858925.02
#Sta/Elev= 30
    3700  507.85  3714.6  508.25  3738.5  504.87  3760.5  503.95  3775.8  504.56
  3791.5   503.1  3815.4  498.27  3905.3  491.15  3992.5  486.89  4210.8  469.37
  4336.7  463.96  4552.4  459.34    4630  457.01  4882.8  449.99  4908.5  447.06
  4969.4  444.99  4969.9  444.49  4987.3  444.99  5007.9  447.77  5045.1  448.79
  5222.8  447.05    5330  449.43  5393.6  451.12  5403.1  452.47  5461.8  454.96
  5534.5  460.32  5606.6  466.66  5622.3  469.01  5659.5  470.87  5694.6  470.84
#Mann= 12 ,-1 , 0
    3700     .12       0  3760.5     .05       0  3905.3     .07       0
  4336.7    .035       0  4552.4     .05       0    4630     .07       0
  4882.8      .1       0  4969.4     .05       0  4987.3      .1       0
  5222.8     .12       0    5330      .1       0  5534.5     .12       0
Bank Sta=4969.4,4987.3
XS Rating Curve= 0 ,0
Exp/Cntr=0.3,0.1

Type RM Length L Ch R = 1 ,288960  ,443,443,443
BEGIN DESCRIPTION:
PEACH CREEK9188
END DESCRIPTION:
XS GIS Cut Line= 3
      2502138.22     13860268.81        2501325.       13859275.
      2500443.76     13858709.88
#Sta/Elev= 30
  3716.1  483.61  3763.5  482.06  3792.2  484.01  3876.9  474.25  4061.1  464.47
  4102.1  463.29  4343.9  456.38  4389.4   454.4  4438.9   457.4  4494.3  455.66
  4636.9  453.05  4644.7  453.01  4780.6  448.15  4897.1  447.24  4935.6   447.3
  4998.9  442.72  4999.4  442.22  5016.8  442.72    5029  445.44  5059.4  447.16
  5463.4  449.29    5586  453.53  5658.7  458.89  5689.1  464.84  5782.9  468.98
  5788.9  470.77    5810  468.86  5903.8  471.56    5993  471.21  6047.1  471.02
#Mann= 12 ,-1 , 0
  3716.1     .07       0  4061.1     .05       0  4102.1     .07       0
  4343.9    .035       0  4494.3     .05       0  4636.9     .07       0
  4644.7     .05       0  4897.1      .1       0  4998.9     .05       0
  5016.8      .1       0  5463.4     .12       0    5993     .07       0
Bank Sta=4998.9,5016.8
XS Rating Curve= 0 ,0
Exp/Cntr=0.3,0.1

Type RM Length L Ch R = 1 ,288517  ,460,460,460
BEGIN DESCRIPTION:
PEACH CREEK9187
END DESCRIPTION:
XS GIS Cut Line= 3
      2502125.01     13859625.01        2501625.       13859025.
      2501724.99     13858525.05
#Sta/Elev= 30
    4219  465.21    4247  464.58  4289.3  460.82  4304.3     458  4346.4  455.16
  4403.2  452.63  4538.6  449.21  4694.8  446.81  4813.9   446.2  4949.9   443.3
  4957.7  442.92  4962.7  441.06  4963.2  440.56  4981.4  441.06  4992.9   443.2
  4996.8  444.79  5020.4  445.96  5142.8  443.92  5173.4  444.72  5214.2  447.92
  5234.6  447.33  5285.6  449.74  5336.6  452.72  5357.3  455.32  5377.4  457.16
  5387.6  455.62  5397.8  457.46    5408  461.01    5457  466.29  5509.9  467.06
#Mann= 8 ,-1 , 0
    4219     .07       0  4289.3     .12       0  4346.4     .07       0
  4813.9      .1       0  4962.7     .05       0  4981.4      .1       0
  5357.3    .035       0    5457     .07       0
Bank Sta=4962.7,4981.4
XS Rating Curve= 0 ,0
Exp/Cntr=0.3,0.1

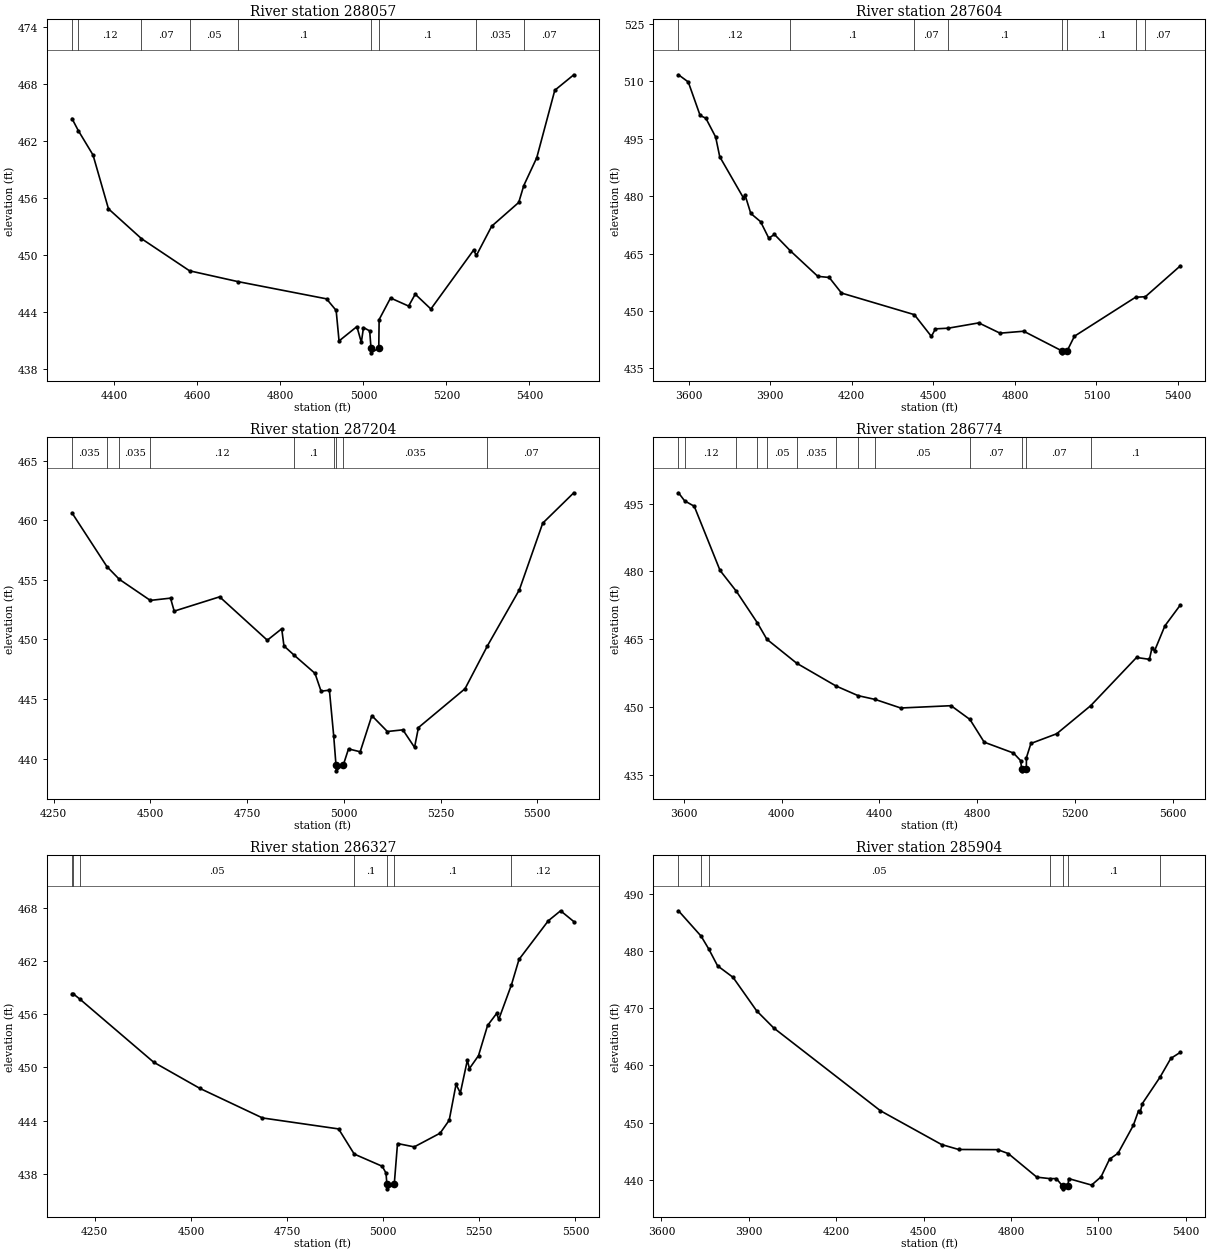
Type RM Length L Ch R = 1 ,288057  ,453,453,453
BEGIN DESCRIPTION:
PEACH CREEK9186
END DESCRIPTION:
XS GIS Cut Line= 3
      2502374.98     13859524.96        2502025.       13858925.
      2501774.98     13858474.96
#Sta/Elev= 30
  4297.5  464.39  4312.8  463.12  4348.3  460.55  4385.5  454.89  4465.1  451.75
  4580.9  448.37  4696.7  447.24    4911  445.42  4934.2   444.2  4941.2  440.99
  4984.2   442.5  4994.9  440.85  5000.1   442.4    5015  442.05  5018.2  440.24
  5018.7  439.74  5036.9  440.24  5037.8  443.24  5065.3  445.51  5108.8  444.66
  5124.8  445.91  5162.5  444.35  5265.5  450.55  5272.1  449.98    5309  453.06
  5374.2  455.56  5386.4  457.34  5417.6  460.26  5461.1  467.36  5506.9  468.99
#Mann= 9 ,-1 , 0
  4297.5     .07       0  4312.8     .12       0  4465.1     .07       0
  4580.9     .05       0  4696.7      .1       0  5018.2     .05       0
  5036.9      .1       0  5272.1    .035       0  5386.4     .07       0
Bank Sta=5018.2,5036.9
XS Rating Curve= 0 ,0
Exp/Cntr=0.3,0.1

Type RM Length L Ch R = 1 ,287604  ,400,400,400
BEGIN DESCRIPTION:
PEACH CREEK9185
END DESCRIPTION:
XS GIS Cut Line= 3
      2503574.97     13859524.98        2502375.       13858725.
        2502025.       13858525.
#Sta/Elev= 30
    3563  511.75    3599  509.87  3642.6  501.11  3663.6   500.4  3699.7  495.48
  3714.7  490.33  3801.8  479.57  3807.8  480.32  3828.9   475.5  3864.9  473.35
    3895  469.05    3916  470.01  3974.8   465.7  4075.3  459.06  4117.3  458.76
  4162.4  454.69  4430.3  449.04  4492.9  443.36  4507.9  445.33  4554.6   445.5
  4667.2  446.89  4745.3   444.2  4832.4  444.71  4973.2  439.56  4973.7  439.06
    4992  439.56  5018.9   443.4  5243.6  453.59  5279.7  453.73  5408.3   461.8
#Mann= 8 ,-1 , 0
    3563     .12       0  3974.8      .1       0  4430.3     .07       0
  4554.6      .1       0  4973.2     .05       0    4992      .1       0
  5243.6    .035       0  5279.7     .07       0
Bank Sta=4973.2,4992
XS Rating Curve= 0 ,0
Exp/Cntr=0.3,0.1

Type RM Length L Ch R = 1 ,287204  ,430,430,430
BEGIN DESCRIPTION:
PEACH CREEK9184
END DESCRIPTION:
XS GIS Cut Line= 3
      2503224.96     13858874.98        2502625.       13858525.
      2502024.96       13858475.
#Sta/Elev= 30
  4297.5  460.62  4387.8  456.11  4419.9  455.04    4500  453.27  4552.2  453.46
  4561.7  452.37  4679.1  453.57  4802.3  449.93  4839.5  450.89  4845.3  449.45
  4871.8  448.67  4925.5  447.15  4941.2  445.65  4962.7  445.74  4973.8  441.92
  4979.7  439.47  4980.2  438.97  4998.7  439.47  5012.1  440.81  5042.3  440.57
  5072.4   443.6  5112.5  442.27  5152.6  442.41  5182.7  440.94  5192.8   442.6
  5313.2  445.86  5371.1  449.46  5453.7  454.17  5513.9  459.75  5594.2   462.3
#Mann= 9 ,-1 , 0
  4297.5    .035       0  4387.8      .1       0  4419.9    .035       0
    4500     .12       0  4871.8      .1       0  4973.8    .035       0
  4979.7    .035       0  4998.7    .035       0  5371.1     .07       0
Bank Sta=4979.7,4998.7
XS Rating Curve= 0 ,0
Exp/Cntr=0.3,0.1

Type RM Length L Ch R = 1 ,286774  ,447,447,447
BEGIN DESCRIPTION:
PEACH CREEK9183
END DESCRIPTION:
XS GIS Cut Line= 3
        2503625.       13859025.        2502525.       13858125.
      2501925.02     13857925.01
#Sta/Elev= 30
  3578.2  497.37  3603.4  495.59  3642.8  494.39  3748.3  480.22  3815.5  475.58
  3901.1  468.63    3940  465.01    4062  459.72  4222.9  454.69  4313.2  452.56
  4383.8  451.71  4487.7  449.83  4693.7  450.34  4770.9   447.3  4829.3  442.28
  4949.2  439.88  4977.9  438.23  4982.8  436.45  4983.3  435.95  5001.8  436.45
  5002.1  438.86  5020.5     442    5126  444.14  5265.5  450.36  5452.7  460.99
  5505.4  460.58    5516   463.1  5526.5  462.46  5568.7  467.97  5631.9  472.58
#Mann= 13 ,-1 , 0
  3578.2     .07       0  3603.4     .12       0  3815.5    .035       0
  3901.1     .12       0    3940     .05       0    4062    .035       0
  4222.9     .05       0  4313.2    .035       0  4383.8     .05       0
  4770.9     .07       0  4982.8     .05       0  5001.8     .07       0
  5265.5      .1       0
Bank Sta=4982.8,5001.8
XS Rating Curve= 0 ,0
Exp/Cntr=0.3,0.1

Type RM Length L Ch R = 1 ,286327  ,423,423,423
BEGIN DESCRIPTION:
PEACH CREEK9182
END DESCRIPTION:
XS GIS Cut Line= 3
      2503375.03     13858425.03        2502825.       13857825.
      2502632.09     13857373.46
#Sta/Elev= 30
  4190.7  458.33  4194.5   458.3  4211.8   457.7  4403.2  450.59  4523.4  447.63
  4686.2  444.29  4884.1  443.05  4924.7  440.21  4997.6  438.83  5007.4  438.06
  5009.7  436.78  5010.2  436.28  5028.8  436.78  5037.3   441.4  5080.8  441.02
  5148.1  442.57  5171.7  444.03  5189.5  448.08  5200.7  447.12  5218.9  450.81
  5224.3  449.87  5247.9  451.33  5271.5  454.74  5295.1   456.1  5300.6  455.43
  5333.7  459.35  5353.2   462.2  5429.4  466.57  5461.4   467.7  5495.7  466.48
#Mann= 7 ,-1 , 0
  4190.7     .05       0  4194.5    .035       0  4211.8     .05       0
  4924.7      .1       0  5009.7     .05       0  5028.8      .1       0
  5333.7     .12       0
Bank Sta=5009.7,5028.8
XS Rating Curve= 0 ,0
Exp/Cntr=0.3,0.1

Type RM Length L Ch R = 1 ,285904  ,674,674,674
BEGIN DESCRIPTION:
PEACH CREEK9181
END DESCRIPTION:
XS GIS Cut Line= 3
        2503775.       13858825.        2503175.       13857625.
      2502825.02     13857475.01
#Sta/Elev= 30
  3658.6  487.12  3736.3  482.67  3762.4  480.43  3792.8  477.47  3845.9  475.45
  3926.9  469.58  3985.6  466.57  4351.8  452.06  4561.4  446.14  4620.1  445.27
  4754.3  445.24  4790.6  444.55  4888.4  440.42  4933.3  440.16  4955.5  440.17
  4976.7  438.87  4977.2  438.37  4995.8  438.87  4997.4  440.17  5076.4  439.03
    5109  440.48    5138  443.57  5167.1   444.6  5219.6  449.49  5237.8  452.09
  5243.2  451.79  5250.5  453.31  5311.5  457.96  5348.4  461.24    5381   462.3
#Mann= 7 ,-1 , 0
  3658.6     .05       0  3736.3    .035       0  3762.4     .05       0
  4933.3      .1       0  4976.7     .05       0  4995.8      .1       0
  5311.5     .12       0
Bank Sta=4976.7,4995.8
XS Rating Curve= 0 ,0
Exp/Cntr=0.3,0.1

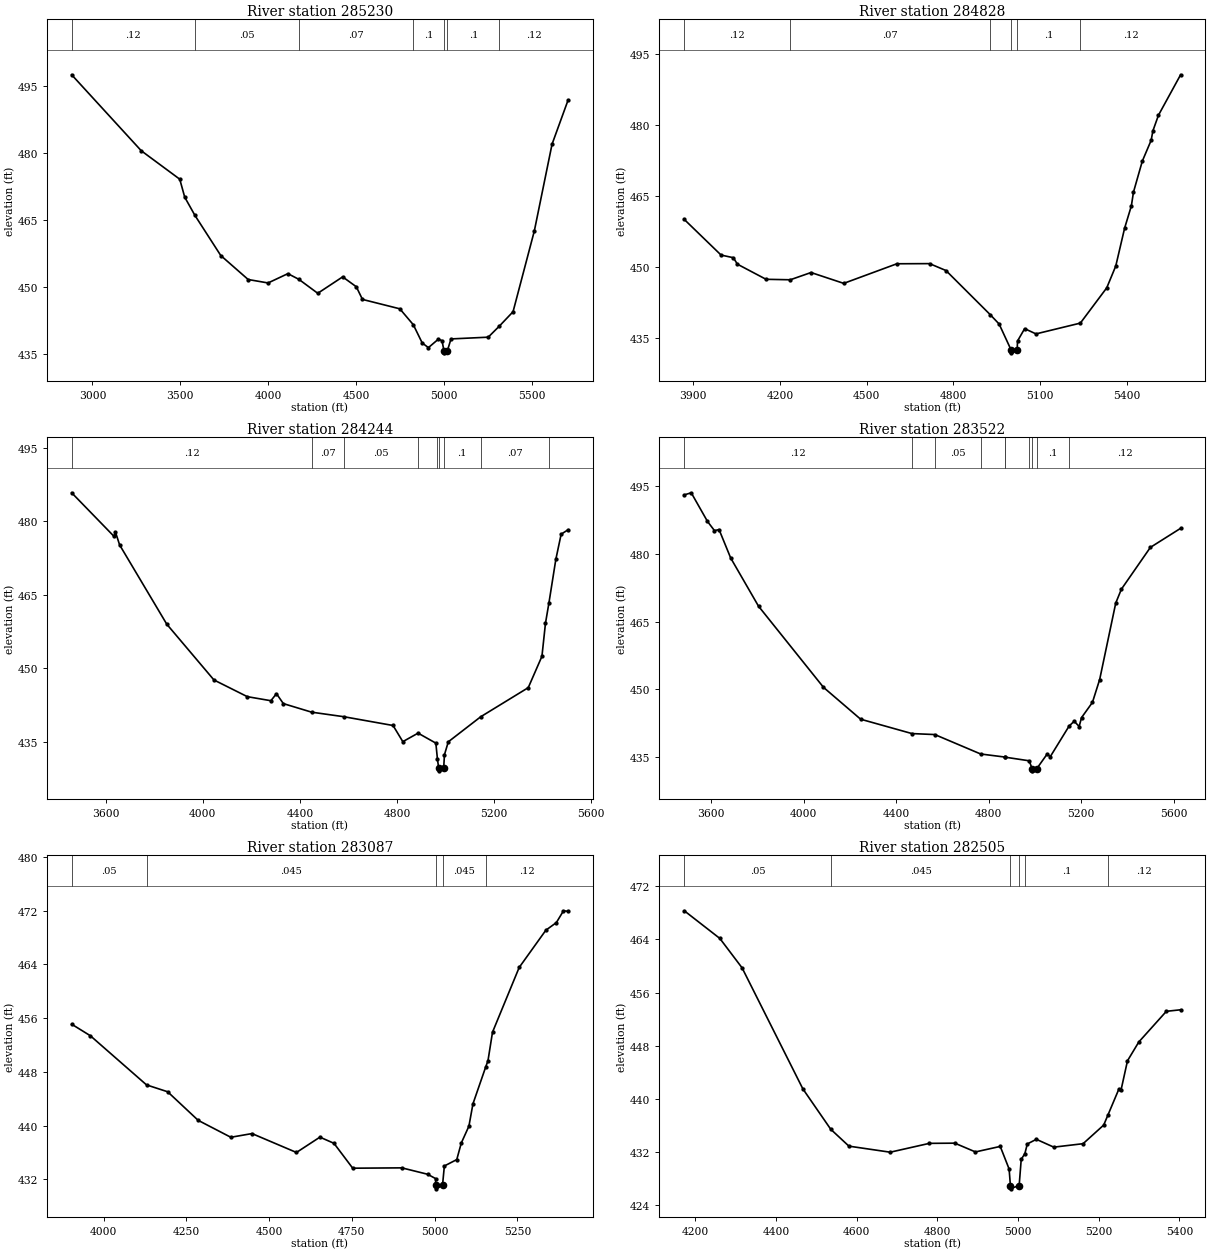
Type RM Length L Ch R = 1 ,285230  ,402,402,402
BEGIN DESCRIPTION:
PEACH CREEK9180
END DESCRIPTION:
XS GIS Cut Line= 3
      2504924.97     13858674.97      2503479.69     13857123.96
      2503574.99     13856425.05
#Sta/Elev= 30
  2881.6  497.51    3278  480.52  3496.9  474.17  3525.2  470.15  3583.1  466.09
  3730.4  457.11  3886.3  451.75  3999.6  450.98  4112.5  453.06  4174.9  451.79
  4282.5  448.67  4424.2  452.34  4501.9  450.13    4537   447.3  4749.6   445.2
  4826.5  441.64  4877.1  437.57  4912.3  436.52  4968.9  438.41  4989.9  438.08
  5000.7  435.86  5001.2  435.36  5020.7  435.86  5040.9  438.47  5252.9  438.86
  5315.9  441.32  5394.2  444.55  5515.3   462.6  5616.2  481.99    5707   491.8
#Mann= 7 ,-1 , 0
  2881.6     .12       0  3583.1     .05       0  4174.9     .07       0
  4826.5      .1       0  5000.7     .05       0  5020.7      .1       0
  5315.9     .12       0
Bank Sta=5000.7,5020.7
XS Rating Curve= 0 ,0
Exp/Cntr=0.3,0.1

Type RM Length L Ch R = 1 ,284828  ,584,584,584
BEGIN DESCRIPTION:
PEACH CREEK9179
END DESCRIPTION:
XS GIS Cut Line= 3
      2504624.97     13857824.97        2503825.       13857025.
      2503624.99     13856474.96
#Sta/Elev= 30
  3868.9  460.04  3996.1  452.52  4038.6  451.96  4052.7  450.59  4151.7   447.4
  4235.6   447.3  4307.3  448.83  4420.4  446.54  4604.2  450.68  4717.4  450.71
    4774  449.25  4926.6  439.96  4957.8  437.96  5000.1  432.37  5000.6  431.87
  5020.2  432.37  5021.5  434.37  5046.1  436.98  5085.3  435.87  5238.8  438.15
  5330.1   445.6  5361.3  450.21  5391.9  458.21  5415.2   462.9  5422.5  465.81
  5453.1  472.36  5483.7  476.76  5489.7  478.75    5509  482.06  5585.5  490.59
#Mann= 6 ,-1 , 0
  3868.9     .12       0  4235.6     .07       0  4926.6      .1       0
  5000.1     .05       0  5020.2      .1       0  5238.8     .12       0
Bank Sta=5000.1,5020.2
XS Rating Curve= 0 ,0
Exp/Cntr=0.3,0.1

Type RM Length L Ch R = 1 ,284244  ,722,722,722
BEGIN DESCRIPTION:
PEACH CREEK9178
END DESCRIPTION:
XS GIS Cut Line= 3
      2504925.01     13858075.02        2504275.       13856675.
      2503974.97     13856274.96
#Sta/Elev= 30
  3460.3  485.82  3634.8  476.91  3640.3  477.85  3657.7  475.17  3851.9  458.98
  4046.1  447.59  4183.5  444.18  4280.6  443.35  4303.5  444.79  4331.9  442.76
  4448.5  441.01  4580.2  440.09  4783.6  438.29  4823.8  434.99  4886.6  436.73
  4959.8  434.69  4966.5  431.35  4971.7  429.53  4972.2  429.03    4992  429.53
  4995.2  432.32  5011.1  434.96  5144.4  440.07  5340.3  446.02  5396.6  452.42
  5411.1  459.15  5425.6  463.38  5453.9  472.24  5475.7  477.36  5503.9  478.26
#Mann= 9 ,-1 , 0
  3460.3     .12       0  4448.5     .07       0  4580.2     .05       0
  4886.6     .07       0  4966.5      .1       0  4971.7     .05       0
    4992      .1       0  5144.4     .07       0  5425.6     .12       0
Bank Sta=4971.7,4992
XS Rating Curve= 0 ,0
Exp/Cntr=0.3,0.1

Type RM Length L Ch R = 1 ,283522  ,435,435,435
BEGIN DESCRIPTION:
PEACH CREEK9177
END DESCRIPTION:
XS GIS Cut Line= 3
        2505025.     13858074.99      2504917.39     13856802.15
      2504636.72      13855979.5
#Sta/Elev= 30
    3483  493.11  3513.1  493.58  3583.4  487.22  3613.5  485.19  3633.5  485.41
  3683.7  479.11  3804.1  468.41  4085.1   450.4  4245.7  443.33  4467.6  440.14
  4566.6  439.92  4764.8  435.61  4869.4  434.93  4869.7  434.91  4974.7   434.1
  4987.4  432.37  4987.9  431.87  5007.7  432.37  5053.2  435.65  5065.5  434.98
  5147.4  441.81  5169.4  442.88  5190.9  441.71  5201.1  443.68  5248.3  447.06
  5279.6  452.14  5349.1  469.11  5373.6  472.19  5498.9  481.46  5629.6  485.69
#Mann= 10 ,-1 , 0
    3483     .12       0  4467.6     .07       0  4566.6     .05       0
  4764.8     .07       0  4869.4     .05       0  4869.7     .07       0
  4974.7      .1       0  4987.4     .05       0  5007.7      .1       0
  5147.4     .12       0
Bank Sta=4987.4,5007.7
XS Rating Curve= 0 ,0
Exp/Cntr=0.3,0.1

Type RM Length L Ch R = 1 ,283087  ,582,582,582
BEGIN DESCRIPTION:
PEACH CREEK9176
END DESCRIPTION:
XS GIS Cut Line= 3
      2506025.03     13857375.03        2505275.       13856575.
      2505075.02     13856225.04
#Sta/Elev= 30
  3903.4   455.1  3959.9  453.38  4129.6  446.07  4193.4  445.05  4285.6   440.8
  4384.3  438.28  4448.3  438.83  4582.6  436.02  4653.5   438.3    4696  437.38
  4752.6  433.68  4901.1  433.73  4978.8  432.78  5002.9  432.14  5003.6  431.11
  5004.1  430.61  5023.9  431.11  5029.5  434.01    5067  434.96  5080.7  437.43
  5103.7  439.93  5115.9  443.25  5154.8  448.79  5161.3  449.66    5175  453.91
  5255.6  463.54  5336.2  469.08  5367.9  470.21  5389.5  471.97  5403.1  471.89
#Mann= 5 ,-1 , 0
  3903.4     .05       0  4129.6    .045       0  5003.6    .045       0
  5023.9    .045       0  5154.8     .12       0
Bank Sta=5003.6,5023.9
XS Rating Curve= 0 ,0
Exp/Cntr=0.3,0.1

Type RM Length L Ch R = 1 ,282505  ,572,572,572
BEGIN DESCRIPTION:
PEACH CREEK9175
END DESCRIPTION:
XS GIS Cut Line= 3
      2506574.97     13856824.98        2505825.       13856475.
      2505625.01     13856125.02
#Sta/Elev= 30
  4172.4   468.3  4260.6  464.14  4315.8  459.71  4466.4  441.52  4535.6  435.44
  4580.7   432.9  4683.1  431.99  4780.1  433.32  4843.2  433.35  4894.4  432.03
  4955.9  432.86  4977.9  429.46  4981.1  426.98  4981.6  426.48  5001.5  426.98
  5002.9  427.06  5007.9  430.92  5016.9  431.77    5023  433.23  5045.4  433.93
  5088.6  432.75  5161.3  433.27  5212.4  436.07    5223  437.59  5249.8  441.45
  5255.6  441.39  5271.4  445.74  5299.5  448.57  5367.8  453.18  5403.1  453.41
#Mann= 6 ,-1 , 0
  4172.4     .05       0  4535.6    .045       0  4981.1    .045       0
  5001.5    .045       0  5016.9      .1       0    5223     .12       0
Bank Sta=4981.1,5001.5
XS Rating Curve= 0 ,0
Exp/Cntr=0.3,0.1

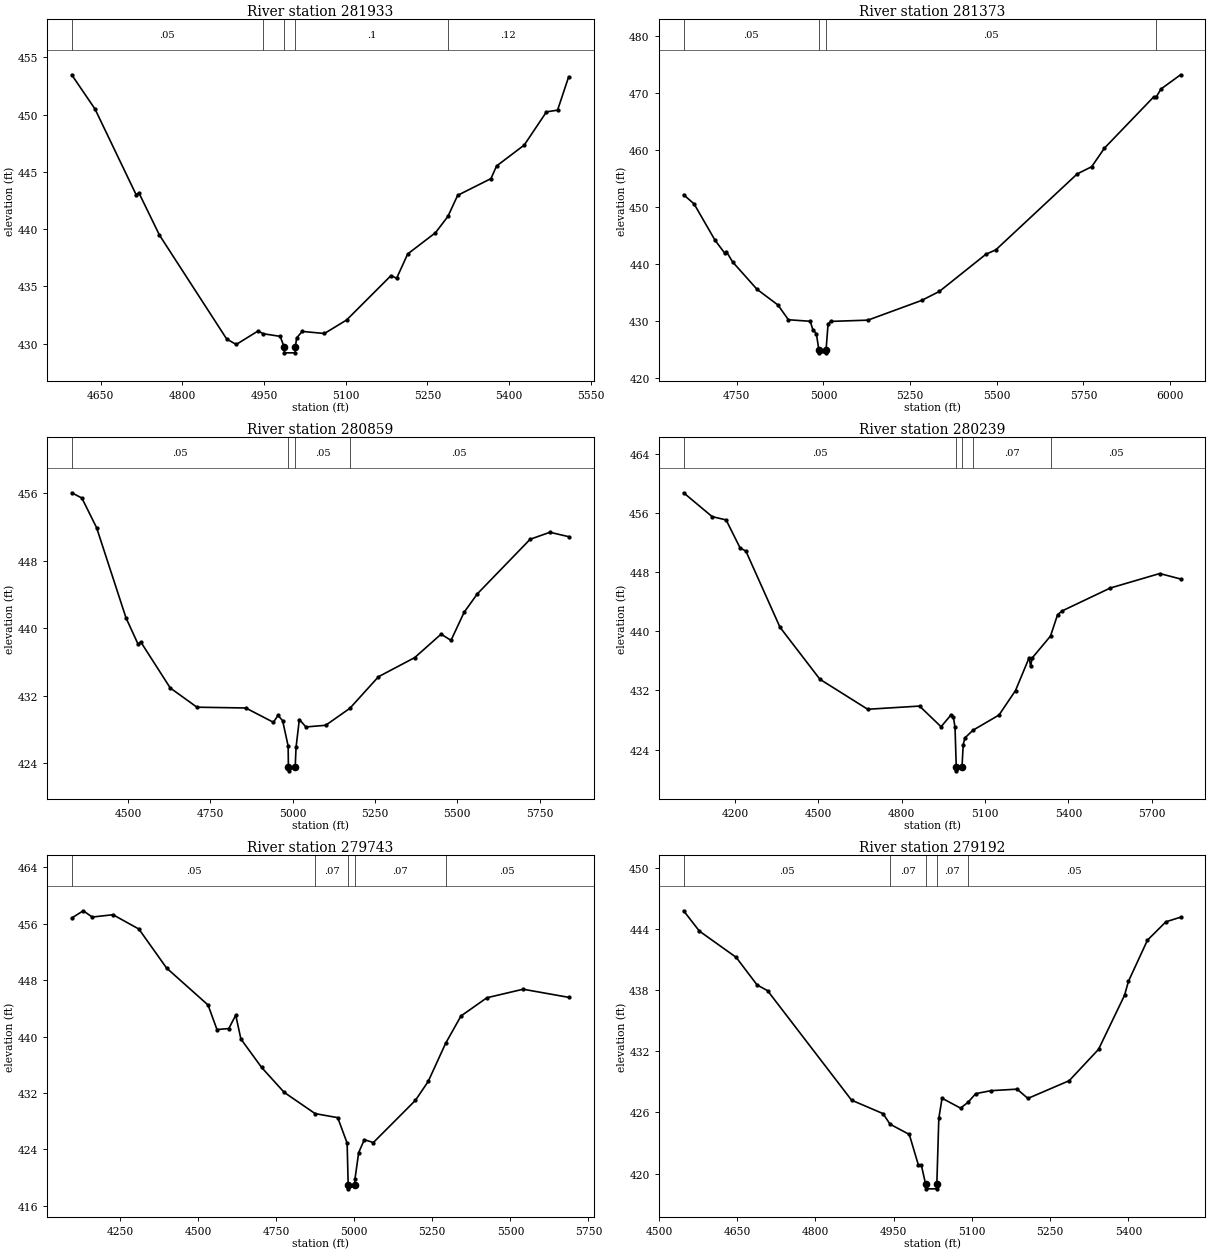
Type RM Length L Ch R = 1 ,281933  ,560,560,560
BEGIN DESCRIPTION:
PEACH CREEK9174
END DESCRIPTION:
XS GIS Cut Line= 3
      2506625.01       13856225.        2506225.       13856175.
      2505725.03     13856075.01
#Sta/Elev= 30
  4596.6  453.49  4639.4   450.5    4715  443.01  4720.1  443.17  4757.9  439.48
  4881.3  430.41  4898.9  429.93  4939.3  431.12  4948.1  430.87  4979.6  430.64
    4987   429.7  4987.5   429.2    5007   429.2  5007.5   429.7  5009.9  430.51
  5020.1  431.07  5060.9  430.89  5101.7  432.07  5183.3  435.95  5193.5  435.71
  5213.9  437.84  5264.9  439.69  5287.8  441.12  5305.7  442.96  5366.9  444.42
  5377.1  445.52    5428  447.35  5468.8  450.25  5489.2   450.4  5509.6  453.31
#Mann= 5 ,-1 , 0
  4596.6     .05       0  4948.1      .1       0    4987     .05       0
  5007.5      .1       0  5287.8     .12       0
Bank Sta=4987,5007.5
XS Rating Curve= 0 ,0
Exp/Cntr=0.3,0.1

Type RM Length L Ch R = 1 ,281373  ,514,514,514
BEGIN DESCRIPTION:
PEACH CREEK9173
END DESCRIPTION:
XS GIS Cut Line= 3
        2506625.     13856175.02        2506575.       13855775.
      2505925.01     13854975.01
#Sta/Elev= 30
  4596.5  452.16  4626.8  450.54  4687.2  444.15  4714.9  441.91    4720  442.16
  4737.6  440.36  4808.2  435.53  4868.6  432.77  4898.9  430.17  4961.8   429.9
  4969.4  428.42  4979.5  427.72  4986.8  424.85  4987.3  424.35    5007  424.35
  5007.5  424.85  5013.3  429.41  5021.2  429.88  5128.2   430.1  5283.3  433.57
  5334.4  435.15  5468.7  441.69  5497.4  442.47  5732.3  455.83    5774  457.09
  5810.6  460.35  5952.9  469.37  5960.2  469.34  5973.7  470.75  6030.4  473.26
#Mann= 4 ,-1 , 0
  4596.5     .05       0  4986.8     .05       0  5007.5     .05       0
  5960.2     .07       0
Bank Sta=4986.8,5007.5
XS Rating Curve= 0 ,0
Exp/Cntr=0.3,0.1

Type RM Length L Ch R = 1 ,280859  ,620,620,620
BEGIN DESCRIPTION:
PEACH CREEK9172
END DESCRIPTION:
XS GIS Cut Line= 3
      2506724.99     13856275.03        2507025.       13855675.
      2507057.37     13854838.18
#Sta/Elev= 30
  4329.5  456.06  4360.3  455.44    4405  451.93  4494.4  441.23  4530.8  438.13
  4539.2  438.38  4628.6  432.93  4709.7  430.65  4857.8  430.56  4941.7  428.86
  4955.6  429.68  4969.6  429.06  4986.4  426.06  4987.2  423.61  4987.7  423.11
  5007.9  423.61  5010.4  425.89  5020.4  429.19  5040.4  428.31  5100.4  428.51
  5173.8  430.52  5260.5  434.26  5370.6  436.53  5450.7  439.31  5480.7  438.57
  5520.7  441.91  5560.8  444.09  5720.9  450.55  5780.9  451.38  5837.8  450.86
#Mann= 4 ,-1 , 0
  4329.5     .05       0  4987.2     .05       0  5007.9     .05       0
  5173.8     .05       0
Bank Sta=4987.2,5007.9
XS Rating Curve= 0 ,0
Exp/Cntr=0.3,0.1

Type RM Length L Ch R = 1 ,280239  ,496,496,496
BEGIN DESCRIPTION:
PEACH CREEK9171
END DESCRIPTION:
XS GIS Cut Line= 3
       2506902.5     13856666.58      2507522.24     13855804.76
      2507396.52     13855089.13
#Sta/Elev= 30
  4015.6  458.71  4118.2  455.49  4168.5  455.04  4218.8  451.26  4239.7  450.83
  4362.4  440.54  4506.1  433.51  4677.9  429.46  4864.5  429.89  4941.9   427.1
  4978.3  428.72    4986  428.47  4992.2     427  4996.6  421.64  4997.1  421.14
  5017.3  421.64  5021.6  424.69  5027.8  425.59  5056.5  426.62  5150.4  428.68
  5209.8  431.99    5259  436.44  5264.1  435.25  5269.8  436.39  5335.7  439.35
  5361.2  442.24  5377.7  442.75  5550.7  445.84  5728.8   447.8  5803.7  447.06
#Mann= 5 ,-1 , 0
  4015.6     .05       0  4996.6     .05       0  5017.3     .05       0
  5056.5     .07       0  5335.7     .05       0
Bank Sta=4996.6,5017.3
XS Rating Curve= 0 ,0
Exp/Cntr=0.3,0.1

Type RM Length L Ch R = 1 ,279743  ,551,551,551
BEGIN DESCRIPTION:
PEACH CREEK9170
END DESCRIPTION:
XS GIS Cut Line= 3
      2508190.41     13856627.88        2507775.       13855825.
      2507502.88     13855194.71
#Sta/Elev= 30
    4096  456.81    4133  457.84  4161.7  456.95  4228.1  457.28    4311  455.25
  4399.6  449.72  4532.4  444.47  4560.9  440.99  4598.8  441.13    4621  443.03
  4637.5  439.65  4703.9  435.61    4776  432.08  4875.2  429.06  4947.4  428.49
  4977.5  424.88  4980.9  418.89  4981.4  418.39  5002.6  418.89  5002.7   419.8
  5014.5  423.54  5032.5  425.36  5061.5  424.96    5196  430.94  5236.9  433.62
  5292.7  439.03  5341.8  442.91  5424.8   445.5  5540.8  446.71  5686.5  445.56
#Mann= 5 ,-1 , 0
    4096     .05       0  4875.2     .07       0  4980.9     .05       0
  5002.6     .07       0  5292.7     .05       0
Bank Sta=4980.9,5002.6
XS Rating Curve= 0 ,0
Exp/Cntr=0.3,0.1

Type RM Length L Ch R = 1 ,279192  ,580,580,580
BEGIN DESCRIPTION:
PEACH CREEK9169
END DESCRIPTION:
XS GIS Cut Line= 3
      2508225.01     13856025.05        2508175.       13855575.
      2507775.01     13855275.01
#Sta/Elev= 30
  4547.2  445.76  4577.4  443.77  4647.9   441.2  4688.1  438.49  4708.2  437.93
  4869.2   427.2  4929.6  425.88  4942.9  424.85  4979.9  423.84  4997.5  420.81
  5003.1  420.81    5011  419.01  5011.5  418.51  5032.2  418.51  5032.7  419.01
  5036.5  425.42  5042.7  427.39  5078.1  426.42  5092.3  426.98  5107.3  427.84
  5136.5  428.13  5186.5  428.28  5207.3  427.37  5286.5  429.11  5342.7  432.18
  5392.7  437.49    5400  438.84  5436.5  442.88  5471.9  444.68    5500  445.13
#Mann= 5 ,-1 , 0
  4547.2     .05       0  4942.9     .07       0    5011     .05       0
  5032.7     .07       0  5092.3     .05       0
Bank Sta=5011,5032.7
XS Rating Curve= 0 ,0
Exp/Cntr=0.3,0.1

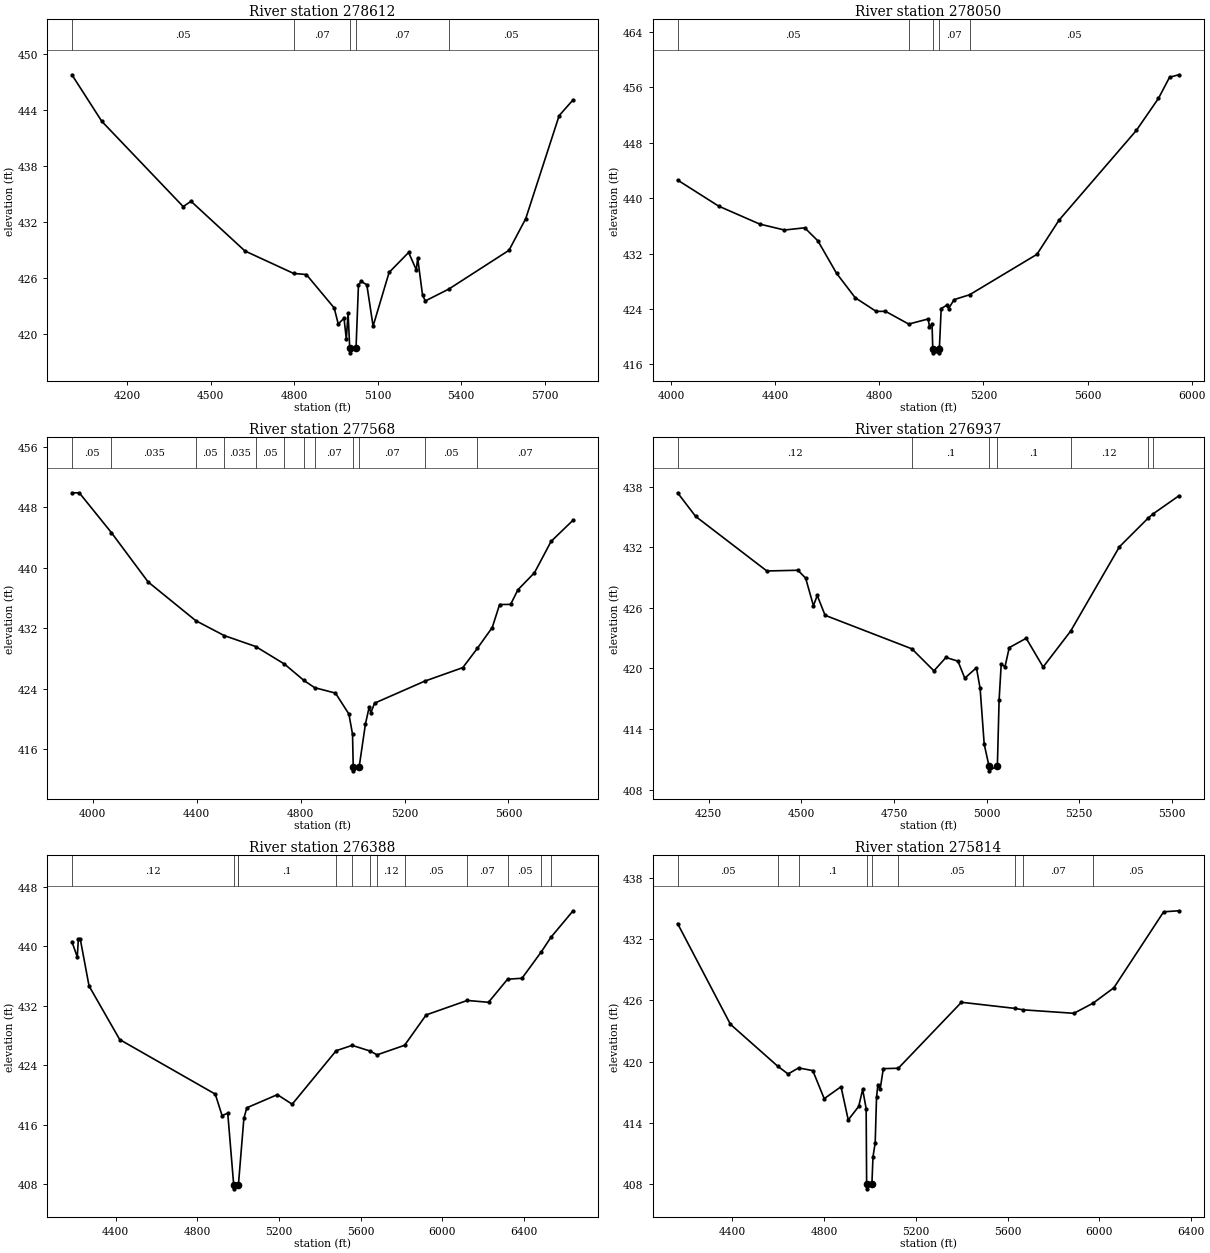
Type RM Length L Ch R = 1 ,278612  ,562,562,562
BEGIN DESCRIPTION:
PEACH CREEK9168
END DESCRIPTION:
XS GIS Cut Line= 3
      2509374.97     13855874.98        2508575.       13855275.
      2507775.02       13855225.
#Sta/Elev= 30
  4000.6   447.8  4107.9  442.81  4400.6  433.66  4428.7  434.23  4622.4   428.9
  4797.5  426.49  4843.3  426.37  4943.3  422.79  4957.9  421.07  4978.7  421.68
    4987  419.45  4993.3  422.27  4999.2  418.47  4999.7  417.97  5021.9  418.47
  5030.6  425.27  5040.6  425.63  5060.7  425.27  5083.2  420.84  5140.8   426.6
    5211  428.74  5238.5  426.87  5243.5  428.13  5261.1  424.13  5271.1  423.54
  5355.3  424.81  5571.7  428.97  5631.8  432.36    5752  443.42  5802.1  445.11
#Mann= 5 ,-1 , 0
  4000.6     .05       0  4797.5     .07       0  4999.2     .05       0
  5021.9     .07       0  5355.3     .05       0
Bank Sta=4999.2,5021.9
XS Rating Curve= 0 ,0
Exp/Cntr=0.3,0.1

Type RM Length L Ch R = 1 ,278050  ,482,482,482
BEGIN DESCRIPTION:
PEACH CREEK9167
END DESCRIPTION:
XS GIS Cut Line= 3
      2509325.02     13855675.03        2508775.       13854875.
      2508075.01     13854225.01
#Sta/Elev= 30
  4024.4   442.6  4182.2  438.84    4340  436.25  4435.1  435.39  4512.9  435.71
  4563.6  433.83  4635.3  429.15  4707.1  425.62  4787.6  423.65  4823.4  423.66
  4912.7  421.82  4987.8  422.56  4992.2  421.44  5002.4  421.83  5005.2  418.17
  5005.7  417.67  5027.4  417.67  5027.9  418.17  5030.7  418.45  5037.5  424.06
    5059  424.54  5065.9  424.06  5087.4  425.35  5146.7  426.05  5405.4  431.88
  5490.5  436.82  5787.5  449.76  5872.6  454.39  5915.1  457.43  5950.5  457.79
#Mann= 5 ,-1 , 0
  4024.4     .05       0  4912.7     .07       0  5005.2     .05       0
  5027.9     .07       0  5146.7     .05       0
Bank Sta=5005.2,5027.9
XS Rating Curve= 0 ,0
Exp/Cntr=0.3,0.1

Type RM Length L Ch R = 1 ,277568  ,631,631,631
BEGIN DESCRIPTION:
PEACH CREEK9166
END DESCRIPTION:
XS GIS Cut Line= 3
       2509720.4     13855659.54      2509197.48     13854768.63
      2508575.03     13854125.03
#Sta/Elev= 30
  3920.2   449.9  3948.7  449.89  4072.2  444.63  4213.4  438.11  4396.7  432.99
  4506.1  431.02  4627.3  429.57  4738.1  427.25    4813  425.08  4854.1  424.13
  4934.3  423.41    4986  420.64    5000  417.96  5002.6  413.63  5003.1  413.13
  5025.4  413.63  5049.5   419.3  5063.7  421.52  5070.6  420.82  5084.8  422.08
    5277  424.98  5424.3  426.78    5480  429.32  5537.5  432.08  5565.8  435.12
  5608.2  435.14  5636.5  437.08  5700.1  439.33  5763.9  443.47  5848.6  446.28
#Mann= 12 ,-1 , 0
  3920.2     .05       0  4072.2    .035       0  4396.7     .05       0
  4506.1    .035       0  4627.3     .05       0  4738.1    .035       0
    4813     .05       0  4854.1     .07       0  5002.6     .05       0
  5025.4     .07       0    5277     .05       0    5480     .07       0
Bank Sta=5002.6,5025.4
XS Rating Curve= 0 ,0
Exp/Cntr=0.3,0.1

Type RM Length L Ch R = 1 ,276937  ,549,549,549
BEGIN DESCRIPTION:
PEACH CREEK9165
END DESCRIPTION:
XS GIS Cut Line= 3
      2509924.99     13855274.98        2509675.       13854475.
      2509225.01     13854225.01
#Sta/Elev= 30
    4166  437.41  4214.7  435.07  4406.9  429.66  4490.8  429.73  4511.7  428.95
  4532.7  426.22  4543.1  427.23  4564.1  425.27  4798.6  421.94    4858  419.76
  4890.5  421.09  4922.9  420.72  4941.3  419.03  4972.7  420.07  4982.7  418.02
  4993.7   412.5  5006.5  410.35    5007  409.85  5029.3  410.35  5033.9  416.84
  5039.6  420.41  5049.9  420.18  5061.3  422.06  5107.1  422.99  5152.8  420.14
  5226.9  423.69  5358.8  432.06    5436  434.89  5448.8   435.3  5518.9   437.1
#Mann= 7 ,-1 , 0
    4166     .12       0  4798.6      .1       0  5006.5     .05       0
  5029.3      .1       0  5226.9     .12       0    5436     .05       0
  5448.8     .07       0
Bank Sta=5006.5,5029.3
XS Rating Curve= 0 ,0
Exp/Cntr=0.3,0.1

Type RM Length L Ch R = 1 ,276388  ,574,574,574
BEGIN DESCRIPTION:
PEACH CREEK9164
END DESCRIPTION:
XS GIS Cut Line= 3
        2510375.     13855274.99        2510225.       13854475.
      2508924.96     13853474.97
#Sta/Elev= 30
  4186.1  440.64  4212.4  438.57  4217.5  440.94  4226.8  441.02    4270  434.67
  4420.1  427.45  4888.1   420.1  4921.2  417.22  4949.2  417.52  4978.4  407.84
  4978.9  407.34  5001.3  407.84  5001.5  407.91  5028.1  416.83  5042.6  418.26
  5192.1  420.03  5264.7  418.74  5480.1  425.95  5558.4  426.67  5647.6  425.89
  5680.1  425.39  5815.1  426.68  5920.7  430.77    6122  432.72    6226  432.47
  6319.3  435.58    6390  435.71  6485.1  439.29  6531.7  441.23  6640.2   444.8
#Mann= 13 ,-1 , 0
  4186.1     .12       0  4978.4     .05       0  5001.3     .12       0
  5001.5      .1       0  5480.1    .035       0  5558.4      .1       0
  5647.6     .05       0  5680.1     .12       0  5815.1     .05       0
    6122     .07       0  6319.3     .05       0  6485.1     .07       0
  6531.7     .05       0
Bank Sta=4978.4,5001.3
XS Rating Curve= 0 ,0
Exp/Cntr=0.3,0.1

Type RM Length L Ch R = 1 ,275814  ,547,547,547
BEGIN DESCRIPTION:
PEACH CREEK9163
END DESCRIPTION:
XS GIS Cut Line= 3
        2510875.     13855024.99        2510625.       13854225.
      2509475.03     13853525.02
#Sta/Elev= 30
  4161.7  433.53  4392.2  423.66  4598.7  419.55  4643.1   418.8  4689.2  419.39
    4751  419.13  4800.8  416.38  4874.1  417.55  4905.5   414.3  4951.1  415.62
  4968.4  417.28  4983.6  415.41  4985.7  408.05  4986.2  407.55  5008.7  408.05
  5013.4  410.69    5023  412.05  5028.9  416.56    5035  417.76  5044.4  417.28
  5058.4  419.32  5123.8  419.36  5398.9  425.82  5632.4  425.22  5667.9  425.08
  5888.9  424.74  5972.5  425.73  6063.3  427.24  6280.3  434.68  6346.1  434.78
#Mann= 9 ,-1 , 0
  4161.7     .05       0  4598.7     .12       0  4689.2      .1       0
  4985.7     .05       0  5008.7      .1       0  5123.8     .05       0
  5632.4    .035       0  5667.9     .07       0  5972.5     .05       0
Bank Sta=4985.7,5008.7
XS Rating Curve= 0 ,0
Exp/Cntr=0.3,0.1