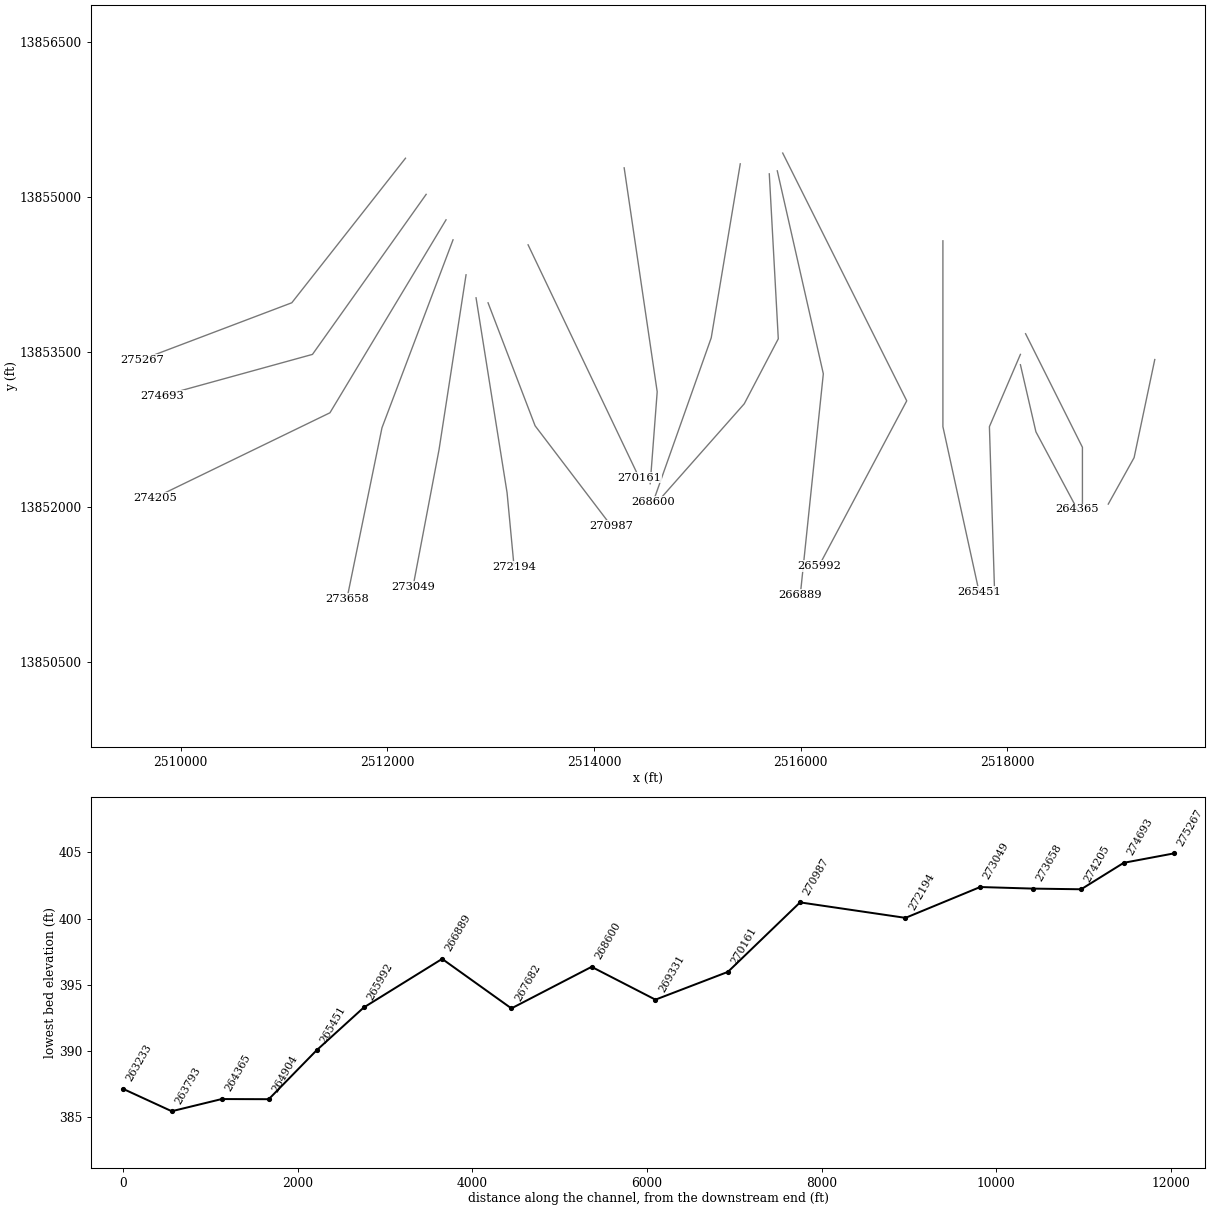
HEC-RAS study PEACH CREEK.prj: PEACH CREEK Base Level Engineering

--- PEACH CREEK.g01 (geometry) --- (continued)

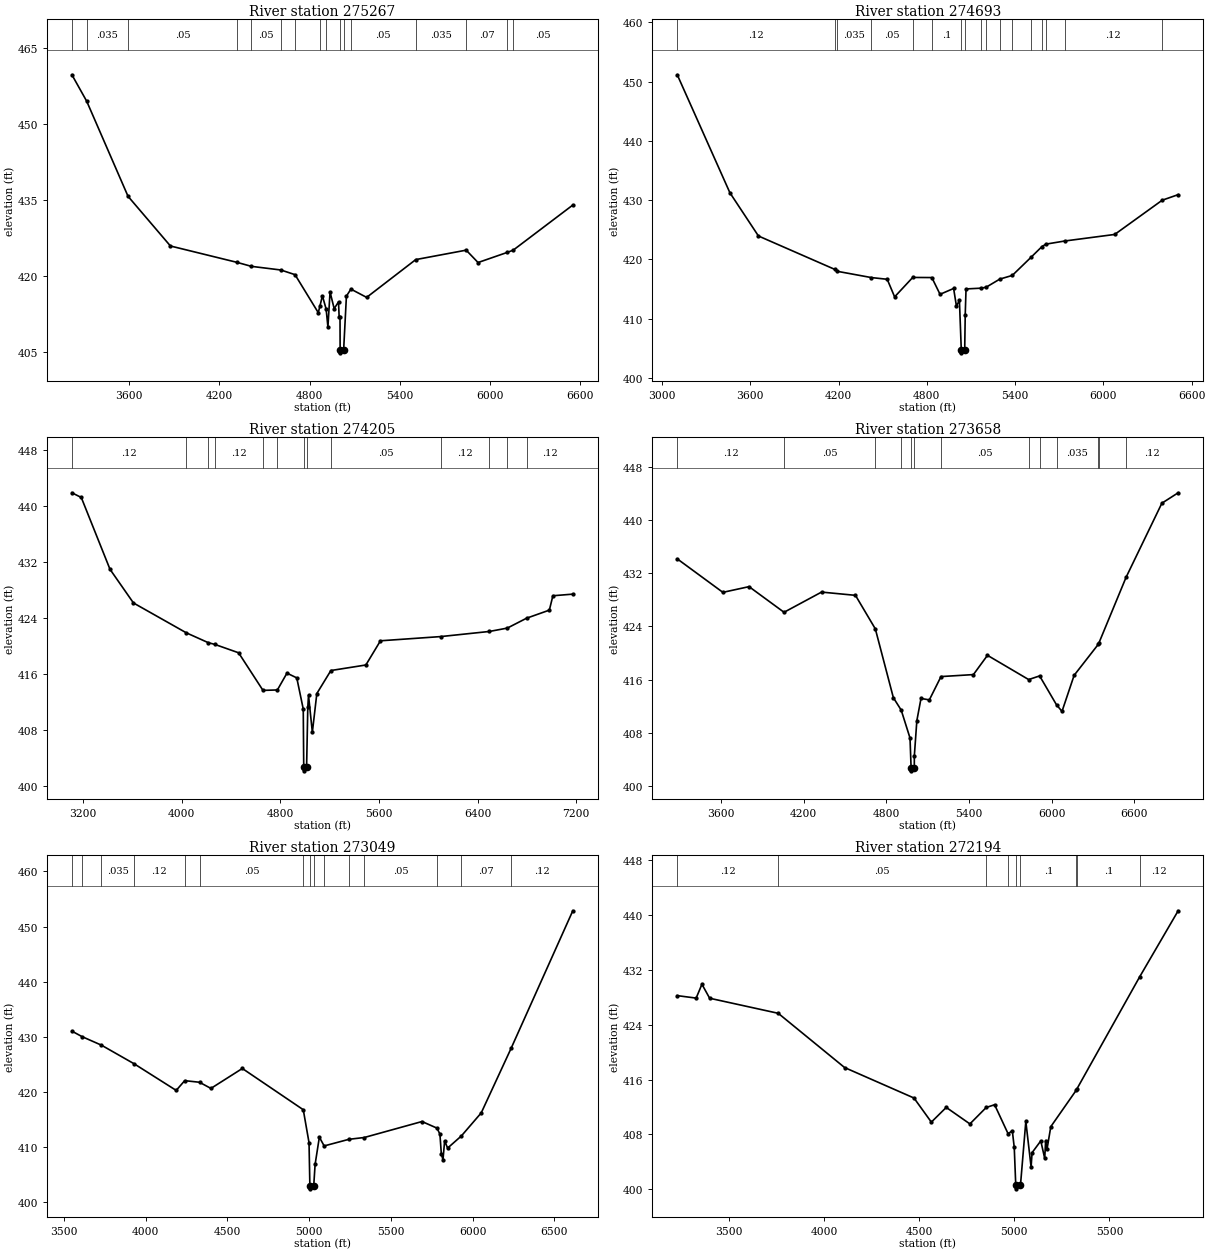
Type RM Length L Ch R = 1 ,275267  ,574,574,574
BEGIN DESCRIPTION:
PEACH CREEK9162
END DESCRIPTION:
XS GIS Cut Line= 3
      2512175.01     13855375.01        2511075.       13853975.
      2509624.97     13853424.99
#Sta/Elev= 30
  3219.8  459.73  3318.2  454.52  3593.2  435.77  3875.1  425.98  4315.9  422.77
  4413.2  421.97  4609.4  421.25  4703.7  420.33  4858.3  412.84  4869.2  414.11
  4885.8  416.17  4910.6  413.55  4922.5  410.02  4936.7  416.92  4964.1  413.63
    4993  414.97  4997.1  412.04  5002.9  412.04  5003.7  405.42  5004.2  404.92
  5026.9  405.42  5045.5   416.1  5075.4  417.48  5180.1  415.85  5506.7   423.3
    5842  425.16    5921  422.72  6116.4  424.73  6154.8  425.16  6551.1  434.05
#Mann= 16 ,-1 , 0
  3219.8     .05       0  3318.2    .035       0  3593.2     .05       0
  4315.9     .07       0  4413.2     .05       0  4609.4    .035       0
  4703.7      .1       0  4869.2     .12       0  4910.6      .1       0
  5003.7     .05       0  5026.9      .1       0  5075.4     .05       0
  5506.7    .035       0    5842     .07       0  6116.4     .12       0
  6154.8     .05       0
Bank Sta=5003.7,5026.9
XS Rating Curve= 0 ,0
Exp/Cntr=0.3,0.1

Type RM Length L Ch R = 1 ,274693  ,488,488,488
BEGIN DESCRIPTION:
PEACH CREEK9161
END DESCRIPTION:
XS GIS Cut Line= 3
      2512375.02     13855025.02        2511275.       13853475.
      2509825.04     13853075.01
#Sta/Elev= 30
  3103.6  451.16  3461.6  431.23  3655.4  423.94  4174.5   418.3  4190.6  417.98
  4422.7  416.92  4530.7  416.63  4581.1  413.66  4704.1  416.94  4834.1  416.92
  4889.9  414.09  4982.1  415.08  5001.2   412.1  5021.5  413.08  5034.2  404.71
  5034.7  404.21  5057.4  404.71    5061  410.64  5066.5     415  5169.5  415.13
  5203.1  415.29    5296  416.66  5380.8  417.28  5507.4  420.32  5581.6  422.13
  5608.8  422.56  5736.5  423.09    6077   424.2  6399.9  429.98  6508.4  430.92
#Mann= 17 ,-1 , 0
  3103.6     .12       0  4174.5     .05       0  4190.6    .035       0
  4422.7     .05       0  4704.1    .035       0  4834.1      .1       0
  5034.2     .05       0  5057.4      .1       0  5169.5     .05       0
  5203.1    .035       0    5296     .05       0  5380.8    .035       0
  5507.4     .07       0  5581.6    .035       0  5608.8     .07       0
  5736.5     .12       0  6399.9     .07       0
Bank Sta=5034.2,5057.4
XS Rating Curve= 0 ,0
Exp/Cntr=0.3,0.1

Type RM Length L Ch R = 1 ,274205  ,547,547,547
BEGIN DESCRIPTION:
B19980
END DESCRIPTION:
XS GIS Cut Line= 3
      2512567.32     13854778.31      2511444.04      13852909.4
      2509749.72     13852086.45
#Sta/Elev= 30
  3108.7  441.85  3184.8  441.18  3417.9  430.94  3608.3  426.14  4037.7  421.88
  4215.3  420.48  4267.6  420.24  4461.2  419.04  4659.1  413.68  4775.9  413.74
  4853.7  416.14  4933.3  415.46  4985.8  411.02  4989.7  402.71  4990.2  402.21
  5012.9  402.71  5022.7  411.25  5028.5  412.99  5059.6  407.71    5096  413.23
    5210  416.51  5493.8   417.3  5612.2  420.75  6101.1  421.35  6496.2  422.08
  6641.4  422.56  6797.9  423.97  6982.5  425.12  7011.3  427.17  7172.8   427.4
#Mann= 13 ,-1 , 0
  3108.7     .12       0  4037.7     .07       0  4215.3     .05       0
  4267.6     .12       0  4659.1     .05       0  4775.9      .1       0
  4989.7     .05       0  5012.9      .1       0    5210     .05       0
  6101.1     .12       0  6496.2    .035       0  6641.4     .07       0
  6797.9     .12       0
Bank Sta=4989.7,5012.9
XS Rating Curve= 0 ,0
Exp/Cntr=0.3,0.1

Type RM Length L Ch R = 1 ,273658  ,609,609,609
BEGIN DESCRIPTION:
B19979
END DESCRIPTION:
XS GIS Cut Line= 3
      2512635.11     13854584.66      2511947.58     13852764.15
      2511608.84     13851109.17
#Sta/Elev= 30
  3282.4  434.17  3613.5  429.13  3803.4  429.99  4057.3  426.13  4329.6  429.17
  4575.7  428.68  4719.9  423.63  4850.8  413.27  4907.7   411.4  4971.6   407.2
  4979.4  402.76  4979.9  402.26  5002.8  402.76    5003  404.51  5021.2  409.82
  5051.4  413.16  5111.8  412.94  5196.5  416.45  5431.7  416.75  5533.8  419.65
  5832.7     416  5912.2  416.55  6034.8   412.2  6074.7  411.21  6162.7  416.64
  6337.8   421.3    6344  421.58  6539.8   431.4  6799.5  442.55  6917.7  444.12
#Mann= 13 ,-1 , 0
  3282.4     .12       0  4057.3     .05       0  4719.9     .12       0
  4907.7      .1       0  4979.4     .05       0  5002.8      .1       0
  5196.5     .05       0  5832.7    .035       0  5912.2     .07       0
  6034.8    .035       0  6337.8     .12       0    6344    .035       0
  6539.8     .12       0
Bank Sta=4979.4,5002.8
XS Rating Curve= 0 ,0
Exp/Cntr=0.3,0.1

Type RM Length L Ch R = 1 ,273049  ,855,855,855
BEGIN DESCRIPTION:
B19978
END DESCRIPTION:
XS GIS Cut Line= 3
      2512760.99     13854245.75      2512499.54     13852551.12
      2512247.77     13851224.48
#Sta/Elev= 30
  3547.9  431.01  3610.2  430.01  3728.8  428.46  3928.8  425.08  4186.1  420.25
  4238.2  422.02  4328.7  421.73  4398.6  420.61  4590.8  424.23  4963.7  416.74
  4998.9  410.76  5004.1  402.88  5004.6  402.38  5027.5  402.88  5036.1  406.82
  5062.1  411.76  5091.4  410.17  5242.8  411.37  5336.9   411.7  5690.2   414.6
    5782   413.4  5799.8  412.31  5808.3  408.77  5818.5  407.64  5828.6  411.08
    5847  409.78    5931  411.98  6052.6  416.17  6235.1  427.87  6612.9  452.86
#Mann= 15 ,-1 , 0
  3547.9    .035       0  3610.2     .12       0  3728.8    .035       0
  3928.8     .12       0  4238.2    .035       0  4328.7     .05       0
  4963.7      .1       0  5004.1     .05       0  5027.5      .1       0
  5091.4     .05       0  5242.8    .035       0  5336.9     .05       0
    5782      .1       0    5931     .07       0  6235.1     .12       0
Bank Sta=5004.1,5027.5
XS Rating Curve= 0 ,0
Exp/Cntr=0.3,0.1

Type RM Length L Ch R = 1 ,272194  ,1207,1207,1207
BEGIN DESCRIPTION:
B19977
END DESCRIPTION:
XS GIS Cut Line= 3
      2512857.83     13854022.95      2513158.01     13852134.73
      2513225.71     13851419.06
#Sta/Elev= 30
  3229.9  428.26  3329.1   427.9  3359.5  429.92    3400  427.88  3760.2  425.68
  4108.8  417.76  4473.3  413.31  4564.4  409.79  4642.7  411.94  4766.9  409.53
  4852.6  411.93  4896.6  412.33  4967.2  408.11  4989.7  408.52  4999.8   406.1
  5007.8  400.55  5008.3  400.05  5032.4  400.55  5060.6   409.9  5088.3  403.23
  5093.4  405.33  5139.2  407.05  5159.8   404.5  5164.8   407.1  5171.7  405.81
  5191.8  409.13  5325.7  414.46  5329.7  414.68  5658.2  430.99  5860.7  440.65
#Mann= 9 ,-1 , 0
  3229.9     .12       0  3760.2     .05       0  4852.6     .07       0
  4967.2      .1       0  5007.8     .05       0  5032.4      .1       0
  5325.7     .07       0  5329.7      .1       0  5658.2     .12       0
Bank Sta=5007.8,5032.4
XS Rating Curve= 0 ,0
Exp/Cntr=0.3,0.1

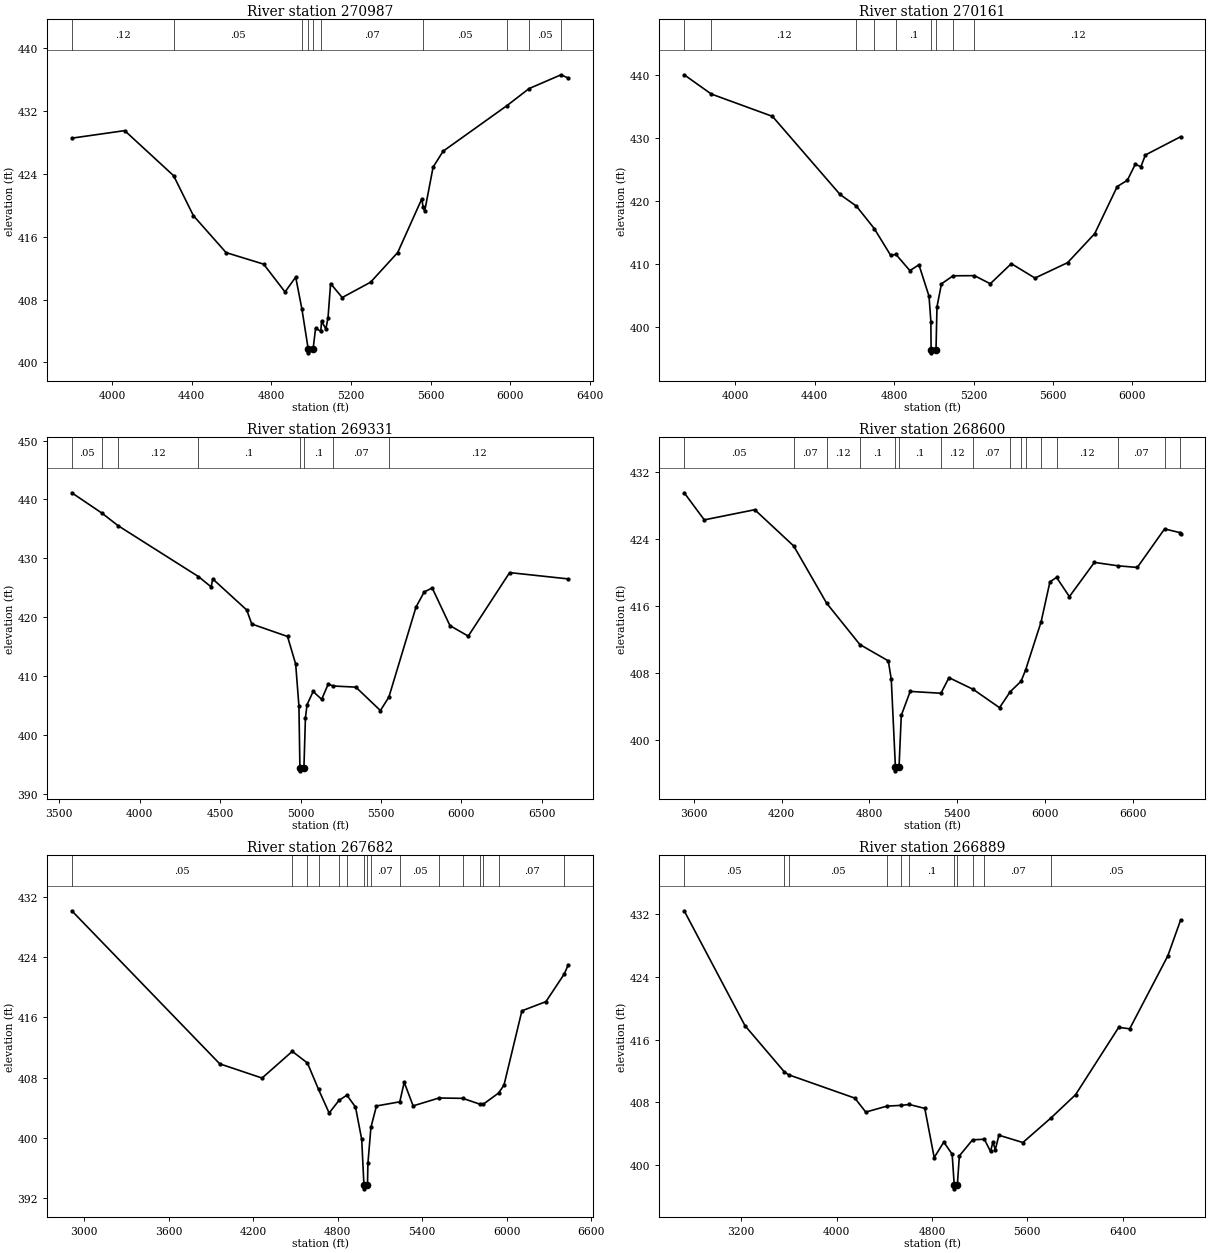
Type RM Length L Ch R = 1 ,270987  ,826,826,826
BEGIN DESCRIPTION:
B19976
END DESCRIPTION:
XS GIS Cut Line= 3
      2512974.02     13853974.59      2513429.15     13852783.52
      2514165.07      13851815.2
#Sta/Elev= 30
  3798.7  428.55  4064.1  429.51  4309.8  423.77  4408.8  418.69  4573.1  413.98
  4761.7  412.51  4868.8  408.97  4922.3  410.86  4953.6  406.79    4985  401.72
  4985.5  401.22  5009.8  401.72  5022.1  404.35  5048.3  403.97  5052.1  405.24
  5073.8  404.27  5084.5  405.67  5097.5  410.04  5155.7  408.26    5298  410.21
  5434.3  413.99    5555  420.81  5561.4  419.85  5569.5  419.24    5612  424.87
  5662.2  426.89  5982.4  432.69  6093.4  434.86  6254.1  436.62    6290   436.2
#Mann= 10 ,-1 , 0
  3798.7     .12       0  4309.8     .05       0  4953.6      .1       0
    4985     .05       0  5009.8      .1       0  5048.3     .07       0
  5561.4     .05       0  5982.4    .035       0  6093.4     .05       0
  6254.1     .12       0
Bank Sta=4985,5009.8
XS Rating Curve= 0 ,0
Exp/Cntr=0.3,0.1

Type RM Length L Ch R = 1 ,270161  ,830,830,830
BEGIN DESCRIPTION:
B19975
END DESCRIPTION:
XS GIS Cut Line= 2
      2513361.38     13854536.18      2514436.21     13852280.02
#Sta/Elev= 30
  3743.4  439.96  3879.6  436.92  4187.8  433.38  4528.2  421.02  4610.1  419.19
  4700.1  415.64  4783.4  411.37    4809  411.55  4879.8  408.98  4925.2   409.9
  4976.1  404.92  4985.3  400.92  4986.4  396.47  4986.9  395.97  5011.2  396.47
    5016  403.25  5038.7  406.89  5097.2  408.16  5204.8  408.18  5284.4   406.9
  5390.3  410.08  5509.4   407.8  5673.8  410.24    5810  414.82  5923.5  422.28
  5974.5  423.27  6014.4  425.81  6042.6  425.41  6065.3  427.27  6242.5  430.16
#Mann= 9 ,-1 , 0
  3743.4      .1       0  3879.6     .12       0  4610.1      .1       0
  4700.1     .12       0    4809      .1       0  4986.4     .05       0
  5011.2      .1       0  5097.2     .05       0  5204.8     .12       0
Bank Sta=4986.4,5011.2
XS Rating Curve= 0 ,0
Exp/Cntr=0.3,0.1

Type RM Length L Ch R = 1 ,269331  ,731,731,731
BEGIN DESCRIPTION:
B19974
END DESCRIPTION:
XS GIS Cut Line= 3
      2514290.98     13855281.82      2514610.53     13853112.76
      2514542.75     13852221.91
#Sta/Elev= 30
  3578.1  441.14  3766.5  437.66  3865.6  435.55  4365.7  426.89  4444.2  425.14
  4454.3  426.49  4665.3  421.22  4696.9  418.83  4919.2  416.71  4969.8  412.02
    4990  404.88  4996.2  394.37  4996.7  393.87  5021.1  394.37  5030.4  402.87
  5040.5  405.11  5078.4  407.36  5131.5  406.02  5171.9  408.61  5204.2  408.29
  5343.8   408.1  5496.5  404.12  5549.1   406.4  5717.8  421.71  5768.8  424.28
  5818.5  424.96  5928.8  418.56  6042.6  416.77  6299.8  427.57    6664   426.5
#Mann= 8 ,-1 , 0
  3578.1     .05       0  3766.5    .035       0  3865.6     .12       0
  4365.7      .1       0  4996.2     .05       0  5021.1      .1       0
  5204.2     .07       0  5549.1     .12       0
Bank Sta=4996.2,5021.1
XS Rating Curve= 0 ,0
Exp/Cntr=0.3,0.1

Type RM Length L Ch R = 1 ,268600  ,918,918,918
BEGIN DESCRIPTION:
B19973
END DESCRIPTION:
XS GIS Cut Line= 3
      2515414.25     13855320.56      2515133.44     13853635.66
      2514572.23     13852048.81
#Sta/Elev= 30
  3534.1   429.5  3671.5  426.27  4016.2  427.48  4282.3  423.16  4507.1  416.34
  4734.1  411.41  4928.6  409.46  4948.9  407.26    4977  396.85  4977.5  396.35
    5002  396.85  5017.3  402.96  5078.1  405.82  5288.1   405.6  5343.1  407.46
  5508.8  406.06  5688.4  403.88  5761.8  405.79  5835.7  407.03  5867.2  408.41
  5972.6  414.12  6032.7  418.88    6078  419.41  6165.7  417.12  6336.5   421.2
  6499.6  420.79  6629.7   420.6  6815.9  425.19  6921.3  424.75  6925.4  424.55
#Mann= 16 ,-1 , 0
  3534.1     .05       0  4282.3     .07       0  4507.1     .12       0
  4734.1      .1       0    4977     .05       0    5002      .1       0
  5288.1     .12       0  5508.8     .07       0  5761.8     .12       0
  5835.7     .07       0  5867.2     .12       0  5972.6     .07       0
    6078     .12       0  6499.6     .07       0  6815.9     .12       0
  6921.3    .035       0
Bank Sta=4977,5002
XS Rating Curve= 0 ,0
Exp/Cntr=0.3,0.1

Type RM Length L Ch R = 1 ,267682  ,793,793,793
BEGIN DESCRIPTION:
B19972
END DESCRIPTION:
XS GIS Cut Line= 4
      2515695.07     13855223.78      2515782.23     13853625.98
      2515452.99     13852996.55       2514649.6     13852086.69
#Sta/Elev= 30
  2912.2  430.18  3962.5  409.83    4263  407.94  4477.5  411.49  4585.1  409.94
  4663.8  406.44  4739.2  403.29  4810.5     405  4865.5  405.66  4926.3  404.08
  4970.4  399.79  4986.2  393.71  4986.7  393.21  5011.4  393.71  5014.5   396.6
  5035.8  401.38  5075.1  404.23  5240.8  404.78    5272  407.38  5335.6  404.24
  5519.2  405.29  5688.5  405.24  5807.1  404.48  5832.7  404.45  5941.7  405.94
  5980.6     407  6107.7  416.88  6278.4   418.1  6409.7  421.81  6436.5     423
#Mann= 16 ,-1 , 0
  2912.2     .05       0  4477.5     .07       0  4585.1     .05       0
  4663.8     .12       0  4810.5     .07       0  4865.5      .1       0
  4986.2     .05       0  5011.4      .1       0  5035.8     .07       0
  5240.8     .05       0  5519.2     .07       0  5688.5     .05       0
  5807.1     .07       0  5832.7     .12       0  5941.7     .07       0
  6409.7     .12       0
Bank Sta=4986.2,5011.4
XS Rating Curve= 0 ,0
Exp/Cntr=0.3,0.1

Type RM Length L Ch R = 1 ,266889  ,897,897,897
BEGIN DESCRIPTION:
B19971
END DESCRIPTION:
XS GIS Cut Line= 3
      2515772.55     13855252.76      2516217.98     13853287.06
      2515995.42     13851148.54
#Sta/Elev= 30
  2721.1  432.45  3231.5  417.78  3560.7   411.9  3597.9  411.51  4153.3  408.53
  4244.7  406.75  4422.3  407.51  4543.7  407.61  4610.5  407.72  4740.2  407.22
  4819.1  400.94  4899.6  402.92  4969.9  401.37    4987  397.45  4987.5  396.95
  5013.3  397.45  5030.3  401.16    5141  403.21  5240.2  403.28  5291.7  401.72
  5311.8  402.92  5331.9  401.96  5362.1   403.8  5563.1  402.86  5802.6  406.05
  6005.5  408.97  6367.5  417.57  6459.5  417.38  6779.7   426.7  6886.7  431.26
#Mann= 11 ,-1 , 0
  2721.1     .05       0  3560.7    .035       0  3597.9     .05       0
  4422.3     .07       0  4543.7     .12       0  4610.5      .1       0
    4987     .05       0  5013.3      .1       0    5141     .05       0
  5240.2     .07       0  5802.6     .05       0
Bank Sta=4987,5013.3
XS Rating Curve= 0 ,0
Exp/Cntr=0.3,0.1

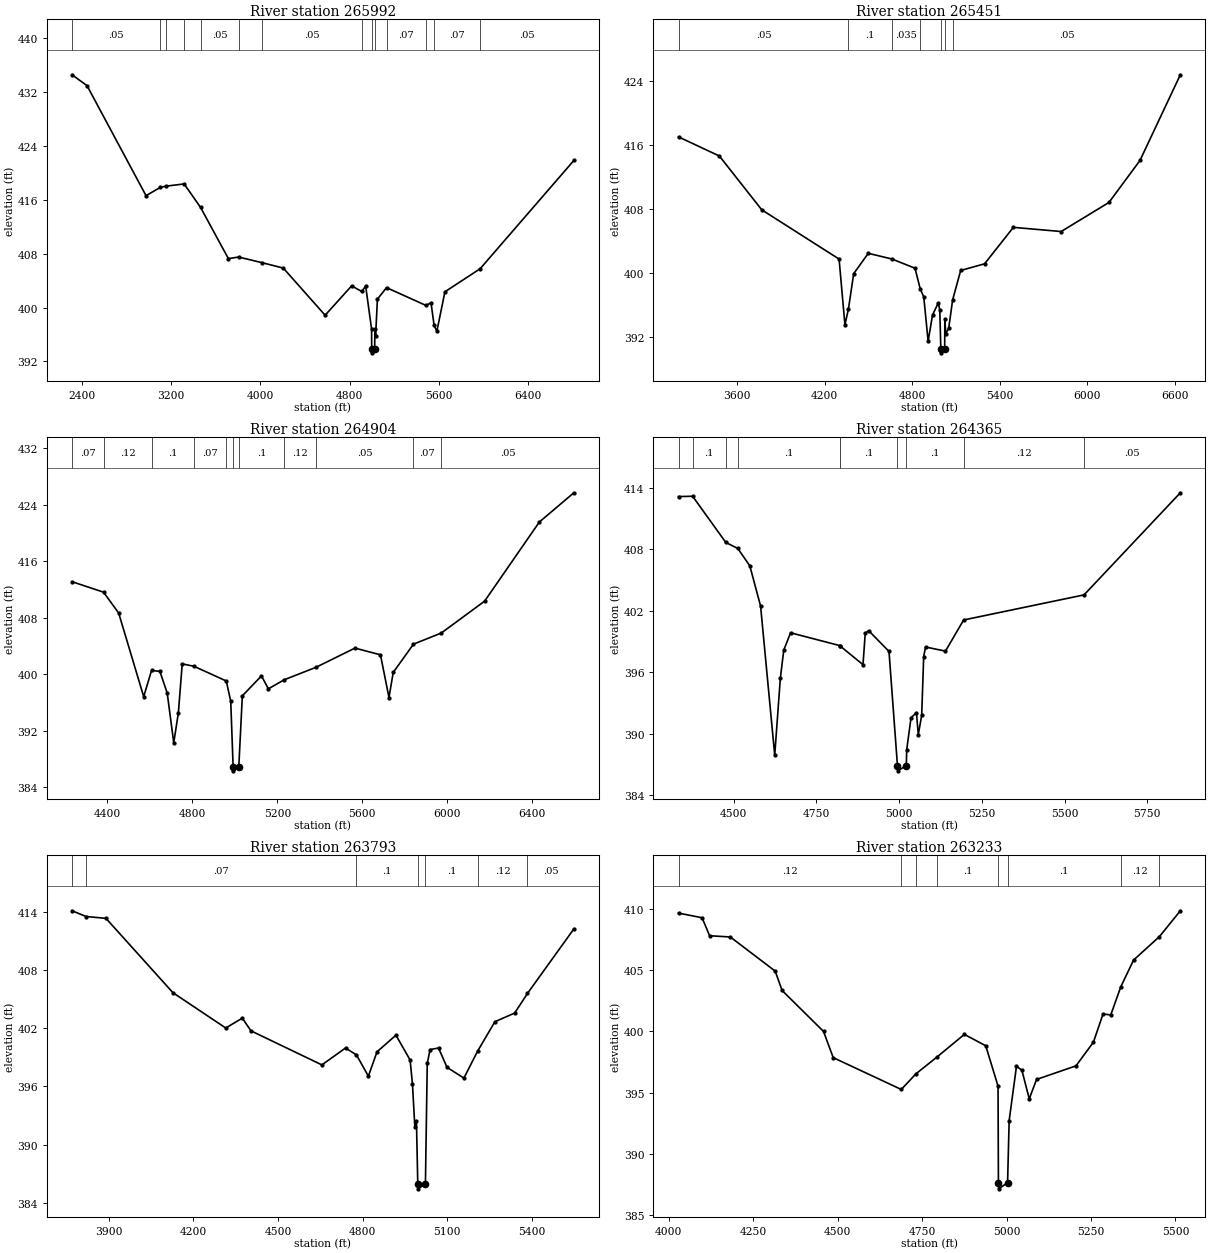
Type RM Length L Ch R = 1 ,265992  ,541,541,541
BEGIN DESCRIPTION:
PEACH CREEK9151
END DESCRIPTION:
XS GIS Cut Line= 3
      2515824.99     13855425.02        2517025.       13853025.
      2516174.99     13851424.97
#Sta/Elev= 30
    2313  434.55  2447.2  432.93  2975.5  416.61  3102.3  417.82  3150.2  418.01
    3317  418.35  3463.5  414.88  3713.4  407.26  3804.7   407.5  4012.5  406.67
  4205.3  405.86  4579.8  398.86  4817.4  403.22  4907.5  402.39  4943.2  403.19
  4996.3  396.77    4997  393.78  4997.5  393.28  5023.3  393.78  5026.4  396.83
  5032.1  395.81  5048.4  401.25  5129.9  402.96  5483.7  400.31  5528.5  400.72
    5556  397.37    5581  396.49  5653.1  402.34  5968.3  405.76  6808.1  421.83
#Mann= 14 ,-1 , 0
    2313     .05       0  3102.3    .035       0  3150.2     .05       0
    3317    .035       0  3463.5     .05       0  3804.7     .12       0
  4012.5     .05       0  4907.5     .07       0    4997     .05       0
  5023.3     .07       0  5129.9     .07       0  5483.7     .12       0
    5556     .07       0  5968.3     .05       0
Bank Sta=4997,5023.3
XS Rating Curve= 0 ,0
Exp/Cntr=0.3,0.1

Type RM Length L Ch R = 1 ,265451  ,547,547,547
BEGIN DESCRIPTION:
PEACH CREEK9150
END DESCRIPTION:
XS GIS Cut Line= 3
        2517375.     13854574.95        2517375.       13852775.
        2517725.     13851174.99
#Sta/Elev= 30
  3199.5  416.99  3479.5   414.6  3769.5  407.89  4299.5  401.74  4339.5  393.52
  4363.9  395.56  4399.5  399.92  4499.5  402.46  4661.5  401.75  4819.5   400.6
  4855.8  397.99  4879.5  397.03  4909.5  391.49  4939.5  394.75  4979.5  396.29
  4989.5  395.34  4996.4  390.54  4996.9  390.04  5022.9  390.54  5023.9   394.3
  5030.2  392.41  5050.6  393.12  5077.3  396.64  5132.5  400.32  5296.3  401.15
  5493.4   405.7  5820.9  405.18  6148.5  408.81  6360.9  414.05  6637.3  424.74
#Mann= 7 ,-1 , 0
  3199.5     .05       0  4363.9      .1       0  4661.5    .035       0
  4855.8     .07       0  4996.4     .05       0  5022.9     .07       0
  5077.3     .05       0
Bank Sta=4996.4,5022.9
XS Rating Curve= 0 ,0
Exp/Cntr=0.3,0.1

Type RM Length L Ch R = 1 ,264904  ,539,539,539
BEGIN DESCRIPTION:
PEACH CREEK9149
END DESCRIPTION:
XS GIS Cut Line= 3
      2518124.99     13853474.97        2517825.       13852775.
        2517875.     13851175.03
#Sta/Elev= 30
  4233.6   413.1  4381.8  411.62    4453  408.67  4570.8  396.84  4607.8  400.55
    4647  400.42  4681.5  397.35  4712.3  390.32    4734  394.55  4752.2  401.48
  4807.4  401.14  4959.6  399.06  4980.6  396.18  4991.9  386.85  4992.4  386.35
  5018.4  386.85  5035.2  396.96  5125.2  399.78  5157.7  397.95  5232.3  399.23
  5381.6  400.99  5565.4  403.71  5685.5  402.76  5725.5  396.72  5745.5  400.27
  5840.8  404.27  5971.7  405.84  6175.7  410.35  6433.3  421.54  6595.9  425.68
#Mann= 11 ,-1 , 0
  4233.6     .07       0  4381.8     .12       0  4607.8      .1       0
  4807.4     .07       0  4959.6      .1       0  4991.9     .05       0
  5018.4      .1       0  5232.3     .12       0  5381.6     .05       0
  5840.8     .07       0  5971.7     .05       0
Bank Sta=4991.9,5018.4
XS Rating Curve= 0 ,0
Exp/Cntr=0.3,0.1

Type RM Length L Ch R = 1 ,264365  ,572,572,572
BEGIN DESCRIPTION:
PEACH CREEK9148
END DESCRIPTION:
XS GIS Cut Line= 3
      2518124.99     13853375.05        2518275.       13852725.
      2518674.99     13851975.03
#Sta/Elev= 30
    4333  413.14  4375.6  413.17  4475.9  408.66  4512.3  408.07  4548.6  406.37
  4581.1  402.44  4623.8  387.89  4640.9  395.44  4651.2  398.15  4671.7  399.84
  4820.3  398.59  4820.4  398.58  4890.7  396.73  4897.5   399.8  4907.8  400.05
  4969.3  398.02  4994.9  386.86  4995.4  386.36  5021.7  386.86  5022.8  388.41
  5035.9  391.54  5052.2  392.04  5057.9   389.9  5068.1  391.77  5074.2  397.51
  5079.8  398.45    5140  398.05    5195  401.09    5559  403.54  5850.1  413.51
#Mann= 10 ,-1 , 0
    4333     .07       0  4375.6      .1       0  4475.9     .12       0
  4512.3      .1       0  4820.3     .07       0  4820.4      .1       0
  4994.9     .05       0  5021.7      .1       0    5195     .12       0
    5559     .05       0
Bank Sta=4994.9,5021.7
XS Rating Curve= 0 ,0
Exp/Cntr=0.3,0.1

Type RM Length L Ch R = 1 ,263793  ,560,560,560
BEGIN DESCRIPTION:
PEACH CREEK9147
END DESCRIPTION:
XS GIS Cut Line= 3
      2518174.99     13853675.02        2518725.       13852575.
        2518725.     13852024.96
#Sta/Elev= 30
  3769.7  414.09  3819.5   413.5  3889.9  413.31  4127.5  405.65  4314.8  402.01
  4373.5  403.03  4404.2  401.72  4655.8  398.21  4739.6  399.95  4778.5  399.24
  4820.7  397.05  4851.4  399.56  4918.5  401.27  4968.8  398.71  4977.2  396.21
  4985.6  391.77  4991.2  392.39    4996  385.94  4996.5  385.44  5023.1  385.94
  5029.6  398.36  5039.6  399.79  5069.6  399.95  5099.6  397.96  5159.6  396.85
  5208.2  399.63  5269.6  402.66  5339.6  403.55    5385  405.57  5549.6  412.22
#Mann= 7 ,-1 , 0
  3769.7     .12       0  3819.5     .07       0  4778.5      .1       0
    4996     .05       0  5023.1      .1       0  5208.2     .12       0
    5385     .05       0
Bank Sta=4996,5023.1
XS Rating Curve= 0 ,0
Exp/Cntr=0.3,0.1

Type RM Length L Ch R = 1 ,263233  ,559,559,559
BEGIN DESCRIPTION:
PEACH CREEK9146
END DESCRIPTION:
XS GIS Cut Line= 3
      2519425.01     13853425.05        2519225.       13852475.
      2518974.98     13852024.96
#Sta/Elev= 30
  4028.9  409.67  4098.6  409.29  4120.9  407.82  4182.2  407.72  4315.1  404.93
  4335.5  403.35  4458.2     400  4486.9  397.86  4688.4  395.26  4731.9  396.54
  4793.6   397.9  4875.2  399.76  4938.5  398.83  4974.9  395.53    4976  387.64
  4976.5  387.14  5003.1  387.64  5007.8  392.72  5029.5  397.16  5045.5  396.83
  5067.3   394.5    5089  396.08  5205.7  397.19  5257.2  399.12  5285.8  401.43
  5308.6  401.35  5338.4  403.65  5376.1  405.83  5452.7  407.75  5514.6  409.86
#Mann= 8 ,-1 , 0
  4028.9     .12       0  4688.4     .07       0  4731.9     .12       0
  4793.6      .1       0    4976     .05       0  5003.1      .1       0
  5338.4     .12       0  5452.7     .07       0
Bank Sta=4976,5003.1
XS Rating Curve= 0 ,0
Exp/Cntr=0.3,0.1