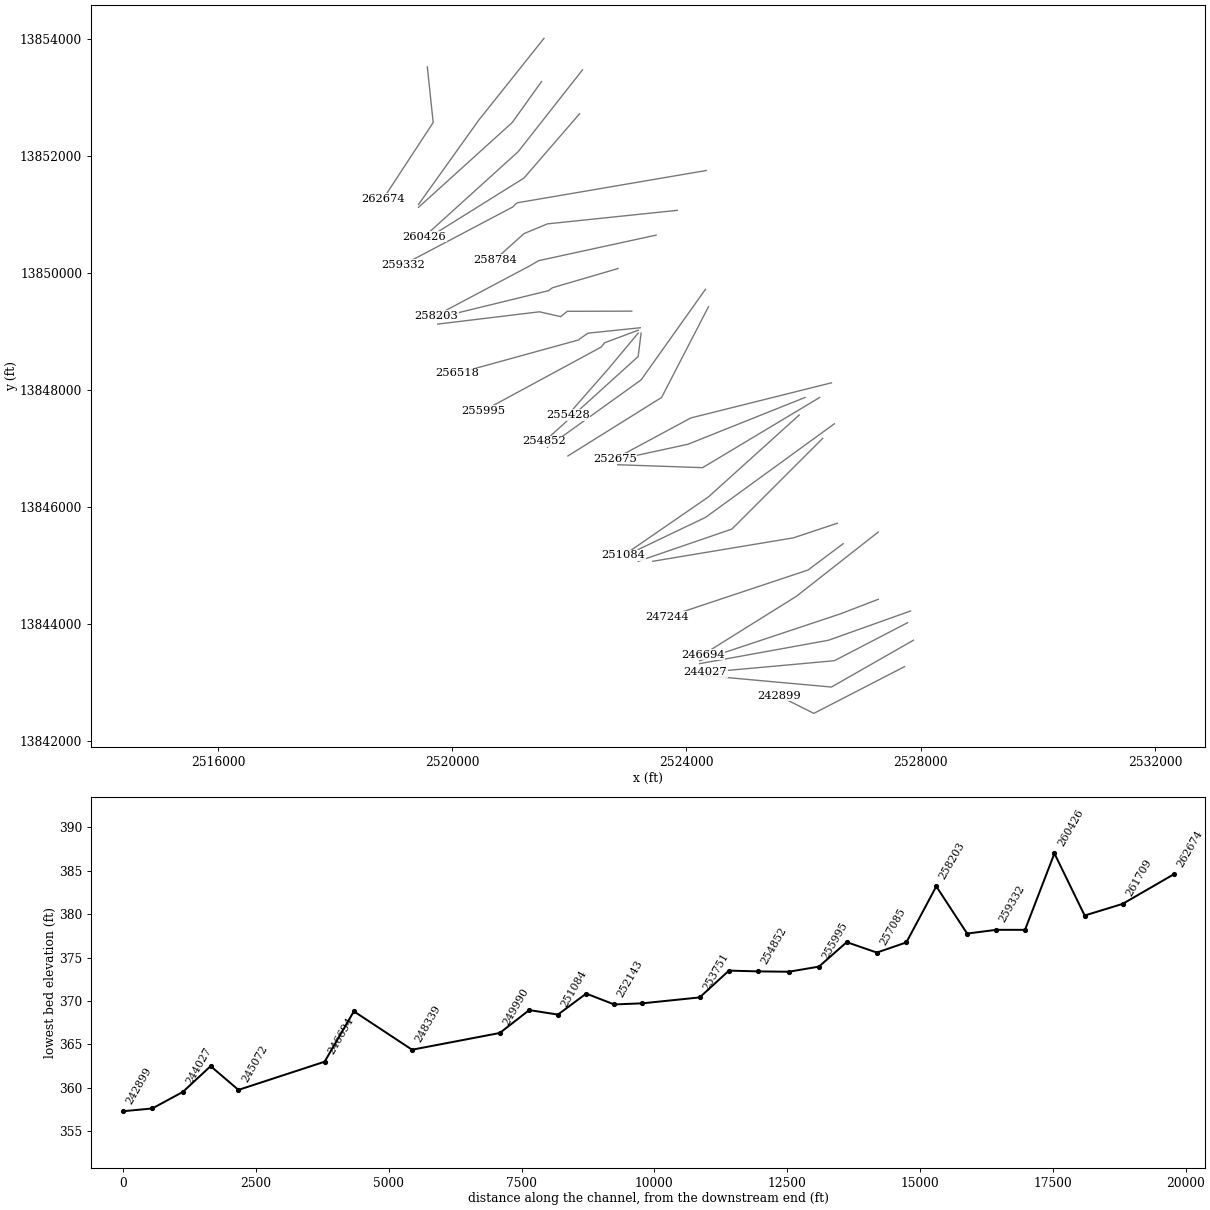
HEC-RAS study PEACH CREEK.prj: PEACH CREEK Base Level Engineering

--- PEACH CREEK.g01 (geometry) --- (continued)

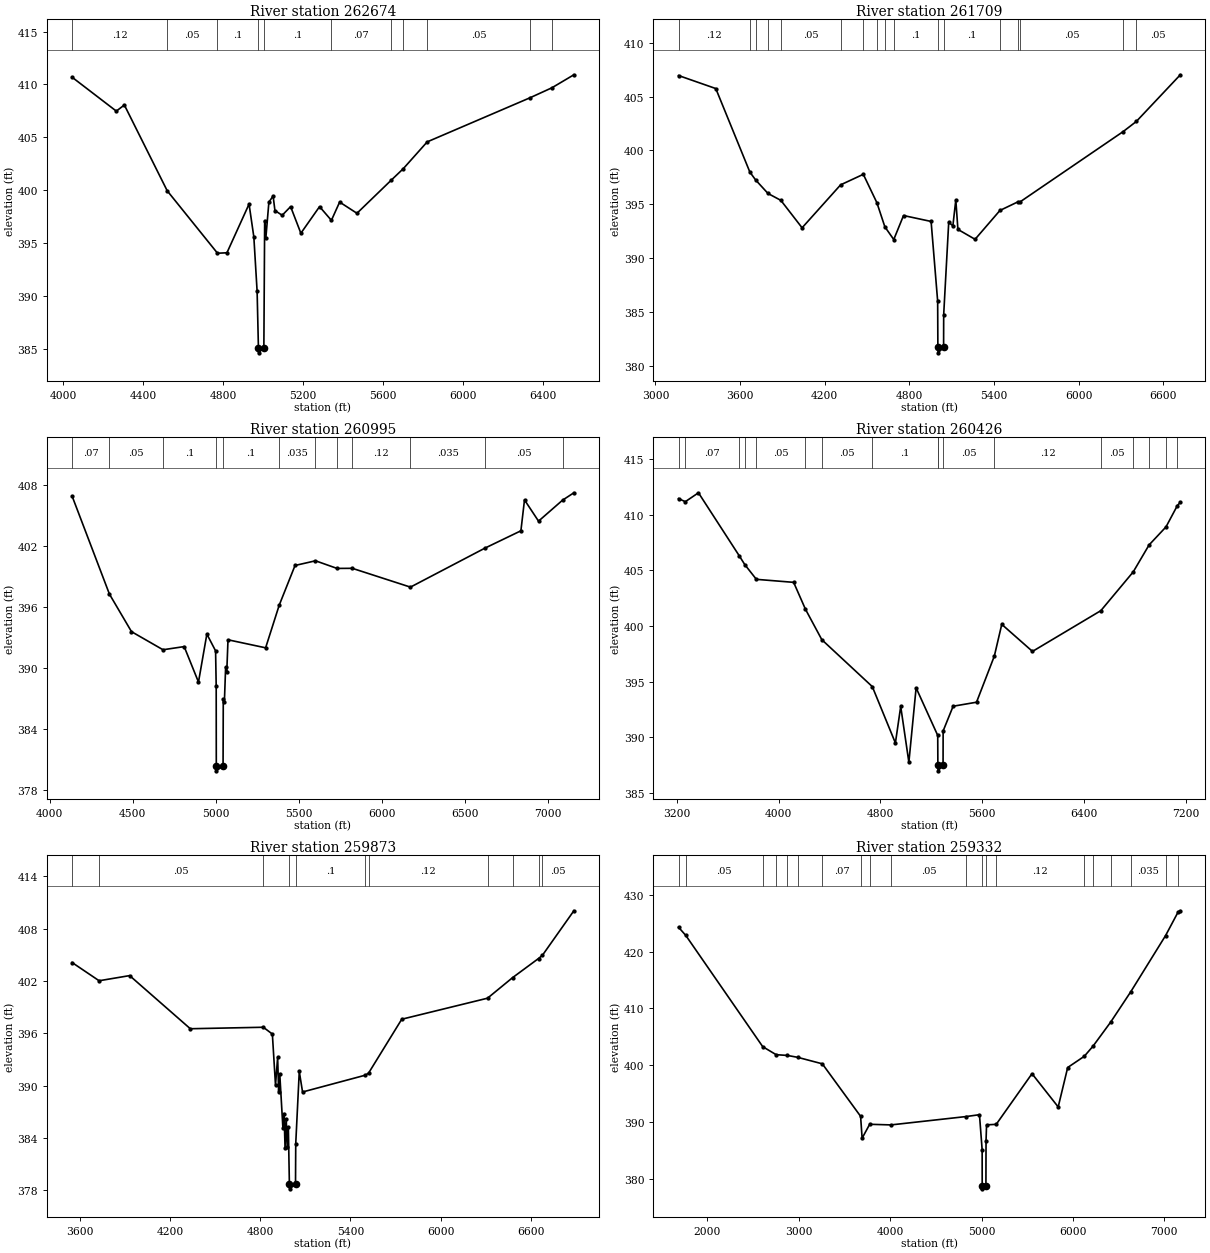
Type RM Length L Ch R = 1 ,262674  ,965,965,965
BEGIN DESCRIPTION:
PEACH CREEK9145
END DESCRIPTION:
XS GIS Cut Line= 3
        2519575.     13853524.98        2519675.       13852575.
      2518824.97     13851274.96
#Sta/Elev= 30
  4044.4  410.69  4265.6  407.48  4305.8  408.06    4520  399.94  4771.4  394.03
  4818.6  394.07  4929.2  398.68  4953.1  395.57  4969.5  390.41    4976   385.1
  4976.5   384.6  5003.2   385.1  5007.2  397.12  5013.2  395.49  5028.3  398.86
  5049.4  399.45  5058.5  398.07  5094.7  397.62  5136.9  398.44  5188.2  395.92
  5281.6  398.44  5340.8  397.14    5382  398.87  5468.6  397.81  5640.8  400.96
  5700.1  402.03  5819.8  404.57  6333.3  408.74  6443.3  409.69  6552.9  410.92
#Mann= 11 ,-1 , 0
  4044.4     .12       0    4520     .05       0  4771.4      .1       0
    4976     .05       0  5003.2      .1       0  5340.8     .07       0
  5640.8     .12       0  5700.1     .07       0  5819.8     .05       0
  6333.3    .035       0  6443.3     .05       0
Bank Sta=4976,5003.2
XS Rating Curve= 0 ,0
Exp/Cntr=0.3,0.1

Type RM Length L Ch R = 1 ,261709  ,714,714,714
BEGIN DESCRIPTION:
PEACH CREEK9144
END DESCRIPTION:
XS GIS Cut Line= 3
      2521567.08     13854013.46      2520453.38     13852615.21
      2519424.98     13851174.97
#Sta/Elev= 30
  3163.4  406.95  3427.5  405.74    3669  397.98  3709.6  397.25  3797.6  395.99
  3888.8  395.35  4039.3   392.8  4312.3  396.79  4473.3  397.77  4569.6  395.13
  4626.1  392.89  4689.2  391.71  4758.4  393.94  4953.9  393.39  5000.4  385.98
  5001.9  381.68  5002.9  381.18  5042.5  381.68  5043.1  384.72  5078.8  393.32
  5108.2  392.98  5129.1  395.39  5143.9  392.65  5265.6  391.73  5441.8  394.41
  5572.2  395.23  5582.7  395.19  6315.4  401.74  6408.6  402.68  6720.7  407.02
#Mann= 17 ,-1 , 0
  3163.4     .12       0    3669     .07       0  3709.6     .12       0
  3797.6    .035       0  3888.8     .05       0  4312.3     .07       0
  4473.3     .05       0  4569.6     .07       0  4626.1     .05       0
  4689.2      .1       0  5001.9     .05       0  5042.5      .1       0
  5441.8     .05       0  5572.2    .035       0  5582.7     .05       0
  6315.4     .07       0  6408.6     .05       0
Bank Sta=5001.9,5042.5
XS Rating Curve= 0 ,0
Exp/Cntr=0.3,0.1

Type RM Length L Ch R = 1 ,260995  ,569,569,569
BEGIN DESCRIPTION:
PEACH CREEK9143
END DESCRIPTION:
XS GIS Cut Line= 3
      2521524.99     13853274.98        2521025.       13852575.
      2519424.99     13851124.99
#Sta/Elev= 30
  4135.7  406.87  4360.6  397.22  4493.3  393.53  4682.9  391.75  4810.3  392.06
  4896.4  388.57  4946.8  393.29  4999.3  391.64    5003  388.15  5003.6  380.34
  5004.6  379.84  5044.3  380.34  5045.6   386.9  5052.3  386.62  5059.8  390.06
  5066.5  389.52    5074  392.73  5300.4  391.94  5382.3  396.14  5477.4  400.04
  5600.5   400.5  5730.2  399.75    5822  399.76  6171.8  397.91  6619.4  401.74
  6836.5  403.45  6858.2  406.49  6942.6   404.4    7087  406.46  7155.2  407.19
#Mann= 12 ,-1 , 0
  4135.7     .07       0  4360.6     .05       0  4682.9      .1       0
  5003.6     .05       0  5044.3      .1       0  5382.3    .035       0
  5600.5     .05       0  5730.2    .035       0    5822     .12       0
  6171.8    .035       0  6619.4     .05       0    7087    .035       0
Bank Sta=5003.6,5044.3
XS Rating Curve= 0 ,0
Exp/Cntr=0.3,0.1

Type RM Length L Ch R = 1 ,260426  ,553,553,553
BEGIN DESCRIPTION:
PEACH CREEK9142
END DESCRIPTION:
XS GIS Cut Line= 3
      2522225.02     13853475.03        2521125.       13852075.
      2519524.98     13850624.98
#Sta/Elev= 30
  3214.8  411.44    3268  411.16  3371.2  411.96  3690.5  406.32  3735.1  405.51
    3826  404.19  4118.6  403.92  4211.1  401.51    4340  398.77  4736.2  394.56
  4917.5   389.5  4959.2  392.78  5023.3  387.77  5080.1  394.45  5249.8  390.18
    5251   387.5    5252     387  5291.7   387.5  5292.3  390.58  5370.7   392.8
  5554.5  393.16  5694.3   397.3  5752.6  400.15  5993.8  397.72  6530.7  401.38
  6784.9  404.86  6909.4  407.28  7042.3   408.9  7130.8   410.8  7154.6  411.11
#Mann= 17 ,-1 , 0
  3214.8     .12       0    3268     .07       0  3690.5     .05       0
  3735.1     .07       0    3826     .05       0  4211.1     .07       0
    4340     .05       0  4736.2      .1       0  5249.8     .05       0
    5251     .05       0  5291.7     .05       0  5694.3     .12       0
  6530.7     .05       0  6784.9    .035       0  6909.4     .05       0
  7042.3    .035       0  7130.8     .05       0
Bank Sta=5251,5291.7
XS Rating Curve= 0 ,0
Exp/Cntr=0.3,0.1

Type RM Length L Ch R = 1 ,259873  ,541,541,541
BEGIN DESCRIPTION:
PEACH CREEK9141
END DESCRIPTION:
XS GIS Cut Line= 3
      2522175.02     13852725.02        2521225.       13851625.
      2519624.97     13850624.98
#Sta/Elev= 30
  3546.6  404.13  3726.6  402.04  3929.8  402.63  4333.7  396.54  4819.8  396.71
  4879.9  395.93  4900.8  390.08  4915.1  393.26  4921.7  389.32  4929.3  391.32
  4950.2  385.14  4957.8  386.82  4964.4  382.91  4972.1  386.22  4978.7  383.02
  4986.3  385.29  4993.3  378.69  4994.3  378.19    5034  378.69  5035.5  383.36
    5059  391.65  5080.9  389.29  5499.6  391.22  5520.9  391.47  5741.2  397.63
  6312.2  400.04  6478.5  402.39  6651.7  404.59  6678.1  404.97  6886.9  410.06
#Mann= 11 ,-1 , 0
  3546.6     .07       0  3726.6     .05       0  4819.8      .1       0
  4993.3     .05       0    5034      .1       0  5499.6     .05       0
  5520.9     .12       0  6312.2    .035       0  6478.5     .05       0
  6651.7    .035       0  6678.1     .05       0
Bank Sta=4993.3,5034
XS Rating Curve= 0 ,0
Exp/Cntr=0.3,0.1

Type RM Length L Ch R = 1 ,259332  ,548,548,548
BEGIN DESCRIPTION:
PEACH CREEK9140
END DESCRIPTION:
XS GIS Cut Line= 5
      2524336.13       13851754.      2521115.37     13851203.26
        2521075.       13851175.      2521035.52     13851131.44
      2519162.46     13850142.86
#Sta/Elev= 30
  1683.1  424.31  1762.7  422.86    2605  403.25  2751.9  401.84  2873.5  401.71
  2986.2  401.38  3257.2  400.23  3676.2  390.98    3693  387.12  3775.7  389.57
  4008.7  389.46  4829.3  390.93  4977.6  391.26    5007  385.08  5007.6  378.69
  5008.6  378.19  5048.3  378.69  5049.6  386.65  5055.3  389.47  5160.9  389.56
  5552.8  398.49  5839.5  392.63  5943.5  399.58  6124.7  401.55  6218.8   403.3
  6415.2  407.61  6634.7  412.95  7015.2  422.84  7150.2  426.93  7176.6  427.21
#Mann= 20 ,-1 , 0
  1683.1    .035       0  1762.7     .05       0    2605    .035       0
  2751.9    .035       0  2873.5     .05       0  2986.2    .035       0
  3257.2     .07       0  3676.2     .12       0  3775.7      .1       0
  4008.7     .05       0  4829.3      .1       0  5007.6     .05       0
  5048.3      .1       0  5160.9     .12       0  6124.7     .12       0
  6218.8    .035       0  6415.2     .12       0  6634.7    .035       0
  7015.2     .12       0  7150.2     .07       0
Bank Sta=5007.6,5048.3
XS Rating Curve= 0 ,0
Exp/Cntr=0.3,0.1

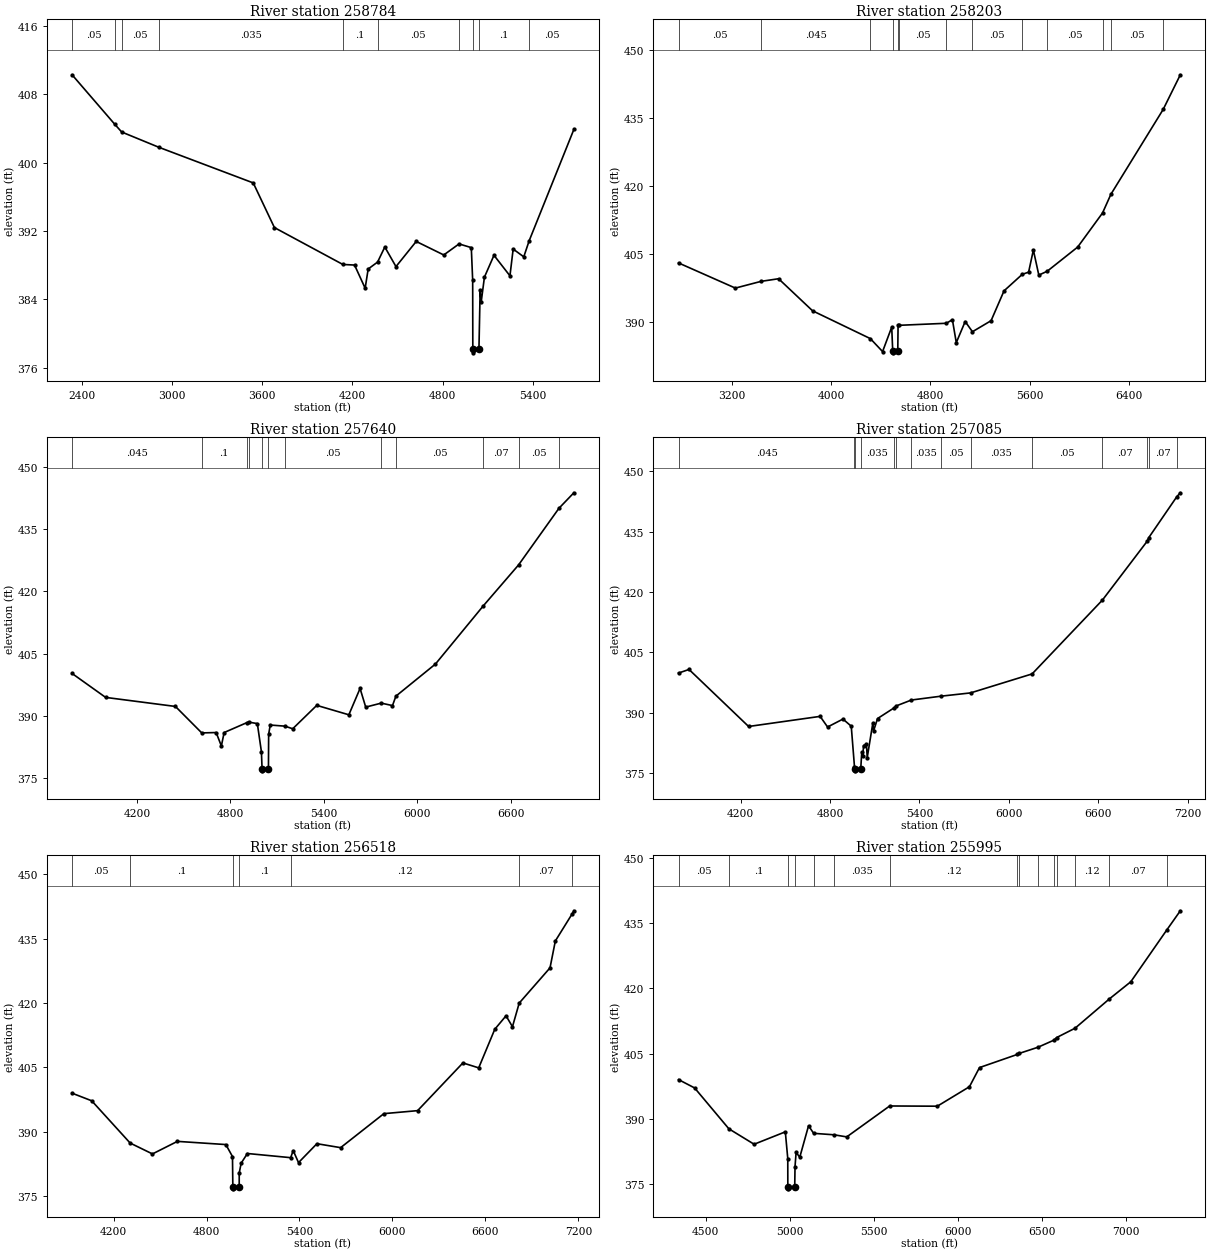
Type RM Length L Ch R = 1 ,258784  ,581,581,581
BEGIN DESCRIPTION:
PEACH CREEK9139
END DESCRIPTION:
XS GIS Cut Line= 4
      2523843.05     13851073.44      2521625.83     13850842.01
        2521225.       13850675.      2520724.98     13850224.98
#Sta/Elev= 30
  2336.6  410.26  2621.7  404.45  2666.6  403.57  2913.1  401.79  3541.2  397.62
  3681.9   392.4  4136.9  388.09  4214.8  388.02  4285.2  385.31  4305.3  387.56
  4367.9  388.37  4415.9  390.13  4490.1  387.84  4624.7  390.78  4807.8   389.2
  4909.5  390.49  4990.9  390.06  5000.1  386.24    5001  378.26    5002  377.76
  5041.8  378.26  5049.8  385.11  5056.5  383.67  5078.2  386.61  5141.7  389.16
  5247.9  386.76  5269.2  389.89  5339.8  388.98  5375.6  390.86  5672.8  403.87
#Mann= 10 ,-1 , 0
  2336.6     .05       0  2621.7     .07       0  2666.6     .05       0
  2913.1    .035       0  4136.9      .1       0  4367.9     .05       0
  4909.5      .1       0    5001     .05       0  5041.8      .1       0
  5375.6     .05       0
Bank Sta=5001,5041.8
XS Rating Curve= 0 ,0
Exp/Cntr=0.3,0.1

Type RM Length L Ch R = 1 ,258203  ,563,563,563
BEGIN DESCRIPTION:
PEACH CREEK9138
END DESCRIPTION:
XS GIS Cut Line= 4
      2523481.98     13850649.83      2521477.08     13850213.72
        2521325.       13850125.      2519725.01     13849275.01
#Sta/Elev= 30
  2772.1     403  3229.5  397.46  3437.6  398.95  3577.5  399.52    3851  392.46
  4316.4  386.33  4414.7  383.48  4488.3  388.86  4496.2   383.7  4497.2   383.2
  4537.1   383.7  4539.5  389.26  4545.2  389.26  4927.9  389.71  4976.8   390.5
  5008.1  385.45  5079.7   390.1  5138.2  387.85  5288.2  390.28  5392.4  396.85
  5539.3  400.49  5590.3  400.97  5628.6  405.84  5672.5  400.32    5740  401.17
  5985.1  406.49  6185.4     414    6253  418.13  6673.6  436.81  6811.7  444.44
#Mann= 13 ,-1 , 0
  2772.1     .05       0  3437.6    .045       0  4316.4      .1       0
  4496.2     .05       0  4537.1      .1       0  4545.2     .05       0
  4927.9      .1       0  5138.2     .05       0  5539.3    .035       0
    5740     .05       0  6185.4     .07       0    6253     .05       0
  6673.6     .07       0
Bank Sta=4496.2,4537.1
XS Rating Curve= 0 ,0
Exp/Cntr=0.3,0.1

Type RM Length L Ch R = 1 ,257640  ,555,555,555
BEGIN DESCRIPTION:
PEACH CREEK9137
END DESCRIPTION:
XS GIS Cut Line= 5
      2522831.67     13850078.69      2521714.98     13849751.66
        2521675.       13849725.        2521652.       13849702.
      2519731.99     13849233.17
#Sta/Elev= 30
  3784.1  400.21  3999.5  394.44  4447.5  392.26  4616.5  385.88  4708.9  385.97
  4742.3  382.74  4760.1  385.97  4905.5  388.35  4916.7  388.49  4973.2  388.13
  4999.3  381.36  5003.6  377.24  5004.6  376.74  5044.5  377.24  5045.8  385.58
  5056.1  387.78  5150.9  387.51  5200.2  386.88  5354.6  392.52  5560.5  390.25
  5632.5   396.6  5668.8   392.1  5768.4  393.06  5840.6  392.47  5862.7  394.75
  6116.3  402.48  6424.4  416.55  6649.6  426.36  6909.2  440.03  7004.7  443.76
#Mann= 12 ,-1 , 0
  3784.1    .045       0  4616.5      .1       0  4905.5     .05       0
  4916.7      .1       0  5003.6     .05       0  5044.5      .1       0
  5150.9     .05       0  5768.4    .035       0  5862.7     .05       0
  6424.4     .07       0  6649.6     .05       0  6909.2     .07       0
Bank Sta=5003.6,5044.5
XS Rating Curve= 0 ,0
Exp/Cntr=0.3,0.1

Type RM Length L Ch R = 1 ,257085  ,567,567,567
BEGIN DESCRIPTION:
PEACH CREEK9136
END DESCRIPTION:
XS GIS Cut Line= 6
      2523065.34     13849350.25      2521965.23     13849347.77
        2521875.       13849275.      2521853.76     13849255.75
      2521489.29     13849339.15      2519752.74     13849128.99
#Sta/Elev= 30
  3783.5  399.86  3853.8  400.76  4253.8  386.59  4733.8   389.1  4783.8  386.46
    4887  388.43  4942.7  386.66  4964.3  376.61  4965.5  376.07  4966.5  375.57
  5006.4  376.07  5013.4   380.3  5020.8  379.28    5025  381.86  5044.8  382.19
  5049.9  378.86  5087.7  387.48  5092.8  385.52  5119.2  388.56  5228.8  391.18
  5244.5   391.7  5346.2  393.16  5545.6  394.12  5743.4  394.93  6156.6  399.65
  6628.8  418.01  6929.6  432.65  6939.5  433.51    7128  443.69  7151.3  444.65
#Mann= 14 ,-1 , 0
  3783.5    .045       0  4964.3    .035       0  4965.5    .035       0
  5006.4    .035       0  5228.8      .1       0  5244.5     .07       0
  5346.2    .035       0  5545.6     .05       0  5743.4    .035       0
  6156.6     .05       0  6628.8     .07       0  6929.6     .05       0
  6939.5     .07       0    7128     .05       0
Bank Sta=4965.5,5006.4
XS Rating Curve= 0 ,0
Exp/Cntr=0.3,0.1

Type RM Length L Ch R = 1 ,256518  ,523,523,523
BEGIN DESCRIPTION:
PEACH CREEK9135
END DESCRIPTION:
XS GIS Cut Line= 5
      2523211.08     13849066.49      2522318.98     13848973.99
        2522175.       13848875.      2522162.58     13848859.48
      2520093.03     13848288.71
#Sta/Elev= 30
  3932.3  399.02  4059.1  397.25  4307.1  387.42  4451.1  384.89    4612  387.81
  4924.7  387.07  4967.5  384.28  4969.8  377.27  4970.8  376.77  5010.9  377.27
  5011.1  380.45  5023.4  382.73  5063.7  384.99    5343  384.02  5359.4  385.67
  5393.7  382.87  5512.4  387.27  5665.4  386.35  5944.5  394.26  6162.3  394.96
  6454.5  406.06  6556.5  404.91  6660.3  413.89  6732.9  417.02  6774.4  414.48
  6817.9  419.98  7016.7  428.17  7051.1  434.43  7158.7  440.68  7170.6  441.45
#Mann= 7 ,-1 , 0
  3932.3     .05       0  4307.1      .1       0  4969.8     .05       0
  5010.9      .1       0    5343     .12       0  6817.9     .07       0
  7158.7    .035       0
Bank Sta=4969.8,5010.9
XS Rating Curve= 0 ,0
Exp/Cntr=0.3,0.1

Type RM Length L Ch R = 1 ,255995  ,567,567,567
BEGIN DESCRIPTION:
PEACH CREEK9134
END DESCRIPTION:
XS GIS Cut Line= 5
      2523176.42     13849024.84      2522600.58     13848809.11
        2522575.       13848775.      2522543.65     13848736.41
       2520538.9     13847650.58
#Sta/Elev= 30
  4338.1  399.04  4433.9  397.12  4637.7  387.74  4788.1  384.19  4973.8  387.04
  4988.4   380.9  4988.7  374.45  4989.7  373.95  5029.8  374.45  5031.6  379.08
    5038   382.3  5059.9  381.22  5112.1  388.44  5142.2   386.7    5264  386.36
  5339.5  385.88    5595  392.98  5878.7  392.93  6069.9   397.4  6129.8   401.8
  6355.7  404.83  6367.6  405.07  6477.9  406.47  6573.6  408.11  6588.3  408.68
  6698.7  410.84    6903  417.57  7030.5  421.51    7243  433.31  7325.3  437.81
#Mann= 15 ,-1 , 0
  4338.1     .05       0  4637.7      .1       0  4988.7     .05       0
  5029.8      .1       0  5142.2     .12       0    5264    .035       0
    5595     .12       0  6355.7    .035       0  6367.6     .07       0
  6477.9    .035       0  6573.6     .12       0  6588.3    .035       0
  6698.7     .12       0    6903     .07       0    7243     .12       0
Bank Sta=4988.7,5029.8
XS Rating Curve= 0 ,0
Exp/Cntr=0.3,0.1

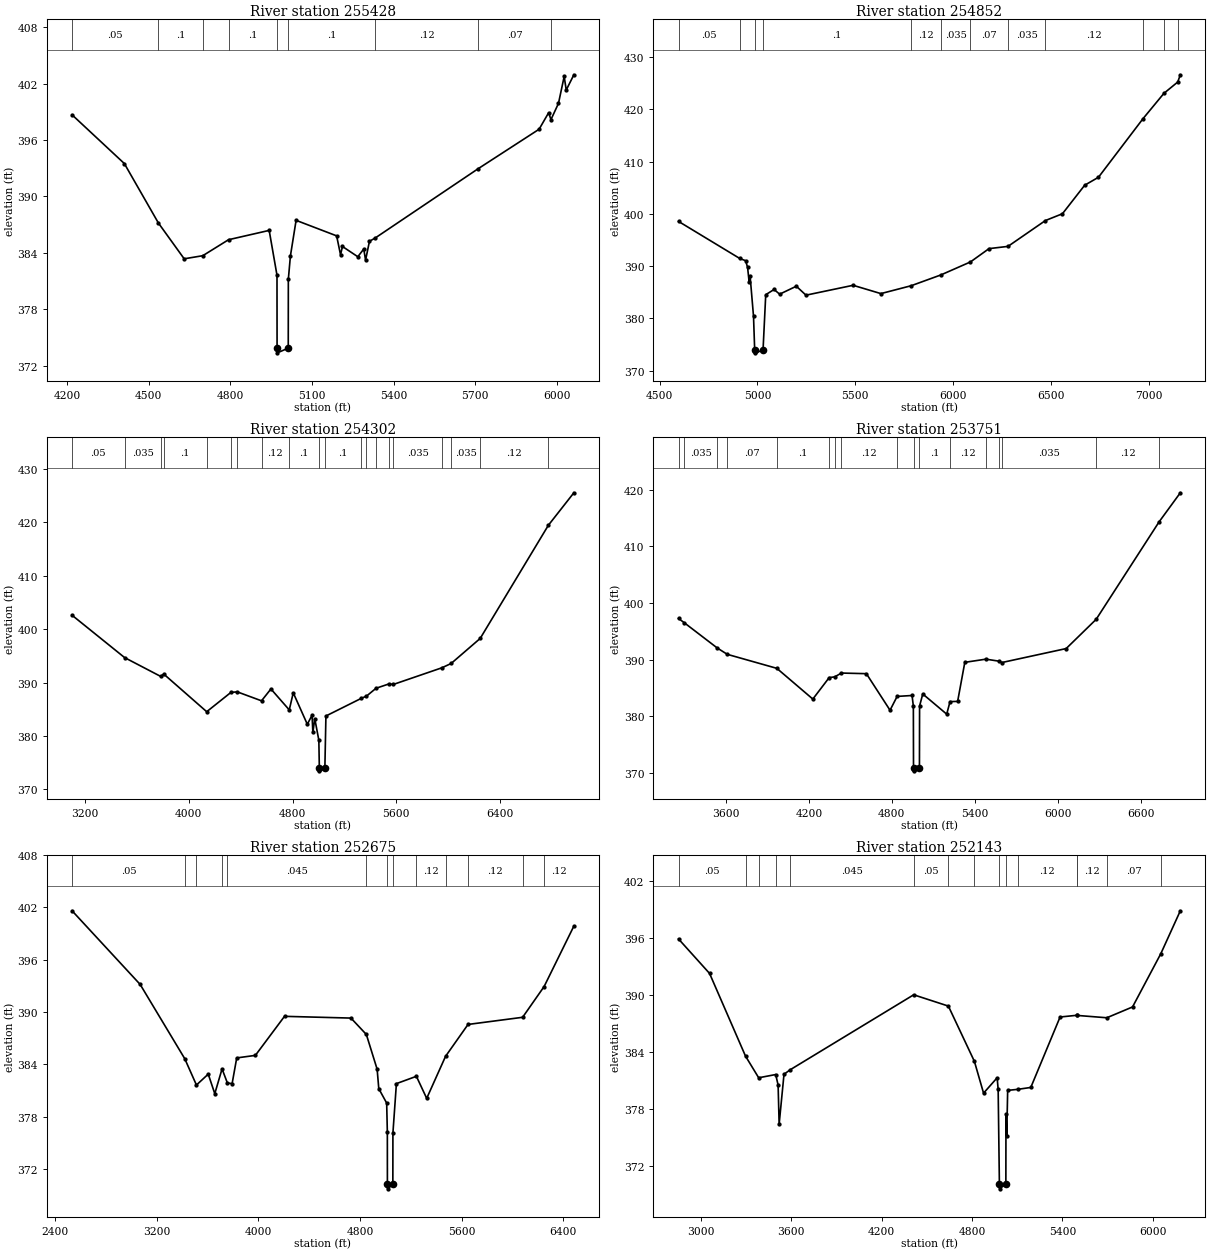
Type RM Length L Ch R = 1 ,255428  ,576,576,576
BEGIN DESCRIPTION:
PEACH CREEK9133
END DESCRIPTION:
XS GIS Cut Line= 3
      2523175.03     13848975.04        2522675.       13848375.
      2521974.99     13847574.99
#Sta/Elev= 30
  4218.7  398.67  4410.8  393.49  4536.1  387.16  4630.7  383.36  4699.1  383.69
  4793.7  385.39  4943.1  386.38  4971.8  381.61  4972.1  373.86  4973.1  373.36
  5013.2  373.86  5013.5  381.18  5021.1  383.66    5042  387.45    5191   385.8
  5205.3  383.79  5212.4  384.67  5268.8  383.58  5290.7   384.4  5297.3  383.22
  5311.6  385.22  5333.6  385.59  5710.5  392.93  5935.1  397.14  5970.2   398.9
  5978.6  398.16  6006.3  399.89  6027.2  402.75  6034.8  401.31  6062.8  402.93
#Mann= 9 ,-1 , 0
  4218.7     .05       0  4536.1      .1       0  4699.1     .05       0
  4793.7      .1       0  4972.1     .05       0  5013.2      .1       0
  5333.6     .12       0  5710.5     .07       0  5978.6     .12       0
Bank Sta=4972.1,5013.2
XS Rating Curve= 0 ,0
Exp/Cntr=0.3,0.1

Type RM Length L Ch R = 1 ,254852  ,550,550,550
BEGIN DESCRIPTION:
PEACH CREEK9132
END DESCRIPTION:
XS GIS Cut Line= 3
        2523225.     13848974.98        2523175.       13848575.
      2521574.98     13847124.98
#Sta/Elev= 30
    4597  398.56  4909.4  391.47  4939.6  391.04  4949.7  389.74  4957.3  387.03
  4962.3  388.17  4979.9  380.39  4985.9   373.9  4986.9   373.4  5028.5   373.9
  5042.3  384.53  5084.9  385.53  5113.3  384.63  5198.5  386.15  5247.8  384.44
  5488.4  386.33  5630.3  384.74  5785.2  386.25  5936.4  388.31  6087.6   390.8
  6182.5  393.35  6279.4  393.78  6470.7  398.73  6557.5  400.03  6671.1  405.49
  6741.4  407.01  6968.7  418.22  7075.7  423.08  7146.1  425.24  7159.4  426.63
#Mann= 12 ,-1 , 0
    4597     .05       0  4909.4      .1       0  4985.9     .05       0
  5028.5      .1       0  5785.2     .12       0  5936.4    .035       0
  6087.6     .07       0  6279.4    .035       0  6470.7     .12       0
  6968.7     .05       0  7075.7     .12       0  7146.1     .05       0
Bank Sta=4985.9,5028.5
XS Rating Curve= 0 ,0
Exp/Cntr=0.3,0.1

Type RM Length L Ch R = 1 ,254302  ,551,551,551
BEGIN DESCRIPTION:
PEACH CREEK9131
END DESCRIPTION:
XS GIS Cut Line= 3
      2524325.01     13849725.01        2523225.       13848175.
      2521624.98     13847024.99
#Sta/Elev= 30
  3099.2  402.62  3504.7  394.69  3782.8  391.17  3806.5  391.61  4137.9  384.56
  4325.5  388.19  4374.3  388.27  4560.7   386.6  4633.3  388.82  4774.7   384.9
  4805.5   388.1    4914  382.21  4950.7  383.91  4956.8  380.67  4971.6  383.25
    5003  379.21  5006.8  373.99  5007.8  373.49  5049.4  373.99  5057.6  383.76
  5330.2  387.06  5370.5  387.48  5444.2  388.95    5546  389.78    5577  389.66
  5951.8  392.78  6023.6  393.59  6247.7  398.28    6774  419.48  6970.3  425.55
#Mann= 20 ,-1 , 0
  3099.2     .05       0  3504.7    .035       0  3782.8     .07       0
  3806.5      .1       0  4137.9     .12       0  4325.5     .05       0
  4374.3    .035       0  4560.7     .12       0  4774.7      .1       0
  5006.8     .05       0  5049.4      .1       0  5330.2     .12       0
  5370.5     .07       0  5444.2     .12       0    5546     .07       0
    5577    .035       0  5951.8     .07       0  6023.6    .035       0
  6247.7     .12       0    6774     .07       0
Bank Sta=5006.8,5049.4
XS Rating Curve= 0 ,0
Exp/Cntr=0.3,0.1

Type RM Length L Ch R = 1 ,253751  ,1076,1076,1076
BEGIN DESCRIPTION:
PEACH CREEK9130
END DESCRIPTION:
XS GIS Cut Line= 3
      2524374.99     13849424.97        2523575.       13847875.
      2521975.04     13846875.02
#Sta/Elev= 30
  3256.3  397.28  3297.5  396.53  3535.9  392.08  3609.2  390.95  3967.7  388.48
  4228.1  383.06  4346.4  386.85  4386.8  386.98  4434.7  387.65  4615.6  387.54
  4786.7  381.09  4838.1  383.53    4946  383.69  4955.5  381.82  4956.6   370.9
  4957.6   370.4  4999.5   370.9  5000.5  381.83  5023.5  383.96  5196.9   380.4
  5220.8  382.61  5275.9  382.65  5327.8  389.54  5480.4   390.1  5576.6  389.74
    5597  389.51  6061.3  391.97  6278.4  397.13  6733.6  414.32  6887.3  419.45
#Mann= 17 ,-1 , 0
  3256.3     .05       0  3297.5    .035       0  3535.9     .05       0
  3609.2     .07       0  3967.7      .1       0  4346.4     .07       0
  4386.8      .1       0  4434.7     .12       0  4838.1      .1       0
  4956.6     .05       0  4999.5      .1       0  5220.8     .12       0
  5480.4    .035       0  5576.6     .12       0    5597    .035       0
  6278.4     .12       0  6733.6     .07       0
Bank Sta=4956.6,4999.5
XS Rating Curve= 0 ,0
Exp/Cntr=0.3,0.1

Type RM Length L Ch R = 1 ,252675  ,532,532,532
BEGIN DESCRIPTION:
PEACH CREEK9129
END DESCRIPTION:
XS GIS Cut Line= 3
      2526474.98     13848124.99        2524075.       13847525.
      2522775.02     13846825.01
#Sta/Elev= 30
  2534.1  401.62  3070.1  393.17  3421.2  384.65  3513.2  381.63  3606.1  382.88
  3657.6  380.64  3714.9  383.48  3757.2  381.85  3794.2   381.8  3830.3  384.74
  3977.2  385.03  4206.5  389.51  4729.6  389.31  4850.8  387.43  4935.8  383.44
  4948.7  381.21  5010.8  379.56  5016.1  376.23  5016.5  370.22  5017.5  369.72
  5059.4  370.22  5059.9  376.11  5087.4  381.79  5244.7  382.63  5325.9   380.1
  5474.3  384.92  5651.3  388.58    6081   389.4  6250.3  392.93  6484.4  399.86
#Mann= 13 ,-1 , 0
  2534.1     .05       0  3421.2     .07       0  3513.2      .1       0
  3714.9     .07       0  3757.2    .045       0  4850.8      .1       0
  5016.5     .05       0  5059.4      .1       0  5244.7     .12       0
  5474.3     .07       0  5651.3     .12       0    6081     .07       0
  6250.3     .12       0
Bank Sta=5016.5,5059.4
XS Rating Curve= 0 ,0
Exp/Cntr=0.3,0.1

Type RM Length L Ch R = 1 ,252143  ,527,527,527
BEGIN DESCRIPTION:
PEACH CREEK9128
END DESCRIPTION:
XS GIS Cut Line= 3
      2526024.99       13847875.        2524025.       13847075.
      2522875.02       13846825.
#Sta/Elev= 30
  2852.1  395.91  3058.1  392.28  3296.7  383.57  3384.1  381.29  3497.1  381.63
  3513.1  380.52  3519.9   376.4  3552.2  381.66    3594  382.14    4413  390.03
  4643.3  388.84    4816  383.02  4876.9  379.67  4967.1  381.29  4973.8  380.06
    4982  370.09    4983  369.59  5024.9  370.09  5025.6  377.49  5030.7  375.19
  5036.9  379.96  5103.5  380.07  5190.4  380.27  5384.8  387.69  5495.5  387.87
  5495.8  387.86    5695  387.61  5865.8  388.75  6053.5  394.36    6183  398.88
#Mann= 15 ,-1 , 0
  2852.1     .05       0  3296.7     .07       0  3384.1     .12       0
  3497.1     .07       0    3594    .045       0    4413     .05       0
  4643.3     .07       0    4816      .1       0    4982     .05       0
  5024.9      .1       0  5103.5     .12       0  5495.5     .07       0
  5495.8     .12       0    5695     .07       0  6053.5     .12       0
Bank Sta=4982,5024.9
XS Rating Curve= 0 ,0
Exp/Cntr=0.3,0.1

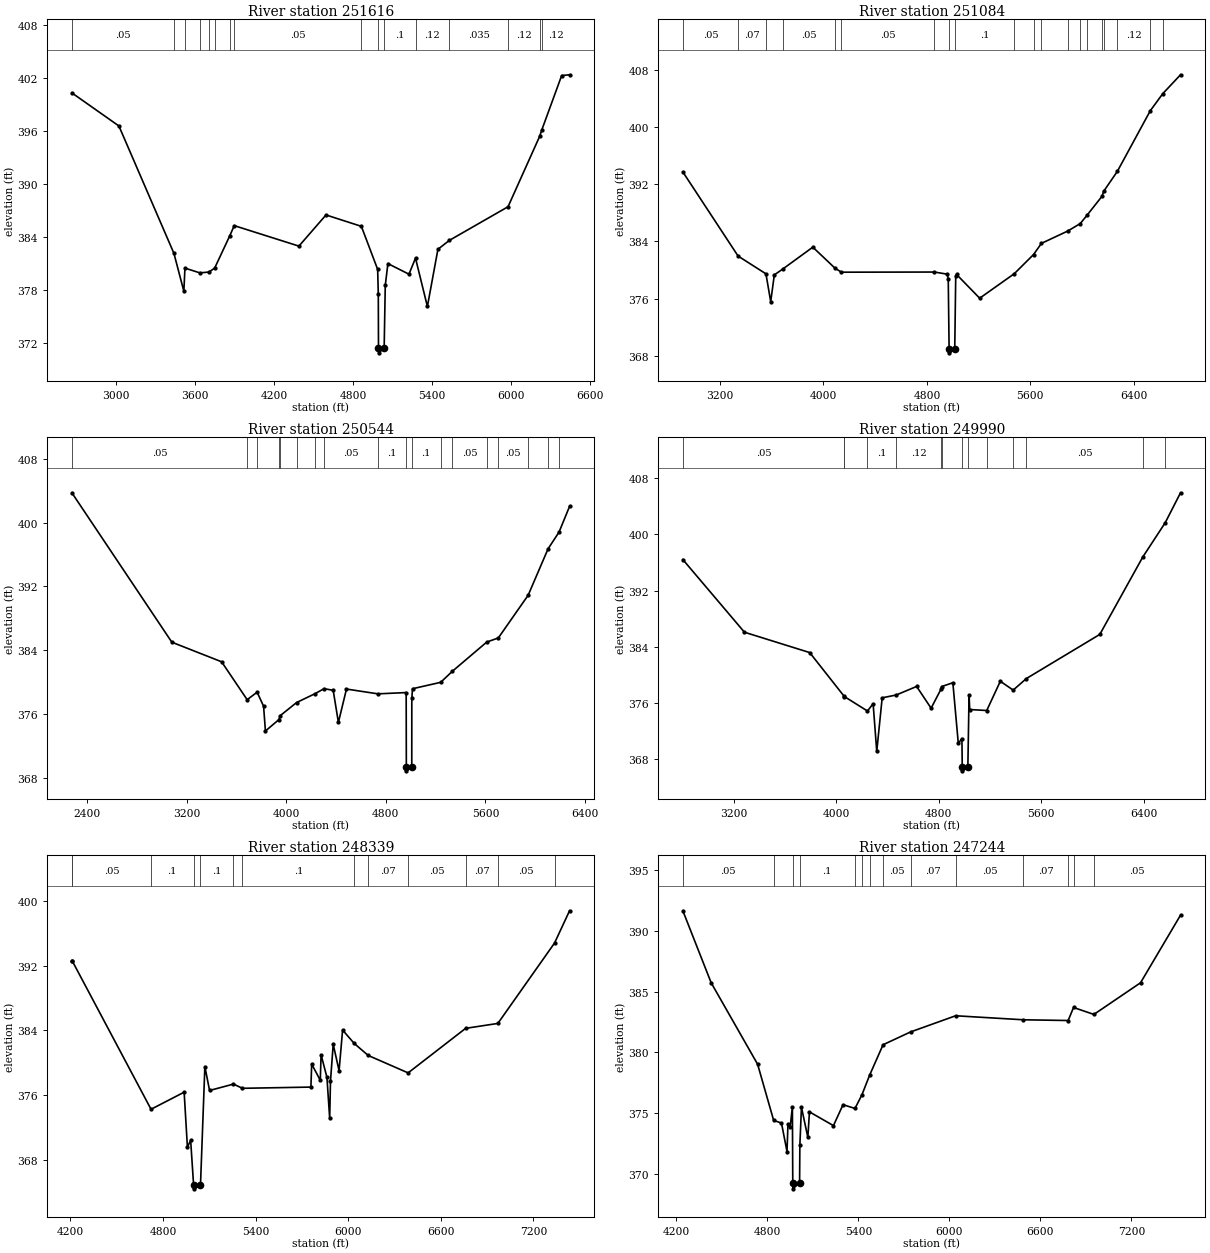
Type RM Length L Ch R = 1 ,251616  ,532,532,532
BEGIN DESCRIPTION:
PEACH CREEK9127
END DESCRIPTION:
XS GIS Cut Line= 3
      2526274.96     13847874.98        2524275.       13846675.
        2522825.       13846725.
#Sta/Elev= 30
  2663.5  400.29  3021.1  396.54  3439.3  382.11  3514.8  377.82  3523.1  380.44
  3636.1   379.9  3705.2  379.99    3749  380.44    3862  384.04  3897.9  385.25
  4389.4  382.93  4595.4  386.46  4864.2  385.17  4988.1  380.29  4992.9  377.47
  4994.4  371.34  4995.4  370.84  5037.4  371.34  5045.9  378.48  5065.9  380.95
    5226  379.75  5275.7  381.57  5366.1  376.09  5446.1  382.57  5533.1  383.58
  5979.1  387.39  6219.3  395.36    6237  396.14  6386.7  402.25  6446.7  402.34
#Mann= 16 ,-1 , 0
  2663.5     .05       0  3439.3     .07       0  3523.1     .12       0
  3636.1     .07       0  3705.2     .12       0    3749     .05       0
    3862    .045       0  3897.9     .05       0  4864.2      .1       0
  4994.4     .05       0  5037.4      .1       0  5275.7     .12       0
  5533.1    .035       0  5979.1     .12       0  6219.3     .07       0
    6237     .12       0
Bank Sta=4994.4,5037.4
XS Rating Curve= 0 ,0
Exp/Cntr=0.3,0.1

Type RM Length L Ch R = 1 ,251084  ,540,540,540
BEGIN DESCRIPTION:
PEACH CREEK9126
END DESCRIPTION:
XS GIS Cut Line= 3
      2525925.03     13847575.03        2524375.       13846175.
        2522925.       13845175.
#Sta/Elev= 30
    2912  393.72  3339.6  381.95  3554.9  379.47  3591.7  375.57  3619.5  379.32
    3685  380.14  3917.5   383.2  4090.3  380.24  4139.2   379.7  4858.1  379.72
  4958.5  379.42  4965.2  378.71  4971.8  368.92  4972.8  368.42  5015.4  368.92
    5023  379.14  5029.1  379.39  5208.3  376.06  5476.1  379.49  5625.1  382.17
    5686  383.73  5889.2  385.45  5986.5   386.5  6038.2  387.65  6155.6  390.34
  6167.1     391    6273  393.79  6528.4  402.29  6625.2  404.68  6762.1  407.31
#Mann= 20 ,-1 , 0
    2912     .05       0  3339.6     .07       0  3554.9      .1       0
    3685     .05       0  4090.3    .035       0  4139.2     .05       0
  4858.1      .1       0  4971.8     .05       0  5015.4      .1       0
  5476.1     .12       0  5625.1    .035       0    5686     .12       0
  5889.2     .07       0  5986.5     .05       0  6038.2     .07       0
  6155.6     .12       0  6167.1     .07       0    6273     .12       0
  6528.4    .035       0  6625.2     .12       0
Bank Sta=4971.8,5015.4
XS Rating Curve= 0 ,0
Exp/Cntr=0.3,0.1

Type RM Length L Ch R = 1 ,250544  ,554,554,554
BEGIN DESCRIPTION:
PEACH CREEK9125
END DESCRIPTION:
XS GIS Cut Line= 3
      2526524.98     13847424.98        2524325.       13845825.
      2523175.02     13845275.01
#Sta/Elev= 30
  2279.7  403.72  3082.2  385.03  3481.8  382.58  3686.8  377.84  3766.9  378.78
  3818.7  377.02  3833.4  373.92  3940.9  375.34    3953  375.85  4083.2  377.48
  4234.2  378.61  4304.5  379.22  4377.5  379.01  4419.2     375  4484.1  379.17
  4736.5  378.57  4963.3  378.73  4964.6  369.44  4965.6  368.94  5008.2  369.44
  5008.5     378  5014.1  379.21  5240.3  380.01    5333  381.38  5610.3  385.05
  5702.8  385.56  5942.3   390.9  6102.3  396.71  6190.3   398.8  6274.7  402.01
#Mann= 18 ,-1 , 0
  2279.7     .05       0  3686.8      .1       0  3766.9    .035       0
  3940.9     .05       0    3953     .07       0  4083.2     .05       0
  4234.2     .12       0  4304.5     .05       0  4736.5      .1       0
  4964.6     .05       0  5008.2      .1       0  5240.3     .12       0
    5333     .05       0  5610.3     .07       0  5702.8     .05       0
  5942.3     .07       0  6102.3     .12       0  6190.3     .05       0
Bank Sta=4964.6,5008.2
XS Rating Curve= 0 ,0
Exp/Cntr=0.3,0.1

Type RM Length L Ch R = 1 ,249990  ,1651,1651,1651
BEGIN DESCRIPTION:
PEACH CREEK9124
END DESCRIPTION:
XS GIS Cut Line= 3
      2526324.97     13847174.97        2524775.       13845625.
      2523174.98     13845074.99
#Sta/Elev= 30
  2802.3  396.42  3283.1  386.06  3792.2  383.16  4061.9  376.91  4063.6  376.88
    4243  374.83  4287.2  375.87  4315.5  369.07  4357.9  376.71  4467.1  377.11
  4626.6  378.33  4739.7  375.23  4815.6   377.9  4821.4  378.31  4909.4  378.86
  4951.9  370.21  4980.1  370.91  4982.8   366.8  4983.8   366.3  5026.5   366.8
  5035.9  377.15  5041.1  375.04  5173.9   374.9  5279.8  379.07  5380.2  377.81
  5483.4  379.46  6056.3  385.75  6391.8  396.79  6566.3  401.66  6686.2  405.94
#Mann= 14 ,-1 , 0
  2802.3     .05       0  4061.9    .035       0  4063.6     .05       0
    4243      .1       0  4467.1     .12       0  4815.6     .05       0
  4821.4      .1       0  4982.8     .05       0  5026.5      .1       0
  5173.9     .12       0  5380.2     .07       0  5483.4     .05       0
  6391.8     .07       0  6566.3     .05       0
Bank Sta=4982.8,5026.5
XS Rating Curve= 0 ,0
Exp/Cntr=0.3,0.1

Type RM Length L Ch R = 1 ,248339  ,1095,1095,1095
BEGIN DESCRIPTION:
PEACH CREEK9123
END DESCRIPTION:
XS GIS Cut Line= 3
      2526574.96     13845724.99        2525825.       13845475.
      2523425.03       13845075.
#Sta/Elev= 30
  4210.5  392.62  4214.5  392.56  4723.3  374.23  4937.8  376.35  4958.9  369.54
  4979.9  370.39  4998.9  364.87  4999.9  364.37  5043.7  364.87    5072  379.53
  5102.4  376.56  5257.4  377.35  5315.5  376.83  5758.8  376.98  5763.9  379.83
  5819.7  377.82  5824.7  380.99  5862.7  378.18  5880.5   373.1  5885.6   377.7
  5903.3  382.28  5941.3  379.01  5964.1  384.05  6039.3  382.39  6129.9   380.9
  6388.5  378.74  6761.1  384.26  6969.8  384.87  7337.2  394.84  7434.1  398.83
#Mann= 13 ,-1 , 0
  4210.5    .035       0  4214.5     .05       0  4723.3      .1       0
  4998.9     .05       0  5043.7      .1       0  5257.4     .07       0
  5315.5      .1       0  6039.3     .05       0  6129.9     .07       0
  6388.5     .05       0  6761.1     .07       0  6969.8     .05       0
  7337.2     .07       0
Bank Sta=4998.9,5043.7
XS Rating Curve= 0 ,0
Exp/Cntr=0.3,0.1

Type RM Length L Ch R = 1 ,247244  ,550,550,550
BEGIN DESCRIPTION:
PEACH CREEK9122
END DESCRIPTION:
XS GIS Cut Line= 3
        2526675.       13845375.        2526075.       13844925.
      2523675.02     13844125.01
#Sta/Elev= 30
  4243.6  391.63  4430.1  385.72  4736.3  379.03    4842  374.42  4893.6   374.2
  4930.1  371.86  4936.3  374.12  4950.9  373.89  4965.5  375.53    4968   369.3
    4969   368.8    5013   369.3  5014.7  372.37  5025.2   375.5  5067.4  373.02
  5077.9  375.12    5236  373.99  5299.3  375.71    5378   375.4  5423.8  376.52
  5474.8  378.14    5563  380.63    5744  381.68  6041.2  383.01  6487.7  382.68
  6782.9  382.62  6818.3  383.69  6952.4  383.12  7259.9  385.72  7523.4  391.27
#Mann= 14 ,-1 , 0
  4243.6     .05       0    4842      .1       0    4968     .05       0
    5013      .1       0    5378     .05       0  5423.8      .1       0
  5474.8     .07       0    5563     .05       0    5744     .07       0
  6041.2     .05       0  6487.7     .07       0  6782.9     .05       0
  6818.3     .07       0  6952.4     .05       0
Bank Sta=4968,5013
XS Rating Curve= 0 ,0
Exp/Cntr=0.3,0.1

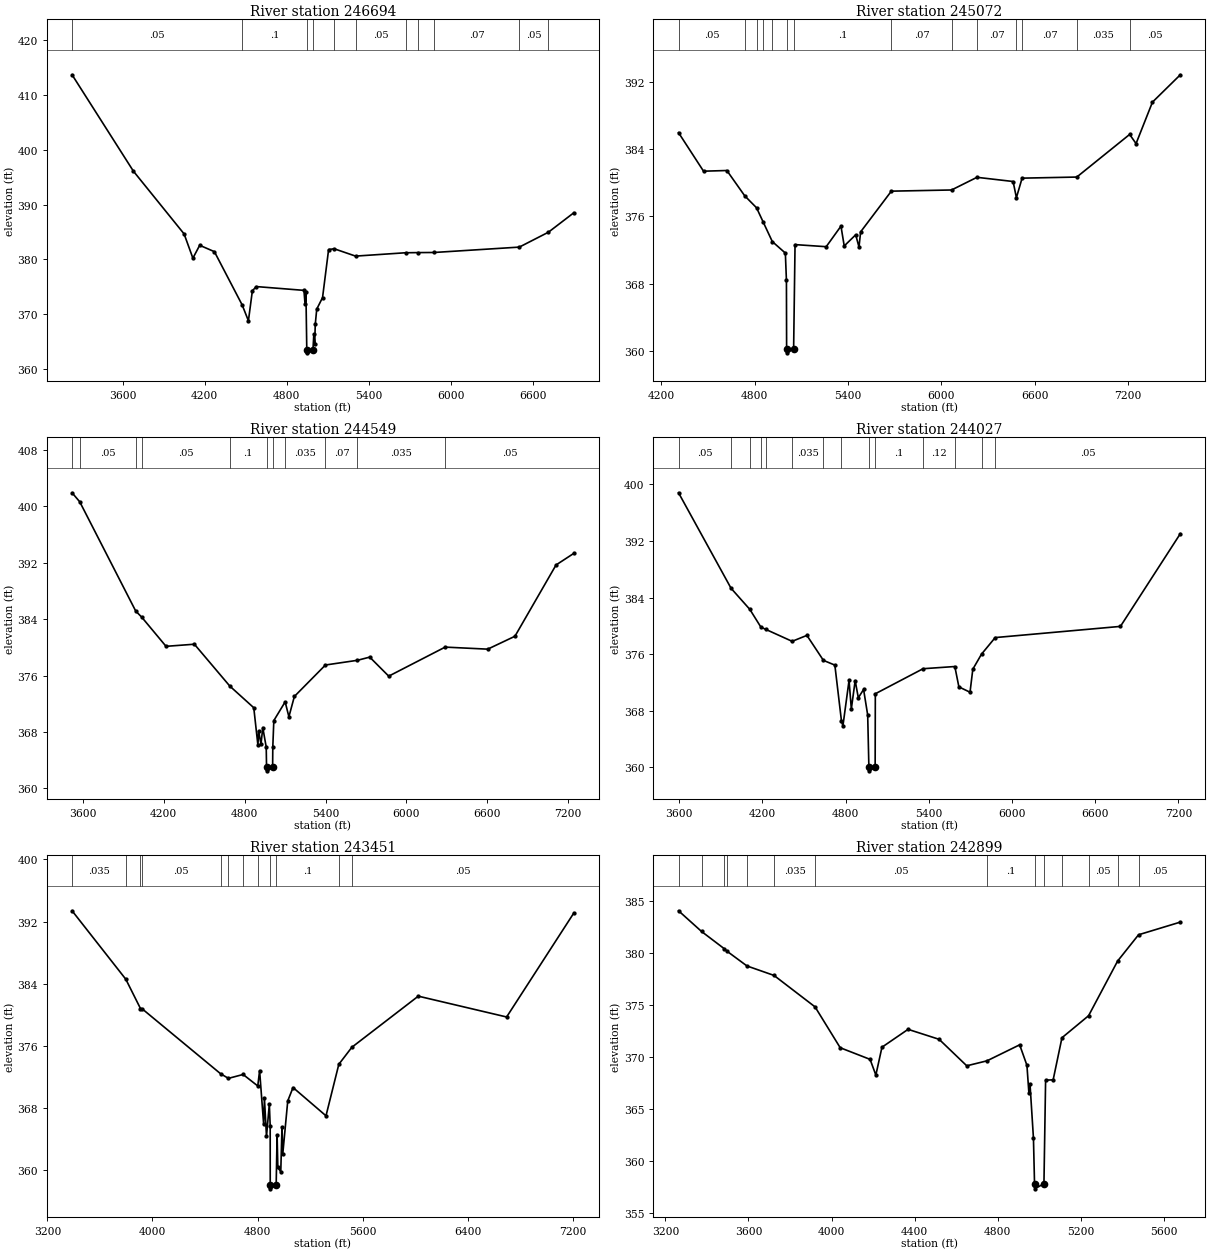
Type RM Length L Ch R = 1 ,246694  ,1622,1622,1622
BEGIN DESCRIPTION:
PEACH CREEK9121
END DESCRIPTION:
XS GIS Cut Line= 3
      2527274.98     13845574.99        2525875.       13844475.
      2524275.02     13843475.01
#Sta/Elev= 30
  3230.7  413.64    3679  396.08  4049.5  384.65  4113.7  380.23  4163.4  382.58
  4270.9  381.42  4473.7  371.72  4519.5  368.83  4548.4   374.3  4577.3  375.06
  4925.3  374.37  4933.4  371.86  4939.7  374.04  4946.1  363.49  4947.1  362.99
  4991.1  363.49  4997.5  366.37  5003.9  364.66    5008  368.17  5018.8  370.95
  5061.2  373.05  5105.5   381.8  5145.9  381.95  5302.5  380.61  5667.5  381.22
  5762.1  381.25  5876.2  381.27  6499.2  382.25  6711.8  384.96  6897.9  388.51
#Mann= 11 ,-1 , 0
  3230.7     .05       0  4473.7      .1       0  4946.1     .05       0
  4991.1      .1       0  5145.9     .07       0  5302.5     .05       0
  5667.5     .07       0  5762.1     .05       0  5876.2     .07       0
  6499.2     .05       0  6711.8    .035       0
Bank Sta=4946.1,4991.1
XS Rating Curve= 0 ,0
Exp/Cntr=0.3,0.1

Type RM Length L Ch R = 1 ,245072  ,523,523,523
BEGIN DESCRIPTION:
PEACH CREEK9120
END DESCRIPTION:
XS GIS Cut Line= 3
        2527275.       13844425.        2526625.       13844175.
      2524225.03     13843375.01
#Sta/Elev= 30
  4309.6  385.98  4470.3  381.39  4620.3  381.47  4735.3  378.45  4811.1  377.03
  4854.1  375.32  4912.5     373  4996.4  371.63  5003.3  368.37  5004.5  360.24
  5005.5  359.74  5049.6  360.24  5058.7  372.64    5259  372.39  5353.9  374.84
  5374.9  372.48  5448.7  373.81  5469.8  372.35  5480.4  374.16  5677.9  379.01
    6065  379.15  6228.3  380.66  6460.7  380.16  6481.9  378.23  6518.5  380.56
  6870.1  380.69  7209.9  385.77  7251.2  384.68  7356.6  389.62  7535.8  392.88
#Mann= 14 ,-1 , 0
  4309.6     .05       0  4735.3     .07       0  4811.1      .1       0
  4854.1     .07       0  4912.5      .1       0  5004.5     .05       0
  5049.6      .1       0  5677.9     .07       0    6065     .05       0
  6228.3     .07       0  6481.9     .05       0  6518.5     .07       0
  6870.1    .035       0  7209.9     .05       0
Bank Sta=5004.5,5049.6
XS Rating Curve= 0 ,0
Exp/Cntr=0.3,0.1

Type RM Length L Ch R = 1 ,244549  ,522,522,522
BEGIN DESCRIPTION:
PEACH CREEK9119
END DESCRIPTION:
XS GIS Cut Line= 3
      2527824.99       13844225.        2526425.       13843725.
      2524224.97     13843324.99
#Sta/Elev= 30
  3519.5  401.92  3576.4  400.64  3991.8  385.14  4036.2  384.28  4216.6  380.14
  4426.9  380.44  4689.8   374.5  4867.5  371.43  4898.3  366.11  4903.6  368.14
  4921.1  366.26  4934.4  368.62  4959.9  365.84  4962.3  362.98  4963.3  362.48
  5007.4  362.98  5008.6  365.82  5016.3  369.61  5100.3  372.26  5128.1  370.15
  5168.7  373.03  5399.2  377.49  5636.9  378.16  5727.7  378.61  5868.8  375.91
  6287.4  380.03  6603.1  379.74  6805.1  381.57    7110  391.68  7242.2  393.33
#Mann= 11 ,-1 , 0
  3519.5    .035       0  3576.4     .05       0  3991.8     .07       0
  4036.2     .05       0  4689.8      .1       0  4962.3     .05       0
  5007.4      .1       0  5100.3    .035       0  5399.2     .07       0
  5636.9    .035       0  6287.4     .05       0
Bank Sta=4962.3,5007.4
XS Rating Curve= 0 ,0
Exp/Cntr=0.3,0.1

Type RM Length L Ch R = 1 ,244027  ,576,576,576
BEGIN DESCRIPTION:
PEACH CREEK9118
END DESCRIPTION:
XS GIS Cut Line= 3
        2527775.       13844025.        2526525.       13843375.
      2524324.98       13843175.
#Sta/Elev= 30
  3595.7   398.8  3974.6   385.3  4109.9  382.32  4189.4  379.82  4223.3  379.51
  4414.8  377.81  4521.2  378.65  4640.2  375.12  4722.8  374.45  4770.5  366.55
  4780.9  365.86  4825.1  372.28  4841.6  368.26  4869.3  372.26  4891.9  369.83
    4930  371.01  4959.5   367.4  4968.2  360.01  4969.2  359.51  5013.3  360.01
  5014.6   370.4  5358.9  373.94  5587.8  374.25  5617.1  371.37  5697.4  370.62
  5717.5  373.87  5780.3     376  5878.9  378.34  6781.9  379.92  7213.7  393.02
#Mann= 14 ,-1 , 0
  3595.7     .05       0  3974.6     .07       0  4109.9     .05       0
  4189.4     .07       0  4223.3     .05       0  4414.8    .035       0
  4640.2     .12       0  4770.5      .1       0  4968.2     .05       0
  5013.3      .1       0  5358.9     .12       0  5587.8      .1       0
  5780.3     .12       0  5878.9     .05       0
Bank Sta=4968.2,5013.3
XS Rating Curve= 0 ,0
Exp/Cntr=0.3,0.1

Type RM Length L Ch R = 1 ,243451  ,552,552,552
BEGIN DESCRIPTION:
PEACH CREEK9117
END DESCRIPTION:
XS GIS Cut Line= 3
      2527875.01     13843725.01        2526475.       13842925.
      2524275.04       13843125.
#Sta/Elev= 30
  3387.5  393.39  3796.7  384.58  3908.4  380.81  3920.5  380.78  4518.9  372.41
  4578.4  371.82  4690.1  372.32  4801.8  370.84  4815.7  372.82  4846.6  365.89
  4852.4  369.24  4868.2  364.35  4889.8  368.51  4896.3  365.71  4896.7   358.1
  4897.7   357.6  4941.9   358.1  4948.9  364.54  4954.6  360.36  4976.9   359.8
  4986.3  365.59    4992  362.07  5030.1  368.92  5070.3  370.64  5321.3     367
    5419  373.63  5518.2  375.82  6024.2   382.4  6696.9  379.72    7209  393.11
#Mann= 12 ,-1 , 0
  3387.5    .035       0  3796.7     .05       0  3908.4     .07       0
  3920.5     .05       0  4518.9    .035       0  4578.4      .1       0
  4690.1    .035       0  4801.8      .1       0  4896.7     .05       0
  4941.9      .1       0    5419     .12       0  5518.2     .05       0
Bank Sta=4896.7,4941.9
XS Rating Curve= 0 ,0
Exp/Cntr=0.3,0.1

Type RM Length L Ch R = 1 ,242899  ,1587,1587,1587
BEGIN DESCRIPTION:
PEACH CREEK9116
END DESCRIPTION:
XS GIS Cut Line= 3
      2527725.01     13843275.01        2526175.       13842475.
      2525575.01       13842775.
#Sta/Elev= 30
  3263.5  384.04  3374.2  382.05  3483.5  380.39    3496  380.16  3592.8  378.73
  3722.9  377.82  3920.6  374.79  4041.6  370.86  4185.4  369.74  4213.2  368.23
  4242.6  370.91  4368.3  372.63  4517.7  371.67  4650.7  369.12  4748.1   369.6
  4905.3  371.14  4940.3  369.17  4949.6  366.55  4955.2  367.34  4971.7  362.15
  4976.9  357.78  4977.9  357.28  5022.2  357.78  5030.2  367.74  5066.5  367.77
  5108.9  371.82    5237  373.94  5376.7   379.2  5477.5  381.73  5678.6  382.95
#Mann= 14 ,-1 , 0
  3263.5     .05       0  3374.2    .035       0  3483.5     .07       0
    3496    .035       0  3592.8     .07       0  3722.9    .035       0
  3920.6     .05       0  4748.1      .1       0  4976.9     .05       0
  5022.2      .1       0  5108.9     .12       0    5237     .05       0
  5376.7     .12       0  5477.5     .05       0
Bank Sta=4976.9,5022.2
XS Rating Curve= 0 ,0
Exp/Cntr=0.3,0.1