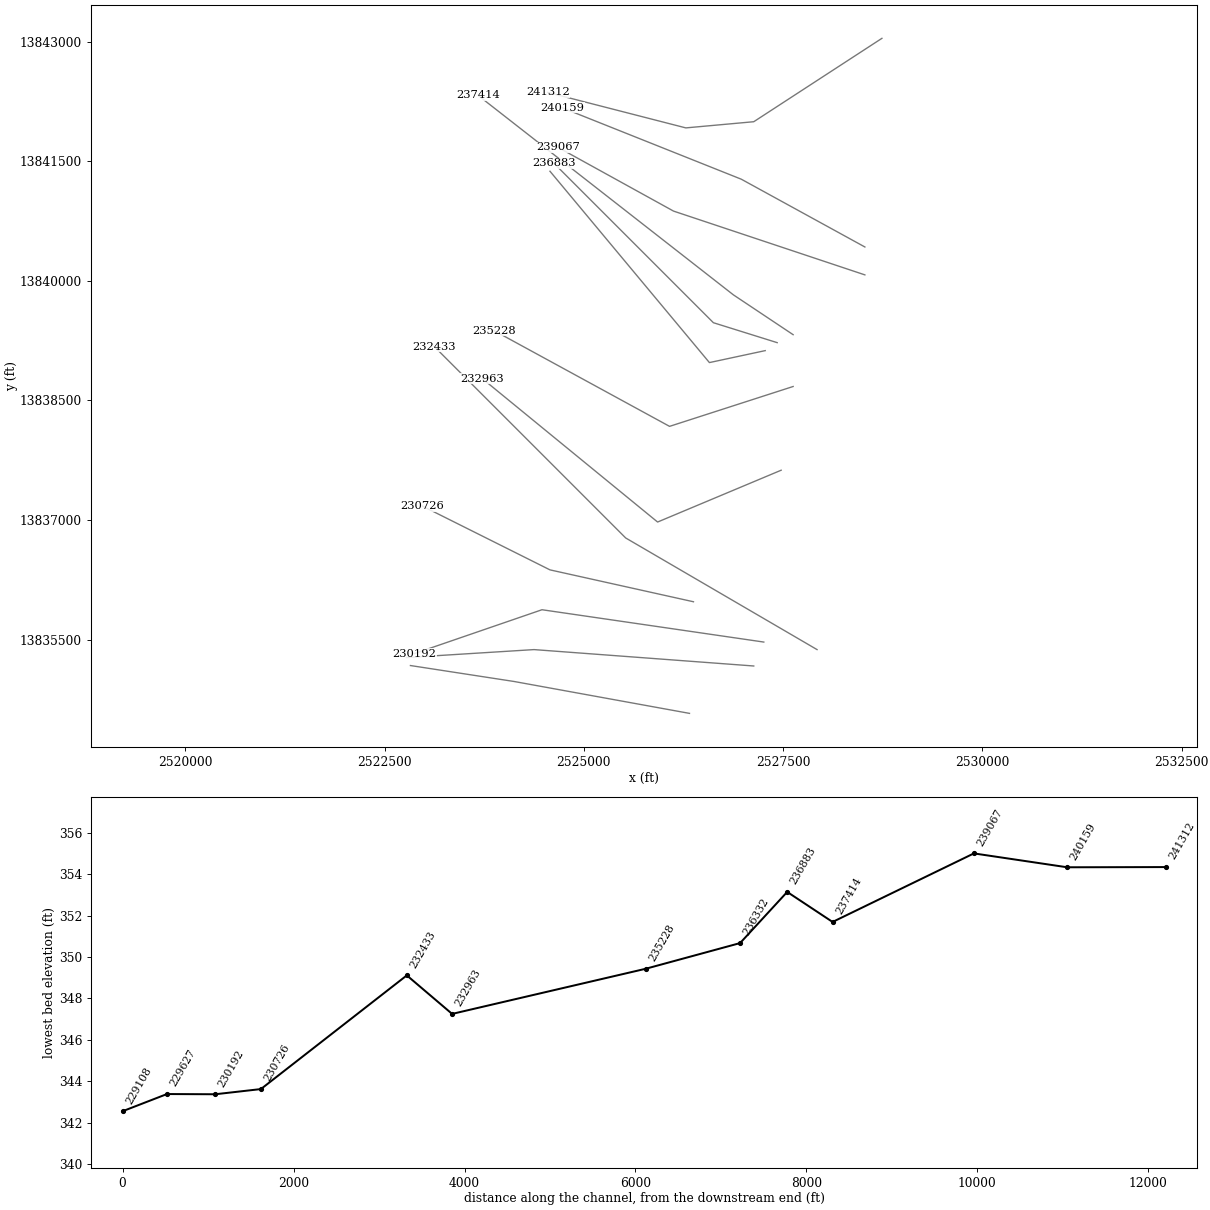
HEC-RAS study PEACH CREEK.prj: PEACH CREEK Base Level Engineering

--- PEACH CREEK.g01 (geometry) --- (continued)

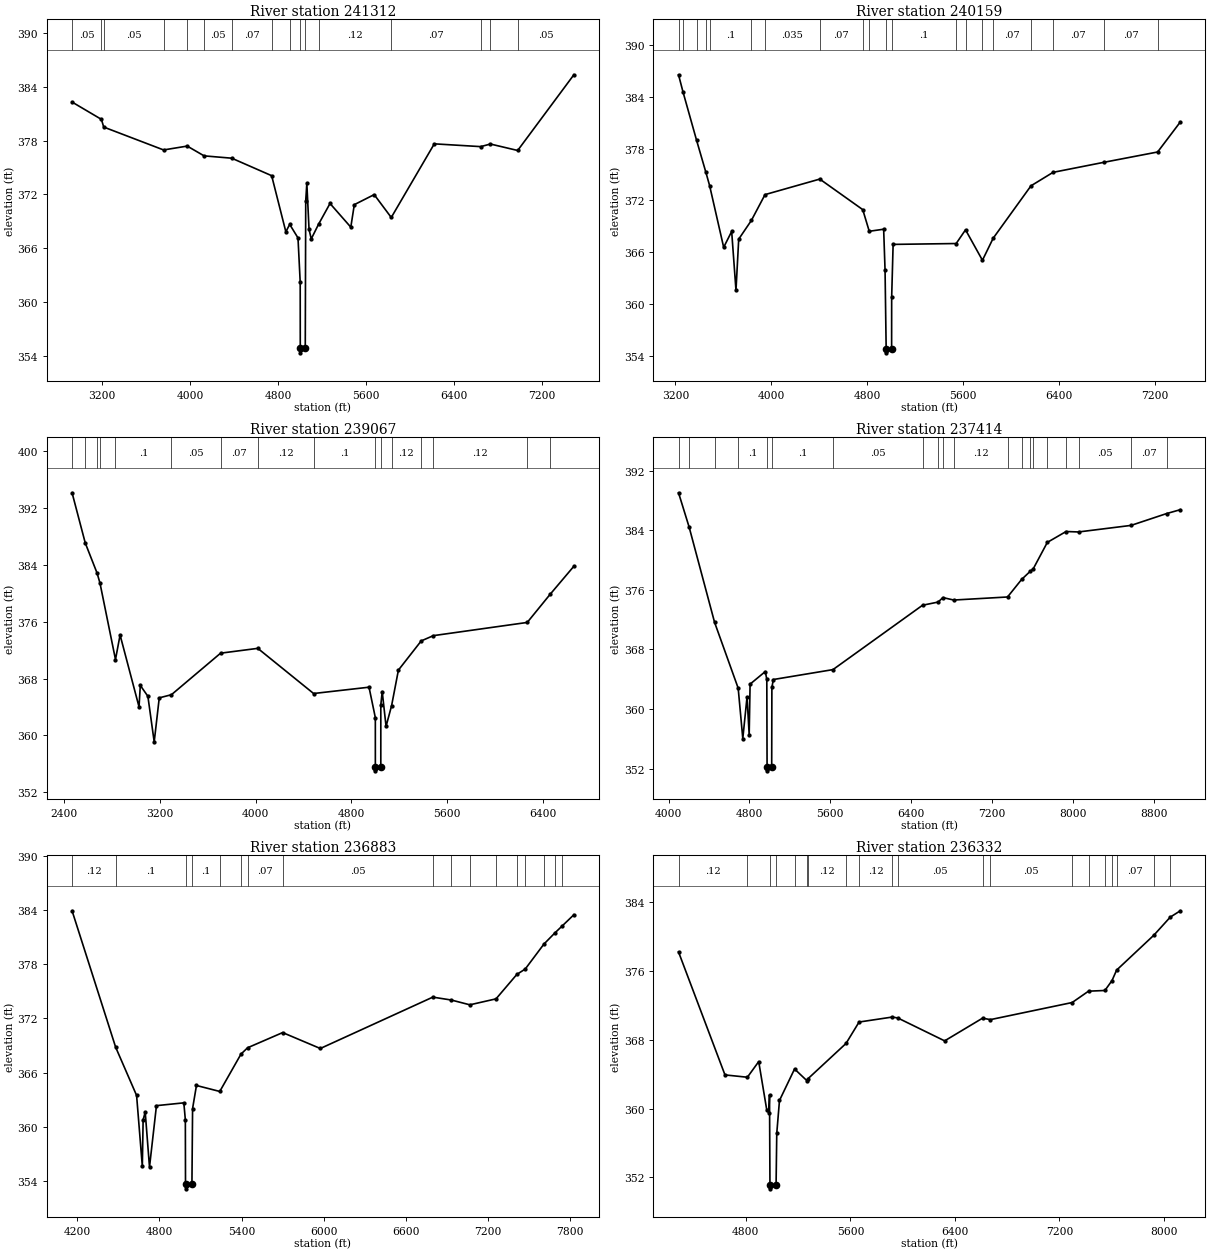
Type RM Length L Ch R = 1 ,241312  ,1153,1153,1153
BEGIN DESCRIPTION:
B19970
END DESCRIPTION:
XS GIS Cut Line= 4
      2528738.71     13843041.98      2527131.24     13841996.15
      2526279.09     13841918.68      2524545.71     13842364.13
#Sta/Elev= 30
  2925.3   382.3    3192  380.37  3213.2  379.51  3757.5  376.96  3972.4  377.39
  4125.9   376.3  4377.2  376.04  4740.3  374.09  4869.4  367.83  4904.3  368.66
  4979.8  367.15  4999.9  362.21  5000.5  354.84  5001.5  354.34  5045.9  354.84
  5050.1   371.3  5060.2  373.24  5080.2   368.1  5100.3  367.04  5166.9  368.68
    5271  370.99    5460  368.35  5491.9  370.86  5672.7  371.98  5827.9  369.43
  6219.2  377.64  6641.6  377.33  6729.4  377.62  6977.4   376.9  7488.4  385.34
#Mann= 16 ,-1 , 0
  2925.3     .05       0    3192     .07       0  3213.2     .05       0
  3757.5     .07       0  3972.4    .035       0  4125.9     .05       0
  4377.2     .07       0  4740.3     .12       0  4904.3      .1       0
  5000.5     .05       0  5045.9      .1       0  5166.9     .12       0
  5827.9     .07       0  6641.6     .05       0  6729.4     .07       0
  6977.4     .05       0
Bank Sta=5000.5,5045.9
XS Rating Curve= 0 ,0
Exp/Cntr=0.3,0.1

Type RM Length L Ch R = 1 ,240159  ,1092,1092,1092
BEGIN DESCRIPTION:
PEACH CREEK9115
END DESCRIPTION:
XS GIS Cut Line= 3
        2528525.       13840425.        2526975.       13841275.
      2524730.48     13842170.16
#Sta/Elev= 30
    3226  386.56  3262.5  384.61  3376.6  378.96  3453.7  375.27  3485.2  373.71
  3602.4  366.56  3669.1   368.4    3705  361.58  3727.8  367.51  3833.1  369.67
  3947.2  372.67  4403.7  374.47    4762  370.93  4816.3  368.42  4936.4  368.66
  4948.1   363.9  4957.3  354.83  4958.3  354.33  5002.8  354.83  5003.2  360.76
  5015.3   366.9  5541.1     367  5619.1  368.59  5760.1  365.06  5849.9  367.62
    6165  373.69  6348.8  375.25  6771.1  376.41  7220.9  377.61  7410.2  381.09
#Mann= 20 ,-1 , 0
    3226     .07       0  3262.5     .12       0  3376.6     .07       0
  3453.7     .12       0  3485.2      .1       0  3833.1     .07       0
  3947.2    .035       0  4403.7     .07       0    4762     .12       0
  4816.3      .1       0  4957.3     .05       0  5002.8      .1       0
  5541.1     .12       0  5619.1      .1       0  5760.1     .12       0
  5849.9     .07       0    6165     .12       0  6348.8     .07       0
  6771.1     .07       0  7220.9     .05       0
Bank Sta=4957.3,5002.8
XS Rating Curve= 0 ,0
Exp/Cntr=0.3,0.1

Type RM Length L Ch R = 1 ,239067  ,1653,1653,1653
BEGIN DESCRIPTION:
PEACH CREEK9114
END DESCRIPTION:
XS GIS Cut Line= 3
      2528524.97     13840075.01        2526125.       13840875.
      2524675.04     13841674.98
#Sta/Elev= 30
  2469.7  394.16  2579.7  387.09  2678.3  382.85  2702.4  381.45  2831.9  370.68
  2870.2  374.13  3028.3  364.01  3038.9  367.03  3102.1   365.5  3154.8  359.08
    3197  365.28  3298.4  365.72  3708.6  371.57  4018.9  372.25  4484.5  365.89
  4946.8  366.78  4999.5  362.49  4999.6   355.5  5000.6     355  5045.1   355.5
  5045.2  364.29  5056.8  366.17  5088.9  361.26  5135.1  364.18    5192  369.19
  5382.4   373.3  5483.5  374.04  6266.7   375.9    6458  379.87  6655.5  383.81
#Mann= 16 ,-1 , 0
  2469.7     .07       0  2579.7     .12       0  2678.3      .1       0
  2702.4     .12       0  2831.9      .1       0  3298.4     .05       0
  3708.6     .07       0  4018.9     .12       0  4484.5      .1       0
  4999.6     .05       0  5045.1      .1       0  5135.1     .12       0
  5382.4     .07       0  5483.5     .12       0  6266.7     .05       0
    6458     .07       0
Bank Sta=4999.6,5045.1
XS Rating Curve= 0 ,0
Exp/Cntr=0.3,0.1

Type RM Length L Ch R = 1 ,237414  ,531,531,531
BEGIN DESCRIPTION:
PEACH CREEK9113
END DESCRIPTION:
XS GIS Cut Line= 3
      2527625.04     13839324.97        2526875.       13839825.
      2523675.02     13842324.99
#Sta/Elev= 30
  4098.7  389.02  4203.8   384.4    4455  371.63  4688.5  362.79  4734.2  356.03
  4776.3  361.63  4797.3  356.51  4806.3  363.33  4956.6  365.02  4971.6  363.97
  4974.3  352.19  4975.3  351.69  5019.9  352.19  5021.8  362.88  5036.3  363.95
  5625.9  365.28  6511.5  373.92  6665.8  374.35  6713.1  374.95  6820.1  374.62
  7352.2  375.03  7491.8  377.39  7576.8  378.48  7605.5  378.79  7745.7  382.36
  7931.3  383.82  8054.2  383.76  8573.3  384.64  8925.6  386.23  9060.9  386.75
#Mann= 20 ,-1 , 0
  4098.7     .05       0  4203.8     .12       0    4455      .1       0
  4688.5      .1       0  4974.3     .05       0  5019.9      .1       0
  5625.9     .05       0  6511.5    .035       0  6665.8     .12       0
  6713.1    .035       0  6820.1     .12       0  7352.2     .05       0
  7491.8     .07       0  7576.8     .05       0  7605.5     .07       0
  7745.7     .07       0  7931.3     .07       0  8054.2     .05       0
  8573.3     .07       0  8925.6     .05       0
Bank Sta=4974.3,5019.9
XS Rating Curve= 0 ,0
Exp/Cntr=0.3,0.1

Type RM Length L Ch R = 1 ,236883  ,551,551,551
BEGIN DESCRIPTION:
PEACH CREEK9112
END DESCRIPTION:
XS GIS Cut Line= 3
      2527425.03     13839224.99        2526625.       13839475.
      2524625.01     13841474.99
#Sta/Elev= 30
  4161.9  383.89  4480.4   368.8  4633.4  363.47  4675.3  355.63  4681.1  360.77
  4696.3  361.63  4727.7  355.55  4778.5  362.34  4978.6  362.65  4989.6  360.77
  4990.8  353.64  4991.8  353.14  5037.7  353.64  5042.5  362.02  5070.8  364.57
  5241.1  363.91  5396.2  368.04  5444.4  368.74  5700.7  370.42  5975.9  368.66
  6797.8  374.34  6933.2  374.02  7068.5  373.49  7259.8  374.15  7411.8  376.85
  7473.3  377.45  7609.9  380.21  7689.8  381.44  7745.2  382.24  7828.5  383.45
#Mann= 17 ,-1 , 0
  4161.9     .12       0  4480.4      .1       0  4990.8     .05       0
  5037.7      .1       0  5241.1     .05       0  5396.2    .035       0
  5444.4     .07       0  5700.7     .05       0  6797.8     .07       0
  6933.2    .035       0  7068.5     .12       0  7259.8     .07       0
  7411.8     .05       0  7473.3     .07       0  7609.9     .05       0
  7689.8     .07       0  7745.2     .05       0
Bank Sta=4990.8,5037.7
XS Rating Curve= 0 ,0
Exp/Cntr=0.3,0.1

Type RM Length L Ch R = 1 ,236332  ,1104,1104,1104
BEGIN DESCRIPTION:
PEACH CREEK9111
END DESCRIPTION:
XS GIS Cut Line= 3
      2527275.03     13839125.01        2526575.       13838975.
      2524575.01     13841374.99
#Sta/Elev= 30
  4284.9  378.22  4640.3  363.92  4811.8  363.65  4898.5  365.47  4959.9  359.86
  4976.1  359.51  4981.2  361.59  4984.5  351.17  4985.5  350.67  5031.4  351.17
  5036.6  357.13  5057.4  360.95  5172.8  364.61  5265.8  363.27  5274.3  363.46
  5566.6  367.58  5666.5  370.07  5920.7  370.65  5963.1  370.54  6321.4  367.88
  6611.4  370.52  6671.6  370.35  7297.3  372.34  7422.4  373.66  7547.6  373.74
    7602  374.89  7637.4  376.11    7923  380.18  8047.7  382.27  8124.9  383.01
#Mann= 20 ,-1 , 0
  4284.9     .12       0  4811.8      .1       0  4984.5     .05       0
  5031.4      .1       0  5172.8     .12       0  5265.8     .07       0
  5274.3     .12       0  5566.6     .07       0  5666.5     .12       0
  5920.7     .07       0  5963.1     .05       0  6611.4     .12       0
  6671.6     .05       0  7297.3     .07       0  7422.4    .035       0
  7547.6     .07       0    7602     .05       0  7637.4     .07       0
    7923     .05       0  8047.7     .05       0
Bank Sta=4984.5,5031.4
XS Rating Curve= 0 ,0
Exp/Cntr=0.3,0.1

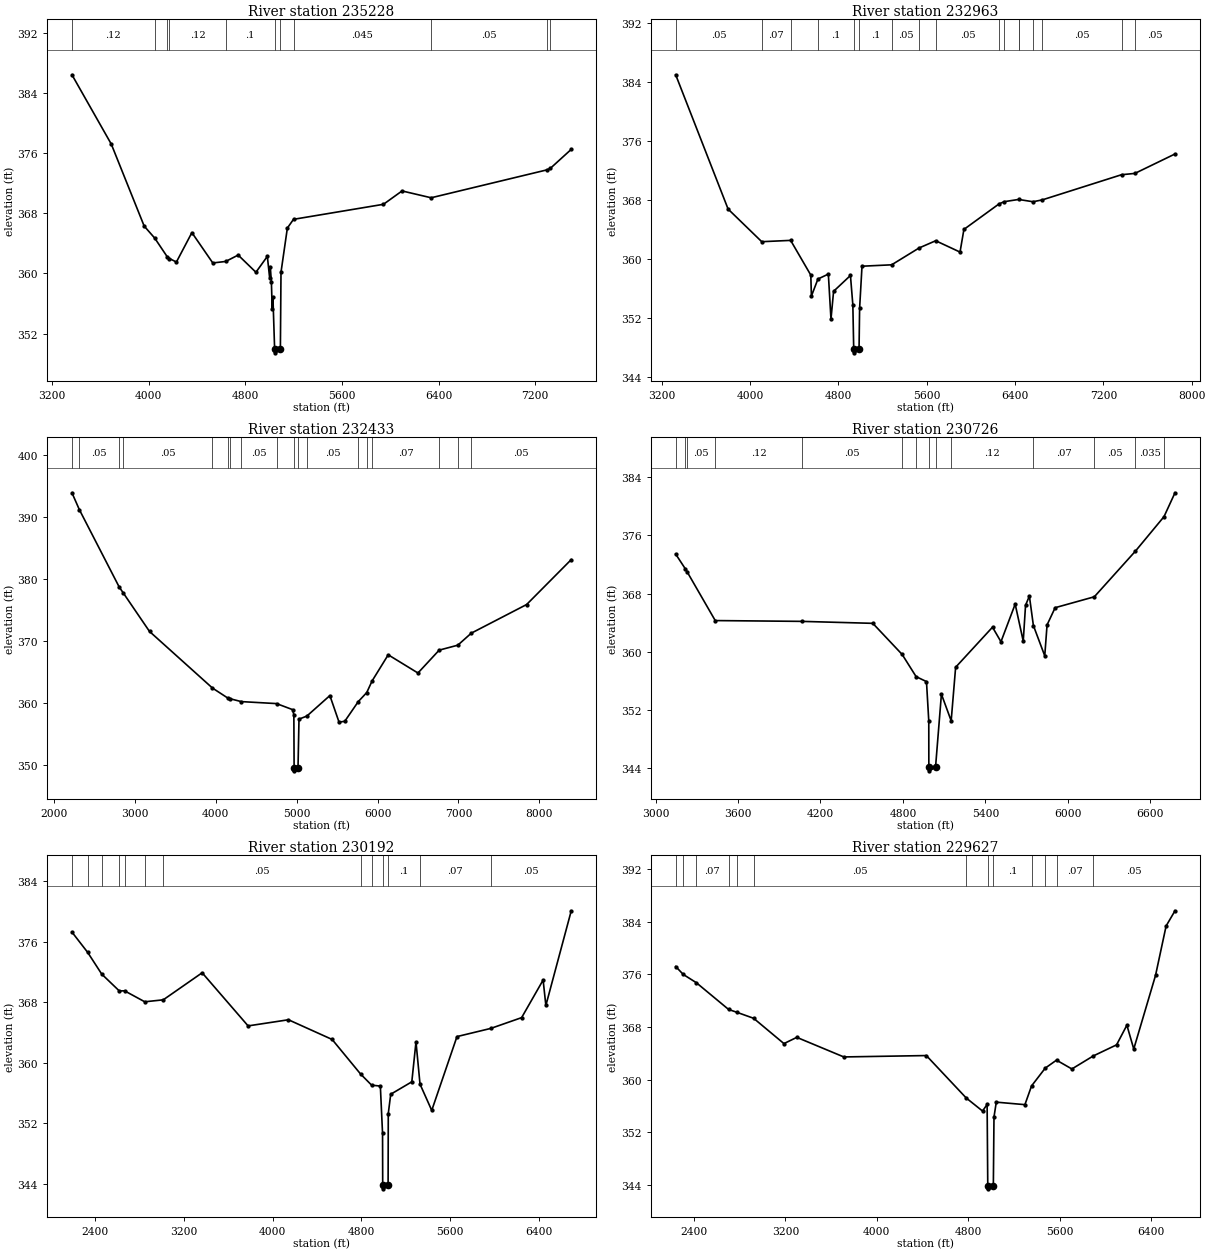
Type RM Length L Ch R = 1 ,235228  ,2265,2265,2265
BEGIN DESCRIPTION:
PEACH CREEK9110
END DESCRIPTION:
XS GIS Cut Line= 3
      2527624.97     13838674.99        2526075.       13838175.
      2523875.01     13839374.99
#Sta/Elev= 30
  3363.1  386.46  3688.8  377.23  3961.2  366.31  4048.9   364.7  4151.4  362.24
  4170.8  361.99  4228.1  361.52  4356.3  365.44  4529.4   361.4  4636.3   361.6
  4739.5  362.45  4886.6  360.16  4981.2  362.28  4999.8  359.46  5005.5  360.91
  5014.5  358.89  5021.6  355.25  5027.3  356.89  5041.4  349.93  5042.4  349.43
  5089.1  349.93  5094.2  360.16  5146.9  366.05  5197.9  367.21  5942.4  369.21
  6096.6  370.99  6337.5  370.08  7294.9  373.79  7323.3  373.98  7497.7  376.53
#Mann= 11 ,-1 , 0
  3363.1     .12       0  4048.9      .1       0  4151.4     .07       0
  4170.8     .12       0  4636.3      .1       0  5041.4     .05       0
  5089.1      .1       0  5197.9    .045       0  6337.5     .05       0
  7294.9    .035       0  7323.3     .05       0
Bank Sta=5041.4,5089.1
XS Rating Curve= 0 ,0
Exp/Cntr=0.3,0.1

Type RM Length L Ch R = 1 ,232963  ,530,530,530
BEGIN DESCRIPTION:
PEACH CREEK9109
END DESCRIPTION:
XS GIS Cut Line= 3
      2527474.99       13837625.        2525925.       13836975.
        2523725.       13838775.
#Sta/Elev= 30
  3325.8  385.03  3800.8  366.78  4105.5  362.35  4367.1  362.53  4549.9  357.81
  4555.3  354.96  4614.5  357.28  4708.8  357.95  4732.6  351.82  4756.3  355.61
    4909  357.76  4930.7  353.77  4938.6  347.75  4939.6  347.25  4986.9  347.75
    4992  353.29  5013.7  359.02  5282.3  359.21  5531.1   361.5  5681.3  362.48
  5901.7  360.94  5936.9  364.02  6255.5  367.49  6302.1  367.79  6432.4  368.09
  6562.7  367.78  6646.5  368.03  7364.6  371.45  7485.8  371.63  7849.1  374.27
#Mann= 17 ,-1 , 0
  3325.8     .05       0  4105.5     .07       0  4367.1     .12       0
  4614.5      .1       0  4938.6     .05       0  4986.9      .1       0
  5282.3     .05       0  5531.1     .12       0  5681.3     .05       0
  6255.5    .045       0  6302.1     .05       0  6432.4     .07       0
  6432.4     .05       0  6562.7     .07       0  6646.5     .05       0
  7364.6    .035       0  7485.8     .05       0
Bank Sta=4938.6,4986.9
XS Rating Curve= 0 ,0
Exp/Cntr=0.3,0.1

Type RM Length L Ch R = 1 ,232433  ,1707,1707,1707
BEGIN DESCRIPTION:
PEACH CREEK9108
END DESCRIPTION:
XS GIS Cut Line= 3
      2527924.98     13835375.01        2525525.       13836775.
      2523124.99     13839175.01
#Sta/Elev= 30
  2221.5  393.85  2312.9  391.14  2805.9  378.68  2857.2  377.71  3180.3  371.54
  3958.6  362.43  4144.9  360.85  4176.6  360.71  4315.1  360.25  4750.5  359.93
  4949.1  358.96  4964.8  358.12    4968  349.61    4969  349.11  5016.3  349.61
  5028.3  357.43  5125.4  357.92  5410.1  361.22  5523.2  356.95  5593.9  357.08
  5761.8  360.26  5865.6   361.7  5932.8  363.59  6131.3  367.78    6499  364.85
  6761.2  368.53  6991.9  369.33  7158.1  371.26  7842.5  375.87  8394.1   383.1
#Mann= 18 ,-1 , 0
  2221.5     .07       0  2312.9     .05       0  2805.9    .035       0
  2857.2     .05       0  3958.6    .035       0  4144.9     .05       0
  4176.6    .035       0  4315.1     .05       0  4750.5      .1       0
    4968     .05       0  5016.3      .1       0  5125.4     .05       0
  5761.8     .07       0  5865.6     .05       0  5932.8     .07       0
  6761.2     .05       0  6991.9    .035       0  7158.1     .05       0
Bank Sta=4968,5016.3
XS Rating Curve= 0 ,0
Exp/Cntr=0.3,0.1

Type RM Length L Ch R = 1 ,230726  ,534,534,534
BEGIN DESCRIPTION:
PEACH CREEK9107
END DESCRIPTION:
XS GIS Cut Line= 3
      2526375.02       13835975.        2524575.       13836375.
      2522974.98     13837175.01
#Sta/Elev= 30
  3146.6  373.42  3217.9  371.36    3229  371.01  3434.4  364.28    4063  364.17
  4580.8   363.9  4794.4  359.62    4896  356.57  4971.3  355.89    4988  350.48
  4988.5  344.12  4989.5  343.62  5037.2  344.12    5080  354.16    5151   350.5
  5183.4  357.86  5451.7  363.37  5513.2  361.37  5616.6  366.54  5675.3  361.45
  5692.1  366.38    5720  367.65  5749.1   363.6  5831.8  359.43  5848.6  363.68
  5907.3  366.05  6192.5  367.55  6491.2  373.82  6699.5  378.57  6779.4  381.85
#Mann= 14 ,-1 , 0
  3146.6     .05       0  3217.9     .12       0    3229     .05       0
  3434.4     .12       0    4063     .05       0  4794.4    .035       0
    4896      .1       0  4988.5     .05       0  5037.2      .1       0
    5151     .12       0  5749.1     .07       0  6192.5     .05       0
  6491.2    .035       0  6699.5     .12       0
Bank Sta=4988.5,5037.2
XS Rating Curve= 0 ,0
Exp/Cntr=0.3,0.1

Type RM Length L Ch R = 1 ,230192  ,565,565,565
BEGIN DESCRIPTION:
PEACH CREEK9106
END DESCRIPTION:
XS GIS Cut Line= 3
      2527257.14      13835469.5        2524475.       13835875.
      2522875.02     13835325.01
#Sta/Elev= 30
  2188.8  377.25  2330.7  374.57  2457.7   371.7    2616  369.48  2663.1   369.5
  2845.7  368.05  3012.5  368.31  3363.2  371.88  3777.5  364.87  4141.4  365.68
  4535.5  363.08  4791.5  358.53  4891.5  357.05  4970.4  356.93  4990.2  350.68
  4991.6  343.87  4992.6  343.37  5040.3  343.87  5041.9   353.3  5063.8  355.85
  5254.1  357.49  5291.8  362.76  5328.2  357.18  5433.9  353.72  5661.5  363.46
  5966.9  364.54  6244.5  365.96  6438.4  370.92  6463.2  367.57  6692.2  380.06
#Mann= 13 ,-1 , 0
  2188.8    .035       0  2330.7     .07       0  2457.7     .05       0
    2616     .07       0  2663.1     .05       0  2845.7     .07       0
  3012.5     .05       0  4791.5    .035       0  4891.5      .1       0
  4991.6     .05       0  5040.3      .1       0  5328.2     .07       0
  5966.9     .05       0
Bank Sta=4991.6,5040.3
XS Rating Curve= 0 ,0
Exp/Cntr=0.3,0.1

Type RM Length L Ch R = 1 ,229627  ,519,519,519
BEGIN DESCRIPTION:
PEACH CREEK9105
END DESCRIPTION:
XS GIS Cut Line= 3
      2527131.22     13835169.32        2524375.       13835375.
        2522775.       13835275.
#Sta/Elev= 30
    2241  377.21  2307.6     376  2421.3  374.75  2703.5  370.68  2776.8  370.24
  2922.7  369.33  3187.8  365.48  3300.2  366.43  3711.3  363.45  4433.3  363.66
  4782.4   357.2  4924.7  355.22  4964.8  356.22  4970.5  343.88  4971.5  343.38
  5019.3  343.88  5024.9  354.31    5045  356.57  5295.4  356.19  5353.5  359.04
  5473.2  361.75  5571.7  362.96  5706.2  361.62  5893.2   363.6    6097  365.29
  6187.2  368.28  6247.3  364.66  6437.7  375.85  6530.4  383.38    6608  385.69
#Mann= 13 ,-1 , 0
    2241    .035       0  2307.6     .05       0  2421.3     .07       0
  2703.5     .05       0  2776.8     .07       0  2922.7     .05       0
  4782.4      .1       0  4970.5     .05       0  5019.3      .1       0
  5353.5    .035       0  5473.2     .05       0  5571.7     .07       0
  5893.2     .05       0
Bank Sta=4970.5,5019.3
XS Rating Curve= 0 ,0
Exp/Cntr=0.3,0.1

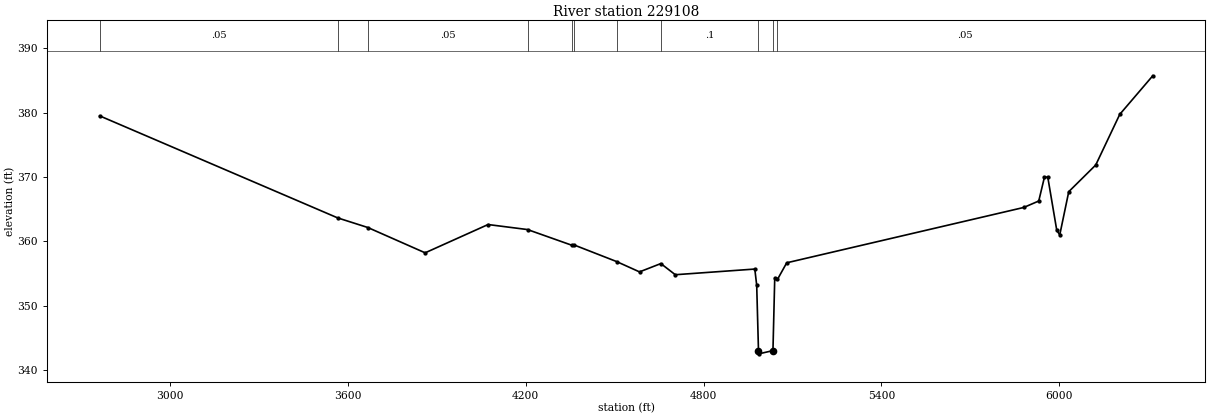
Type RM Length L Ch R = 1 ,229108  ,544,544,544
BEGIN DESCRIPTION:
PEACH CREEK9104
END DESCRIPTION:
XS GIS Cut Line= 3
      2526325.02       13834575.        2524125.       13834975.
      2522824.98       13835175.
#Sta/Elev= 30
  2763.4  379.49  3566.2  363.65  3667.7  362.16  3861.1  358.23  4073.3  362.62
  4206.4  361.84  4355.5  359.41  4362.2  359.47  4506.4  356.88    4584  355.27
  4655.9  356.56  4704.7  354.83  4972.8  355.71  4979.2  353.19  4985.2  343.05
  4986.2  342.55    5034  343.05    5040  354.28  5049.3  354.11  5080.4  356.68
  5879.7  365.27  5930.3  366.27  5949.3  369.93  5960.7     370    5991  361.75
  6001.1     361  6031.5  367.72  6122.5  371.86  6203.5  379.72  6314.8  385.71
#Mann= 11 ,-1 , 0
  2763.4     .05       0  3566.2     .07       0  3667.7     .05       0
  4206.4     .07       0  4355.5     .05       0  4362.2     .07       0
  4506.4     .12       0  4655.9      .1       0  4985.2     .05       0
    5034      .1       0  5049.3     .05       0
Bank Sta=4985.2,5034
XS Rating Curve= 0 ,0
Exp/Cntr=0.3,0.1