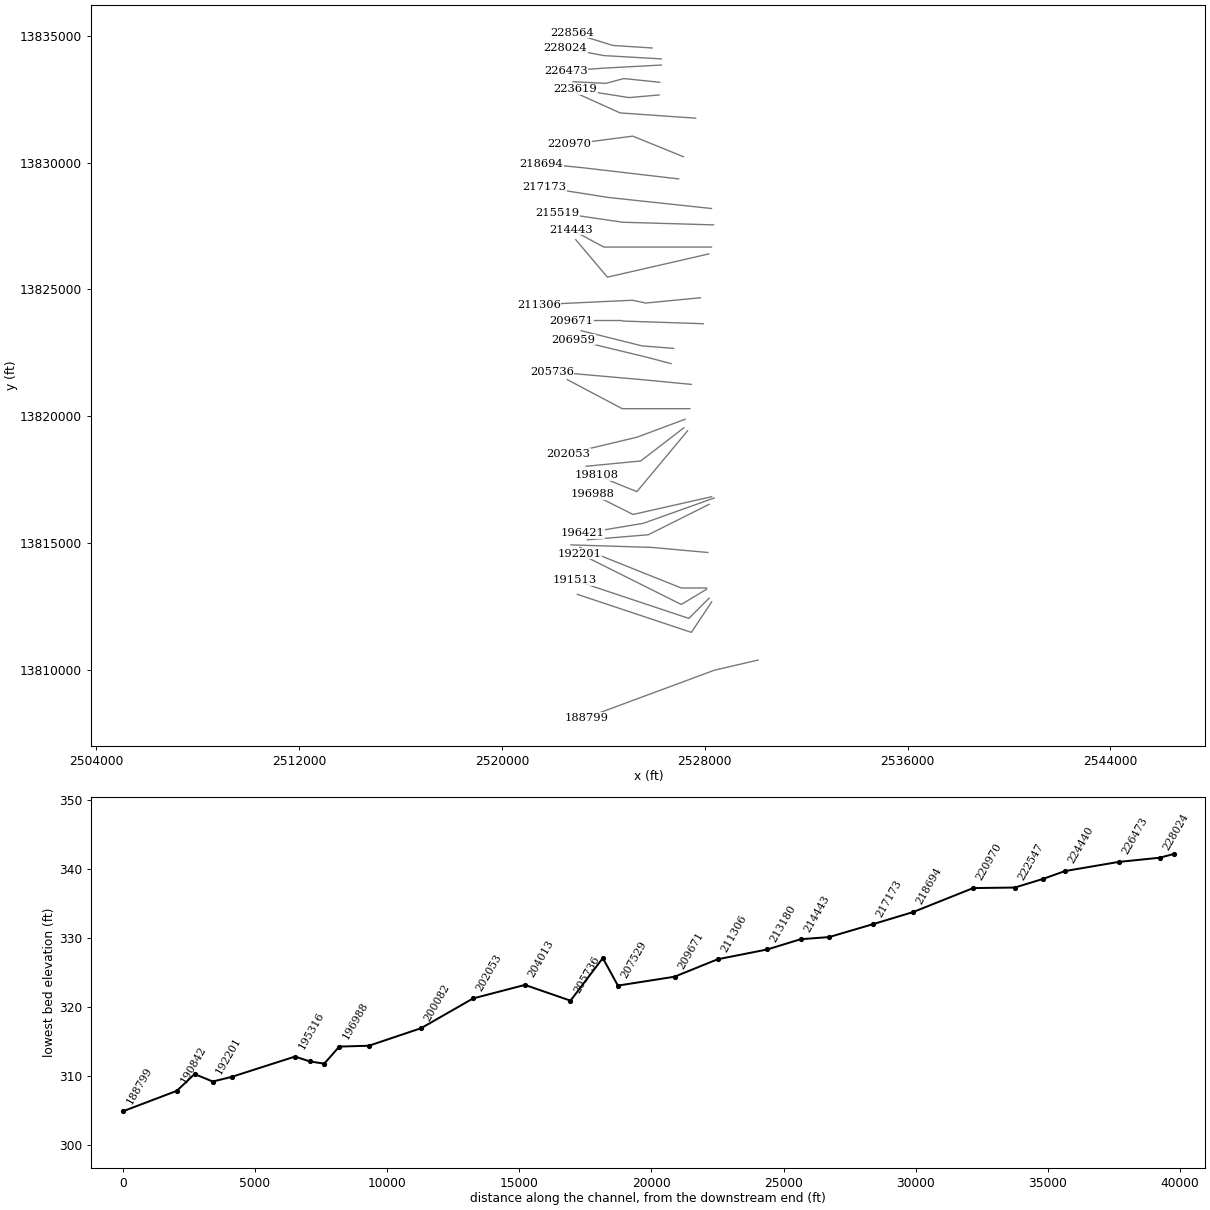
HEC-RAS study PEACH CREEK.prj: PEACH CREEK Base Level Engineering

--- PEACH CREEK.g01 (geometry) --- (continued)

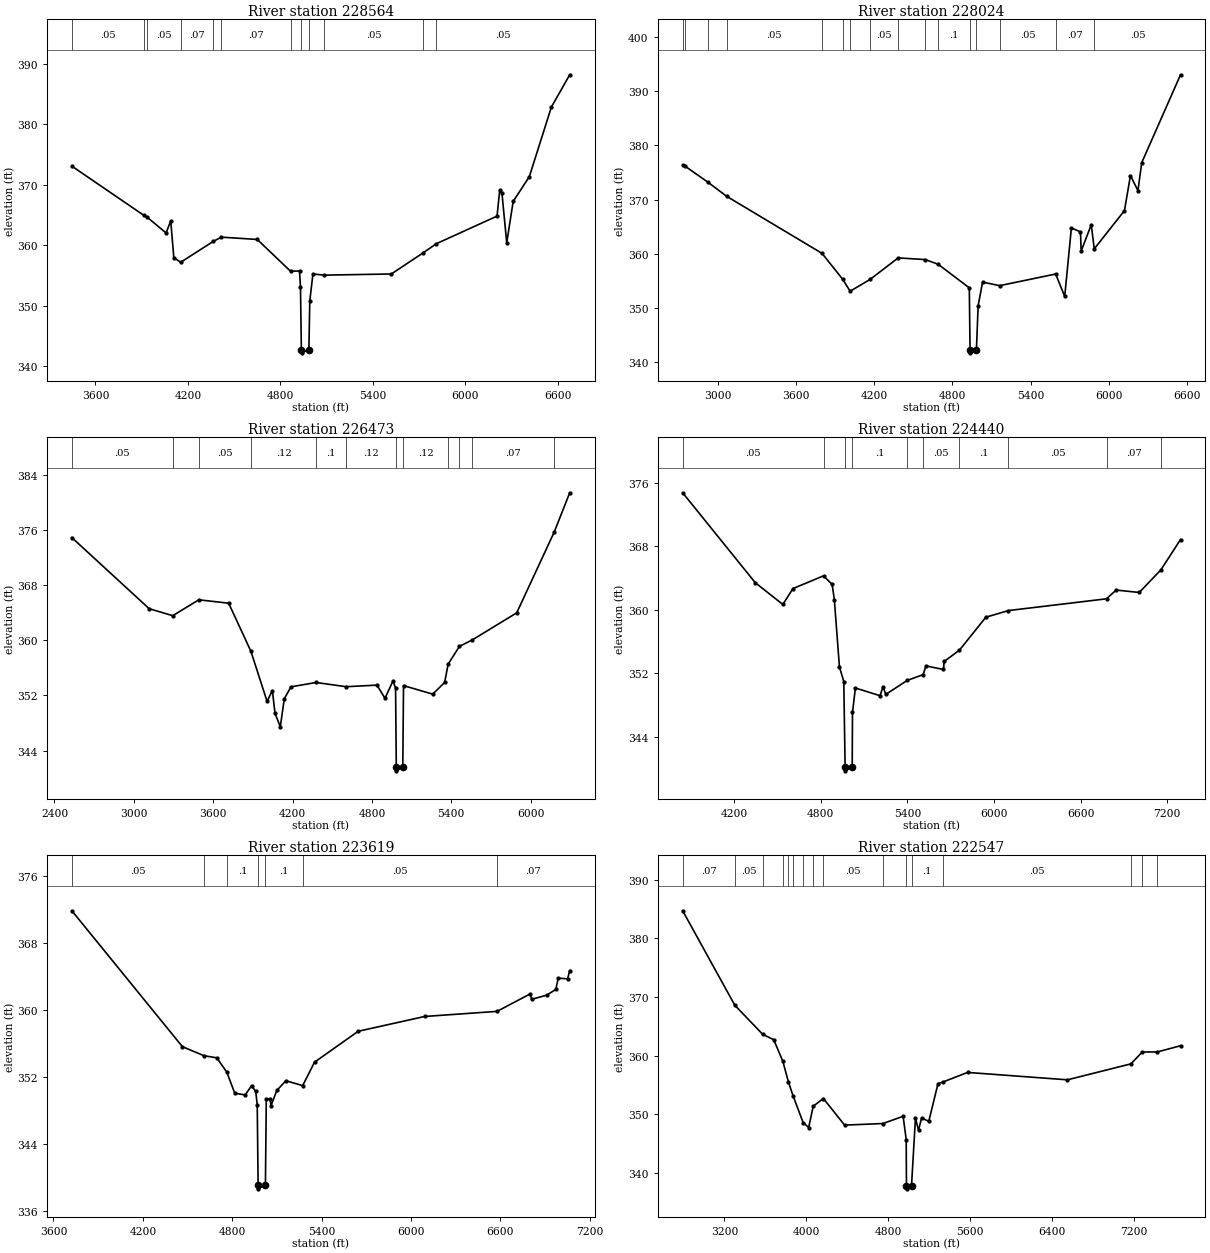
Type RM Length L Ch R = 1 ,228564  ,540,540,540
BEGIN DESCRIPTION:
PEACH CREEK9103
END DESCRIPTION:
XS GIS Cut Line= 3
      2525924.95       13834525.        2524375.       13834625.
      2522774.98     13835125.01
#Sta/Elev= 30
  3447.2  373.09  3914.4  364.95  3933.3   364.7  4058.4  362.04  4088.5  364.05
  4108.5  357.96  4153.3   357.2  4365.4  360.66  4416.8  361.35  4649.6  360.97
  4865.5  355.72    4924  355.75  4930.2  353.06  4935.9  342.72  4936.9  342.22
  4984.7  342.72  4990.4  350.78  5010.9  355.26  5084.5  355.07  5519.5  355.26
  5728.1  358.79  5810.9  360.26  6205.2  364.83  6222.5  369.08  6236.7  368.71
  6268.1  360.42    6310  367.27  6414.8  371.36  6557.8  382.87  6676.7   388.2
#Mann= 12 ,-1 , 0
  3447.2     .05       0  3914.4     .07       0  3933.3     .05       0
  4153.3     .07       0  4365.4     .05       0  4416.8     .07       0
  4865.5      .1       0  4935.9     .05       0  4984.7      .1       0
  5084.5     .05       0  5728.1    .035       0  5810.9     .05       0
Bank Sta=4935.9,4984.7
XS Rating Curve= 0 ,0
Exp/Cntr=0.3,0.1

Type RM Length L Ch R = 1 ,228024  ,1551,1551,1551
BEGIN DESCRIPTION:
PEACH CREEK9102
END DESCRIPTION:
XS GIS Cut Line= 3
      2526288.78     13834094.45        2524025.       13834225.
      2522502.54     13834510.84
#Sta/Elev= 30
  2732.8  376.41  2753.5  376.14  2929.4  373.16  3069.7  370.61  3801.6  360.05
  3960.4  355.24  4016.7  353.06  4170.1  355.25  4385.1  359.22  4592.3  358.91
  4691.1  358.05  4930.2  353.68  4935.9  342.17  4936.9  341.67  4984.7  342.17
  4997.8  350.35  5031.7  354.75  5163.2  354.09    5592  356.24  5661.7   352.1
  5712.6  364.76  5782.4  364.03  5787.5  360.47  5865.2  365.36  5887.9  360.89
  6119.6  367.96  6165.4  374.44    6223  371.65  6251.8  376.81  6549.4  393.07
#Mann= 16 ,-1 , 0
  2732.8    .035       0  2753.5     .05       0  2929.4    .035       0
  3069.7     .05       0  3801.6     .07       0  3960.4     .05       0
  4016.7     .07       0  4170.1     .05       0  4385.1     .07       0
  4592.3     .05       0  4691.1      .1       0  4935.9     .05       0
  4984.7      .1       0  5163.2     .05       0    5592     .07       0
  5887.9     .05       0
Bank Sta=4935.9,4984.7
XS Rating Curve= 0 ,0
Exp/Cntr=0.3,0.1

Type RM Length L Ch R = 1 ,226473  ,2033,2033,2033
BEGIN DESCRIPTION:
PEACH CREEK9101
END DESCRIPTION:
XS GIS Cut Line= 3
      2526288.79     13833852.36      2523955.06     13833726.48
      2522531.86     13833619.98
#Sta/Elev= 30
  2531.5  374.88  3116.1  364.57  3294.4  363.56  3491.4  365.86    3717  365.37
  3885.5  358.38  4007.4  351.13  4047.5  352.69  4067.5   349.4  4107.6  347.45
  4137.6   351.5  4187.7  353.24    4378  353.87  4605.4  353.26  4838.6  353.49
  4898.8  351.58  4959.7  354.11    4979  353.05  4984.6  341.56  4985.6  341.06
  5033.5  341.56  5039.2  353.42  5259.8  352.18    5350  353.87  5376.6  356.54
    5462  359.11  5560.6  360.06    5895  363.97  6178.7  375.69  6295.8  381.38
#Mann= 12 ,-1 , 0
  2531.5     .05       0  3294.4    .035       0  3491.4     .05       0
  3885.5     .12       0    4378      .1       0  4605.4     .12       0
  4984.6     .05       0  5033.5     .12       0  5376.6     .12       0
    5462     .05       0  5560.6     .07       0  6178.7     .12       0
Bank Sta=4984.6,5033.5
XS Rating Curve= 0 ,0
Exp/Cntr=0.3,0.1

Type RM Length L Ch R = 1 ,224440  ,821,821,821
BEGIN DESCRIPTION:
B19969
END DESCRIPTION:
XS GIS Cut Line= 4
       2526225.4      13833172.4      2524808.72     13833318.23
      2524100.39     13833130.73      2522809.39      13833193.2
#Sta/Elev= 30
  3843.4  374.74  4346.4  363.42  4537.4  360.68  4607.8  362.68  4819.3  364.28
  4879.2   363.2  4894.3  361.27  4929.5  352.83  4959.7  350.97  4968.8  340.23
  4969.8  339.73    5018  340.23    5020  347.09  5040.1  350.16    5211  349.19
  5231.1  350.31  5251.2  349.36  5398.8  351.11    5509  351.84  5529.5  352.94
  5650.2  352.49  5655.4   353.5  5761.2  354.93  5943.8  359.07  6100.5  359.91
    6780  361.39  6846.7  362.49  7006.9  362.19  7156.4  365.03  7292.8  368.85
#Mann= 10 ,-1 , 0
  3843.4     .05       0  4819.3      .1       0  4968.8     .05       0
    5018      .1       0  5398.8     .12       0    5509     .05       0
  5761.2      .1       0  6100.5     .05       0    6780     .07       0
  7156.4    .035       0
Bank Sta=4968.8,5018
XS Rating Curve= 0 ,0
Exp/Cntr=0.3,0.1

Type RM Length L Ch R = 1 ,223619  ,1072,1072,1072
BEGIN DESCRIPTION:
B19968
END DESCRIPTION:
XS GIS Cut Line= 3
      2526204.54      13832672.4      2525017.06     13832568.23
      2522892.08     13832901.56
#Sta/Elev= 30
  3723.6  371.88    4466  355.61  4611.5  354.53  4696.9  354.28  4764.6  352.54
  4817.3  350.04  4887.6  349.84    4930  350.94  4958.2  350.26  4968.3  348.66
  4974.1   339.1  4975.1   338.6  5023.3   339.1  5029.1  349.38  5055.2  349.35
  5060.3  348.53  5099.9  350.38  5160.7  351.54  5273.3  350.95    5353  353.76
  5646.5  357.46  6092.8  359.23  6578.5  359.84    6802  361.94  6810.6  361.28
  6911.8  361.78  6972.5  362.46  6989.9  363.82  7052.5  363.73  7066.6  364.73
#Mann= 7 ,-1 , 0
  3723.6     .05       0  4611.5     .12       0  4764.6      .1       0
  4974.1     .05       0  5023.3      .1       0  5273.3     .05       0
  6578.5     .07       0
Bank Sta=4974.1,5023.3
XS Rating Curve= 0 ,0
Exp/Cntr=0.3,0.1

Type RM Length L Ch R = 1 ,222547  ,1577,1577,1577
BEGIN DESCRIPTION:
B19967
END DESCRIPTION:
XS GIS Cut Line= 3
      2527642.05     13831755.73      2524662.89     13831964.07
      2522954.58     13832734.89
#Sta/Elev= 30
  2792.9  384.68  3302.3  368.59  3572.9  363.67  3682.1  362.72  3770.8  359.06
  3825.7  355.52  3869.8  353.22  3968.7  348.63  4022.9  347.78  4067.7  351.41
  4166.6  352.72  4373.8  348.19  4748.4  348.46  4945.2  349.69  4975.3  345.74
  4977.7  337.84  4978.7  337.34    5027  337.84  5065.5  349.34  5095.6  347.33
  5125.6   349.4  5195.8  348.84    5286  355.27  5331.2  355.51  5574.7  357.16
    6549   355.9  7169.7  358.62  7279.1  360.63  7428.1  360.65  7653.5   361.7
#Mann= 16 ,-1 , 0
  2792.9     .07       0  3302.3     .05       0  3572.9     .12       0
  3770.8     .05       0  3825.7     .12       0  3869.8     .12       0
  3968.7     .05       0  4067.7    .035       0  4166.6     .05       0
  4748.4      .1       0  4977.7     .05       0    5027      .1       0
  5331.2     .05       0  7169.7     .07       0  7279.1    .035       0
  7428.1     .07       0
Bank Sta=4977.7,5027
XS Rating Curve= 0 ,0
Exp/Cntr=0.3,0.1

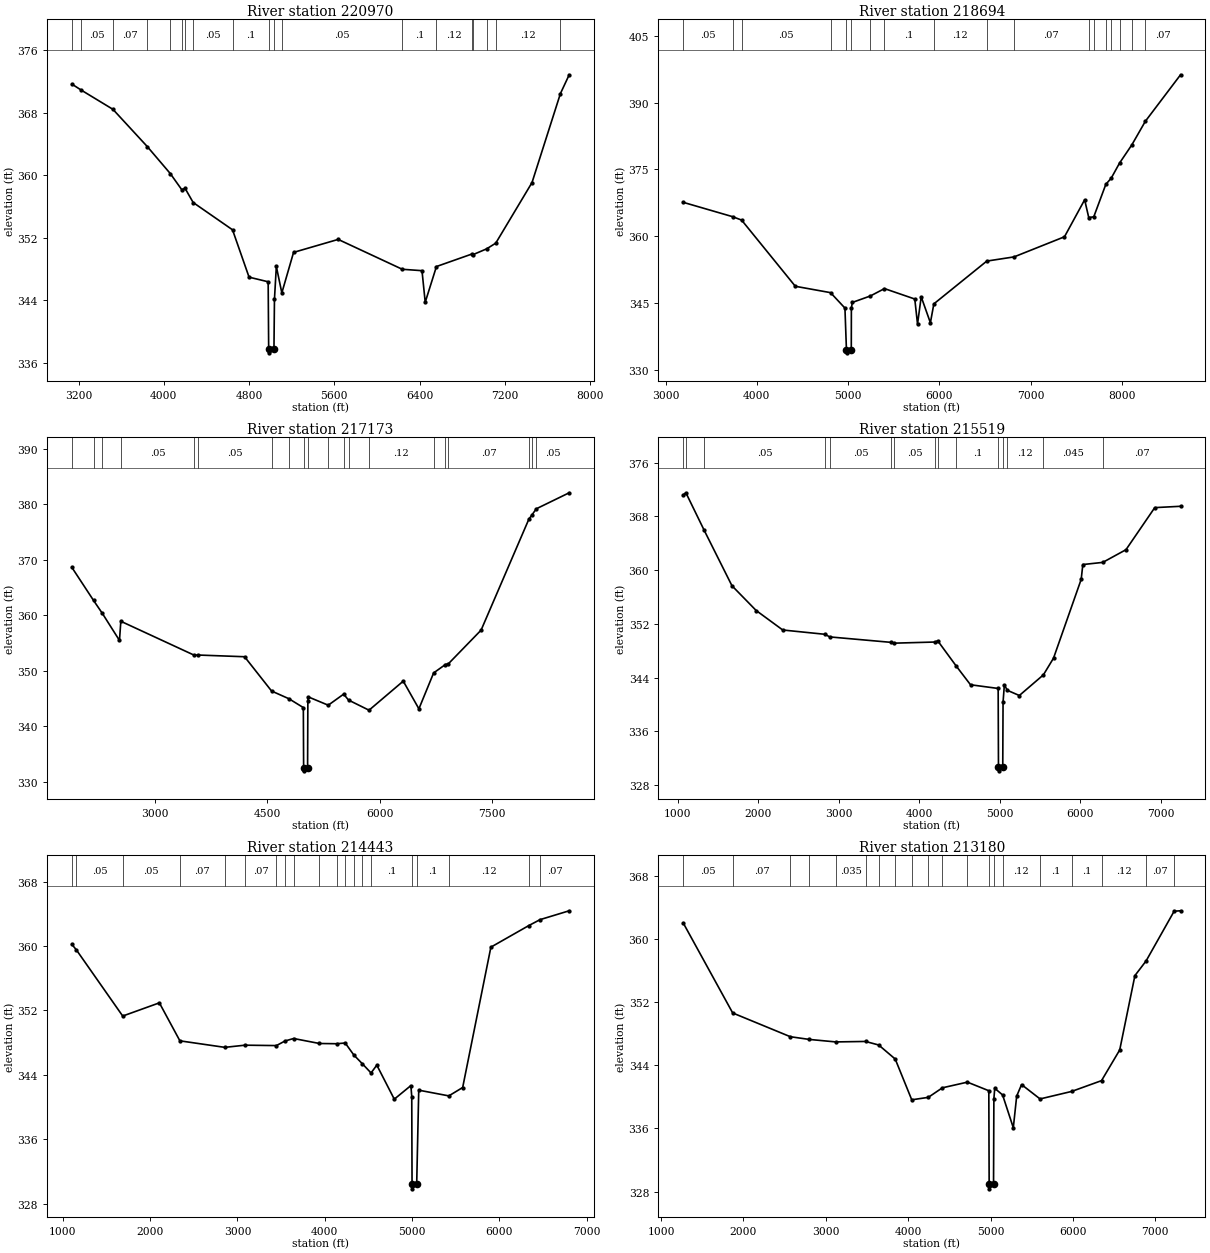
Type RM Length L Ch R = 1 ,220970  ,2276,2276,2276
BEGIN DESCRIPTION:
PEACH CREEK9097
END DESCRIPTION:
XS GIS Cut Line= 3
      2527162.89      13830234.9      2525162.89      13831047.4
      2522675.03       13830725.
#Sta/Elev= 30
  3136.6  371.64    3227  370.85  3522.2  368.41  3844.9  363.64    4060   360.2
  4167.6  358.14  4199.3   358.3  4275.1  356.49  4644.4     353  4799.7  346.94
    4979  346.35  4983.7  337.76  4984.7  337.26  5033.3  337.76    5038   344.1
  5055.6  348.31  5107.3  344.93  5217.3  350.11  5636.1  351.77  6237.5  347.95
  6422.6  347.77  6452.8  343.73  6558.1   348.3  6888.9  349.89  6897.8   349.8
  7028.9  350.56  7114.7  351.29    7455  359.04  7721.7  370.43    7804  372.83
#Mann= 19 ,-1 , 0
  3136.6     .07       0    3227     .05       0  3522.2     .07       0
  3844.9     .05       0    4060    .035       0  4167.6     .05       0
  4199.3    .035       0  4275.1     .05       0  4644.4      .1       0
  4983.7     .05       0  5033.3      .1       0  5107.3     .05       0
  6237.5      .1       0  6558.1     .12       0  6888.9    .035       0
  6897.8     .12       0  7028.9    .035       0  7114.7     .12       0
  7721.7     .07       0
Bank Sta=4983.7,5033.3
XS Rating Curve= 0 ,0
Exp/Cntr=0.3,0.1

Type RM Length L Ch R = 1 ,218694  ,1521,1521,1521
BEGIN DESCRIPTION:
B19966
END DESCRIPTION:
XS GIS Cut Line= 3
      2526975.37      13829359.9      2523225.39      13829797.4
      2521559.41       13829964.
#Sta/Elev= 30
  3192.9  367.58  3733.4  364.36  3832.9  363.59  4421.5  348.72  4807.4  347.29
  4965.2  343.82  4981.8  334.37  4982.9  333.77  5034.7  334.37  5035.7  343.76
  5045.7  345.09  5243.4  346.54  5398.4   348.2  5730.4  345.86  5760.6  340.23
  5800.8  346.36  5901.5  340.53  5939.5  344.77  6519.5  354.38  6818.1  355.32
  7370.7  359.84  7591.8  368.15  7636.5  364.17  7691.6  364.32  7823.7  371.61
  7883.3  373.02    7974  376.39    8109  380.49  8257.1  385.79  8642.6  396.23
#Mann= 18 ,-1 , 0
  3192.9     .05       0  3733.4    .035       0  3832.9     .05       0
  4807.4      .1       0  4981.8     .05       0  5034.7      .1       0
  5243.4     .05       0  5398.4      .1       0  5939.5     .12       0
  6519.5    .035       0  6818.1     .07       0  7636.5     .12       0
  7691.6     .07       0  7823.7     .12       0  7883.3     .07       0
    7974    .035       0    8109     .05       0  8257.1     .07       0
Bank Sta=4981.8,5034.7
XS Rating Curve= 0 ,0
Exp/Cntr=0.3,0.1

Type RM Length L Ch R = 1 ,217173  ,1654,1654,1654
BEGIN DESCRIPTION:
B19965
END DESCRIPTION:
XS GIS Cut Line= 3
      2528267.06     13828193.23      2524183.72     13828630.73
      2521683.77     13829026.56
#Sta/Elev= 30
  1890.2  368.62  2179.3  362.68  2298.2  360.32  2525.9  355.47    2544  358.92
  3524.1  352.81  3568.6  352.85  4195.4  352.54  4555.9  346.37  4787.9  344.98
  4979.8  343.39  4983.6  332.61  4984.6  332.01  5036.5  332.61  5040.2  344.66
  5048.3   345.3  5312.1  343.82  5517.8  345.81  5583.4  344.74  5856.5  342.92
  6313.2  348.15  6522.1  343.17  6718.8  349.63  6876.1  351.14  6916.9  351.29
  7352.3  357.33    7989  377.27  8026.4  377.97  8089.2  379.16    8528  382.04
#Mann= 20 ,-1 , 0
  1890.2     .07       0  2179.3     .05       0  2298.2     .07       0
    2544     .05       0  3524.1    .035       0  3568.6     .05       0
  4555.9     .12       0  4787.9      .1       0  4983.6     .05       0
  5036.5      .1       0  5312.1     .05       0  5517.8     .12       0
  5583.4      .1       0  5856.5     .12       0  6718.8     .07       0
  6876.1     .12       0  6916.9     .07       0    7989     .05       0
  8026.4    .035       0  8089.2     .05       0
Bank Sta=4983.6,5036.5
XS Rating Curve= 0 ,0
Exp/Cntr=0.3,0.1

Type RM Length L Ch R = 1 ,215519  ,1076,1076,1076
BEGIN DESCRIPTION:
B19964
END DESCRIPTION:
XS GIS Cut Line= 3
      2528350.39      13827547.4      2524767.06     13827651.57
       2522204.6     13828026.56
#Sta/Elev= 30
  1069.5  371.21    1103  371.52  1330.7  365.92  1675.1  357.68  1975.3     354
  2305.4   351.1  2829.1  350.46  2889.1  350.07  3650.6  349.26  3687.7  349.14
    4198  349.31  4229.6  349.49  4460.6  345.71  4636.4  342.95  4979.8   342.4
  4983.6  330.74  4984.7  330.14  5036.8  330.74  5040.5  340.37  5056.8  342.91
  5094.4  342.12  5242.6  341.35  5541.2  344.42  5667.1  346.91  6010.7  358.64
  6030.9  360.84  6278.4  361.16  6566.6  363.05  6923.9  369.31  7244.1  369.51
#Mann= 15 ,-1 , 0
  1069.5     .05       0    1103    .035       0  1330.7     .05       0
  2829.1     .07       0  2889.1     .05       0  3650.6    .035       0
  3687.7     .05       0    4198    .035       0  4229.6     .05       0
  4460.6      .1       0  4983.6     .05       0  5036.8      .1       0
  5094.4     .12       0  5541.2    .045       0  6278.4     .07       0
Bank Sta=4983.6,5036.8
XS Rating Curve= 0 ,0
Exp/Cntr=0.3,0.1

Type RM Length L Ch R = 1 ,214443  ,1263,1263,1263
BEGIN DESCRIPTION:
B19963
END DESCRIPTION:
XS GIS Cut Line= 3
      2528267.08      13826672.4      2524017.06      13826672.4
      2522746.23      13827359.9
#Sta/Elev= 30
  1104.4  360.21  1156.3  359.52  1686.9   351.3  2106.5  352.94  2341.6  348.22
  2855.7  347.41  3087.1  347.68  3446.7  347.63  3545.2   348.2  3643.7  348.51
  3939.2  347.89  4136.3  347.86  4234.8  347.95  4333.3  346.46  4431.8  345.36
  4530.3  344.23  4596.5   345.2  4796.5  340.97  4986.5  342.66  4996.5   341.3
  4999.9  330.43  5000.9  329.83  5053.1  330.43  5076.5  342.09    5421  341.38
  5579.5  342.42  5902.5  359.86  6336.4  362.54  6465.7  363.28  6799.3  364.38
#Mann= 20 ,-1 , 0
  1104.4     .07       0  1156.3     .05       0  1686.9     .05       0
  2341.6     .07       0  2855.7     .12       0  3087.1     .07       0
  3446.7    .035       0  3545.2     .07       0  3643.7    .035       0
  3939.2     .07       0  4136.3    .035       0  4234.8     .12       0
  4333.3     .05       0  4431.8    .035       0  4530.3      .1       0
  4999.9     .05       0  5053.1      .1       0    5421     .12       0
  6336.4     .07       0  6465.7     .07       0
Bank Sta=4999.9,5053.1
XS Rating Curve= 0 ,0
Exp/Cntr=0.3,0.1

Type RM Length L Ch R = 1 ,213180  ,1874,1874,1874
BEGIN DESCRIPTION:
B19962
END DESCRIPTION:
XS GIS Cut Line= 3
      2528162.87     13826401.56      2524162.89      13825484.9
      2522912.88     13826964.08
#Sta/Elev= 30
  1267.7  362.06    1869  350.64    2569  347.63  2796.5  347.29  3120.3  346.97
  3482.2  347.03  3641.8  346.58  3842.6   344.8  4043.4  339.63  4244.2  339.94
  4415.2  341.15  4719.3  341.87  4979.4  340.78  4983.5  328.94  4984.6  328.34
  5036.8  328.94  5040.9  339.75  5051.2  341.09  5146.5  340.25  5276.9  336.09
  5317.9   340.1    5377  341.56  5601.9  339.74  5984.7  340.69  6348.2  342.06
  6569.1  345.95  6753.7  355.38  6889.5  357.24  7230.3  363.55    7308   363.6
#Mann= 20 ,-1 , 0
  1267.7     .05       0    1869     .07       0    2569     .05       0
  2796.5     .07       0  3120.3    .035       0  3482.2    .035       0
  3641.8     .05       0  3842.6    .035       0  4043.4     .12       0
  4244.2     .05       0  4415.2     .05       0  4719.3      .1       0
  4983.5     .05       0  5036.8      .1       0  5146.5     .12       0
  5601.9      .1       0  5984.7      .1       0  6348.2     .12       0
  6889.5     .07       0  7230.3     .07       0
Bank Sta=4983.5,5036.8
XS Rating Curve= 0 ,0
Exp/Cntr=0.3,0.1

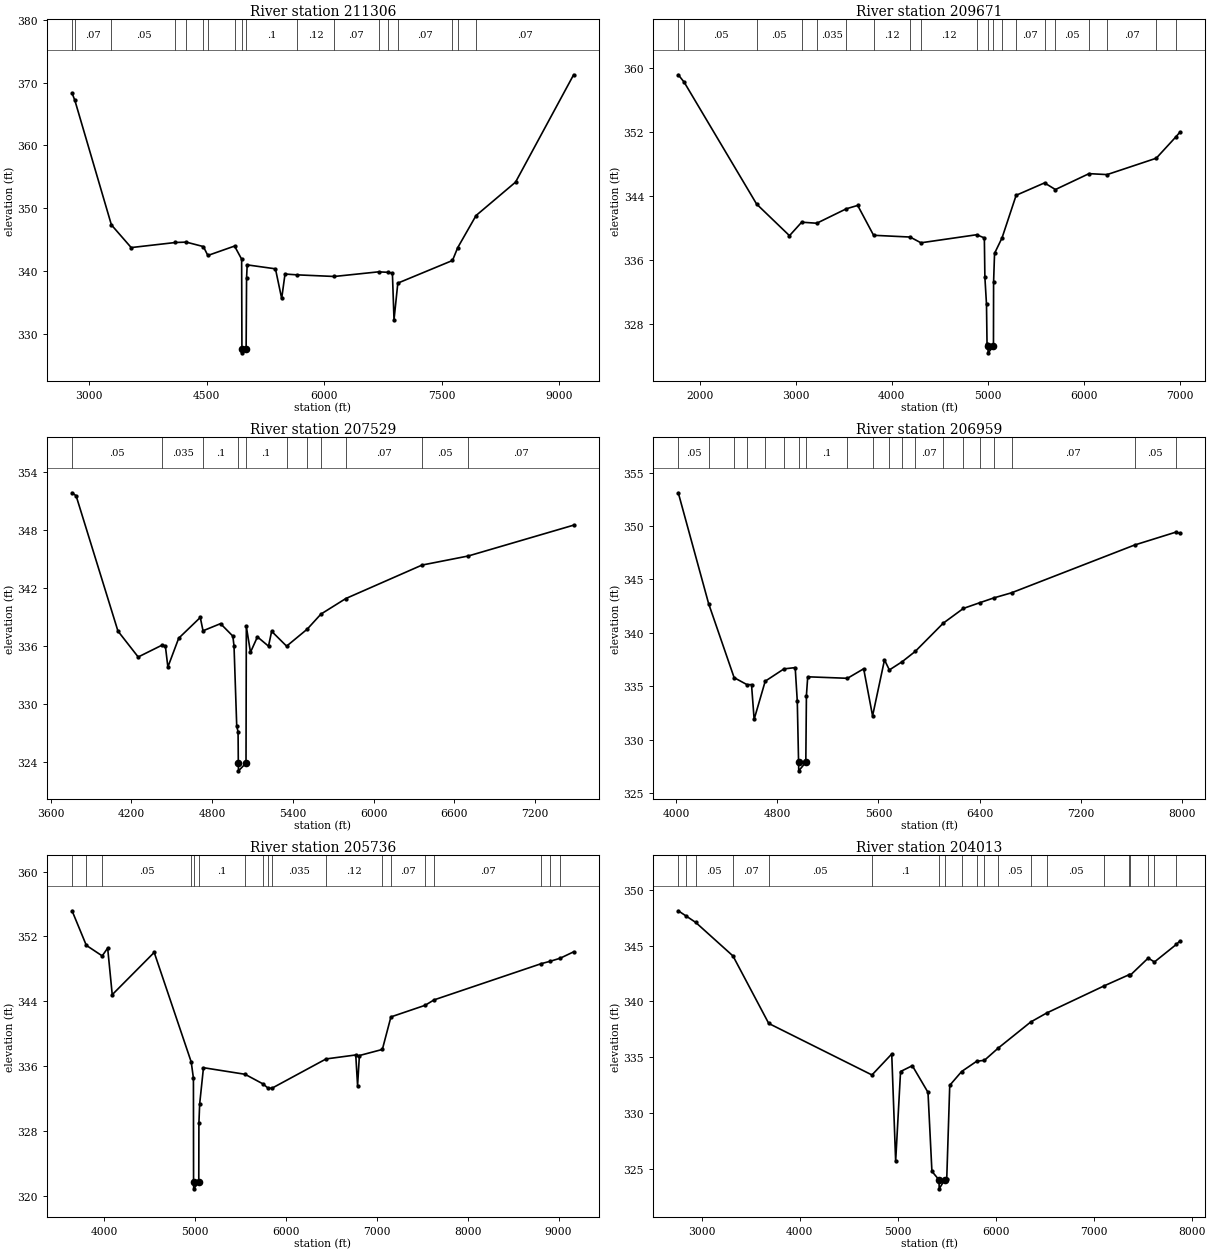
Type RM Length L Ch R = 1 ,211306  ,1635,1635,1635
BEGIN DESCRIPTION:
PEACH CREEK9090
END DESCRIPTION:
XS GIS Cut Line= 5
      2527830.02     13824672.65      2525648.48     13824462.06
      2525598.47     13824482.83      2525148.53     13824575.24
      2521454.57     13824401.57
#Sta/Elev= 30
    2783  368.35  2819.2  367.17  3285.2  347.33  3537.8  343.71    4103  344.52
  4240.8  344.58  4459.2  343.87  4516.5  342.45  4857.6  343.95    4948  341.86
  4951.6  327.52  4952.7  326.92  5005.2  327.52  5010.9  338.86  5018.9  340.95
  5379.5  340.32  5459.1  335.59  5501.7  339.49  5653.8  339.36  6130.4   339.1
  6695.8  339.84  6819.8  339.76  6872.7  339.62  6893.2   332.2  6941.8  338.04
  7639.8  341.65  7706.2  343.69  7940.6  348.82    8445  354.15  9186.2  371.27
#Mann= 18 ,-1 , 0
    2783    .035       0  2819.2     .07       0  3285.2     .05       0
    4103    .035       0  4240.8     .07       0  4459.2    .035       0
  4516.5     .07       0  4857.6      .1       0  4951.6     .05       0
  5005.2      .1       0  5653.8     .12       0  6130.4     .07       0
  6695.8      .1       0  6819.8     .12       0  6941.8     .07       0
  7639.8    .035       0  7706.2     .05       0  7940.6     .07       0
Bank Sta=4951.6,5005.2
XS Rating Curve= 0 ,0
Exp/Cntr=0.3,0.1

Type RM Length L Ch R = 1 ,209671  ,2142,2142,2142
BEGIN DESCRIPTION:
PEACH CREEK9089
END DESCRIPTION:
XS GIS Cut Line= 4
      2527942.87     13823648.35      2524766.65     13823754.18
        2524725.       13823775.      2522725.04       13823775.
#Sta/Elev= 30
  1775.9   359.2  1837.4  358.27  2591.9  343.01  2934.4  339.05  3061.3  340.74
  3218.6  340.61  3526.6  342.42  3644.8  342.84  3810.5   339.1  4190.8  338.88
  4303.7  338.16  4884.3  339.17  4964.1  338.77  4969.7  333.84  4986.5  330.45
  4992.1  325.46  5001.9  325.18  5003.2  324.38    5059  325.18  5060.4  333.26
  5070.4  336.84  5148.5  338.78  5295.3  344.11  5590.8  345.66  5704.5  344.83
  6054.3  346.82  6242.5   346.7  6754.6  348.75  6957.2   351.4  7000.4     352
#Mann= 20 ,-1 , 0
  1775.9    .035       0  1837.4     .05       0  2591.9     .05       0
  3061.3     .07       0  3218.6    .035       0  3526.6     .05       0
  3810.5     .12       0  4190.8    .035       0  4303.7     .12       0
  4884.3      .1       0  5001.9     .05       0    5059      .1       0
  5148.5     .12       0  5295.3     .07       0  5590.8     .05       0
  5704.5     .05       0  6054.3     .07       0  6242.5     .07       0
  6754.6     .05       0  6957.2     .07       0
Bank Sta=5001.9,5059
XS Rating Curve= 0 ,0
Exp/Cntr=0.3,0.1

Type RM Length L Ch R = 1 ,207529  ,570,570,570
BEGIN DESCRIPTION:
PEACH CREEK9088
END DESCRIPTION:
XS GIS Cut Line= 3
      2526774.97       13822675.        2525525.       13822775.
      2523125.03     13823374.99
#Sta/Elev= 30
  3759.4  351.86  3789.5  351.55  4100.5  337.55  4250.9  334.87  4428.8   336.1
  4452.8  336.01  4471.6  333.83  4551.9  336.81  4712.4  338.96  4732.8  337.58
  4862.9  338.32  4954.4  337.03  4963.2     336  4983.3  327.72  4993.3  327.12
  4995.1  323.89  4996.4  323.09  5052.3  323.89  5054.6  338.03  5085.5  335.36
  5137.1  336.95  5219.5  335.99  5242.7  337.53    5354  335.99  5507.1  337.75
  5609.4  339.31  5794.4  340.92  6360.4  344.38  6704.2  345.32  7487.2  348.51
#Mann= 11 ,-1 , 0
  3759.4     .05       0  4428.8    .035       0  4732.8      .1       0
  4995.1     .05       0  5052.3      .1       0    5354     .12       0
  5507.1    .035       0  5609.4     .05       0  5794.4     .07       0
  6360.4     .05       0  6704.2     .07       0
Bank Sta=4995.1,5052.3
XS Rating Curve= 0 ,0
Exp/Cntr=0.3,0.1

Type RM Length L Ch R = 1 ,206959  ,1223,1223,1223
BEGIN DESCRIPTION:
PEACH CREEK9087
END DESCRIPTION:
XS GIS Cut Line= 3
      2526675.04     13822074.99        2525725.       13822325.
      2522824.97     13823025.01
#Sta/Elev= 30
  4017.3  353.11  4257.2  342.74  4458.9  335.81  4561.6  335.15  4596.4  335.16
  4617.1  331.91  4704.8  335.48    4853  336.63  4941.8  336.75  4958.3   333.6
  4968.5  327.89  4969.8  327.09  5025.7  327.89  5030.5  334.14  5040.8  335.89
    5355  335.75  5483.2  336.64  5553.6  332.23  5647.8  337.47  5686.4  336.53
  5788.4  337.31  5890.4  338.26  6112.6  340.91  6271.8  342.29  6400.6  342.82
  6511.7  343.27  6652.2  343.75  7624.9  348.22  7949.6  349.42    7983  349.32
#Mann= 20 ,-1 , 0
  4017.3     .05       0  4257.2     .07       0  4458.9     .07       0
  4561.6     .12       0  4704.8     .12       0    4853      .1       0
  4968.5     .05       0  5025.7      .1       0    5355     .12       0
  5553.6     .07       0  5686.4     .12       0  5788.4    .035       0
  5890.4     .07       0  6112.6     .05       0  6271.8     .05       0
  6400.6     .07       0  6511.7    .035       0  6652.2     .07       0
  7624.9     .05       0  7949.6     .07       0
Bank Sta=4968.5,5025.7
XS Rating Curve= 0 ,0
Exp/Cntr=0.3,0.1

Type RM Length L Ch R = 1 ,205736  ,1723,1723,1723
BEGIN DESCRIPTION:
B19961
END DESCRIPTION:
XS GIS Cut Line= 3
      2527475.35     13821255.74      2525517.06     13821443.23
      2521975.37     13821755.73
#Sta/Elev= 30
  3642.8  355.17  3799.8  350.91  3974.7  349.61  4034.9  350.57  4085.2  344.83
  4547.3  350.04  4954.8  336.54  4979.2  334.53  4980.7   321.7    4982   320.9
  5038.1   321.7  5039.5  328.98    5048  331.37  5089.7  335.83  5547.3  335.02
  5745.6  333.83  5799.7  333.32  5843.5   333.3  6439.6  336.91  6766.6   337.4
  6786.7  333.62  6806.7  337.33  7059.4  338.08  7153.8  342.09  7530.1  343.52
  7629.2  344.19  8808.4  348.65  8908.5  348.95  9017.1  349.32  9165.5  350.11
#Mann= 18 ,-1 , 0
  3642.8     .05       0  3799.8     .07       0  3974.7     .05       0
  4954.8      .1       0  4980.7     .05       0  5038.1      .1       0
  5547.3     .12       0  5745.6    .035       0  5799.7     .12       0
  5843.5    .035       0  6439.6     .12       0  7059.4     .05       0
  7153.8     .07       0  7530.1     .05       0  7629.2     .07       0
  8808.4     .05       0  8908.5     .07       0  9017.1     .05       0
Bank Sta=4980.7,5038.1
XS Rating Curve= 0 ,0
Exp/Cntr=0.3,0.1

Type RM Length L Ch R = 1 ,204013  ,1960,1960,1960
BEGIN DESCRIPTION:
B19960
END DESCRIPTION:
XS GIS Cut Line= 3
      2527412.87      13820297.4      2524746.22      13820297.4
      2522579.77     13821443.12
#Sta/Elev= 30
  2762.3  348.12  2838.9  347.67  2939.7  347.08  3320.4  344.07  3685.2  338.02
  4738.5   333.4  4940.2  335.28  4980.2  325.66  5030.2  333.71  5150.2  334.23
  5310.2  331.84  5350.2  324.76  5422.9  323.99  5424.2  323.19  5480.3  323.99
  5501.3  324.05  5532.1  332.47  5653.6  333.71  5807.2  334.63  5885.5  334.71
  6026.7  335.81  6358.5  338.15  6520.1  338.95    7108  341.39  7364.9   342.4
  7376.2  342.36    7557  343.88  7620.4  343.53  7843.4   345.1  7879.7  345.41
#Mann= 20 ,-1 , 0
  2762.3     .05       0  2838.9     .07       0  2939.7     .05       0
  3320.4     .07       0  3685.2     .05       0  4738.5      .1       0
  5422.9     .05       0  5480.3      .1       0  5653.6     .07       0
  5807.2     .05       0  5885.5     .07       0  6026.7     .05       0
  6358.5     .07       0  6520.1     .05       0    7108     .07       0
  7364.9    .035       0  7376.2     .05       0    7557    .035       0
  7620.4     .12       0  7843.4     .07       0
Bank Sta=5422.9,5480.3
XS Rating Curve= 0 ,0
Exp/Cntr=0.3,0.1

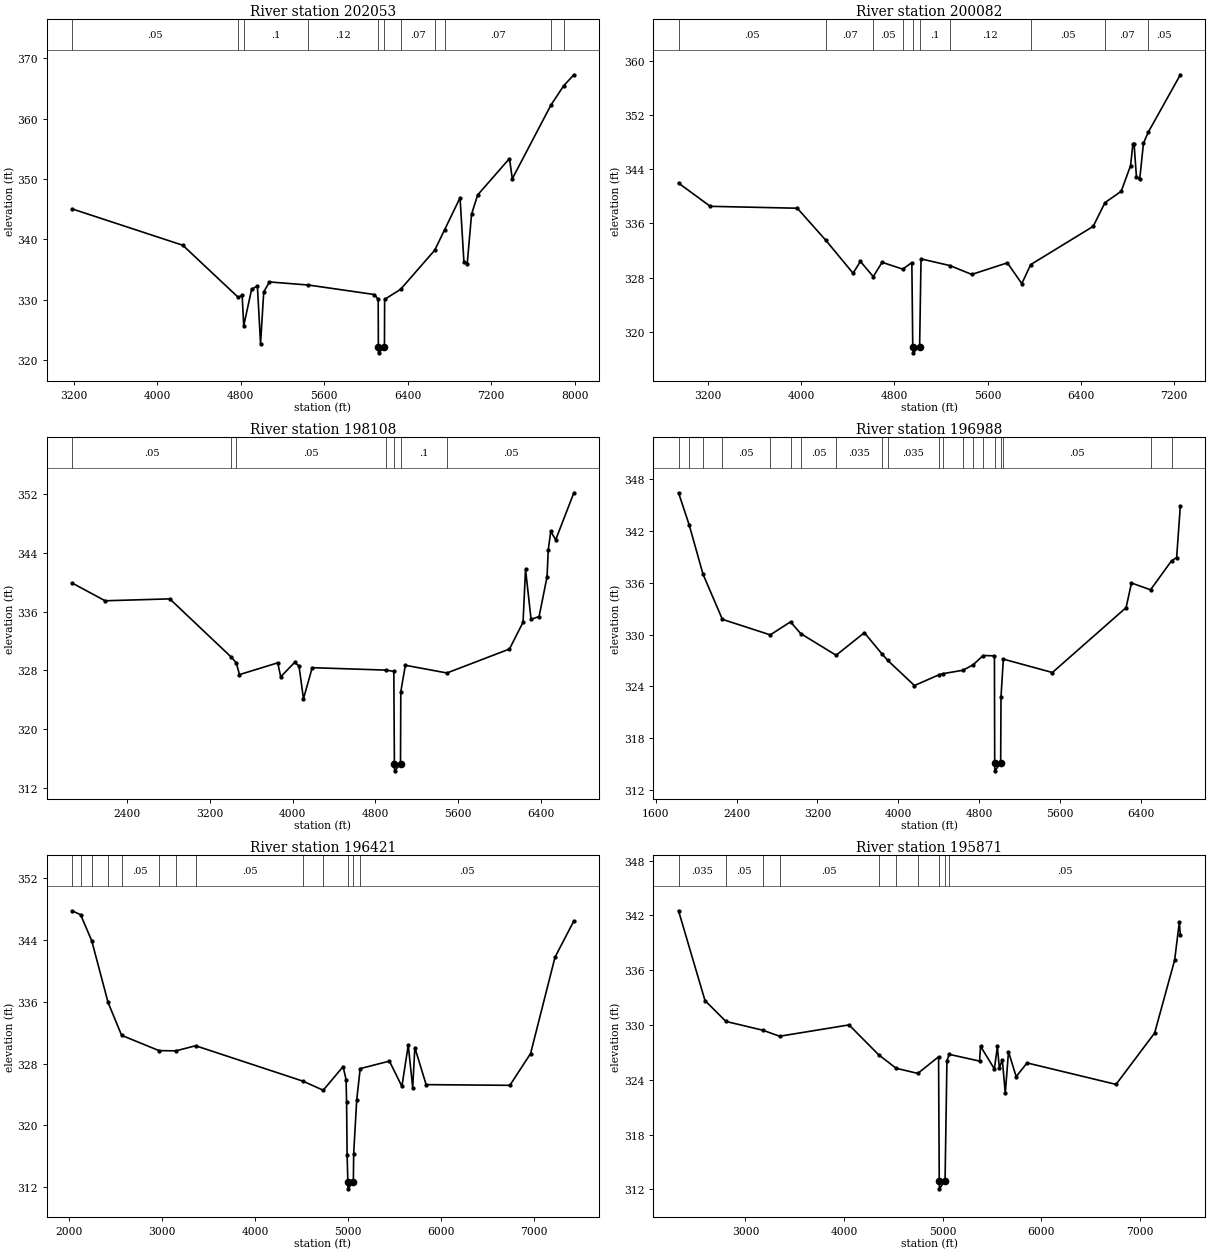
Type RM Length L Ch R = 1 ,202053  ,1971,1971,1971
BEGIN DESCRIPTION:
B19959
END DESCRIPTION:
XS GIS Cut Line= 3
      2527225.42     13819880.74      2525329.56      13819172.4
      2522621.26     13818526.57
#Sta/Elev= 30
  3184.8  345.05  4245.8  339.03  4777.1  330.41  4814.4  330.75  4829.6  325.73
  4905.3  331.75  4960.5  332.29  4990.8  322.74  5021.4  331.32  5076.4  332.96
  5449.8  332.45  6081.6  330.88    6118  330.07  6119.8  322.13  6121.2  321.23
    6178  322.13  6179.7  330.08  6332.8  331.74  6659.9  338.22  6754.3  341.59
  6902.4  346.89  6939.4  336.31  6971.3     336  7012.4  344.15  7070.9  347.35
    7376  353.38  7403.1  350.04    7772  362.19  7894.4   365.4  7992.9  367.24
#Mann= 11 ,-1 , 0
  3184.8     .05       0  4777.1     .07       0  4829.6      .1       0
  5449.8     .12       0  6119.8     .05       0    6178     .12       0
  6332.8     .07       0  6659.9     .05       0  6754.3     .07       0
    7772    .035       0  7894.4     .07       0
Bank Sta=6119.8,6178
XS Rating Curve= 0 ,0
Exp/Cntr=0.3,0.1

Type RM Length L Ch R = 1 ,200082  ,1974,1974,1974
BEGIN DESCRIPTION:
B19958
END DESCRIPTION:
XS GIS Cut Line= 3
      2527183.74     13819547.41      2525475.39      13818234.9
      2523329.81     13818026.59
#Sta/Elev= 30
  2945.8  341.95    3218  338.52  3965.7  338.24  4210.6  333.51  4444.9  328.65
  4507.9  330.39  4618.3  328.15  4694.3  330.26  4871.6  329.25  4949.8  330.22
  4957.6   317.8  4959.1   316.9  5016.5   317.8  5028.7  330.76  5276.2  329.78
  5464.3  328.47  5770.2  330.18  5894.2  327.11  5970.6  329.92  6507.1  335.56
  6608.9  339.07  6748.2  340.74  6828.6  344.54  6848.7  347.77  6858.8  347.68
  6878.8  342.88    6907  342.52  6939.1  347.82  6980.5  349.46  7255.8  357.93
#Mann= 10 ,-1 , 0
  2945.8     .05       0  4210.6     .07       0  4618.3     .05       0
  4871.6      .1       0  4957.6     .05       0  5016.5      .1       0
  5276.2     .12       0  5970.6     .05       0  6608.9     .07       0
  6980.5     .05       0
Bank Sta=4957.6,5016.5
XS Rating Curve= 0 ,0
Exp/Cntr=0.3,0.1

Type RM Length L Ch R = 1 ,198108  ,1120,1120,1120
BEGIN DESCRIPTION:
PEACH CREEK9079
END DESCRIPTION:
XS GIS Cut Line= 3
      2527324.97     13819424.97        2525325.       13817025.
      2523725.04     13817674.98
#Sta/Elev= 30
  1867.3   339.9  2186.8  337.48  2811.6  337.74  3406.2  329.82  3454.3  329.06
  3485.9  327.44  3855.6  329.04  3884.3  327.14  4018.3  329.09  4061.3  328.61
  4104.2  324.15  4188.9  328.38  4906.5  328.05  4977.7  327.87  4983.4  315.25
  4984.9  314.35  5042.4  315.25  5045.3  325.12  5089.1  328.71  5491.2  327.66
  6095.8  330.92    6227  334.56  6251.1  341.74  6304.7  334.95  6382.3  335.34
  6459.3  340.76  6470.7   344.4  6494.8  346.91  6542.9  345.78  6718.3  352.17
#Mann= 7 ,-1 , 0
  1867.3     .05       0  3406.2     .07       0  3454.3     .05       0
  4906.5      .1       0  4983.4     .05       0  5042.4      .1       0
  5491.2     .05       0
Bank Sta=4983.4,5042.4
XS Rating Curve= 0 ,0
Exp/Cntr=0.3,0.1

Type RM Length L Ch R = 1 ,196988  ,567,567,567
BEGIN DESCRIPTION:
PEACH CREEK9078
END DESCRIPTION:
XS GIS Cut Line= 3
      2528274.97     13816824.99        2525175.       13816125.
      2523574.98     13816925.01
#Sta/Elev= 30
  1825.9  346.44    1931  342.73  2067.9  337.02  2259.7  331.78  2733.8  329.98
  2934.5  331.49  3034.8  330.13  3385.7  327.62  3665.3  330.23  3837.6   327.8
    3896  327.03  4161.1  324.11  4406.2  325.37  4439.6  325.48  4640.3  325.88
  4740.7   326.5    4841  327.59  4952.7  327.55  4955.4  315.13  4956.8  314.23
  5014.4  315.13  5017.9  322.83  5040.9  327.17  5526.6  325.62  6256.1  333.14
  6309.2  335.99  6498.1   335.2  6706.2  338.57  6756.4  338.94  6792.8   344.9
#Mann= 20 ,-1 , 0
  1825.9     .07       0    1931    .035       0  2067.9     .07       0
  2259.7     .05       0  2733.8     .07       0  2934.5    .035       0
  3034.8     .05       0  3385.7    .035       0  3837.6     .07       0
    3896    .035       0  4406.2     .07       0  4439.6     .12       0
  4640.3      .1       0  4740.7     .12       0    4841      .1       0
  4955.4     .05       0  5014.4      .1       0  5040.9     .05       0
  6498.1     .05       0  6706.2    .035       0
Bank Sta=4955.4,5014.4
XS Rating Curve= 0 ,0
Exp/Cntr=0.3,0.1

Type RM Length L Ch R = 1 ,196421  ,550,550,550
BEGIN DESCRIPTION:
PEACH CREEK9077
END DESCRIPTION:
XS GIS Cut Line= 3
      2528375.04     13816775.02        2525575.       13815775.
      2523174.97     13815374.99
#Sta/Elev= 30
  2027.8   347.8  2120.1  347.28    2240   343.9  2415.3  335.93  2561.6  331.65
  2964.9  329.67  3145.8  329.64  3359.2   330.3  4518.2   325.7  4733.6  324.53
    4948   327.6  4979.8  325.91  4985.7  322.95    4991  316.17  4999.4  312.65
  5000.9  311.75  5058.4  312.65  5061.9  316.33  5094.8  323.31  5132.3  327.34
  5447.1  328.31  5581.5  325.03  5649.9  330.38    5698  324.86  5720.9  330.07
  5842.5  325.26  6744.8  325.17  6967.8  329.29  7231.4  341.79  7434.2  346.48
#Mann= 13 ,-1 , 0
  2027.8     .05       0  2120.1     .07       0    2240    .035       0
  2415.3     .07       0  2561.6     .05       0  2964.9    .035       0
  3145.8     .07       0  3359.2     .05       0  4518.2     .07       0
  4733.6      .1       0  4999.4     .05       0  5058.4      .1       0
  5132.3     .05       0
Bank Sta=4999.4,5058.4
XS Rating Curve= 0 ,0
Exp/Cntr=0.3,0.1

Type RM Length L Ch R = 1 ,195871  ,555,555,555
BEGIN DESCRIPTION:
PEACH CREEK9076
END DESCRIPTION:
XS GIS Cut Line= 3
      2528174.99     13816524.99        2525775.       13815325.
      2523374.99       13815125.
#Sta/Elev= 30
  2321.3   342.5  2589.6  332.68  2802.1  330.39  3176.1  329.43  3346.6  328.77
  4051.4  330.01  4351.9  326.74  4528.4  325.27  4749.3   324.7  4959.8  326.52
  4966.7  312.97  4968.1  312.07  5025.7  312.97  5044.7  326.06  5067.2  326.79
  5375.8  326.05  5385.9  327.67  5526.4  325.19  5556.5  327.65  5576.5  325.28
  5606.6   326.2  5636.8  322.55  5669.4  327.08  5747.1  324.35  5857.5  325.85
  6760.6   323.5    7152  329.12  7355.2   337.1  7402.9  341.26  7412.9  339.83
#Mann= 10 ,-1 , 0
  2321.3    .035       0  2802.1     .05       0  3176.1     .07       0
  3346.6     .05       0  4351.9     .07       0  4528.4     .12       0
  4749.3      .1       0  4966.7     .05       0  5025.7      .1       0
  5067.2     .05       0
Bank Sta=4966.7,5025.7
XS Rating Curve= 0 ,0
Exp/Cntr=0.3,0.1

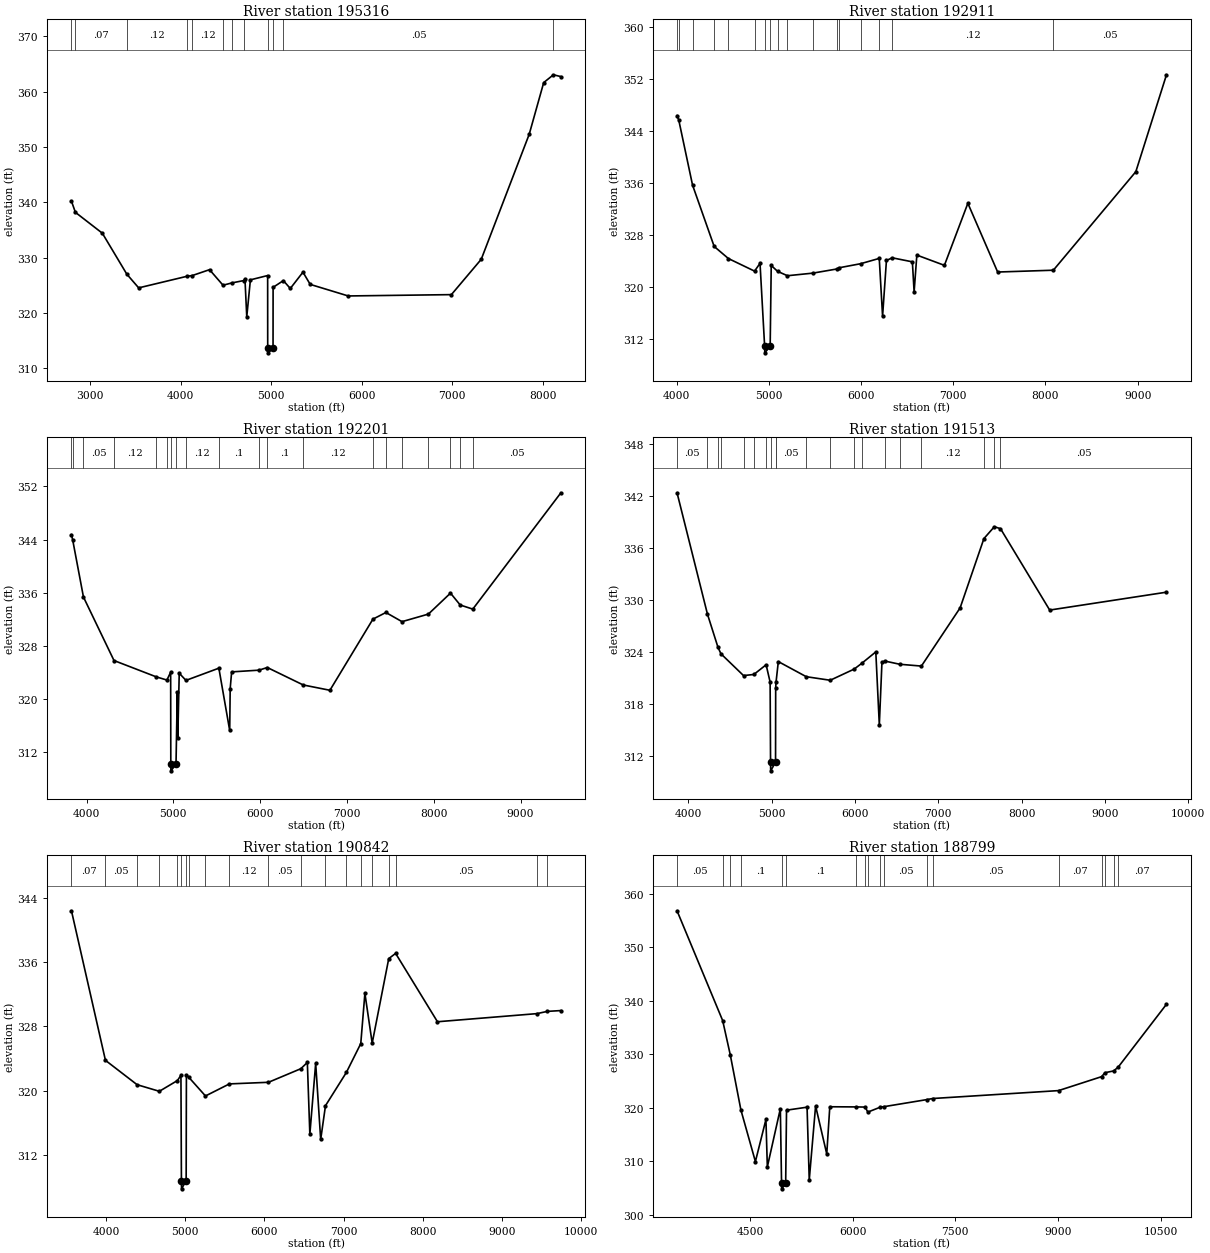
Type RM Length L Ch R = 1 ,195316  ,2405,2405,2405
BEGIN DESCRIPTION:
PEACH CREEK9075
END DESCRIPTION:
XS GIS Cut Line= 3
      2528125.01       13814625.        2525925.       13814825.
      2522725.04       13814925.
#Sta/Elev= 30
    2791  340.19  2834.6  338.17  3132.4   334.4    3403     327  3534.1  324.52
  4064.4   326.6  4127.1  326.75  4317.3  327.81  4466.5     325  4565.7  325.42
  4698.5  325.85  4708.9  326.17    4729   319.3  4769.1  325.97  4959.9  326.75
  4960.5  313.68    4962  312.78  5019.5  313.68  5020.1  324.62  5133.6  325.83
  5210.2  324.41  5350.2  327.36  5430.3  325.15  5850.5  323.06    6991   323.3
  7321.2  329.69  7851.5  352.29  8011.5  361.62  8118.9  363.03  8201.6   362.7
#Mann= 12 ,-1 , 0
    2791     .12       0  2834.6     .07       0    3403     .12       0
  4064.4     .07       0  4127.1     .12       0  4466.5     .07       0
  4565.7     .12       0  4698.5      .1       0  4960.5     .05       0
  5019.5      .1       0  5133.6     .05       0  8118.9    .035       0
Bank Sta=4960.5,5019.5
XS Rating Curve= 0 ,0
Exp/Cntr=0.3,0.1

Type RM Length L Ch R = 1 ,192911  ,710,710,710
BEGIN DESCRIPTION:
PEACH CREEK9074
END DESCRIPTION:
XS GIS Cut Line= 3
      2528074.97       13813225.        2527075.       13813225.
        2523075.       13814825.
#Sta/Elev= 30
  4004.6  346.37  4023.2  345.69  4172.8  335.66  4407.3  326.21  4561.5  324.35
  4845.3  322.41  4904.6  323.61  4954.6  310.82  4956.1  309.82  5014.6  310.82
  5026.1  323.28  5094.5  322.38  5201.8   321.7  5477.2   322.1  5738.2  322.74
  5763.6  322.93    5995  323.55  6197.6  324.37  6233.7  315.46  6275.5  324.05
  6338.6  324.46  6556.8  323.84  6575.7  319.22  6605.3  324.88  6904.2   323.3
  7158.6  332.86  7481.7  322.27  8085.7  322.55  8980.2  337.73  9312.7  352.66
#Mann= 17 ,-1 , 0
  4004.6     .05       0  4023.2     .07       0  4172.8     .05       0
  4407.3     .07       0  4561.5     .12       0  4845.3      .1       0
  4954.6     .05       0  5014.6      .1       0  5094.5    .035       0
  5201.8     .12       0  5477.2    .035       0  5738.2     .12       0
  5763.6    .035       0    5995     .12       0  6197.6      .1       0
  6338.6     .12       0  8085.7     .05       0
Bank Sta=4954.6,5014.6
XS Rating Curve= 0 ,0
Exp/Cntr=0.3,0.1

Type RM Length L Ch R = 1 ,192201  ,688,688,688
BEGIN DESCRIPTION:
PEACH CREEK9073
END DESCRIPTION:
XS GIS Cut Line= 3
      2528074.97     13813174.98        2527075.       13812575.
        2523075.       13814575.
#Sta/Elev= 30
    3826  344.74  3840.5  343.93  3964.3  335.34  4316.2  325.77  4803.4  323.31
  4925.5  322.83  4968.8  324.01  4970.5  310.15    4972  309.15  5030.5  310.15
  5045.3  320.97  5050.9  314.03  5067.6  323.86    5145  322.78  5524.2  324.62
    5649  315.23  5654.6  321.54  5671.4  324.06  5986.5  324.32  6082.3  324.72
    6496  322.09  6803.4  321.29    7299  332.01  7448.3  333.01    7634  331.63
  7937.8  332.77  8192.5  335.93  8304.2  334.14  8449.4  333.52  9464.3  351.05
#Mann= 20 ,-1 , 0
    3826     .05       0  3840.5     .07       0  3964.3     .05       0
  4316.2     .12       0  4803.4     .12       0  4925.5      .1       0
  4970.5     .05       0  5030.5      .1       0    5145     .12       0
  5524.2      .1       0  5986.5     .05       0  6082.3      .1       0
    6496     .12       0    7299     .05       0  7448.3     .07       0
    7634     .05       0  7937.8     .12       0  8192.5    .035       0
  8304.2    .035       0  8449.4     .05       0
Bank Sta=4970.5,5030.5
XS Rating Curve= 0 ,0
Exp/Cntr=0.3,0.1

Type RM Length L Ch R = 1 ,191513  ,671,671,671
BEGIN DESCRIPTION:
PEACH CREEK9072
END DESCRIPTION:
XS GIS Cut Line= 3
      2528174.97     13812824.97        2527375.       13812025.
      2522875.04     13813524.99
#Sta/Elev= 30
  3864.4  342.41  4229.7  328.36  4356.5  324.51  4391.6  323.78  4662.6  321.26
  4786.1  321.39  4933.5  322.51  4981.6  320.51  4986.8  311.24  4988.3  310.24
  5046.8  311.24  5048.4  319.85  5052.4  320.47  5080.1  322.88  5415.9  321.13
  5702.9  320.72  5989.9  322.01  6080.5  322.67  6250.1     324  6292.3  315.56
  6323.9   322.8  6359.7  322.94    6538  322.57  6797.3  322.36    7262  329.09
  7547.8  337.11  7672.7  338.48  7746.7  338.26  8337.2  328.84  9739.1  330.91
#Mann= 20 ,-1 , 0
  3864.4     .05       0  4229.7     .07       0  4356.5     .05       0
  4391.6     .07       0  4662.6     .05       0  4786.1    .035       0
  4933.5     .12       0  4986.8     .05       0  5046.8     .12       0
  5052.4     .05       0  5415.9    .035       0  5702.9    .035       0
  5989.9     .12       0  6080.5      .1       0  6359.7     .12       0
    6538     .05       0  6797.3     .12       0  7547.8     .05       0
  7672.7    .035       0  7746.7     .05       0
Bank Sta=4986.8,5046.8
XS Rating Curve= 0 ,0
Exp/Cntr=0.3,0.1

Type RM Length L Ch R = 1 ,190842  ,2043,2043,2043
BEGIN DESCRIPTION:
PEACH CREEK9071
END DESCRIPTION:
XS GIS Cut Line= 3
      2528275.02     13812675.03        2527475.       13811475.
      2522974.98     13812975.01
#Sta/Elev= 30
  3561.8  342.38  3991.4  323.78  4391.6  320.75  4672.6  319.93  4901.7  321.27
  4945.5  321.93  4951.5   308.8    4953   307.8  5011.5   308.8  5014.6  321.95
  5045.9  321.66  5255.5  319.35  5558.2  320.85  6051.9  321.05  6460.9  322.74
    6543  323.52  6574.7   314.6  6648.4   323.4  6711.7  313.94  6772.3  318.14
  7036.5  322.28  7218.2  325.86  7270.4  332.11  7362.6  325.92  7571.7  336.43
  7658.6  337.08  8187.4  328.58  9445.2  329.59  9576.8  329.87  9747.5  329.97
#Mann= 20 ,-1 , 0
  3561.8     .07       0  3991.4     .05       0  4391.6     .05       0
  4672.6     .12       0  4901.7     .07       0  4951.5     .05       0
  5011.5     .07       0  5045.9      .1       0  5255.5     .05       0
  5558.2     .12       0  6051.9     .05       0  6460.9     .12       0
  6772.3     .05       0  7036.5    .035       0  7218.2     .12       0
  7362.6     .05       0  7571.7    .035       0  7658.6     .05       0
  9445.2    .035       0  9576.8     .05       0
Bank Sta=4951.5,5011.5
XS Rating Curve= 0 ,0
Exp/Cntr=0.3,0.1

Type RM Length L Ch R = 1 ,188799  ,1531,1531,1531
BEGIN DESCRIPTION:
PEACH CREEK9070
END DESCRIPTION:
XS GIS Cut Line= 3
      2530100.41     13810380.74      2528392.06      13809984.9
      2523329.91     13808110.03
#Sta/Elev= 30
  3434.2  356.82  4101.1  336.28  4211.9  329.89  4367.5  319.56  4579.2  309.92
  4733.1  317.79  4753.7  308.93  4943.6   319.8  4961.4  305.82  4962.9  304.82
  5021.4  305.82  5034.1  319.53    5334  320.09    5366  306.49  5458.8  320.32
  5621.9  311.34  5666.2  320.17    6049  320.14  6182.6  320.11  6222.1  319.17
  6405.3   320.1  6464.8   320.2  7089.8  321.52  7167.8  321.71  9008.2  323.19
  9637.9   325.8  9687.4  326.54  9813.7  326.87  9880.2  327.58   10586  339.34
#Mann= 18 ,-1 , 0
  3434.2     .05       0  4101.1     .07       0  4211.9     .12       0
  4367.5      .1       0  4961.4     .05       0  5021.4      .1       0
    6049     .05       0  6182.6      .1       0  6222.1     .05       0
  6405.3     .12       0  6464.8     .05       0  7089.8    .035       0
  7167.8     .05       0  9008.2     .07       0  9637.9     .12       0
  9687.4     .07       0  9813.7     .12       0  9880.2     .07       0
Bank Sta=4961.4,5021.4
XS Rating Curve= 0 ,0
Exp/Cntr=0.3,0.1