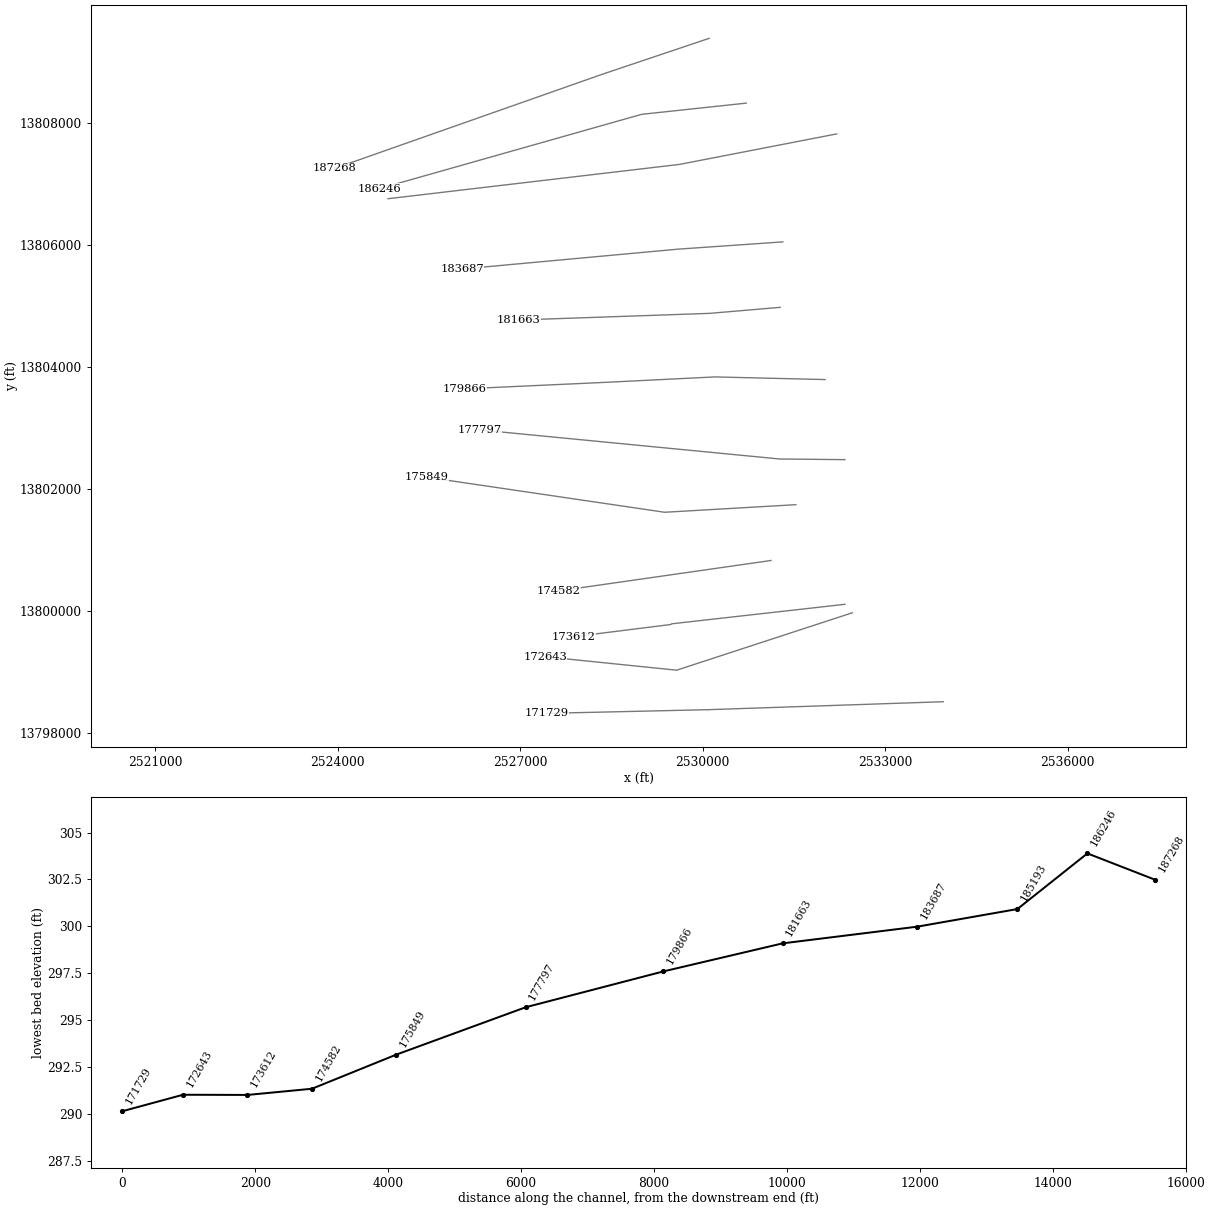
HEC-RAS study PEACH CREEK.prj: PEACH CREEK Base Level Engineering

--- PEACH CREEK.g01 (geometry) --- (continued)

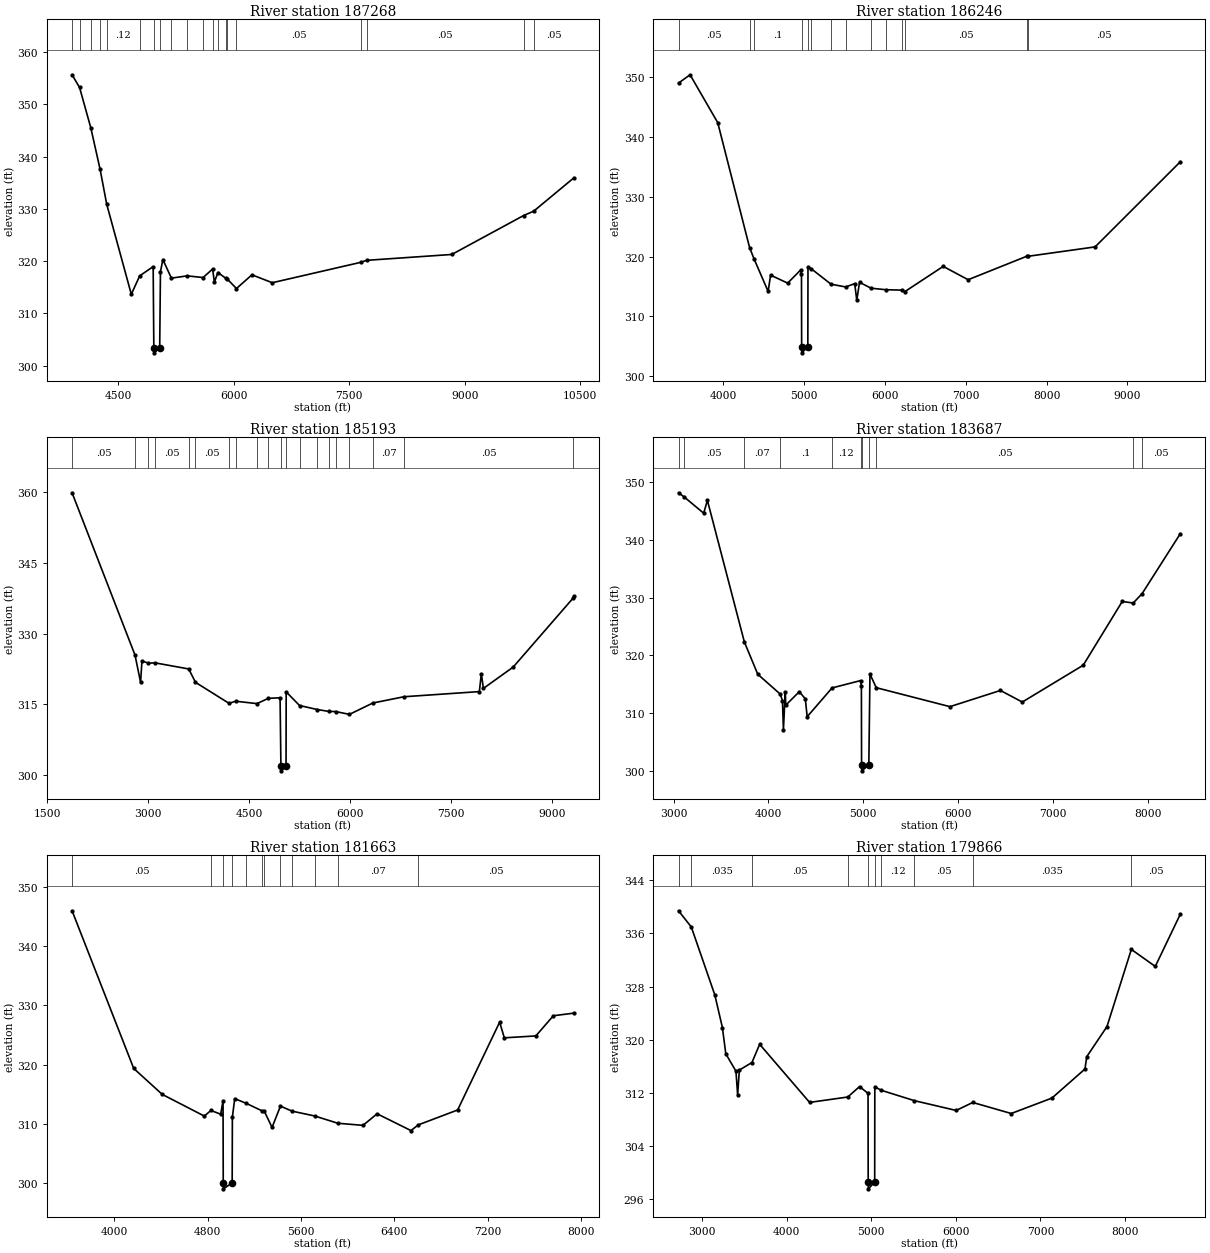
Type RM Length L Ch R = 1 ,187268  ,1022,1022,1022
BEGIN DESCRIPTION:
B19957
END DESCRIPTION:
XS GIS Cut Line= 3
      2530108.32     13809385.03      2528350.54     13808795.88
      2523948.25     13807251.22
#Sta/Elev= 30
  3898.9  355.62  3996.4  353.19  4141.3  345.54    4263  337.56  4348.8  330.89
  4668.5  313.67  4777.5  317.19  4952.5  318.96  4961.1  303.48  4962.6  302.48
  5037.5  303.48  5047.1  317.98  5078.7   320.3  5189.2  316.76    5395  317.19
  5600.8  316.87  5724.9  318.49  5747.8  316.02  5794.2  317.83  5896.1  316.72
  5912.9  316.62  6034.6  314.77  6235.6  317.39  6500.6  315.88  7650.1  319.78
  7725.9  320.16    8832  321.28  9765.3  328.72    9896  329.55 10418.2  335.92
#Mann= 20 ,-1 , 0
  3898.9     .05       0  3996.4     .07       0  4141.3     .05       0
    4263     .07       0  4348.8     .12       0  4777.5      .1       0
  4961.1     .05       0  5037.5      .1       0  5189.2     .12       0
    5395     .05       0  5600.8     .12       0  5724.9     .07       0
  5794.2     .12       0  5896.1     .05       0  5912.9     .07       0
  6034.6     .05       0  7650.1    .035       0  7725.9     .05       0
  9765.3     .07       0    9896     .05       0
Bank Sta=4961.1,5037.5
XS Rating Curve= 0 ,0
Exp/Cntr=0.3,0.1

Type RM Length L Ch R = 1 ,186246  ,1053,1053,1053
BEGIN DESCRIPTION:
B19956
END DESCRIPTION:
XS GIS Cut Line= 3
      2530716.79     13808322.63      2528997.64     13808139.13
      2524690.05     13806922.18
#Sta/Elev= 30
  3448.8  349.01  3591.4   350.4  3933.3   342.4  4327.4   321.5  4382.7   319.6
  4556.8  314.16    4587  316.89  4798.2  315.55  4959.1  317.75  4969.2     317
  4971.2  304.89  4972.7  303.89  5047.6  304.89  5049.6  318.26  5086.4  317.99
  5334.6  315.37  5516.4  314.91  5627.3  315.47    5653  312.67  5686.9  315.69
  5830.1   314.7    6011  314.45  6212.4  314.38  6248.7  314.14  6721.5  318.35
  7030.1  316.12  7755.6  320.05  7765.9  320.03  8599.8  321.61  9653.9  335.85
#Mann= 14 ,-1 , 0
  3448.8     .05       0  4327.4     .07       0  4382.7      .1       0
  4971.2     .05       0  5047.6      .1       0  5086.4     .07       0
  5334.6     .05       0  5516.4     .07       0  5830.1    .035       0
    6011     .05       0  6212.4     .07       0  6248.7     .05       0
  7755.6    .035       0  7765.9     .05       0
Bank Sta=4971.2,5047.6
XS Rating Curve= 0 ,0
Exp/Cntr=0.3,0.1

Type RM Length L Ch R = 1 ,185193  ,1506,1506,1506
BEGIN DESCRIPTION:
PEACH CREEK9069
END DESCRIPTION:
XS GIS Cut Line= 3
      2532204.57     13807818.24      2529621.22     13807318.23
      2524829.82     13806755.76
#Sta/Elev= 30
  1868.3  359.87  2803.6  325.46  2886.4  319.68  2906.6  324.21  3003.1  323.75
  3102.9  323.81  3601.8  322.52  3701.6  319.69  4200.5  315.23  4300.3  315.68
  4615.7  315.17  4783.8  316.29    4959  316.41  4971.1  301.92  4972.6  300.92
  5047.5  301.92  5049.6  317.66  5247.8  314.77  5510.9  313.92  5685.9  313.51
  5784.9  313.49  5989.3  312.89  6337.6   315.3  6800.4  316.63  7919.7  317.72
  7949.3  321.48  7979.6  318.39  8422.6  322.92  9313.2  337.55  9323.9  337.95
#Mann= 20 ,-1 , 0
  1868.3     .05       0  2803.6     .07       0  3003.1     .12       0
  3102.9     .05       0  3601.8    .035       0  3701.6     .05       0
  4200.5     .12       0  4300.3      .1       0  4615.7      .1       0
  4783.8     .12       0  4971.1    .035       0  5047.5    .035       0
  5247.8     .07       0  5510.9     .05       0  5685.9     .07       0
  5784.9    .035       0  5989.3     .05       0  6337.6     .07       0
  6800.4     .05       0  9313.2     .05       0
Bank Sta=4971.1,5047.5
XS Rating Curve= 0 ,0
Exp/Cntr=0.3,0.1

Type RM Length L Ch R = 1 ,183687  ,2024,2024,2024
BEGIN DESCRIPTION:
PEACH CREEK9068
END DESCRIPTION:
XS GIS Cut Line= 3
      2531318.71     13806048.01      2529593.45     13805928.65
      2526045.23     13805603.12
#Sta/Elev= 30
  3051.4   348.2  3111.4  347.47  3316.5  344.66  3355.8  346.88  3745.7  322.33
    3887  316.73    4123   313.3  4147.7  312.15  4157.7  307.12  4177.2  313.69
  4182.2  311.37  4324.8   313.7  4388.3  312.48  4408.3  309.37    4671  314.36
    4971  315.63    4980  314.71    4982  300.98  4983.5  299.98  5058.4  300.98
  5070.4  316.76  5136.8   314.4    5914  311.11  6446.2  313.92  6677.2  311.91
  7319.9   318.3  7731.6  329.36  7846.9  329.08  7940.7  330.71  8343.9  341.11
#Mann= 11 ,-1 , 0
  3051.4     .07       0  3111.4     .05       0  3745.7     .07       0
    4123      .1       0    4671     .12       0    4971      .1       0
    4982     .05       0  5058.4      .1       0  5136.8     .05       0
  7846.9    .035       0  7940.7     .05       0
Bank Sta=4982,5058.4
XS Rating Curve= 0 ,0
Exp/Cntr=0.3,0.1

Type RM Length L Ch R = 1 ,181663  ,1797,1797,1797
BEGIN DESCRIPTION:
PEACH CREEK9067
END DESCRIPTION:
XS GIS Cut Line= 3
      2531274.99       13804975.      2530114.28     13804876.13
      2526979.17     13804767.65
#Sta/Elev= 30
  3638.2  345.95  4166.7  319.38    4411  315.01  4772.3  311.35  4828.2   312.3
  4912.5  311.67  4932.5  313.97  4934.2  300.09  4935.7  299.09  5010.8  300.09
  5012.5  311.16  5032.5  314.29  5129.2  313.52  5269.1  312.21  5284.7  312.23
  5352.7  309.44  5424.6  313.03    5523  312.19  5719.9  311.36  5916.9  310.14
  6132.6  309.79  6253.3  311.74  6543.4  308.91  6606.6  309.87  6943.7  312.38
  7303.9  327.18  7343.9  324.54  7614.1  324.86  7764.2  328.26  7940.1   328.7
#Mann= 12 ,-1 , 0
  3638.2     .05       0  4828.2      .1       0  4934.2     .05       0
  5010.8      .1       0  5129.2     .07       0  5269.1      .1       0
  5284.7     .07       0  5424.6    .035       0    5523     .07       0
  5719.9     .12       0  5916.9     .07       0  6606.6     .05       0
Bank Sta=4934.2,5010.8
XS Rating Curve= 0 ,0
Exp/Cntr=0.3,0.1

Type RM Length L Ch R = 1 ,179866  ,2069,2069,2069
BEGIN DESCRIPTION:
PEACH CREEK9066
END DESCRIPTION:
XS GIS Cut Line= 4
      2532013.18     13803791.06      2530201.08     13803834.46
      2528454.12     13803747.66      2526089.35     13803639.18
#Sta/Elev= 30
  2723.8  339.41  2874.8  336.97  3152.1  326.77  3242.1  321.85  3282.1   317.9
  3402.2  315.29  3422.2  311.71  3442.2  315.45  3591.2  316.59  3682.3  319.33
  4272.4  310.59  4723.1   311.4  4862.9  312.97    4963  311.95  4964.8  298.59
  4966.3  297.59  5041.4  298.59  5043.1  312.95  5117.1  312.42    5511  310.85
  6004.3  309.38  6200.3  310.58    6655  308.92  7135.6  311.24    7526  315.61
  7547.4  317.47  7786.2     322    8074   333.6  8356.8  331.04  8652.8   338.9
#Mann= 10 ,-1 , 0
  2723.8     .12       0  2874.8    .035       0  3591.2     .05       0
  4723.1      .1       0  4964.8     .05       0  5041.4      .1       0
  5117.1     .12       0    5511     .05       0  6200.3    .035       0
    8074     .05       0
Bank Sta=4964.8,5041.4
XS Rating Curve= 0 ,0
Exp/Cntr=0.3,0.1

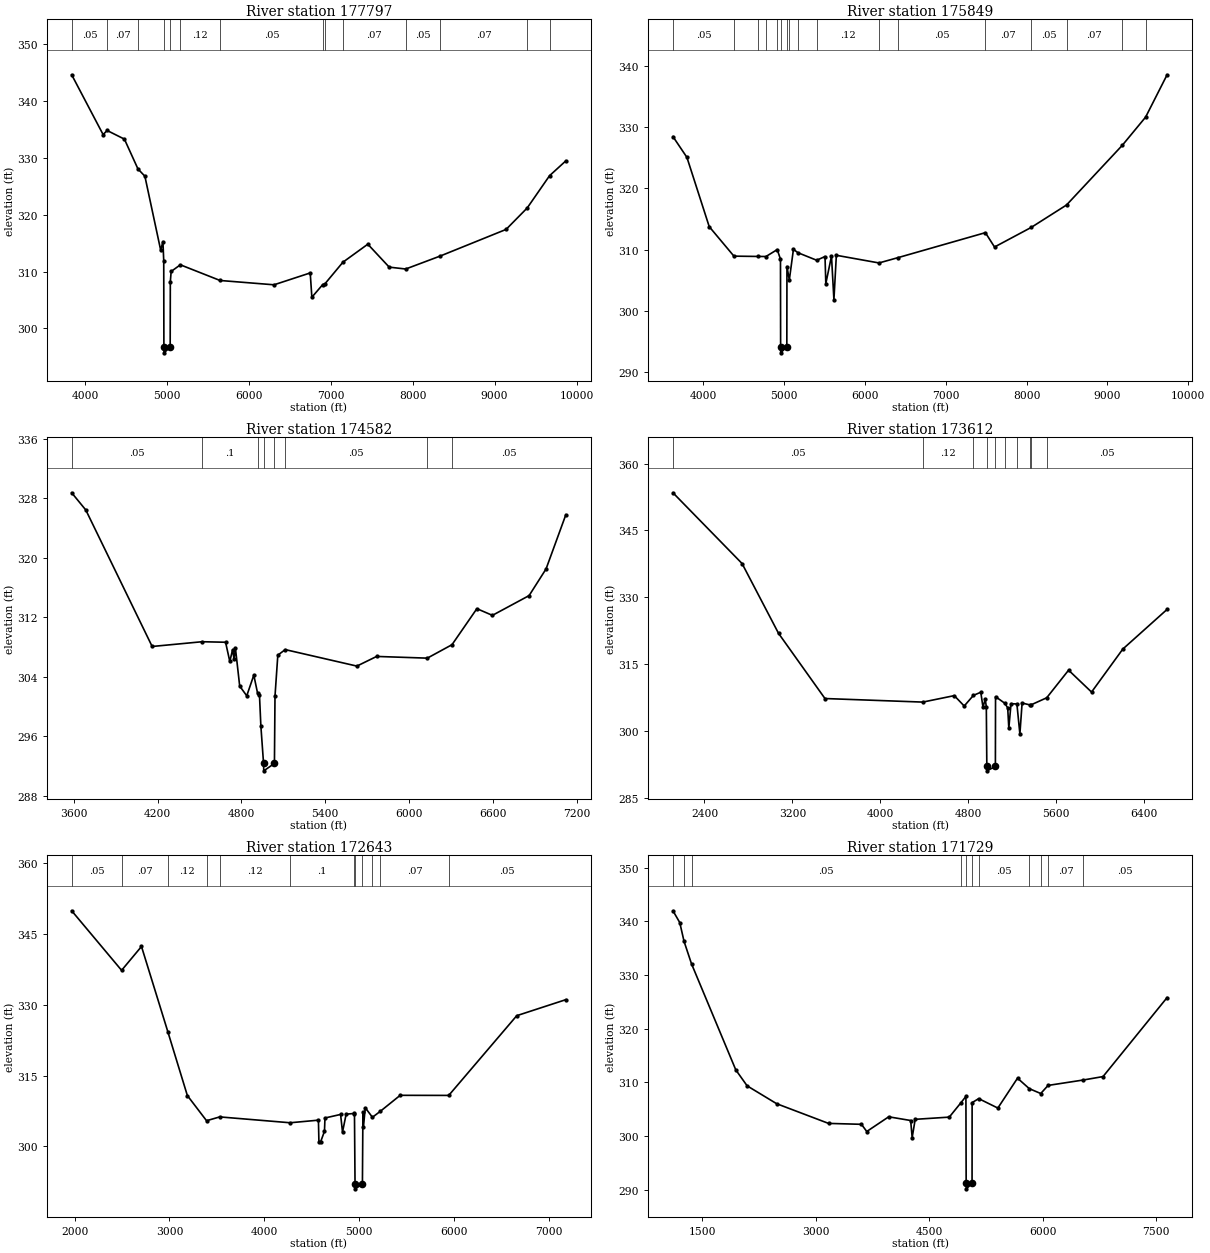
Type RM Length L Ch R = 1 ,177797  ,1948,1948,1948
BEGIN DESCRIPTION:
PEACH CREEK9065
END DESCRIPTION:
XS GIS Cut Line= 3
      2532338.66     13802478.13      2531264.45     13802488.98
      2526328.74     13802966.28
#Sta/Elev= 30
  3836.4  344.64  4220.1  334.11    4269  334.83  4480.1  333.31  4645.5  328.06
  4730.1  326.78  4923.2  313.75  4950.3  315.27  4960.3  311.88  4962.2  296.68
  4963.7  295.68  5038.9  296.68  5040.7  308.19  5050.8  310.01  5163.2  311.18
  5648.2  308.42  6306.6  307.66  6748.7  309.75  6768.7  305.47  6902.1  307.71
  6925.7  307.79  7148.1  311.64  7451.9  314.81  7713.1  310.77  7914.3  310.44
  8335.1  312.72  9139.8  317.41    9398  321.19  9670.8  326.87  9869.4  329.48
#Mann= 14 ,-1 , 0
  3836.4     .05       0    4269     .07       0  4645.5     .12       0
  4962.2     .05       0  5038.9     .12       0  5163.2     .12       0
  5648.2     .05       0  6902.1     .07       0  6925.7     .05       0
  7148.1     .07       0  7914.3     .05       0  8335.1     .07       0
    9398     .05       0  9670.8     .07       0
Bank Sta=4962.2,5038.9
XS Rating Curve= 0 ,0
Exp/Cntr=0.3,0.1

Type RM Length L Ch R = 1 ,175849  ,1267,1267,1267
BEGIN DESCRIPTION:
PEACH CREEK9064
END DESCRIPTION:
XS GIS Cut Line= 3
      2531532.99     13801739.92      2529376.99     13801615.35
      2525465.26     13802189.93
#Sta/Elev= 30
  3625.4  328.42  3798.1  325.03  4074.1  313.73  4379.8  308.92  4680.3  308.87
    4776  308.86  4915.5  309.99  4955.6  308.42  4957.3  294.15  4958.8  293.15
  5034.1  294.15  5035.7  307.23    5065  305.04  5115.9  310.03  5171.6  309.48
  5403.6  308.25  5506.5  308.86  5516.5  304.44  5586.7  308.93  5616.7  301.81
  5646.8  309.06  6174.4  307.81  6410.5  308.68  7490.7  312.75  7603.7  310.41
    8057   313.6  8494.3  317.26  9184.8     327  9473.2   331.6  9738.7   338.5
#Mann= 17 ,-1 , 0
  3625.4     .05       0  4379.8     .07       0  4680.3     .12       0
    4776     .07       0  4915.5      .1       0  4957.3     .05       0
  5034.1      .1       0    5065     .12       0  5171.6     .05       0
  5403.6     .12       0  6174.4     .07       0  6410.5     .05       0
  7490.7     .07       0    8057     .05       0  8494.3     .07       0
  9184.8     .05       0  9473.2    .035       0
Bank Sta=4957.3,5034.1
XS Rating Curve= 0 ,0
Exp/Cntr=0.3,0.1

Type RM Length L Ch R = 1 ,174582  ,970,970,970
BEGIN DESCRIPTION:
PEACH CREEK9063
END DESCRIPTION:
XS GIS Cut Line= 3
      2531125.04     13800825.01        2529725.       13800625.
      2527624.98       13800325.
#Sta/Elev= 30
  3585.7  328.76  3686.8  326.44  4161.5  308.07    4519  308.71  4686.8  308.64
  4717.1  306.05  4737.3  307.66  4747.4  306.34  4757.5  307.81  4787.8  302.74
  4838.3  301.43  4888.8  304.21  4915.4  301.82  4929.2  301.59  4939.3  297.37
  4958.5  292.33    4960  291.33  5036.4  292.33  5040.4  301.38  5060.6   306.9
  5113.6  307.65  5626.3  305.43  5767.7  306.73  6130.2   306.5  6306.9  308.31
  6484.9  313.16    6596  312.26  6858.6  314.92  6979.9  318.51  7121.3   325.8
#Mann= 8 ,-1 , 0
  3585.7     .05       0    4519      .1       0  4915.4     .12       0
  4958.5     .05       0  5036.4     .05       0  5113.6     .05       0
  6130.2     .07       0  6306.9     .05       0
Bank Sta=4958.5,5036.4
XS Rating Curve= 0 ,0
Exp/Cntr=0.3,0.1

Type RM Length L Ch R = 1 ,173612  ,969,969,969
BEGIN DESCRIPTION:
PEACH CREEK9062
END DESCRIPTION:
XS GIS Cut Line= 5
      2532340.32      13800106.6       2529494.5     13799787.19
        2529475.       13799775.      2529451.58     13799772.07
      2527875.04       13799575.
#Sta/Elev= 30
    2113  353.45  2742.2  337.56  3074.3  321.88    3497  307.24  4387.8  306.44
  4674.3  307.89  4764.9  305.56  4848.8  307.95  4915.8  308.65  4935.9  305.28
  4956.3  307.11  4966.1  305.37  4970.8     292  4972.3     291  5048.7     292
  5050.1  307.66  5134.8  306.17  5160.9  305.13    5171  300.57  5191.2  306.08
  5244.6  306.02  5271.8  299.26  5291.9  306.23  5367.9  305.78  5375.3  305.84
    5516  307.41  5715.2  313.61  5924.3  308.69    6209  318.35  6612.1  327.26
#Mann= 10 ,-1 , 0
    2113     .05       0  4387.8     .12       0  4848.8    .035       0
  4970.8    .035       0  5048.7    .035       0  5134.8     .05       0
  5244.6     .07       0  5367.9     .05       0  5375.3     .07       0
    5516     .05       0
Bank Sta=4970.8,5048.7
XS Rating Curve= 0 ,0
Exp/Cntr=0.3,0.1

Type RM Length L Ch R = 1 ,172643  ,914,914,914
BEGIN DESCRIPTION:
PEACH CREEK9061
END DESCRIPTION:
XS GIS Cut Line= 5
      2532461.78      13799967.7      2529586.53     13799030.77
        2529575.       13799025.      2529567.67     13799027.09
      2527409.84     13799247.21
#Sta/Elev= 30
  1969.1  349.88  2495.7  337.27  2705.6  342.32    2983  324.31  3189.6  310.76
  3392.1  305.43  3530.9  306.24  4273.6     305  4572.4  305.55  4577.7   300.9
  4595.1  300.93  4636.3   303.2  4641.5  306.01  4806.3  306.76  4826.5  303.02
  4864.9  306.82  4945.5  306.96  4952.7     307  4958.7  292.01  4960.2  291.01
  5036.6  292.01  5041.9  307.29  5046.9     304  5066.6  308.18  5142.3  306.16
    5227  307.45    5435  310.81  5947.4  310.79  6664.9  327.67  7182.7  331.06
#Mann= 12 ,-1 , 0
  1969.1     .05       0  2495.7     .07       0    2983     .12       0
  3392.1    .035       0  3530.9     .12       0  4273.6      .1       0
  4945.5    .035       0  4958.7    .035       0  5036.6    .035       0
  5142.3     .12       0    5227     .07       0  5947.4     .05       0
Bank Sta=4958.7,5036.6
XS Rating Curve= 0 ,0
Exp/Cntr=0.3,0.1

Type RM Length L Ch R = 1 ,171729  ,967,967,967
BEGIN DESCRIPTION:
PEACH CREEK9060
END DESCRIPTION:
XS GIS Cut Line= 5
       2533954.9     13798509.38      2530078.55     13798378.55
        2530075.       13798375.      2530059.57     13798378.43
      2527428.54     13798318.44
#Sta/Elev= 30
  1111.2  341.97  1201.2  339.77  1257.9  336.26  1356.4  332.08  1941.6  312.31
  2091.7  309.33  2481.9     306  3167.6  302.33  3602.5  302.16  3672.6  300.82
  3962.7  303.56  4252.9  302.87  4272.9   299.7  4312.9  303.09  4763.2   303.5
  4913.2  306.11  4983.3  307.36  4986.5  291.13    4988  290.13  5064.5  291.13
  5065.2   306.2  5152.1  306.95  5405.3  305.19  5665.3  310.76  5820.9  308.81
  5972.2   307.9  6069.2  309.41  6534.4  310.42  6795.6  311.06  7642.3  325.79
#Mann= 11 ,-1 , 0
  1111.2     .05       0  1257.9    .035       0  1356.4     .05       0
  4913.2      .1       0  4986.5     .05       0  5064.5      .1       0
  5152.1     .05       0  5820.9     .07       0  5972.2     .05       0
  6069.2     .07       0  6534.4     .05       0
Bank Sta=4986.5,5064.5
XS Rating Curve= 0 ,0
Exp/Cntr=0.3,0.1