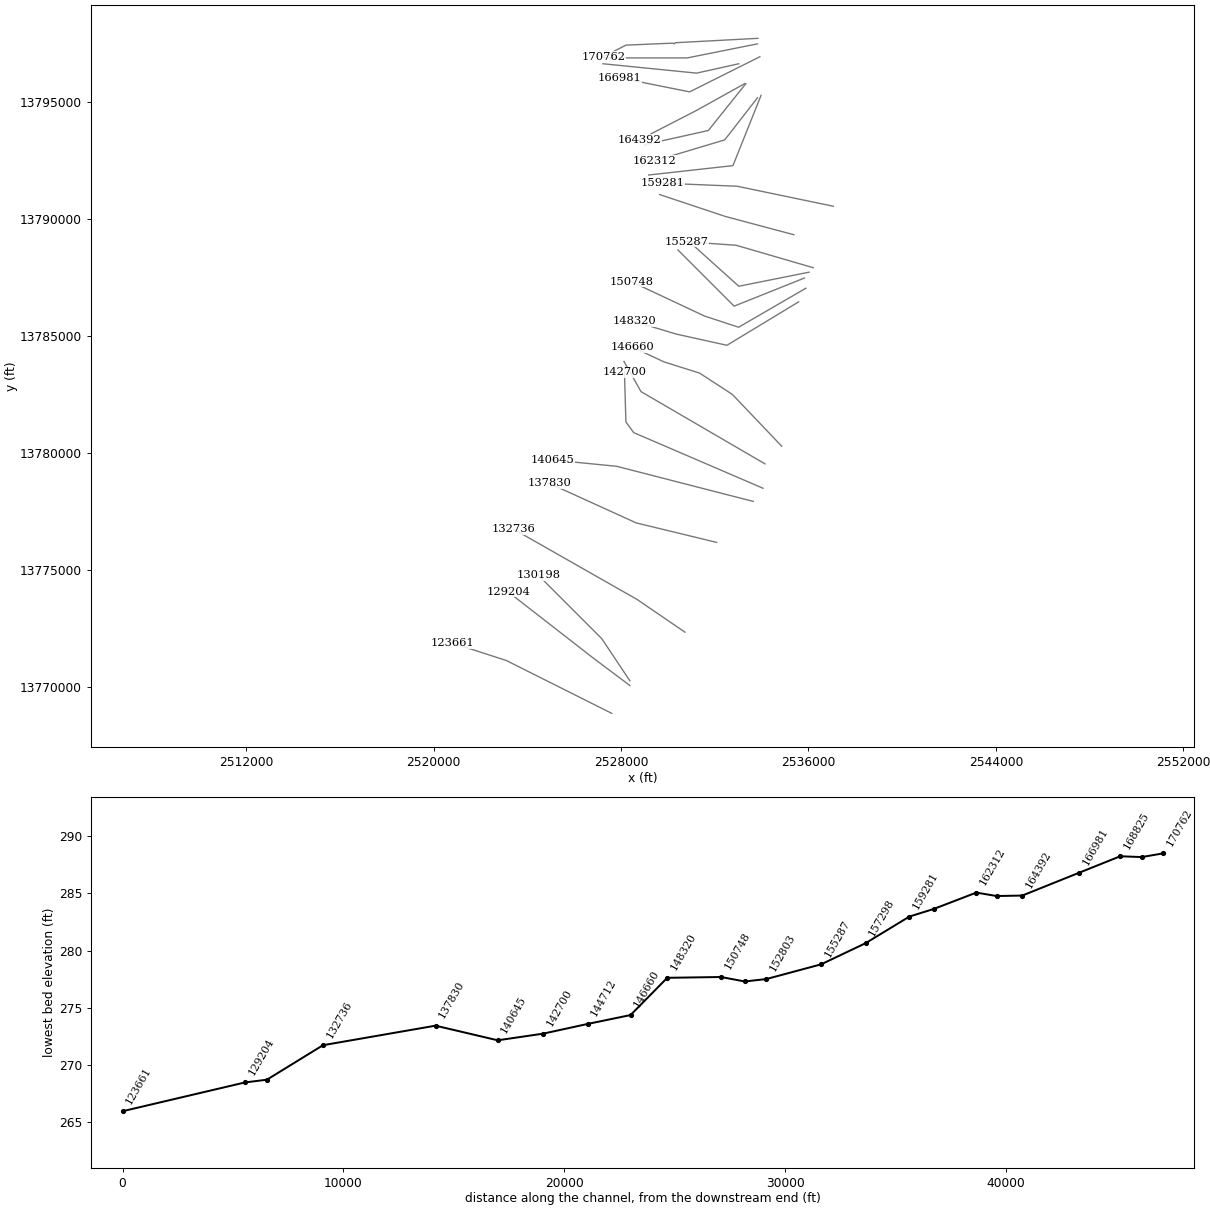
HEC-RAS study PEACH CREEK.prj: PEACH CREEK Base Level Engineering

--- PEACH CREEK.g01 (geometry) --- (continued)

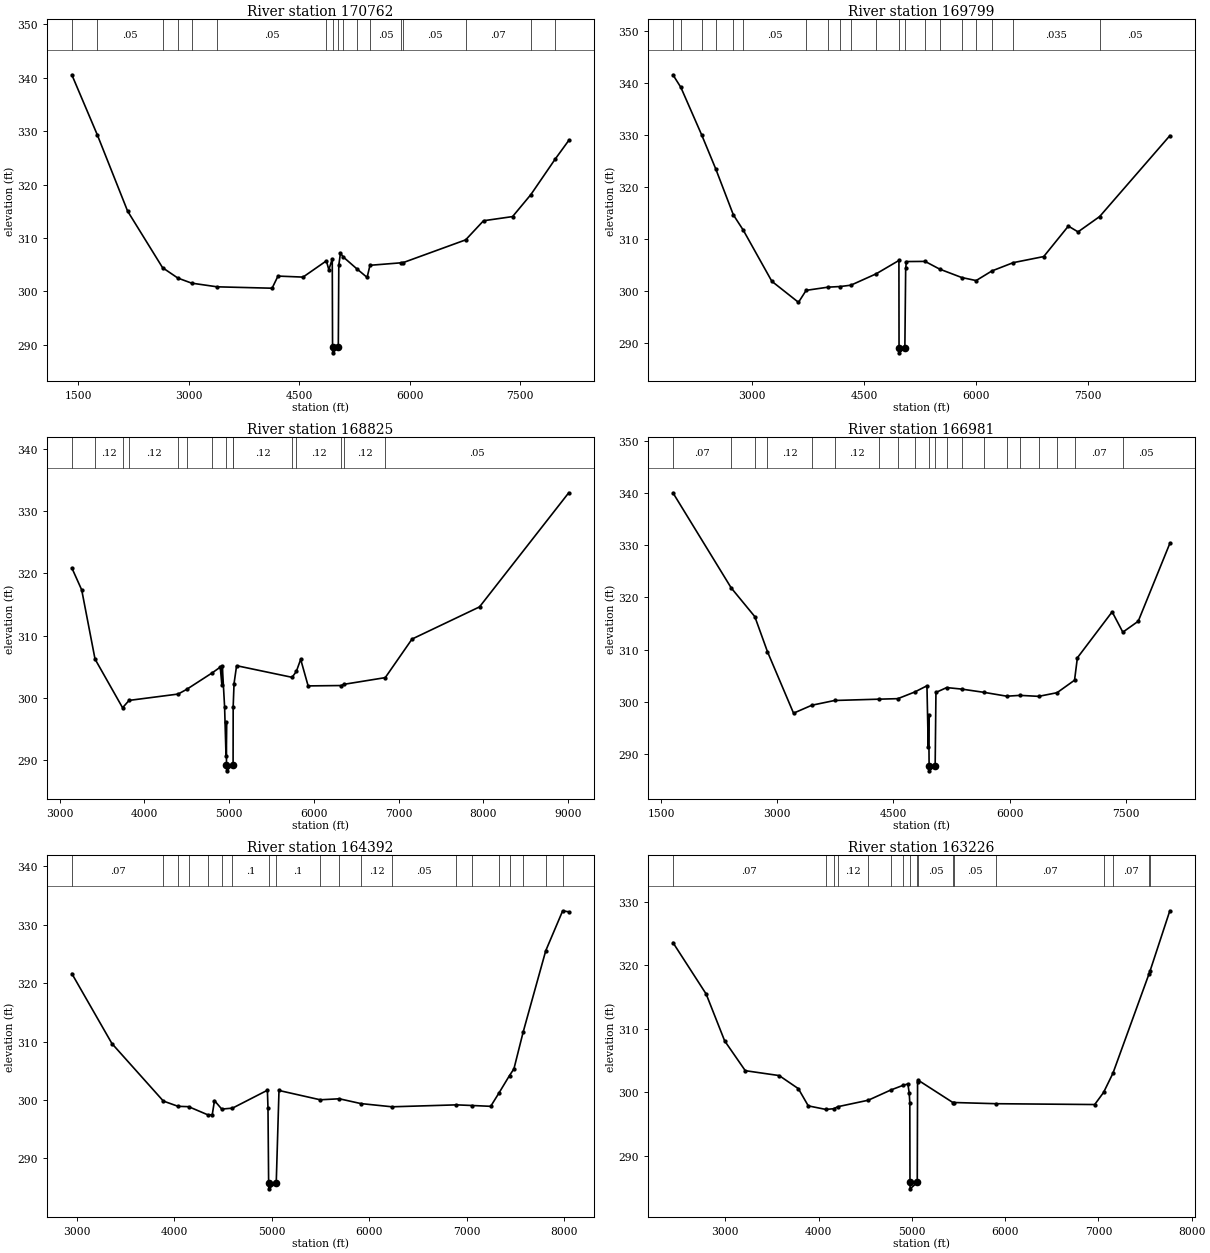
Type RM Length L Ch R = 1 ,170762  ,963,963,963
BEGIN DESCRIPTION:
PEACH CREEK9059
END DESCRIPTION:
XS GIS Cut Line= 6
      2533841.98     13797710.76      2530313.52     13797523.15
        2530275.       13797475.      2530206.25     13797505.56
       2528208.1     13797421.02      2527245.26     13796929.75
#Sta/Elev= 30
    1410  340.56  1758.2  329.25    2168  315.03  2643.1  304.44  2850.5   302.5
  3037.6  301.55  3384.4  300.86  4130.8   300.6  4210.9  302.87  4551.4  302.68
  4868.3  305.72  4901.9  304.06  4948.3  306.09  4952.5   289.5    4954   288.5
  5030.5   289.5  5037.2  304.89  5059.8  307.18  5094.4  306.49  5279.7  304.26
  5421.9  302.62  5460.9  304.89  5885.7  305.36    5915  305.41  6760.5  309.65
  7003.3  313.23  7398.1  314.01  7646.8  318.13  7973.8  324.71  8161.2  328.26
#Mann= 17 ,-1 , 0
    1410    .035       0  1758.2     .05       0  2643.1     .07       0
  2850.5     .05       0  3037.6     .07       0  3384.4     .05       0
  4868.3      .1       0  4952.5     .05       0  5030.5      .1       0
  5094.4     .05       0  5279.7      .1       0  5460.9     .05       0
  5885.7    .035       0    5915     .05       0  6760.5     .07       0
  7646.8     .05       0  7973.8    .035       0
Bank Sta=4952.5,5030.5
XS Rating Curve= 0 ,0
Exp/Cntr=0.3,0.1

Type RM Length L Ch R = 1 ,169799  ,974,974,974
BEGIN DESCRIPTION:
PEACH CREEK9058
END DESCRIPTION:
XS GIS Cut Line= 3
        2533825.       13797475.        2530825.       13796875.
      2527225.01       13796875.
#Sta/Elev= 30
  1935.8  341.58  2042.3  339.16    2323  329.97  2511.5  323.44  2745.7  314.68
    2879  311.73  3261.5  301.92  3618.5  297.88  3721.3  300.18  4012.9  300.79
  4180.5  300.92  4320.6  301.17    4659  303.35  4964.6  305.92  4966.2  289.18
  4967.7  288.18  5044.2  289.18  5055.2  304.39  5065.2  305.71  5314.9  305.74
  5511.9  304.25  5807.3  302.64  5999.5  302.06  6210.9  303.91  6496.7   305.5
  6905.2  306.67  7235.2  312.52  7365.2  311.41  7655.2  314.36  8595.2  329.88
#Mann= 20 ,-1 , 0
  1935.8     .07       0  2042.3     .07       0    2323     .05       0
  2511.5     .05       0  2745.7    .035       0    2879     .05       0
  3721.3     .05       0  4012.9     .05       0  4180.5     .07       0
  4320.6     .12       0    4659      .1       0  4966.2     .05       0
  5044.2      .1       0  5314.9     .12       0  5511.9     .07       0
  5807.3      .1       0  5999.5      .1       0  6210.9     .07       0
  6496.7    .035       0  7655.2     .05       0
Bank Sta=4966.2,5044.2
XS Rating Curve= 0 ,0
Exp/Cntr=0.3,0.1

Type RM Length L Ch R = 1 ,168825  ,1844,1844,1844
BEGIN DESCRIPTION:
PEACH CREEK9057
END DESCRIPTION:
XS GIS Cut Line= 3
        2533025.       13796625.        2531225.       13796225.
      2527224.96       13796625.
#Sta/Elev= 30
  3143.4  320.87  3259.9  317.33  3417.3  306.21  3742.3  298.39    3819  299.57
  4397.9  300.59  4498.2  301.34  4801.5  304.01  4895.1  304.92  4914.3  302.04
  4919.4  305.08  4946.3  298.53    4963  290.62  4968.1  296.11  4968.4  289.25
  4969.9  288.25  5046.4  289.25  5047.5  298.58  5057.7  302.27  5087.8  305.15
  5742.5  303.28  5792.6  304.22  5844.1  306.17    5932   301.9  6320.5  301.96
  6356.7  302.16  6842.1  303.23  7158.1  309.43  7954.5   314.6  9007.3  332.94
#Mann= 15 ,-1 , 0
  3143.4     .07       0  3417.3     .12       0  3742.3      .1       0
    3819     .12       0  4397.9     .07       0  4498.2     .12       0
  4801.5      .1       0  4968.4     .05       0  5046.4      .1       0
  5047.5     .12       0  5742.5     .07       0  5792.6     .12       0
  6320.5     .07       0  6356.7     .12       0  6842.1     .05       0
Bank Sta=4968.4,5046.4
XS Rating Curve= 0 ,0
Exp/Cntr=0.3,0.1

Type RM Length L Ch R = 1 ,166981  ,2589,2589,2589
BEGIN DESCRIPTION:
PEACH CREEK9056
END DESCRIPTION:
XS GIS Cut Line= 3
      2533925.02     13796925.01        2530925.       13795425.
      2527925.03     13796024.99
#Sta/Elev= 30
  1654.2  340.02  2406.9  321.81  2711.4  316.32  2874.1  309.63  3211.1  297.85
  3446.7  299.37  3740.7  300.28    4308  300.53  4557.4  300.63  4774.6   301.9
  4932.9  303.09  4949.6   291.3  4955.2  297.58  4960.9  287.82  4962.4  286.82
  5038.9  287.82  5049.1  301.82  5187.8  302.75  5380.8  302.46  5668.3  301.84
  5964.1   301.1  6134.5  301.26  6374.5  301.07  6612.2  301.77  6837.9  304.16
  6874.6  308.45  7323.3  317.24  7461.1  313.35  7659.8  315.44  8067.7  330.33
#Mann= 20 ,-1 , 0
  1654.2     .07       0  2406.9     .12       0  2711.4     .07       0
  2874.1     .12       0  3446.7      .1       0  3740.7     .12       0
    4308     .07       0  4557.4     .12       0  4774.6     .07       0
  4960.9     .05       0  5038.9     .07       0  5187.8      .1       0
  5380.8     .12       0  5668.3     .07       0  5964.1     .07       0
  6134.5     .05       0  6374.5     .07       0  6612.2     .07       0
  6837.9     .07       0  7461.1     .05       0
Bank Sta=4960.9,5038.9
XS Rating Curve= 0 ,0
Exp/Cntr=0.3,0.1

Type RM Length L Ch R = 1 ,164392  ,1166,1166,1166
BEGIN DESCRIPTION:
PEACH CREEK9054
END DESCRIPTION:
XS GIS Cut Line= 3
      2533274.99       13795775.      2531204.56     13794624.48
      2528775.04     13793375.02
#Sta/Elev= 30
  2947.5  321.62  3359.3  309.65  3886.9  299.82    4038  298.92  4146.5  298.86
  4344.5  297.46    4389  297.48  4411.8   299.9  4486.2  298.45  4596.7  298.61
    4955  301.67    4961  298.66  4967.7  285.81  4969.2  284.81  5045.7  285.81
    5074  301.63  5496.8  300.04  5693.6  300.21  5914.4  299.39  6234.2  298.84
  6894.5  299.17  7059.6  299.06  7247.1  298.92  7331.2  301.18  7440.3  304.19
  7485.4  305.32  7580.6  311.64  7812.4  325.54  7986.2  332.36  8048.1  332.18
#Mann= 20 ,-1 , 0
  2947.5     .07       0  3886.9     .12       0    4038      .1       0
  4146.5     .07       0  4344.5     .07       0  4486.2     .12       0
  4596.7      .1       0  4967.7     .05       0  5045.7      .1       0
  5496.8     .07       0  5693.6     .07       0  5914.4     .12       0
  6234.2     .05       0  6894.5     .12       0  7059.6     .07       0
  7331.2     .07       0  7440.3     .12       0  7580.6     .07       0
  7812.4    .035       0  7986.2     .07       0
Bank Sta=4967.7,5045.7
XS Rating Curve= 0 ,0
Exp/Cntr=0.3,0.1

Type RM Length L Ch R = 1 ,163226  ,914,914,914
BEGIN DESCRIPTION:
PEACH CREEK9053
END DESCRIPTION:
XS GIS Cut Line= 3
      2533325.03     13795775.03        2531725.       13793775.
      2529024.96     13793174.99
#Sta/Elev= 30
  2438.7  323.54  2794.9  315.44  2993.4  308.06  3214.3  303.37  3577.7   302.6
  3783.4  300.54  3889.9  297.83    4078  297.27  4162.2  297.38  4206.9   297.7
    4533  298.72    4775  300.33  4909.2  301.08  4957.6  301.28    4972  299.86
  4978.4  298.32  4980.2  285.77  4981.7  284.77  5058.2  285.77  5061.5  301.61
    5065   301.9  5440.7  298.35  5451.1  298.36  5906.9  298.17  6960.4  298.04
  7055.4  299.94  7155.8  302.96  7541.5  318.56  7552.3  318.99  7765.9  328.54
#Mann= 17 ,-1 , 0
  2438.7     .07       0    4078     .12       0  4162.2      .1       0
  4206.9     .12       0    4533     .07       0    4775     .12       0
  4909.2      .1       0  4980.2     .05       0  5058.2      .1       0
    5065     .05       0  5440.7     .07       0  5451.1     .05       0
  5906.9     .07       0  7055.4     .12       0  7155.8     .07       0
  7541.5    .035       0  7552.3     .07       0
Bank Sta=4980.2,5058.2
XS Rating Curve= 0 ,0
Exp/Cntr=0.3,0.1

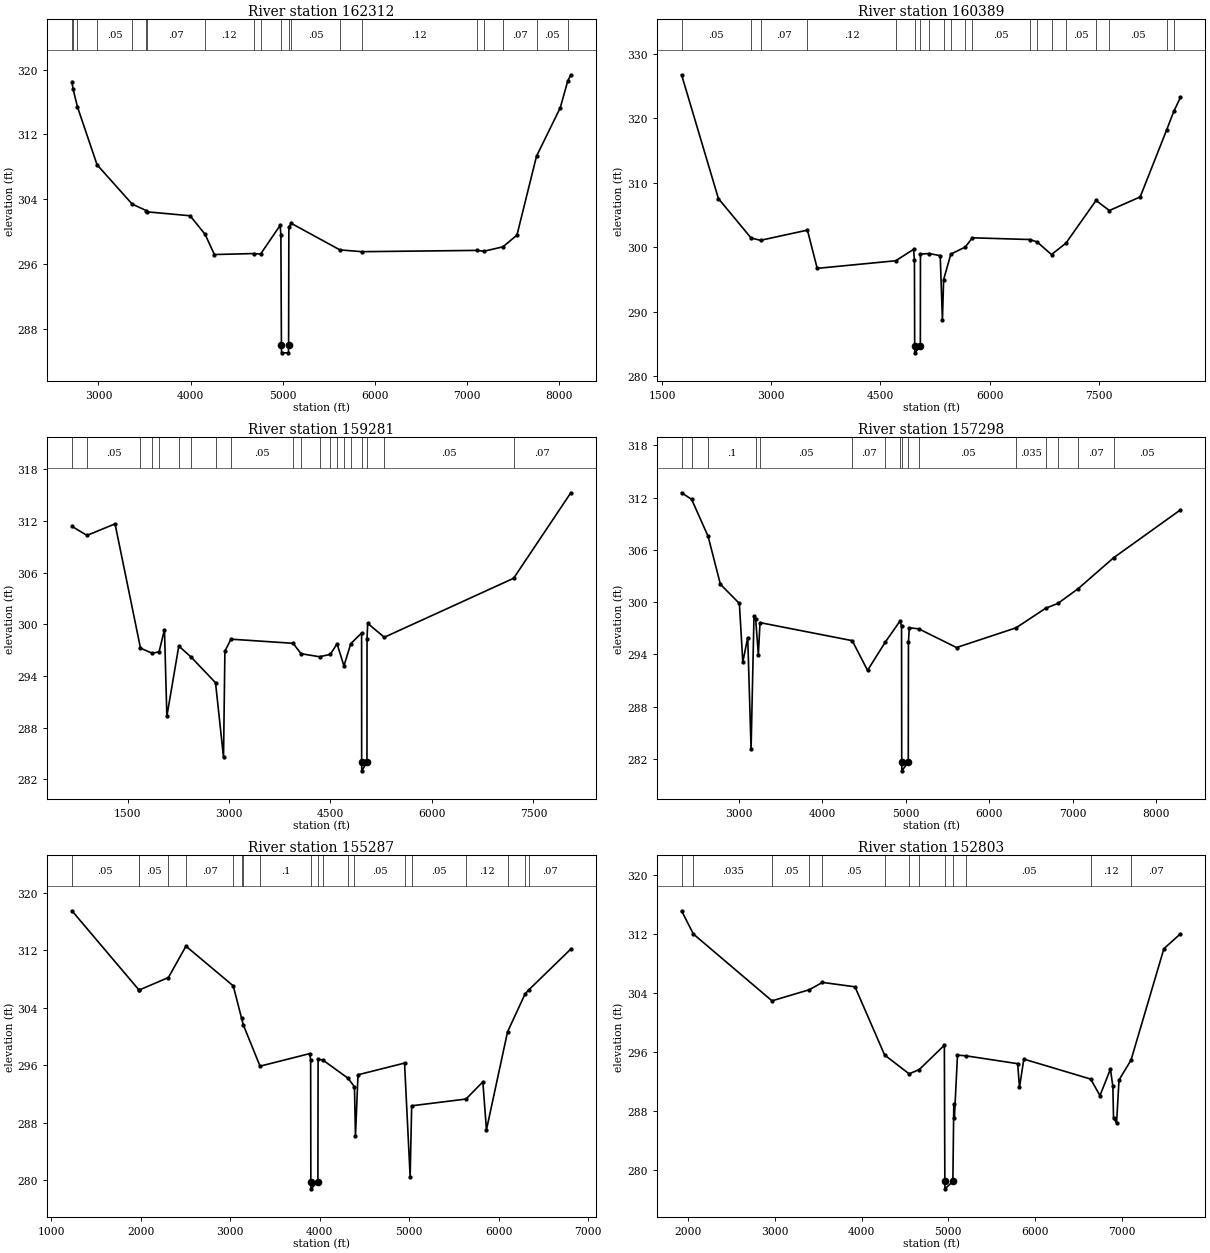
Type RM Length L Ch R = 1 ,162312  ,1923,1923,1923
BEGIN DESCRIPTION:
PEACH CREEK9052
END DESCRIPTION:
XS GIS Cut Line= 3
      2533824.99     13795174.99        2532425.       13793375.
      2529425.02     13792475.01
#Sta/Elev= 30
  2711.9   318.5  2724.6  317.59  2771.7   315.4  2984.7  308.25  3365.4  303.41
  3520.3   302.6  3530.9  302.45  3994.1  301.97  4156.5  299.68  4257.5  297.19
  4684.4  297.31  4758.9  297.25  4970.5  300.78  4978.7  299.65  4984.6  286.07
  4986.1  285.07  5061.1  285.07  5062.6  286.07  5065.3  300.59    5092  301.03
  5619.4  297.76  5858.2  297.54  7102.4   297.7  7183.8   297.6  7387.7  298.14
  7539.7  299.58  7751.9  309.31  8009.5  315.28  8090.4  318.57  8124.3  319.35
#Mann= 20 ,-1 , 0
  2711.9    .035       0  2724.6     .05       0  2771.7    .035       0
  2984.7     .05       0  3365.4     .07       0  3520.3    .035       0
  3530.9     .07       0  4156.5     .12       0  4684.4      .1       0
  4758.9     .12       0  4984.6     .05       0  5062.6     .12       0
    5092     .05       0  5619.4     .07       0  5858.2     .12       0
  7102.4     .07       0  7183.8     .12       0  7387.7     .07       0
  7751.9     .05       0  8090.4    .035       0
Bank Sta=4984.6,5062.6
XS Rating Curve= 0 ,0
Exp/Cntr=0.3,0.1

Type RM Length L Ch R = 1 ,160389  ,1108,1108,1108
BEGIN DESCRIPTION:
PEACH CREEK9051
END DESCRIPTION:
XS GIS Cut Line= 3
      2533975.01     13795275.03        2532775.       13792275.
      2529174.98       13791875.
#Sta/Elev= 30
  1768.9  326.76  2275.1  307.56    2724  301.45  2853.8  301.09  3497.7  302.67
  3632.2  296.74  4711.4  297.92  4955.6  299.69  4967.7  298.02  4971.1  284.64
  4972.6  283.64  5049.1  284.64  5050.3  298.95  5171.2  299.04    5322  298.71
  5352.2  288.71  5368.8     295  5467.6  298.95  5665.2  300.04  5763.9  301.48
  6554.2  301.21    6653  300.83  6850.6  298.88  7048.1  300.64  7462.5  307.27
  7645.3  305.71  8068.8  307.82  8431.1  318.17  8529.9  321.07  8622.2  323.26
#Mann= 20 ,-1 , 0
  1768.9     .05       0    2724    .035       0  2853.8     .07       0
  3497.7     .12       0  4711.4      .1       0  4971.1     .05       0
  5049.1      .1       0  5171.2     .12       0  5368.8     .07       0
  5467.6     .12       0  5665.2     .07       0  5763.9     .05       0
  6554.2     .07       0    6653     .12       0  6850.6     .07       0
  7048.1     .05       0  7462.5     .07       0  7645.3     .05       0
  8431.1    .035       0  8529.9     .07       0
Bank Sta=4971.1,5049.1
XS Rating Curve= 0 ,0
Exp/Cntr=0.3,0.1

Type RM Length L Ch R = 1 ,159281  ,1983,1983,1983
BEGIN DESCRIPTION:
PEACH CREEK9050
END DESCRIPTION:
XS GIS Cut Line= 3
      2537058.77     13790541.14      2532954.56     13791395.32
      2529774.95       13791525.
#Sta/Elev= 30
   678.4  311.36   900.9  310.31  1315.7  311.65    1692  297.22  1865.8  296.62
    1967   296.8  2046.4  299.37  2081.6   289.3    2258  297.46  2441.6  296.17
  2801.1   293.2  2919.2  284.54  2939.6  296.87  3029.4  298.26  3947.7  297.78
  4065.4  296.57  4338.3  296.22  4496.7  296.49  4597.9  297.72  4699.1  295.15
  4800.3  297.74  4960.2  298.97    4961  283.97  4962.5  282.97  5039.5  283.97
  5040.3  298.31  5050.3   300.1  5295.4  298.48    7207  305.33  8052.8  315.26
#Mann= 20 ,-1 , 0
   678.4     .12       0   900.9     .05       0    1692     .12       0
  1865.8     .12       0    1967      .1       0    2258     .12       0
  2441.6     .05       0  2801.1      .1       0  3029.4     .05       0
  3947.7     .12       0  4065.4     .05       0  4338.3     .07       0
  4496.7     .05       0  4597.9     .07       0  4699.1     .05       0
  4800.3     .12       0    4961     .05       0  5039.5      .1       0
  5295.4     .05       0    7207     .07       0
Bank Sta=4961,5039.5
XS Rating Curve= 0 ,0
Exp/Cntr=0.3,0.1

Type RM Length L Ch R = 1 ,157298  ,2011,2011,2011
BEGIN DESCRIPTION:
PEACH CREEK9049
END DESCRIPTION:
XS GIS Cut Line= 3
      2535375.03     13789324.99      2532454.56     13790103.65
      2529643.79     13791040.57
#Sta/Elev= 30
    2310  312.55  2430.5   311.8  2628.5  307.55  2775.8  302.05  3003.4  299.85
  3044.8  293.12  3103.8  295.94  3143.9  283.11  3178.8  298.37  3198.8  298.08
  3231.1  293.98  3251.2  297.65  4357.3  295.58  4541.2  292.17  4755.4  295.43
    4930  297.82  4949.1  297.24  4951.3  281.64  4952.8  280.64  5029.8  281.64
  5031.9   295.4  5041.9  297.06  5156.9  296.93  5608.5  294.79  6322.3  297.05
  6680.2  299.31  6824.5  299.85    7070  301.56  7492.8  305.09  8295.3  310.59
#Mann= 16 ,-1 , 0
    2310     .05       0  2430.5     .07       0  2628.5      .1       0
  3198.8     .12       0  3251.2     .05       0  4357.3     .07       0
  4755.4     .05       0    4930      .1       0  4951.3     .05       0
  5029.8      .1       0  5156.9     .05       0  6322.3    .035       0
  6680.2     .07       0  6824.5     .12       0    7070     .07       0
  7492.8     .05       0
Bank Sta=4951.3,5029.8
XS Rating Curve= 0 ,0
Exp/Cntr=0.3,0.1

Type RM Length L Ch R = 1 ,155287  ,2484,2484,2484
BEGIN DESCRIPTION:
PEACH CREEK9048
END DESCRIPTION:
XS GIS Cut Line= 3
      2536204.51     13787916.16      2532912.89     13788874.48
      2530774.97       13789025.
#Sta/Elev= 30
  1232.7  317.53  1978.6  306.54  1984.5  306.49    2310  308.23  2506.1   312.6
  3034.3  307.07  3126.6  302.59  3146.2  301.65  3333.5  295.88  3888.1  297.63
  3898.7  296.74  3900.8  279.79  3902.3  278.79  3979.5  279.79  3981.8  296.84
  4035.5  296.73  4316.4   294.2    4388  293.01  4399.1  286.15  4427.4  294.68
  4947.1  296.31  5009.7   280.5  5026.9  290.36  5633.1   291.3  5821.7  293.69
  5861.8  287.01  6097.4  300.66  6292.7  305.93  6336.4  306.53  6804.2   312.2
#Mann= 20 ,-1 , 0
  1232.7     .05       0  1978.6    .035       0  1984.5     .05       0
    2310     .07       0  2506.1     .07       0  3034.3     .05       0
  3126.6     .07       0  3146.2     .12       0  3333.5      .1       0
  3900.8     .05       0  3979.5      .1       0  4035.5     .05       0
  4316.4     .07       0    4388     .05       0  4947.1      .1       0
  5026.9     .05       0  5633.1     .12       0  6097.4     .07       0
  6292.7     .05       0  6336.4     .07       0
Bank Sta=3900.8,3979.5
XS Rating Curve= 0 ,0
Exp/Cntr=0.3,0.1

Type RM Length L Ch R = 1 ,152803  ,972,972,972
BEGIN DESCRIPTION:
PEACH CREEK 47.0
END DESCRIPTION:
XS GIS Cut Line= 3
      2536024.97     13787724.99        2533025.       13787125.
        2531025.       13788925.
#Sta/Elev= 30
  1925.6   315.2  2061.6  312.05  2967.9  302.99  3398.7   304.5  3549.5  305.49
  3924.4  304.89  4266.2  295.64  4548.5  293.09  4665.7  293.68  4954.4  296.97
    4960   278.5  4961.5   277.5  5052.5   278.5  5063.1     289  5069.8  287.09
  5105.7  295.63  5205.6  295.53  5799.3  294.47  5820.2  291.24  5870.3  295.09
  6641.2  292.38  6747.8  290.14  6868.5  293.73  6896.5  291.39    6904  287.13
  6939.1  286.42  6967.5  292.26  7105.3  294.94  7484.7  310.06  7675.7  312.08
#Mann= 13 ,-1 , 0
  1925.6     .05       0  2061.6    .035       0  2967.9     .05       0
  3398.7    .035       0  3549.5     .05       0  4266.2     .12       0
  4548.5     .07       0  4665.7     .12       0    4960     .05       0
  5052.5     .12       0  5205.6     .05       0  6641.2     .12       0
  7105.3     .07       0
Bank Sta=4960,5052.5
XS Rating Curve= 0 ,0
Exp/Cntr=0.3,0.1

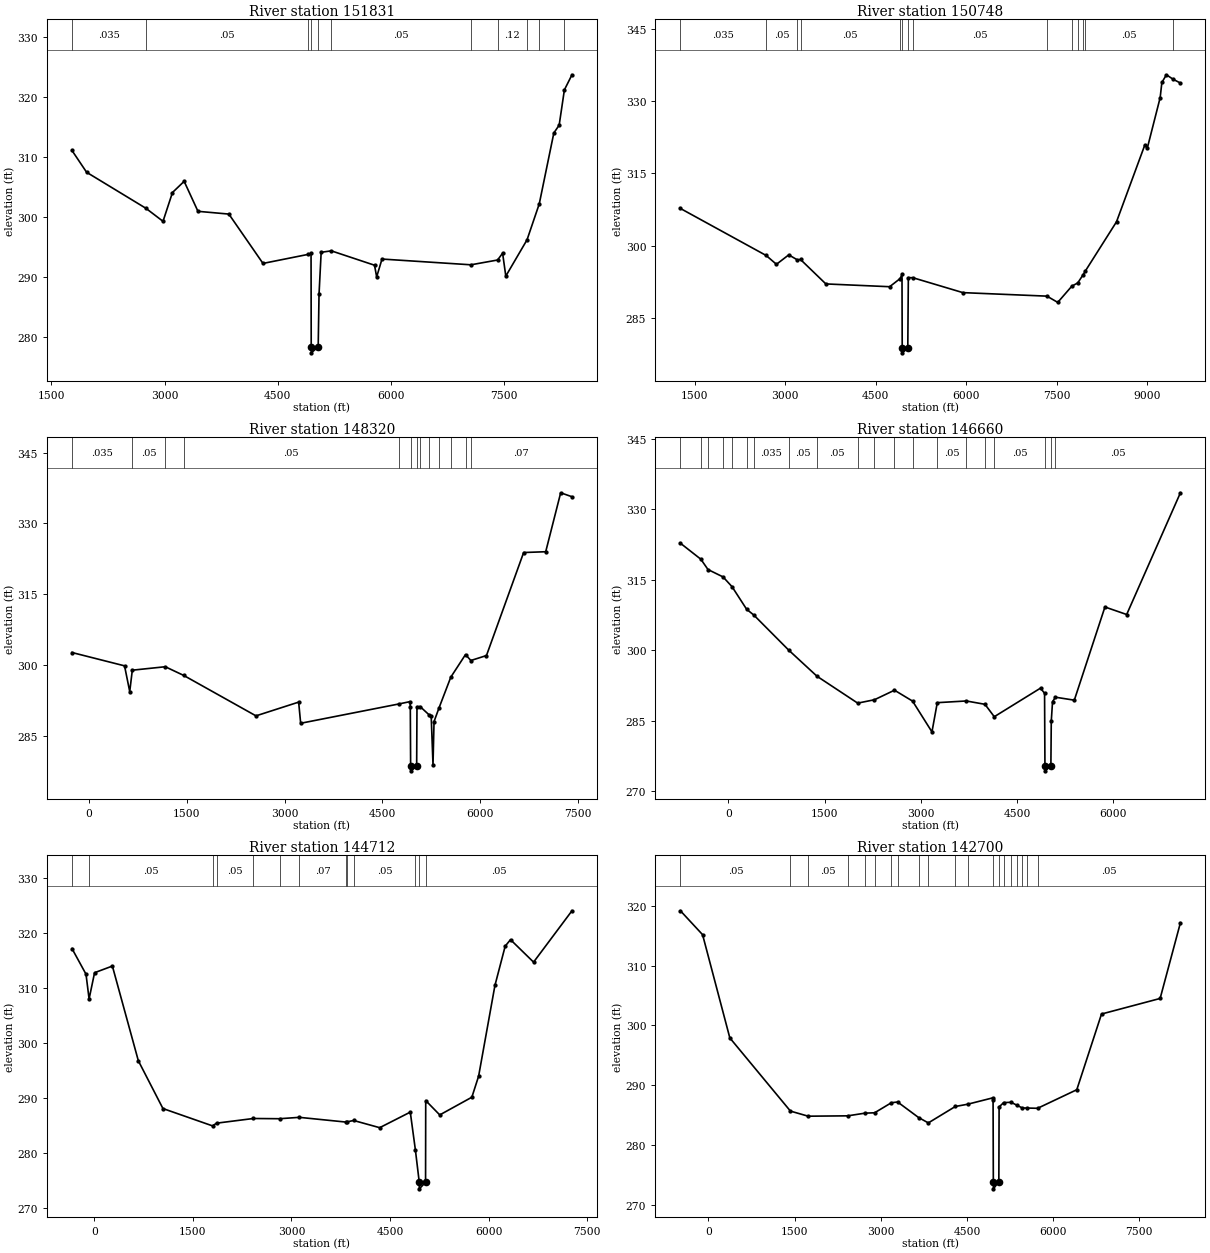
Type RM Length L Ch R = 1 ,151831  ,1083,1083,1083
BEGIN DESCRIPTION:
PEACH CREEK 46.0
END DESCRIPTION:
XS GIS Cut Line= 3
        2535825.       13787475.        2532825.       13786275.
      2530425.01     13788674.99
#Sta/Elev= 30
  1773.1  311.08    1967  307.44  2752.2  301.43  2979.4  299.25  3104.6  304.06
  3259.4  305.93  3442.5  300.92  3851.8  300.46  4304.1  292.22  4898.6  293.72
  4940.9  293.88  4943.1  278.29  4944.6  277.29  5035.6  278.29  5046.6  287.05
  5074.9  294.08  5209.6  294.32    5782  291.92  5810.3  289.97    5881  292.95
  7059.5  291.99  7412.6  292.79  7479.1  293.93  7521.5   290.1  7802.8  296.16
  7964.9  302.17  8157.9     314  8228.6  315.31  8297.9   321.2  8398.3  323.72
#Mann= 11 ,-1 , 0
  1773.1    .035       0  2752.2     .05       0  4898.6      .1       0
  4943.1     .05       0  5035.6      .1       0  5209.6     .05       0
  7059.5     .07       0  7412.6     .12       0  7802.8     .07       0
  7964.9     .05       0  8297.9     .07       0
Bank Sta=4943.1,5035.6
XS Rating Curve= 0 ,0
Exp/Cntr=0.3,0.1

Type RM Length L Ch R = 1 ,150748  ,2428,2428,2428
BEGIN DESCRIPTION:
B19955
END DESCRIPTION:
XS GIS Cut Line= 4
      2535892.08     13787041.16      2533017.06     13785374.48
      2531558.72     13785853.65      2528454.54     13787311.99
#Sta/Elev= 30
  1264.3   307.7  2684.8  297.93    2856  296.09  3059.7  298.05  3203.4  297.01
  3255.3  297.09  3675.1  292.01  4732.5  291.43  4906.1  293.12    4937  293.97
  4940.7  278.68  4942.2  277.68  5033.2  278.68  5042.3  293.32  5117.9   293.3
  5946.4   290.2  7339.8  289.47  7518.8  288.17    7752  291.54  7850.4  292.22
  7939.2  293.91  7978.1  294.73  8492.9  304.93  8960.1  320.83  9005.7  320.36
  9216.5  330.75  9244.8   333.9  9319.7   335.5  9431.3  334.57  9552.2  333.78
#Mann= 14 ,-1 , 0
  1264.3    .035       0  2684.8     .05       0  3203.4     .07       0
  3255.3     .05       0  4906.1      .1       0  4940.7     .05       0
  5033.2      .1       0  5117.9     .05       0  7339.8     .07       0
    7752     .12       0  7850.4     .05       0  7939.2     .12       0
  7978.1     .05       0  9431.3     .07       0
Bank Sta=4940.7,5033.2
XS Rating Curve= 0 ,0
Exp/Cntr=0.3,0.1

Type RM Length L Ch R = 1 ,148320  ,1660,1660,1660
BEGIN DESCRIPTION:
B19954
END DESCRIPTION:
XS GIS Cut Line= 4
      2535579.57     13786457.82      2532517.06     13784603.65
      2530350.39     13785082.82      2528559.34     13785624.29
#Sta/Elev= 30
  -260.7  302.66   545.7  299.84   625.3  294.39   664.8  298.92  1170.5  299.65
  1454.8   297.8  2561.9  289.25  3216.6  292.16  3247.5  287.68  4754.4  291.77
  4923.8  292.26  4929.4  291.15  4934.4  278.61  4935.9  277.61  5026.9  278.61
  5031.8  291.17  5079.6  291.22  5222.7   289.4  5249.8  289.22  5277.6   278.9
  5293.4  288.04  5366.8  290.82  5550.5  297.44  5776.4  302.23  5858.3  300.97
  6097.7  302.02    6668  323.83  7006.6     324  7236.4  336.48  7409.5  335.64
#Mann= 13 ,-1 , 0
  -260.7    .035       0   664.8     .05       0  1170.5    .035       0
  1454.8     .05       0  4754.4      .1       0  4934.4     .05       0
  5026.9      .1       0  5079.6     .12       0  5222.7      .1       0
  5366.8     .12       0  5550.5     .07       0  5776.4     .12       0
  5858.3     .07       0
Bank Sta=4934.4,5026.9
XS Rating Curve= 0 ,0
Exp/Cntr=0.3,0.1

Type RM Length L Ch R = 1 ,146660  ,1948,1948,1948
BEGIN DESCRIPTION:
B19953
END DESCRIPTION:
XS GIS Cut Line= 5
      2534858.23     13780293.73      2532748.83     13782507.29
      2531350.39     13783416.15      2529829.56     13783895.32
      2528496.58     13784520.15
#Sta/Elev= 30
  -747.7  322.76  -429.5  319.36  -317.6  317.16   -82.8  315.59      57  313.51
   284.4  308.71   397.3  307.47   939.5  300.03  1380.7  294.47  2015.1  288.75
  2276.1  289.47  2588.5   291.5  2870.2  289.18  3172.4  282.63  3255.3  288.85
  3707.6  289.21  3998.6   288.5  4143.5  285.86  4864.2  291.94  4927.4  290.84
  4933.2  275.45  4934.7  274.35  5025.8  275.45  5031.9  284.92  5051.6  289.07
  5097.1  290.01    5391  289.38  5868.1   309.2  6206.9   307.6  7044.5  333.49
#Mann= 20 ,-1 , 0
  -747.7     .07       0  -429.5    .035       0  -317.6     .12       0
   -82.8     .12       0      57    .035       0   284.4     .07       0
   397.3    .035       0   939.5     .05       0  1380.7     .05       0
  2015.1     .07       0  2276.1     .12       0  2588.5     .12       0
  2870.2     .07       0  3255.3     .05       0  3707.6     .05       0
  3998.6     .07       0  4143.5     .05       0  4933.2     .05       0
  5025.8      .1       0  5097.1     .05       0
Bank Sta=4933.2,5025.8
XS Rating Curve= 0 ,0
Exp/Cntr=0.3,0.1

Type RM Length L Ch R = 1 ,144712  ,2012,2012,2012
BEGIN DESCRIPTION:
B19952
END DESCRIPTION:
XS GIS Cut Line= 3
      2534142.05     13779541.15      2528850.39     13782624.48
      2528121.22     13783916.15
#Sta/Elev= 30
  -338.7  317.26  -125.2   312.6   -78.3   308.1     5.1  312.87   275.9  314.08
   671.3  296.85  1045.2  288.17  1799.5  285.02    1861  285.51  2421.1  286.36
  2819.2  286.32  3120.4  286.57  3830.9  285.71  3851.1  285.76  3946.8     286
  4343.1  284.69  4808.8  287.52  4886.5  280.64  4945.4  274.77  4946.9  273.57
  5041.3  274.77  5043.7  289.62  5257.1  287.01  5745.7  290.23  5848.5  294.06
  6096.9  310.56  6252.9   317.7  6333.8  318.88  6684.7  314.79    7269  324.13
#Mann= 13 ,-1 , 0
  -338.7     .07       0   -78.3     .05       0  1799.5     .07       0
    1861     .05       0  2421.1     .07       0  2819.2    .035       0
  3120.4     .07       0  3830.9     .05       0  3851.1     .07       0
  3946.8     .05       0  4886.5      .1       0  4945.4     .05       0
  5041.3     .05       0
Bank Sta=4945.4,5041.3
XS Rating Curve= 0 ,0
Exp/Cntr=0.3,0.1

Type RM Length L Ch R = 1 ,142700  ,2055,2055,2055
BEGIN DESCRIPTION:
B19951
END DESCRIPTION:
XS GIS Cut Line= 4
      2534058.69      13778499.5      2528537.89     13780874.48
      2528204.56     13781332.82      2528142.06      13783457.8
#Sta/Elev= 30
  -488.2  319.15  -102.5  315.16   371.9  297.92  1426.7   285.7  1735.3  284.85
  2424.4  284.91    2726  285.36  2891.9  285.42    3184   287.1  3292.5  287.22
  3656.7  284.63  3826.7  283.73  4296.7  286.47    4512  286.85    4948  287.91
  4953.6  287.56  4958.1  273.92  4959.6  272.72    5054  273.92  5058.6  286.39
  5137.3  287.12  5267.8  287.17  5362.4  286.71  5462.9  286.22  5548.6  286.21
  5728.8  286.17  6410.8  289.27    6841  301.91  7861.4  304.51  8214.4  317.15
#Mann= 20 ,-1 , 0
  -488.2     .05       0  1426.7    .035       0  1735.3     .05       0
  2424.4     .12       0    2726     .07       0  2891.9     .05       0
    3184     .12       0  3292.5      .1       0  3656.7     .12       0
  3826.7     .05       0  4296.7     .07       0    4512     .05       0
  4958.1     .05       0    5054     .12       0  5137.3     .07       0
  5267.8     .12       0  5362.4     .07       0  5462.9     .12       0
  5548.6     .07       0  5728.8     .05       0
Bank Sta=4958.1,5054
XS Rating Curve= 0 ,0
Exp/Cntr=0.3,0.1

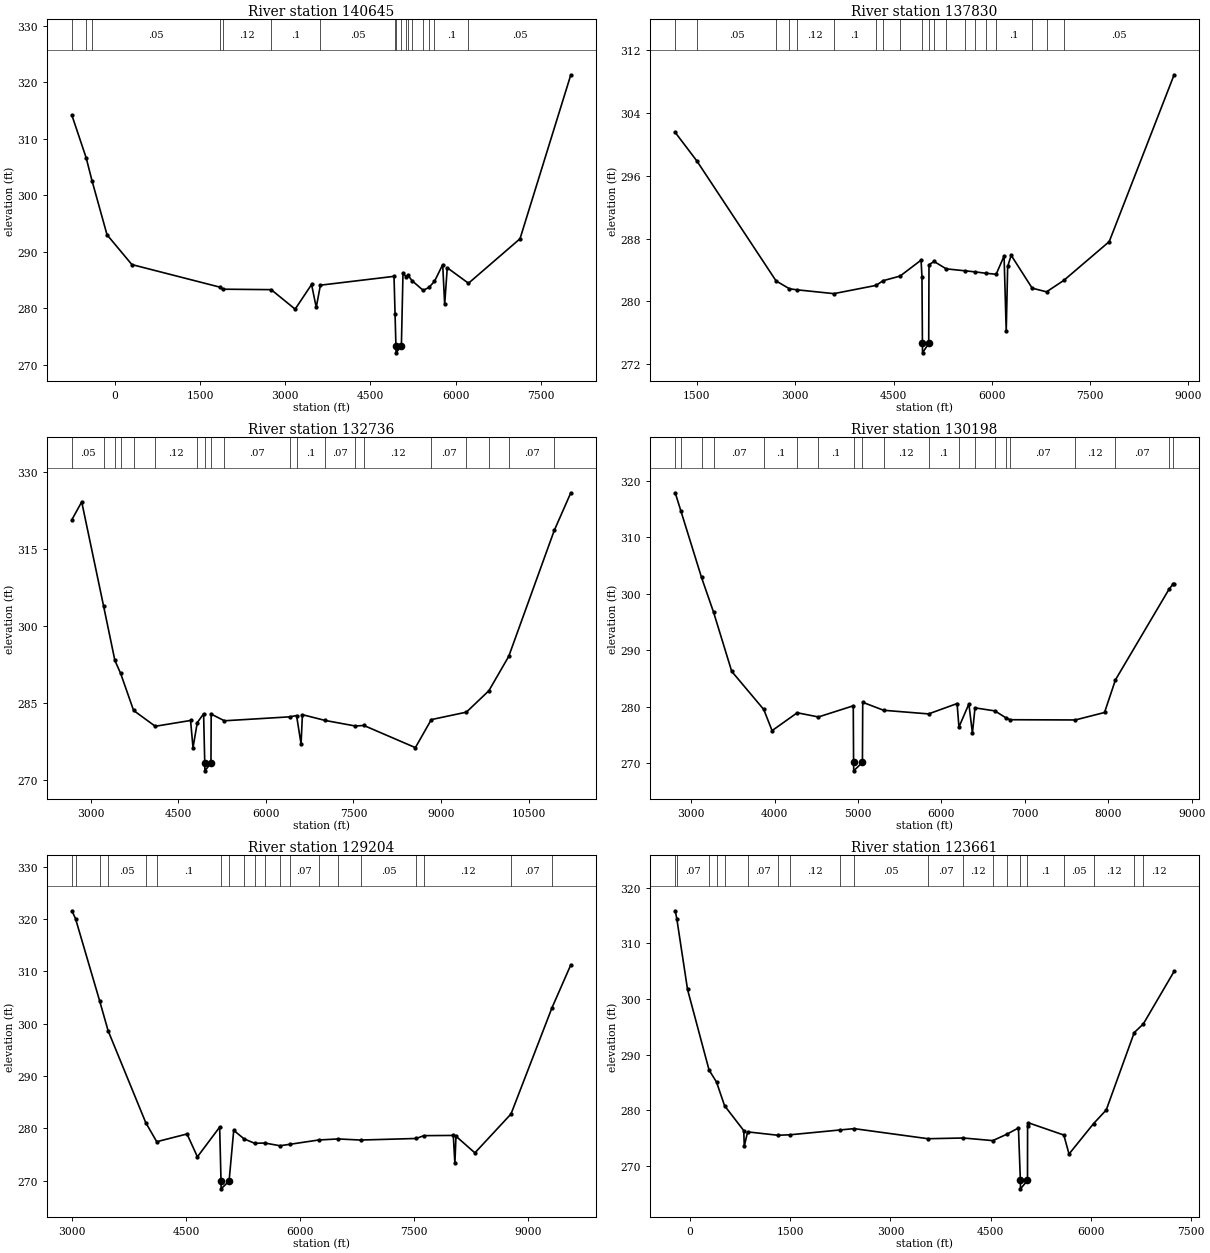
Type RM Length L Ch R = 1 ,140645  ,2815,2815,2815
BEGIN DESCRIPTION:
PEACH CREEK 45.0
END DESCRIPTION:
XS GIS Cut Line= 3
      2533642.09     13777936.97      2527808.72     13779436.98
      2525059.37     13779707.75
#Sta/Elev= 30
    -756  314.12  -505.1  306.61  -402.7  302.58  -137.9  293.01   299.8  287.74
  1850.6  283.75  1896.6  283.39  2753.2  283.31  3174.9  279.86  3464.1  284.22
  3546.7  280.17  3619.5   284.1  4916.3  285.66  4934.3  279.04  4949.8  273.34
  4951.3  272.14  5045.8  273.34  5074.1   286.2  5128.1  285.62  5165.7  285.83
  5230.6  284.92  5430.2  283.18  5529.4  283.69  5628.6  284.77  5773.3  287.73
  5808.3  280.71  5853.7  287.18  6227.4  284.44  7134.7   292.3  8029.8  321.29
#Mann= 17 ,-1 , 0
    -756     .05       0  -505.1    .035       0  -402.7     .05       0
  1850.6     .07       0  1896.6     .12       0  2753.2      .1       0
  3619.5     .05       0  4934.3      .1       0  4949.8     .05       0
  5045.8      .1       0  5128.1     .05       0  5165.7     .12       0
  5230.6     .07       0  5430.2     .12       0  5529.4     .07       0
  5628.6      .1       0  6227.4     .05       0
Bank Sta=4949.8,5045.8
XS Rating Curve= 0 ,0
Exp/Cntr=0.3,0.1

Type RM Length L Ch R = 1 ,137830  ,5094,5094,5094
BEGIN DESCRIPTION:
PEACH CREEK 44.0
END DESCRIPTION:
XS GIS Cut Line= 3
      2532079.58     13776186.98      2528642.06     13777020.32
      2524933.75      13778707.8
#Sta/Elev= 30
  1169.4  301.53  1500.6  297.88  2708.4  282.59  2912.4  281.59  3024.2  281.46
  3590.3  280.97    4233  282.02  4340.7  282.62  4600.2  283.21  4920.3  285.24
    4934   283.1  4940.9  274.62  4942.4  273.42  5036.9  274.62    5041  284.65
  5118.3  285.07  5304.1  284.13  5593.4  283.88  5738.4  283.75  5909.4  283.57
  6065.2  283.44  6186.5  285.76  6219.4  276.18  6241.4  284.44    6295  285.86
  6615.1  281.67  6834.3   281.2  7098.2  282.66  7790.5   287.6  8780.7  308.88
#Mann= 20 ,-1 , 0
  1169.4     .05       0  1500.6     .05       0  2708.4     .07       0
  2912.4      .1       0  3024.2     .12       0  3590.3      .1       0
    4233     .12       0  4340.7     .07       0  4600.2     .05       0
  4940.9     .05       0  5036.9      .1       0  5118.3     .12       0
  5304.1     .07       0  5593.4     .07       0  5738.4    .035       0
  5909.4     .12       0  6065.2      .1       0  6615.1     .12       0
  6834.3     .12       0  7098.2     .05       0
Bank Sta=4940.9,5036.9
XS Rating Curve= 0 ,0
Exp/Cntr=0.3,0.1

Type RM Length L Ch R = 1 ,132736  ,2538,2538,2538
BEGIN DESCRIPTION:
B19950
END DESCRIPTION:
XS GIS Cut Line= 3
      2530725.42     13772353.63      2528683.72     13773749.48
      2523412.91     13776749.47
#Sta/Elev= 30
    2682  320.64  2849.4   324.1  3223.7  303.81  3417.3  293.21  3515.7  290.68
  3737.3  283.47  4108.2  280.39  4712.4  281.52  4754.3  276.22  4827.2   281.1
  4935.6  282.82  4955.3  273.21  4956.8  271.71  5061.4  273.21  5065.2  282.76
  5291.9  281.46  6410.9  282.23  6526.1  282.48  6603.6  276.94  6626.4  282.65
  7018.1  281.52  7533.1  280.44  7677.6  280.55  8559.6  276.23  8832.3  281.69
  9432.6  283.14  9817.3  287.31 10157.4  294.01 10936.2  318.53   11220  325.87
#Mann= 20 ,-1 , 0
    2682     .05       0  3223.7     .07       0  3417.3     .12       0
  3515.7     .07       0  3737.3     .12       0  4108.2     .12       0
  4827.2      .1       0  4955.3     .05       0  5061.4      .1       0
  5291.9     .07       0  6410.9    .035       0  6526.1      .1       0
  7018.1     .07       0  7533.1     .07       0  7677.6     .12       0
  8832.3     .07       0  9432.6     .12       0  9817.3     .12       0
 10157.4     .07       0 10936.2     .05       0
Bank Sta=4955.3,5061.4
XS Rating Curve= 0 ,0
Exp/Cntr=0.3,0.1

Type RM Length L Ch R = 1 ,130198  ,994,994,994
BEGIN DESCRIPTION:
PEACH CREEK 43.0
END DESCRIPTION:
XS GIS Cut Line= 3
        2528375.       13770275.        2527175.       13772075.
        2524475.       13774775.
#Sta/Elev= 30
    2808  317.87  2875.3  314.69  3123.6  302.89    3268  296.74  3485.5  286.28
  3869.6  279.54  3969.3   275.8  4270.9  278.96    4525  278.22  4942.8  280.19
  4946.6  270.19  4948.1  268.69  5052.7  270.19  5056.2  280.81  5307.4   279.4
  5845.7  278.76  6187.6  280.59    6210  276.44    6329  280.52  6371.4  275.34
  6402.4  279.83  6640.9  279.29  6776.3  278.04  6824.8  277.73    7605  277.69
  7955.3  279.01  8086.6  284.79  8729.8  300.84  8774.7  301.67  8789.7  301.75
#Mann= 20 ,-1 , 0
    2808     .05       0  2875.3     .07       0  3123.6     .05       0
    3268     .07       0  3869.6      .1       0  4270.9     .07       0
    4525      .1       0  4946.6     .05       0  5052.7      .1       0
  5307.4     .12       0  5845.7      .1       0    6210      .1       0
  6402.4     .12       0  6640.9     .07       0  6776.3     .05       0
  6824.8     .07       0    7605     .12       0  8086.6     .07       0
  8729.8     .05       0  8774.7     .07       0
Bank Sta=4946.6,5052.7
XS Rating Curve= 0 ,0
Exp/Cntr=0.3,0.1

Type RM Length L Ch R = 1 ,129204  ,5543,5543,5543
BEGIN DESCRIPTION:
PEACH CREEK 42.0
END DESCRIPTION:
XS GIS Cut Line= 3
      2528375.03     13770074.98        2526775.       13771275.
      2523175.03     13774074.98
#Sta/Elev= 30
  3000.5  321.56  3047.9  320.05    3366   304.3  3476.2  298.65  3971.4  281.09
  4115.8  277.45  4514.1  278.93  4650.5  274.56  4943.2  280.24  4961.1  269.95
  4962.6  268.45  5067.2  269.95  5128.1  279.62  5264.8  277.99  5403.1  277.15
  5537.3   277.2  5737.2  276.68  5862.6  276.95  6246.1  277.78  6501.6  277.98
  6796.1  277.77  7527.9  278.07    7630  278.61  8015.7  278.65  8036.5  273.31
    8051   278.5  8299.8  275.32  8774.7  282.75  9313.5  303.04  9561.2  311.24
#Mann= 20 ,-1 , 0
  3000.5     .05       0  3047.9     .07       0    3366     .05       0
  3476.2     .05       0  3971.4     .07       0  4115.8      .1       0
  4961.1     .05       0  5067.2      .1       0  5264.8     .12       0
  5403.1     .07       0  5537.3     .07       0  5737.2     .12       0
  5862.6     .07       0  6246.1     .07       0  6501.6     .07       0
  6796.1     .05       0  7527.9     .07       0    7630     .12       0
  8774.7     .07       0  9313.5     .07       0
Bank Sta=4961.1,5067.2
XS Rating Curve= 0 ,0
Exp/Cntr=0.3,0.1

Type RM Length L Ch R = 1 ,123661  ,1427,1427,1427
BEGIN DESCRIPTION:
PEACH CREEK 41.0
END DESCRIPTION:
XS GIS Cut Line= 3
      2527602.26     13768886.22      2523099.18     13771143.19
      2520788.99     13771891.55
#Sta/Elev= 30
  -220.1  315.86  -196.6  314.46   -35.9  301.74   286.5  287.26   398.2   285.1
   518.2  280.86   805.9  276.38   813.2  273.57   863.3  276.16    1317  275.55
    1502  275.64  2244.7   276.5  2456.8  276.74  3562.9  274.93  4091.9  275.06
    4532  274.59  4740.8  275.73  4915.9  276.86  4944.7  267.43  4946.2  265.93
  5051.4  267.43  5052.6  277.26    5062   277.8  5594.9  275.59  5672.8  272.18
  6041.3  277.66  6229.5  280.09  6648.6  293.99    6784  295.53  7245.3  304.98
#Mann= 20 ,-1 , 0
  -220.1    .035       0  -196.6     .07       0   286.5    .035       0
   398.2     .07       0   518.2     .12       0   863.3     .07       0
    1317     .12       0    1502     .12       0  2244.7    .035       0
  2456.8     .05       0  3562.9     .07       0  4091.9     .12       0
    4532    .035       0  4740.8     .05       0  4944.7     .05       0
  5051.4      .1       0  5594.9     .05       0  6041.3     .12       0
  6648.6    .035       0    6784     .12       0
Bank Sta=4944.7,5051.4
XS Rating Curve= 0 ,0
Exp/Cntr=0.3,0.1