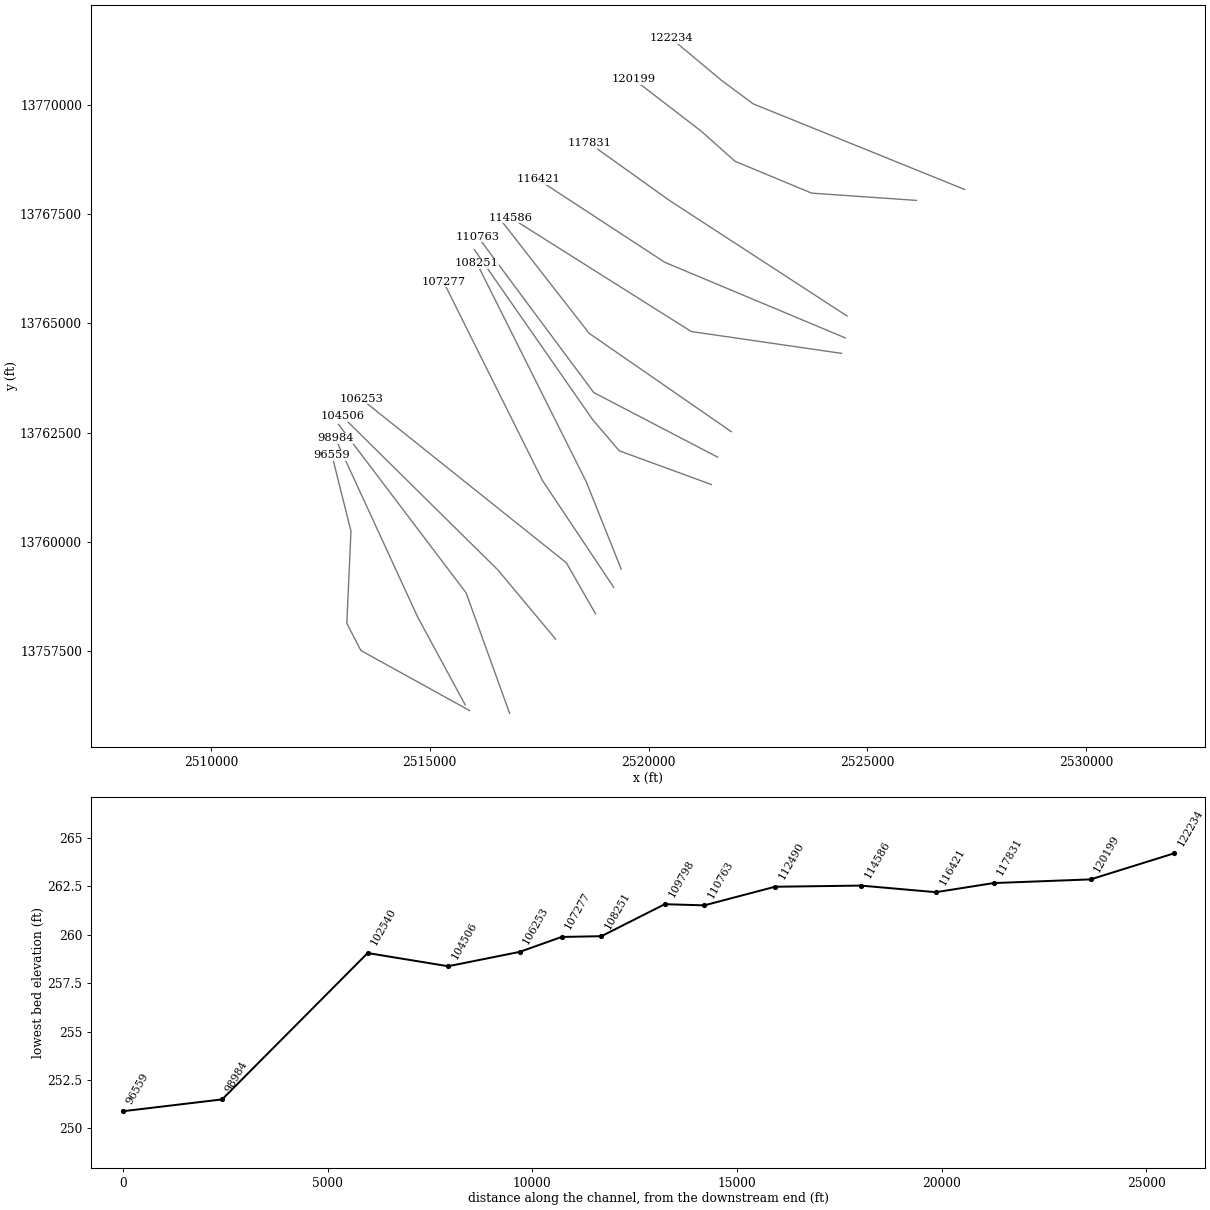
HEC-RAS study PEACH CREEK.prj: PEACH CREEK Base Level Engineering

--- PEACH CREEK.g01 (geometry) --- (continued)

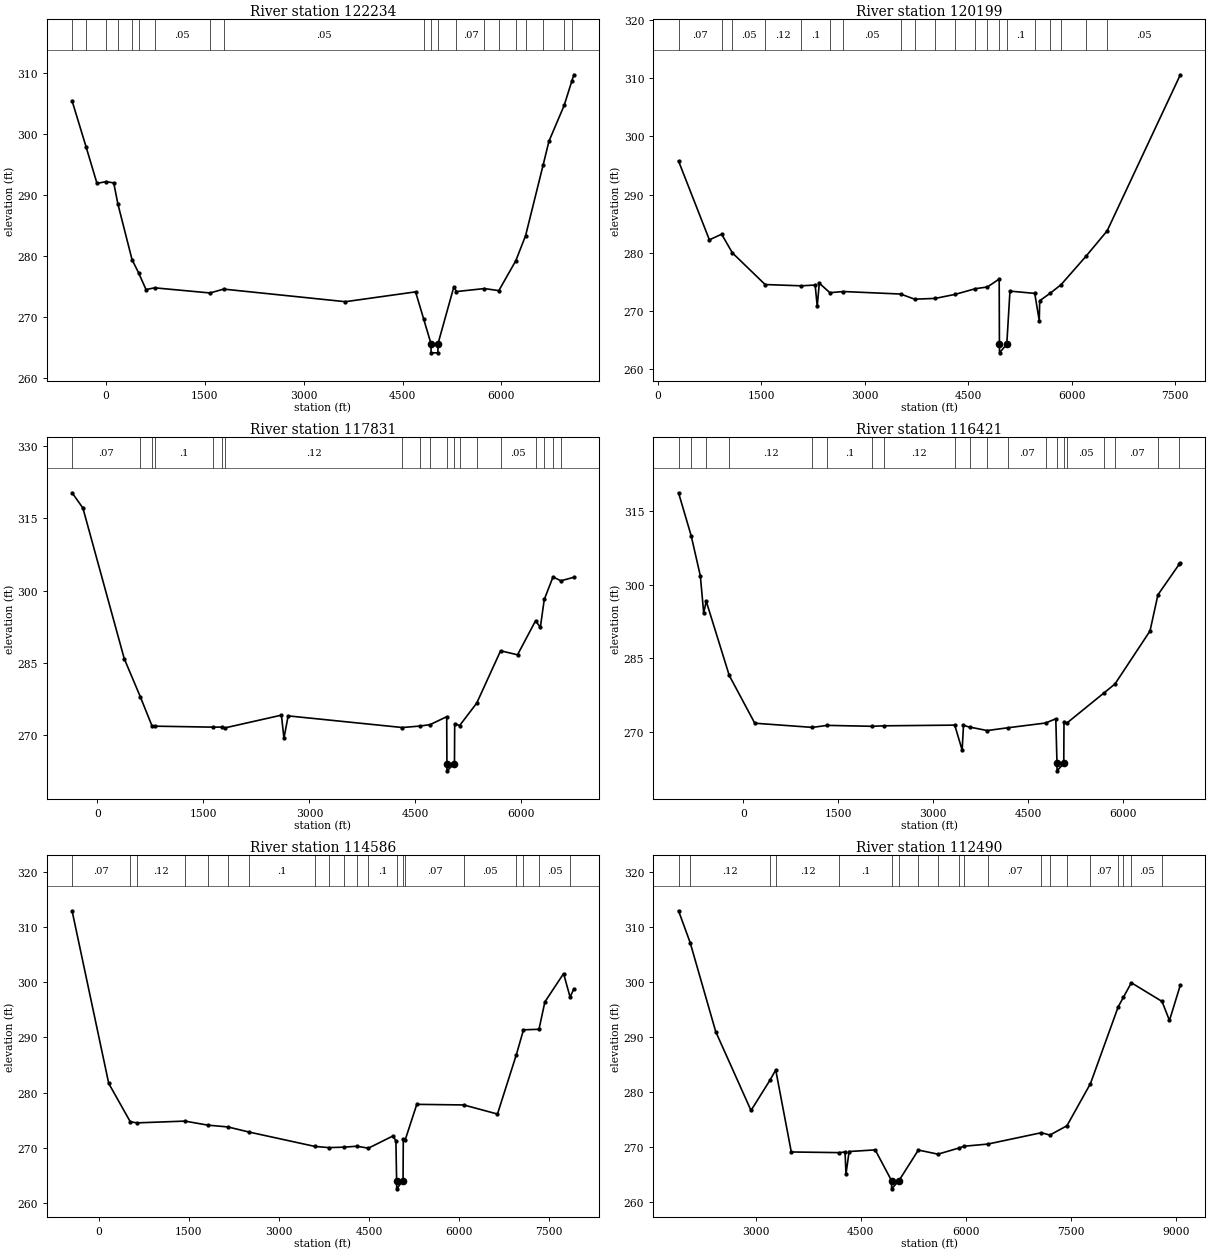
Type RM Length L Ch R = 1 ,122234  ,2035,2035,2035
BEGIN DESCRIPTION:
B19949
END DESCRIPTION:
XS GIS Cut Line= 4
      2527225.37     13768061.99      2522392.06     13770020.32
      2521662.89     13770561.98      2520517.04     13771520.33
#Sta/Elev= 30
  -516.3  305.44  -303.5   297.9  -138.3  291.93     2.3  292.21   116.4     292
   179.2  288.55   394.2  279.44   492.5  277.31   606.2  274.55   737.7  274.83
  1577.6  273.99  1785.4  274.62  3632.7  272.56  4698.2  274.17  4822.7  269.66
  4932.1  265.69  4933.6  264.19  5037.3  264.19  5038.8  265.69  5279.7  275.01
  5318.6  274.22  5743.4  274.71  5961.8  274.37  6219.7  279.27  6368.2  283.37
  6633.1  294.88  6722.5  298.82  6954.4  304.71  7067.9   308.6  7100.8   309.7
#Mann= 20 ,-1 , 0
  -516.3     .05       0  -303.5    .035       0     2.3     .07       0
   179.2     .05       0   394.2     .07       0   492.5     .12       0
   737.7     .05       0  1577.6     .07       0  1785.4     .05       0
  4822.7      .1       0  4932.1     .05       0  5038.8      .1       0
  5318.6     .07       0  5743.4     .12       0  5961.8     .05       0
  6219.7    .035       0  6368.2     .12       0  6633.1     .07       0
  6954.4     .07       0  7067.9     .05       0
Bank Sta=4932.1,5038.8
XS Rating Curve= 0 ,0
Exp/Cntr=0.3,0.1

Type RM Length L Ch R = 1 ,120199  ,2368,2368,2368
BEGIN DESCRIPTION:
B19948
END DESCRIPTION:
XS GIS Cut Line= 5
      2526121.26     13767811.98      2523725.39     13767978.65
      2521975.39     13768707.82      2521204.56     13769395.32
      2519662.87     13770582.83
#Sta/Elev= 30
   300.3  295.76   747.6  282.24   925.5  283.21  1080.6  280.01    1556  274.57
  2078.1  274.35  2281.3  274.48  2311.4  270.84  2341.5   274.8  2494.8  273.17
  2690.8  273.37  3520.3  272.94  3723.7  272.06  4022.8  272.19  4310.9  272.88
  4605.7  273.86  4779.4  274.15    4950  275.51  4953.5  264.35    4955  262.85
  5060.2  264.35  5106.3  273.44  5465.8  273.05  5531.1  268.37  5537.8  271.79
    5691  273.09    5846  274.53  6207.2   279.4    6515  283.77  7576.7  310.56
#Mann= 20 ,-1 , 0
   300.3     .07       0   925.5     .07       0  1080.6     .05       0
    1556     .12       0  2078.1      .1       0  2494.8     .07       0
  2690.8     .05       0  3520.3     .07       0  3723.7     .12       0
  4022.8     .07       0  4310.9     .05       0  4605.7     .07       0
  4779.4      .1       0  4953.5     .05       0  5060.2      .1       0
  5465.8     .12       0    5691     .12       0    5846      .1       0
  6207.2     .12       0    6515     .05       0
Bank Sta=4953.5,5060.2
XS Rating Curve= 0 ,0
Exp/Cntr=0.3,0.1

Type RM Length L Ch R = 1 ,117831  ,1410,1410,1410
BEGIN DESCRIPTION:
PEACH CREEK 40.0
END DESCRIPTION:
XS GIS Cut Line= 3
      2524537.87     13765166.16      2520475.39     13767811.98
      2518642.08     13769124.47
#Sta/Elev= 30
  -359.1  320.24    -206  317.09   379.6  285.88   605.9  278.03   771.2  272.01
   811.1  271.91  1629.6  271.71  1760.1  271.72  1800.7  271.54    2604  274.19
  2640.2  269.41  2699.4  274.04    4316  271.63  4570.3  271.94  4709.1  272.23
  4943.9  273.87    4947  264.16  4948.5  262.66  5053.8  264.16  5056.9  272.44
  5126.8  272.04  5368.2  276.67  5706.8  287.52  5946.3  286.69  6201.2  293.72
  6269.4  292.38  6324.8  298.15  6448.4  302.81  6559.7  302.02  6743.7  302.74
#Mann= 19 ,-1 , 0
  -359.1     .07       0   605.9     .12       0   771.2     .07       0
   811.1      .1       0  1629.6     .12       0  1760.1    .035       0
  1800.7     .12       0    4316     .07       0  4570.3     .12       0
  4709.1      .1       0    4947     .05       0  5053.8      .1       0
  5126.8     .12       0  5368.2     .07       0  5706.8     .05       0
  6201.2    .035       0  6324.8     .05       0  6448.4     .07       0
  6559.7     .05       0
Bank Sta=4947,5053.8
XS Rating Curve= 0 ,0
Exp/Cntr=0.3,0.1

Type RM Length L Ch R = 1 ,116421  ,1835,1835,1835
BEGIN DESCRIPTION:
PEACH CREEK 39.0
END DESCRIPTION:
XS GIS Cut Line= 3
      2524496.26     13764666.13      2520371.22     13766395.32
      2517476.25     13768290.59
#Sta/Elev= 30
   -1023  318.64  -823.5  309.93  -678.4  301.78  -625.4  294.25  -584.9  296.61
  -221.2  281.55   182.1  271.86  1092.6  271.01  1329.1  271.42  2039.7  271.23
    2222  271.33  3343.7  271.47  3460.8  266.39  3481.9  271.41  3578.4  271.08
  3856.3  270.37  4193.5  270.95  4780.4   271.9  4941.2  272.76  4960.2  263.69
  4961.7  262.19  5067.1  263.69  5070.9  272.18  5114.7  271.87  5705.1  278.03
  5877.4  279.83  6430.8  290.59  6555.9  297.93  6893.7  304.16    6910  304.29
#Mann= 20 ,-1 , 0
   -1023     .07       0  -823.5    .035       0  -584.9     .07       0
  -221.2     .12       0  1092.6     .12       0  1329.1      .1       0
  2039.7     .07       0    2222     .12       0  3343.7      .1       0
  3578.4     .12       0  3856.3      .1       0  4193.5     .07       0
  4780.4      .1       0  4960.2     .05       0  5067.1      .1       0
  5114.7     .05       0  5705.1    .035       0  5877.4     .07       0
  6555.9     .07       0  6893.7     .05       0
Bank Sta=4960.2,5067.1
XS Rating Curve= 0 ,0
Exp/Cntr=0.3,0.1

Type RM Length L Ch R = 1 ,114586  ,2096,2096,2096
BEGIN DESCRIPTION:
PEACH CREEK 38.0
END DESCRIPTION:
XS GIS Cut Line= 3
      2524412.93     13764311.98      2520975.39     13764811.98
      2516850.36     13767416.17
#Sta/Elev= 30
  -441.5  312.98   168.9  281.65   527.4   274.7   641.5   274.5  1436.8  274.82
  1816.8  274.09  2152.9  273.76    2497  272.85  3598.2  270.23  3831.7  270.01
  4082.8  270.09  4296.3  270.26  4491.2  269.91  4898.5  272.12  4948.5  271.24
  4960.4  264.03  4961.9  262.53  5067.3  264.03  5071.5   271.5  5101.8  271.37
  5296.3  277.86    6078  277.75  6638.8   276.1  6953.3  286.87  7071.9  291.38
    7330  291.48  7428.3  296.45  7739.4  301.58  7847.8  297.32  7910.5  298.81
#Mann= 20 ,-1 , 0
  -441.5     .07       0   527.4    .035       0   641.5     .12       0
  1436.8     .05       0  1816.8     .05       0  2152.9     .12       0
    2497      .1       0  3598.2    .035       0  3831.7     .07       0
  4082.8    .035       0  4296.3     .07       0  4491.2      .1       0
  4960.4     .05       0  5067.3      .1       0  5101.8     .07       0
    6078     .05       0  6953.3    .035       0  7071.9     .07       0
    7330     .05       0  7847.8     .05       0
Bank Sta=4960.4,5067.3
XS Rating Curve= 0 ,0
Exp/Cntr=0.3,0.1

Type RM Length L Ch R = 1 ,112490  ,1727,1727,1727
BEGIN DESCRIPTION:
PEACH CREEK 37.0
END DESCRIPTION:
XS GIS Cut Line= 3
      2521892.03     13762520.34      2518642.06     13764770.32
      2516663.67     13767310.98
#Sta/Elev= 30
  1894.3     313  2060.3  307.22  2426.3  291.02  2930.4  276.71  3199.6  282.18
  3283.6  284.08  3506.1  269.17  4194.1  269.05  4274.6  269.17  4287.9  265.15
  4332.5  269.25  4705.5  269.55  4938.7  263.97  4940.2  262.47  5045.6  263.97
  5322.4  269.52  5603.4  268.77  5907.8  269.91  5981.9  270.22  6313.2   270.6
  7080.6  272.67  7202.7  272.24  7446.8  273.94  7782.3  281.59  8179.3  295.55
  8253.8  297.29  8366.7  299.92  8805.2  296.53  8912.1  293.07  9067.2   299.5
#Mann= 20 ,-1 , 0
  1894.3     .07       0  2060.3     .12       0  3199.6     .07       0
  3283.6     .12       0  4194.1      .1       0  4938.7     .05       0
  5045.6     .12       0  5322.4     .07       0  5603.4      .1       0
  5907.8     .07       0  5981.9     .12       0  6313.2     .07       0
  7080.6    .035       0  7202.7     .07       0  7446.8     .05       0
  7782.3     .07       0  8179.3     .05       0  8253.8     .07       0
  8366.7     .05       0  8805.2     .07       0
Bank Sta=4938.7,5045.6
XS Rating Curve= 0 ,0
Exp/Cntr=0.3,0.1

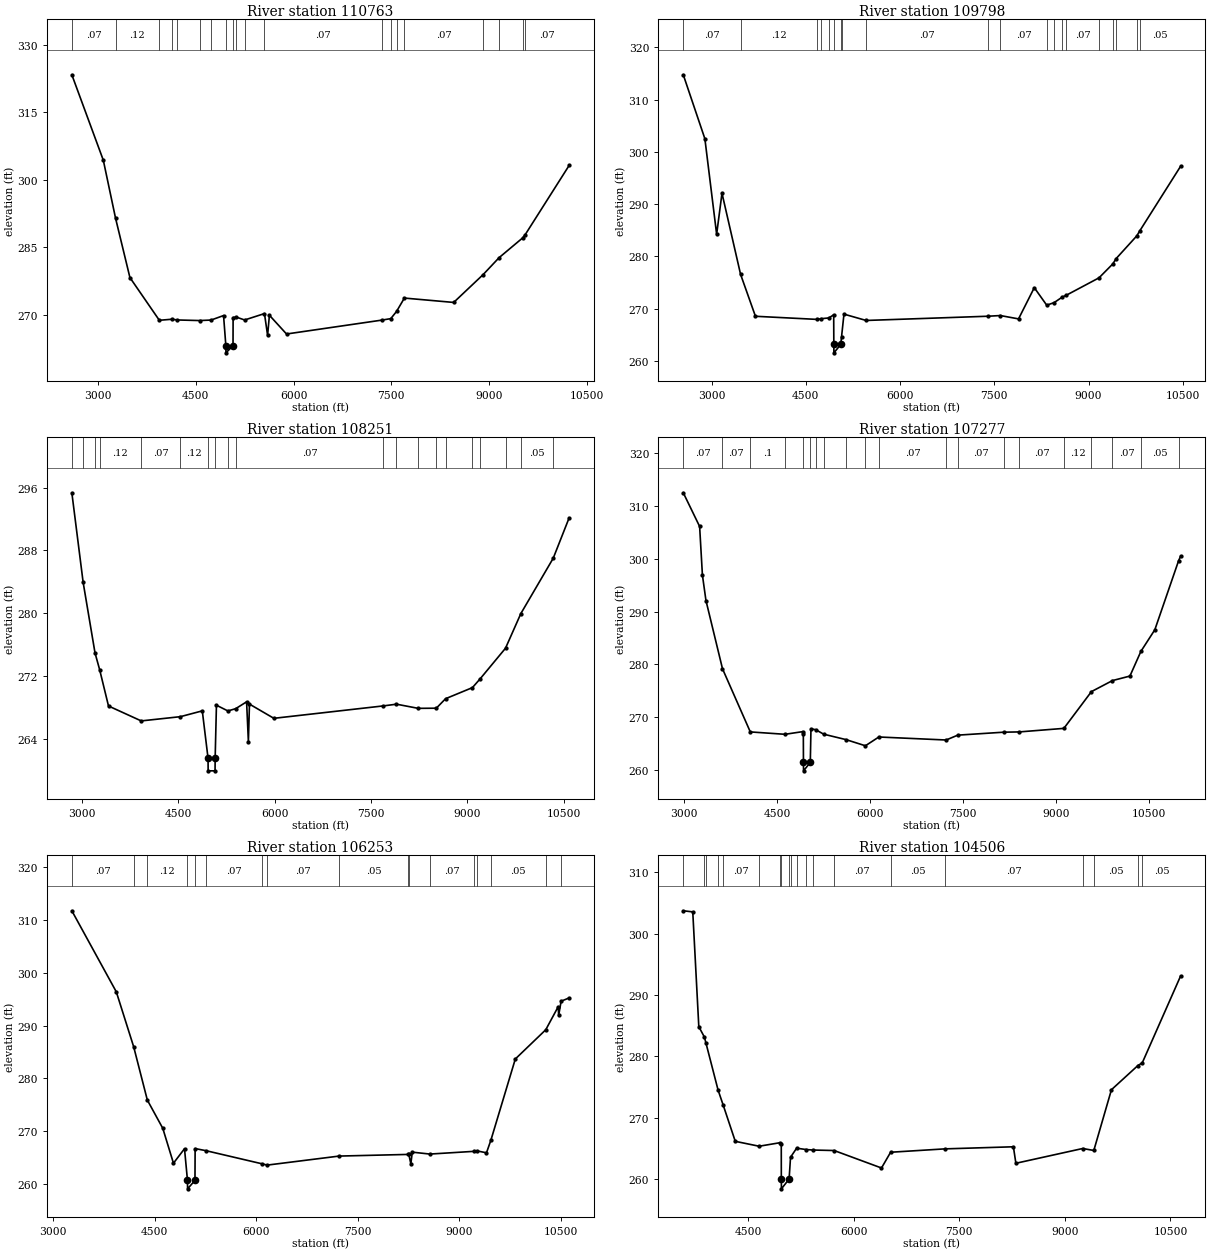
Type RM Length L Ch R = 1 ,110763  ,965,965,965
BEGIN DESCRIPTION:
B19947
END DESCRIPTION:
XS GIS Cut Line= 3
      2521579.53     13761936.99      2518746.22     13763416.15
      2516100.41     13766978.63
#Sta/Elev= 30
  2596.1  323.35  3079.3  304.34  3266.5  291.49  3487.6  278.25  3939.2  268.75
  4131.3  268.98    4218  268.82  4556.2  268.69    4733   268.8    4925   269.8
  4960.3  263.11  4961.8  261.51  5070.3  263.11  5071.7  269.36  5119.9  269.46
  5248.9  268.82  5553.1  270.24  5601.2   265.4  5628.9  269.87  5891.7   265.7
    7356  268.79  7492.3  269.12  7580.7  270.72  7700.8  273.69  8457.7  272.72
  8909.1   278.9  9154.9  282.68  9514.2  287.04  9554.2  287.76 10229.8  303.18
#Mann= 20 ,-1 , 0
  2596.1     .07       0  3266.5     .12       0  3939.2    .035       0
  4131.3     .12       0    4218     .07       0  4556.2     .12       0
    4733      .1       0  4960.3     .05       0  5070.3      .1       0
  5119.9      .1       0  5248.9      .1       0  5553.1     .07       0
    7356     .12       0  7492.3     .07       0  7580.7    .035       0
  7700.8     .07       0  8909.1     .05       0  9154.9     .07       0
  9514.2     .05       0  9554.2     .07       0
Bank Sta=4960.3,5070.3
XS Rating Curve= 0 ,0
Exp/Cntr=0.3,0.1

Type RM Length L Ch R = 1 ,109798  ,1547,1547,1547
BEGIN DESCRIPTION:
B19946
END DESCRIPTION:
XS GIS Cut Line= 4
      2521433.69     13761311.99      2519329.56     13762082.82
      2518725.39     13762791.15      2516017.07     13766686.97
#Sta/Elev= 30
  2548.7  314.73  2892.6   302.5  3079.8  284.24    3165  292.08    3461  276.57
  3697.5  268.56  4684.2  267.96  4744.9   268.1  4865.8  268.24  4943.3  268.84
  4945.4  263.17  4946.9  261.57  5055.4  263.17  5068.6  264.66  5106.9  268.97
  5459.8  267.76    7401  268.57  7596.3   268.7    7886  268.06  8136.7  274.03
  8334.9  270.68  8452.5  271.17  8585.8  272.26  8639.7  272.54  9167.3  275.91
  9386.7  278.57  9439.9  279.59  9769.4  283.94  9812.5  284.82 10465.3  297.22
#Mann= 20 ,-1 , 0
  2548.7     .07       0    3461     .12       0  4684.2     .07       0
  4744.9     .12       0  4865.8      .1       0  4945.4     .05       0
  5055.4      .1       0  5068.6     .12       0  5459.8     .07       0
    7401     .12       0  7596.3     .07       0  8334.9    .035       0
  8452.5     .07       0  8585.8     .05       0  8639.7     .07       0
  9167.3     .05       0  9386.7     .07       0  9439.9     .05       0
  9769.4     .07       0  9812.5     .05       0
Bank Sta=4945.4,5055.4
XS Rating Curve= 0 ,0
Exp/Cntr=0.3,0.1

Type RM Length L Ch R = 1 ,108251  ,974,974,974
BEGIN DESCRIPTION:
PEACH CREEK 36.0
END DESCRIPTION:
XS GIS Cut Line= 3
      2519375.01     13759374.98        2518575.       13761375.
      2516074.98     13766375.03
#Sta/Elev= 30
  2841.7  295.34  3017.8  283.92  3202.6  274.94  3274.2  272.82  3412.6  268.18
  3922.3  266.28  4532.2  266.82  4873.3  267.56  4962.9  261.52  4964.4  259.92
    5072  259.92  5073.5  261.52  5093.6  268.28  5272.1  267.55  5393.5  267.84
  5563.2  268.71  5591.1  263.65  5607.9  268.42    5988  266.61  7691.3  268.19
  7897.7  268.41  8235.8  267.88  8517.8   267.9  8662.1  269.11  9079.8  270.52
  9200.3  271.64  9595.4  275.54  9834.1  279.95 10338.9  287.01   10586  292.14
#Mann= 20 ,-1 , 0
  2841.7     .07       0  3017.8    .035       0  3202.6     .07       0
  3274.2     .12       0  3922.3     .07       0  4532.2     .12       0
  4962.9     .05       0  5073.5      .1       0  5272.1     .07       0
  5393.5     .07       0  7691.3     .12       0  7897.7     .07       0
  8235.8     .12       0  8517.8    .035       0  8662.1     .05       0
  9079.8    .035       0  9200.3     .07       0  9595.4     .12       0
  9834.1     .05       0 10338.9     .05       0
Bank Sta=4962.9,5073.5
XS Rating Curve= 0 ,0
Exp/Cntr=0.3,0.1

Type RM Length L Ch R = 1 ,107277  ,1024,1024,1024
BEGIN DESCRIPTION:
B19945
END DESCRIPTION:
XS GIS Cut Line= 3
      2519204.53     13758957.85      2517579.56     13761395.32
      2515309.37     13765956.52
#Sta/Elev= 30
  2984.1  312.46  3247.9  306.09  3292.9   296.9    3350  292.09    3617  279.18
  4065.7  267.24  4626.2  266.79  4915.4   267.3  4921.4  266.87  4923.2  261.48
  4924.7  259.88  5033.8  261.48  5044.6  267.82  5121.1  267.66  5250.1  266.81
  5608.3  265.79    5923  264.62  6139.9  266.28  7225.6  265.71  7413.9  266.63
  8156.8  267.19    8405  267.24  9125.6  267.91  9570.2  274.86  9910.2  276.95
 10191.4   277.8 10368.7  282.47 10593.5  286.56 10975.7  299.57 11008.5  300.45
#Mann= 20 ,-1 , 0
  2984.1     .07       0    3617     .07       0  4065.7      .1       0
  4626.2     .07       0  4923.2     .05       0  5033.8     .12       0
  5121.1      .1       0  5250.1     .07       0  5608.3     .07       0
    5923     .12       0  6139.9     .07       0  7225.6     .12       0
  7413.9     .07       0  8156.8     .05       0    8405     .07       0
  9125.6     .12       0  9570.2     .07       0  9910.2     .07       0
 10368.7     .05       0 10975.7    .035       0
Bank Sta=4923.2,5033.8
XS Rating Curve= 0 ,0
Exp/Cntr=0.3,0.1

Type RM Length L Ch R = 1 ,106253  ,1747,1747,1747
BEGIN DESCRIPTION:
PEACH CREEK 35.0
END DESCRIPTION:
XS GIS Cut Line= 3
      2518787.89     13758353.64      2518121.22     13759520.32
      2513433.91     13763270.16
#Sta/Elev= 30
  3276.6  311.72  3933.2  296.39    4190  285.99    4392   275.9  4620.1  270.56
  4777.7  263.96    4941   266.7  4984.9  260.71  4986.4  259.11  5095.6  260.71
  5097.9  266.73  5258.3  266.33  6088.4  263.84  6161.7   263.6  7225.8  265.31
    8238  265.62  8254.4  265.63    8285  263.85  8305.8  266.05  8566.4  265.69
    9212   266.2  9261.3  266.29  9402.4  265.93  9467.7  268.33  9828.2  283.68
 10277.9  289.21 10462.1  293.58 10468.5  291.92 10504.9  294.61   10623  295.23
#Mann= 17 ,-1 , 0
  3276.6     .07       0    4190    .035       0    4392     .12       0
  4984.9     .05       0  5095.6     .12       0  5258.3     .07       0
  6088.4     .05       0  6161.7     .07       0  7225.8     .05       0
    8238     .07       0  8254.4     .05       0  8566.4     .07       0
    9212     .05       0  9261.3     .12       0  9467.7     .05       0
 10277.9    .035       0 10504.9     .05       0
Bank Sta=4984.9,5095.6
XS Rating Curve= 0 ,0
Exp/Cntr=0.3,0.1

Type RM Length L Ch R = 1 ,104506  ,1966,1966,1966
BEGIN DESCRIPTION:
PEACH CREEK 33.0
END DESCRIPTION:
XS GIS Cut Line= 3
      2517875.02     13757774.98      2516558.72     13759353.65
      2512996.23     13762874.48
#Sta/Elev= 30
  3579.4  303.73  3714.2  303.55  3800.1  284.82  3879.3  283.13    3901  282.18
  4074.1  274.47  4148.2  271.97  4318.1  266.12  4656.8  265.32  4950.6  265.89
  4971.5  265.66  4972.2  259.97  4973.7  258.37  5082.9  259.97    5103  263.52
  5189.5     265  5326.3  264.78  5421.3   264.7  5722.5  264.62  6395.1  261.77
  6524.9  264.34  7296.5  264.89    8269  265.23  8304.3  262.54  9253.6  264.95
  9411.4  264.63  9661.9  274.54 10038.1  278.49   10100  278.93 10643.6  293.07
#Mann= 20 ,-1 , 0
  3579.4     .07       0  3879.3     .12       0    3901     .07       0
  4074.1     .12       0  4148.2     .07       0  4656.8      .1       0
  4950.6     .07       0  4972.2     .05       0  5082.9     .07       0
    5103     .07       0  5189.5     .05       0  5326.3     .07       0
  5421.3     .05       0  5722.5     .07       0  6524.9     .05       0
  7296.5     .07       0  9253.6     .12       0  9411.4     .05       0
 10038.1     .12       0   10100     .05       0
Bank Sta=4972.2,5082.9
XS Rating Curve= 0 ,0
Exp/Cntr=0.3,0.1

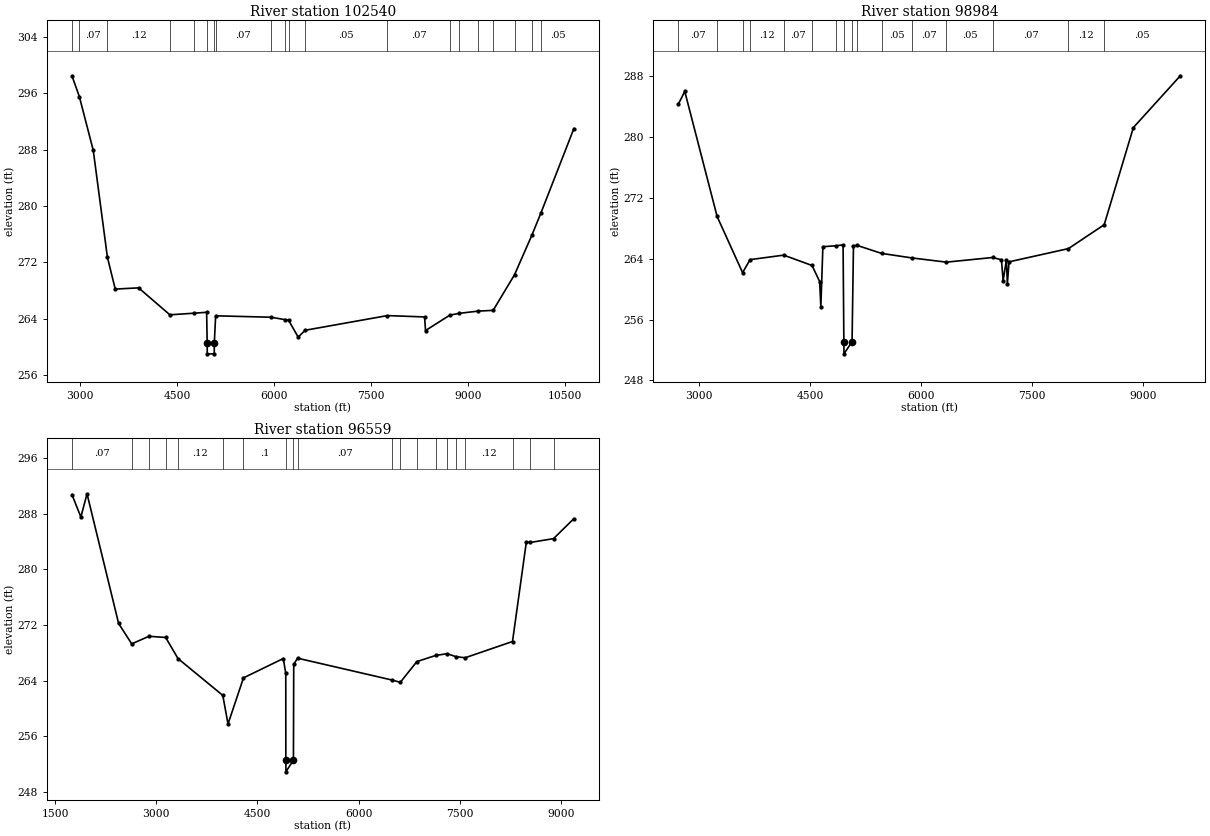
Type RM Length L Ch R = 1 ,102540  ,3556,3556,3556
BEGIN DESCRIPTION:
PEACH CREEK 32.0
END DESCRIPTION:
XS GIS Cut Line= 3
      2516825.01     13756074.98      2515829.56     13758832.82
      2512912.87       13762687.
#Sta/Elev= 30
  2873.9  298.46  2988.2  295.51  3203.5   287.9    3422  272.76  3543.7  268.23
  3905.2   268.4  4389.1  264.58  4764.1  264.81  4957.7  264.94  4966.1  260.65
  4967.6  259.05  5075.4  259.05  5076.9  260.65  5097.1  264.44  5952.9  264.24
  6162.5  263.91  6225.7  263.81  6373.9  261.42  6482.3  262.39  7753.7  264.47
  8329.8  264.28  8344.4  262.35  8719.7  264.53  8866.9  264.79  9161.7  265.11
  9390.4  265.21  9721.8  270.27  9990.1  275.87 10129.7  279.01 10639.3  290.97
#Mann= 20 ,-1 , 0
  2873.9     .05       0  2988.2     .07       0    3422     .12       0
  4389.1     .07       0  4764.1      .1       0  4966.1     .05       0
  5076.9      .1       0  5097.1     .07       0  5952.9     .05       0
  6162.5     .05       0  6225.7     .07       0  6482.3     .05       0
  7753.7     .07       0  8719.7     .12       0  8866.9     .12       0
  9161.7     .12       0  9390.4     .05       0  9721.8     .07       0
  9990.1     .05       0 10129.7     .05       0
Bank Sta=4966.1,5076.9
XS Rating Curve= 0 ,0
Exp/Cntr=0.3,0.1

Type RM Length L Ch R = 1 ,98984   ,2425,2425,2425
BEGIN DESCRIPTION:
PEACH CREEK 31.0
END DESCRIPTION:
XS GIS Cut Line= 3
      2515808.72     13756270.33        2514725.       13758275.
      2512840.84     13762371.63
#Sta/Elev= 30
    2717  284.33    2803  285.98  3240.4  269.55  3584.8  262.17  3686.3  263.88
  4141.2  264.47  4524.1  263.11  4627.1     261  4643.3  257.71  4670.9  265.58
  4843.2   265.7    4944  265.82  4954.6   253.1  4956.1   251.5  5065.5   253.1
  5084.5  265.71  5137.5  265.74  5464.1   264.7  5877.1   264.1  6340.8  263.55
  6966.8  264.16  7085.8  263.86  7108.7  261.13  7153.2  263.87  7165.7  260.69
  7188.7  263.59  7992.1  265.33  8475.6  268.47  8870.3  281.24    9505  288.04
#Mann= 16 ,-1 , 0
    2717     .07       0  3240.4     .12       0  3584.8     .07       0
  3686.3     .12       0  4141.2     .07       0  4524.1     .12       0
  4843.2      .1       0  4954.6     .05       0  5065.5      .1       0
  5137.5     .07       0  5464.1     .05       0  5877.1     .07       0
  6340.8     .05       0  6966.8     .07       0  7992.1     .12       0
  8475.6     .05       0
Bank Sta=4954.6,5065.5
XS Rating Curve= 0 ,0
Exp/Cntr=0.3,0.1

Type RM Length L Ch R = 1 ,96559   ,1759,1759,1759
BEGIN DESCRIPTION:
B19944
END DESCRIPTION:
XS GIS Cut Line= 5
      2515910.38     13756138.56      2513423.99     13757513.61
      2513103.78      13758135.2      2513197.96     13760244.82
      2512764.72     13761977.76
#Sta/Elev= 30
  1751.6  290.75  1883.9  287.53  1974.9  290.87  2443.4  272.22  2637.3  269.29
  2893.2  270.38  3140.7  270.21  3323.2  267.18  3987.3  261.88  4064.6  257.77
  4293.9   264.4  4883.4  267.18  4920.7  265.04  4921.4  252.59  4922.9  250.89
    5034  252.59  5038.5  266.36    5096  267.23    6495  264.09  6618.1  263.76
  6863.2  266.74    7141  267.62  7313.2  267.88  7438.3  267.46  7578.3  267.29
  8280.9  269.63  8486.3  283.96  8543.8  283.87  8888.6  284.42  9190.1  287.29
#Mann= 20 ,-1 , 0
  1751.6     .07       0  2637.3     .12       0  2893.2     .07       0
  3140.7     .07       0  3323.2     .12       0  3987.3      .1       0
  4293.9      .1       0  4921.4     .05       0    5034      .1       0
    5096     .07       0    6495     .12       0  6618.1     .07       0
  6863.2     .07       0    7141     .12       0  7313.2     .12       0
  7438.3     .07       0  7578.3     .12       0  8280.9     .07       0
  8543.8     .05       0  8888.6     .05       0
Bank Sta=4921.4,5034
XS Rating Curve= 0 ,0
Exp/Cntr=0.3,0.1