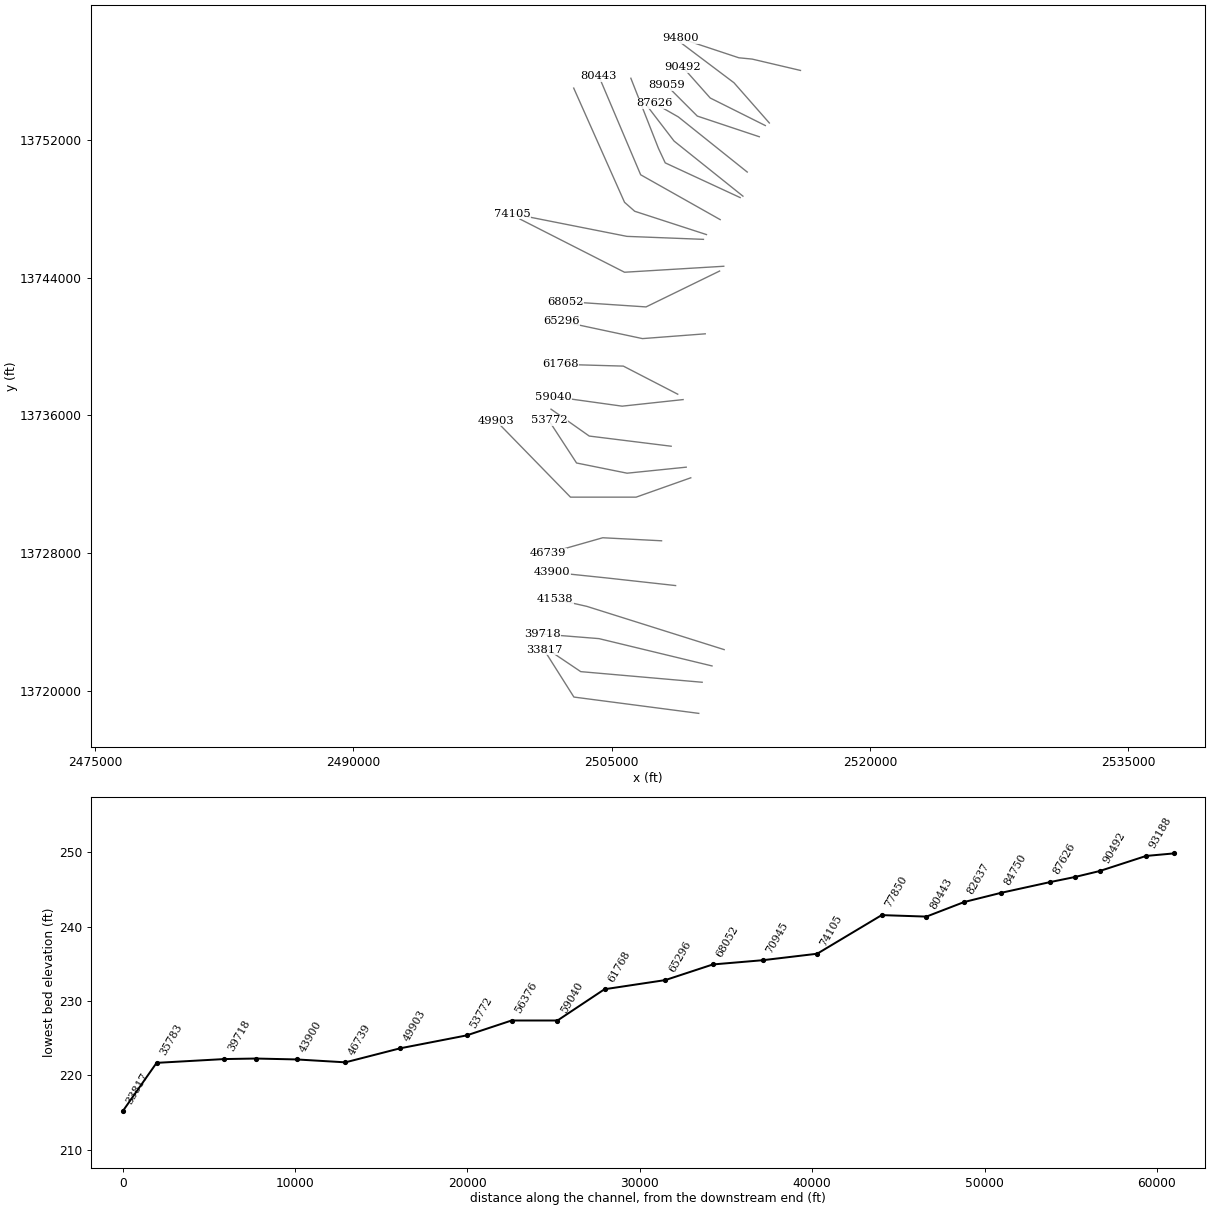
HEC-RAS study PEACH CREEK.prj: PEACH CREEK Base Level Engineering

--- PEACH CREEK.g01 (geometry) --- (continued)

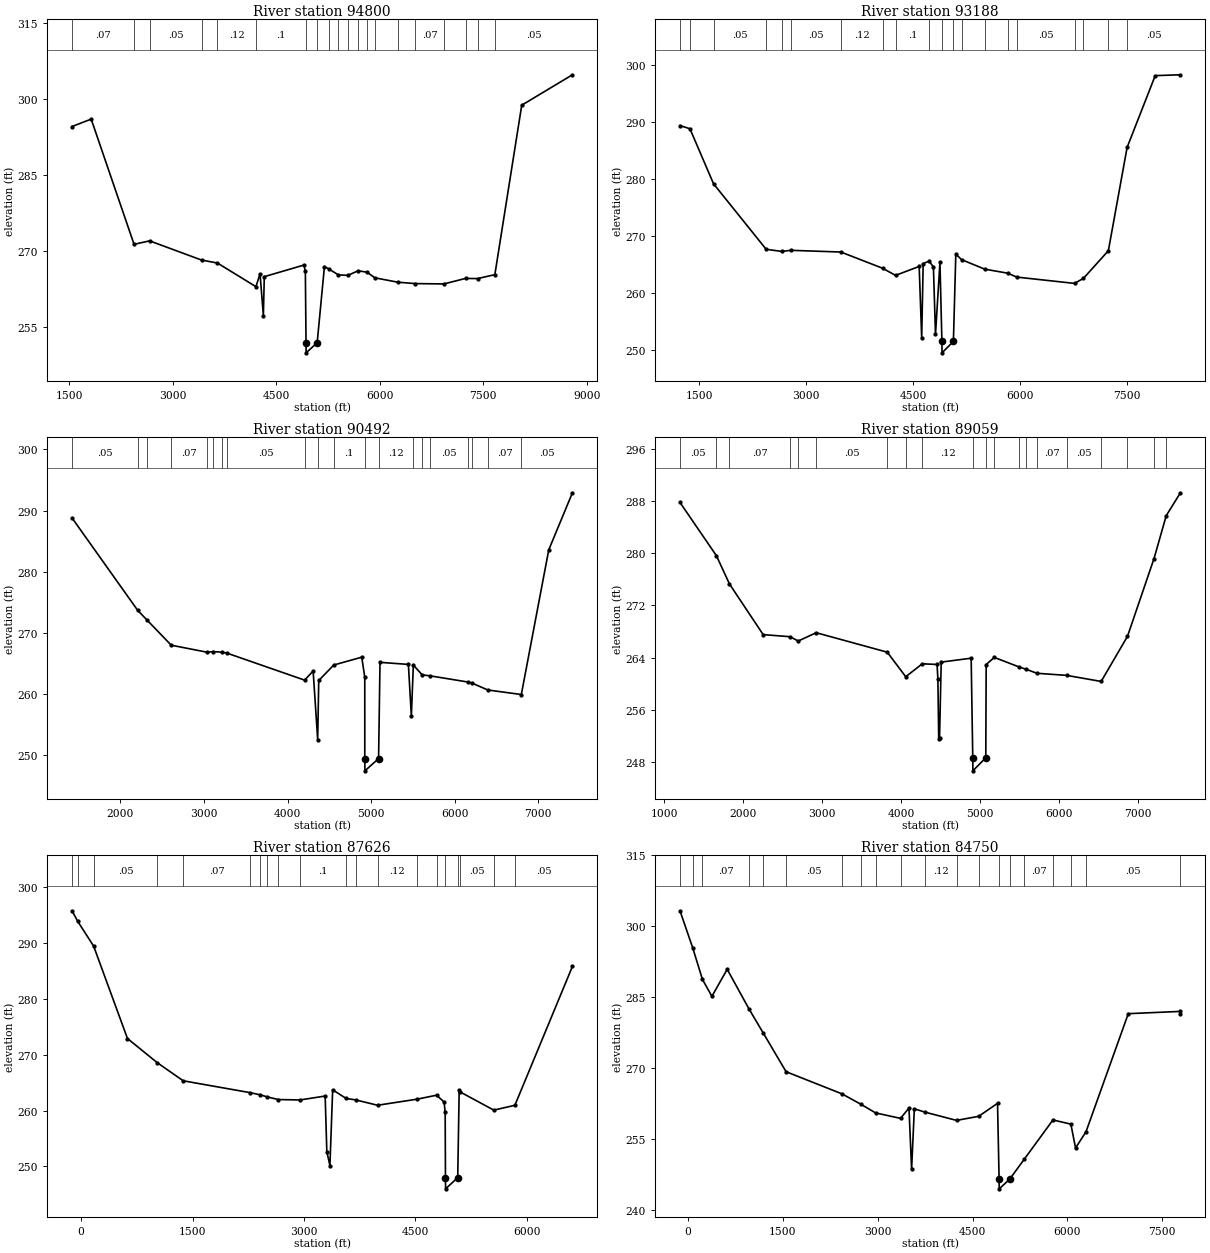
Type RM Length L Ch R = 1 ,94800   ,1612,1612,1612
BEGIN DESCRIPTION:
B19943
END DESCRIPTION:
XS GIS Cut Line= 4
      2515966.88     13756025.56      2513160.29     13756684.83
      2512388.01     13756760.17      2508979.82     13757889.96
#Sta/Elev= 30
  1543.7  294.54  1821.7     296  2442.5  271.27  2668.2  271.95  3419.8  268.16
  3650.8  267.57  4208.5   262.9  4267.8  265.45  4316.1  257.19  4329.4  264.88
  4904.2  267.17  4924.3  265.92  4934.1  251.83  4935.6  249.83  5095.5  251.83
  5200.7  266.87  5261.1  266.43  5401.2  265.24  5539.3  265.13  5689.5  266.04
  5818.2  265.76  5931.2  264.65  6266.1  263.78  6517.7  263.51  6930.9  263.44
  7244.7  264.53    7419   264.5  7669.6  265.28    8059  298.75  8793.2  304.76
#Mann= 20 ,-1 , 0
  1543.7     .07       0  2442.5     .12       0  2668.2     .05       0
  3419.8     .07       0  3650.8     .12       0  4208.5      .1       0
  4934.1     .05       0  5095.5      .1       0  5261.1     .05       0
  5401.2     .12       0  5539.3     .07       0  5689.5     .07       0
  5818.2     .12       0  5931.2     .07       0  6266.1     .05       0
  6517.7     .07       0  6930.9     .05       0  7244.7     .07       0
    7419     .12       0  7669.6     .05       0
Bank Sta=4934.1,5095.5
XS Rating Curve= 0 ,0
Exp/Cntr=0.3,0.1

Type RM Length L Ch R = 1 ,93188   ,2696,2696,2696
BEGIN DESCRIPTION:
PEACH CREEK 30.0
END DESCRIPTION:
XS GIS Cut Line= 3
      2514158.58     13752974.15      2512105.47      13755309.8
      2508979.32     13757663.84
#Sta/Elev= 30
  1226.7  289.41  1366.5  288.86  1697.6  279.19  2436.3  267.68    2653  267.31
  2784.6   267.5  3484.9   267.2  4070.5  264.35  4252.2   263.1  4583.6  264.67
    4619  252.11  4639.9  265.17  4723.6   265.6  4783.5  264.57  4812.7  252.75
  4875.3  265.38  4902.7  251.49  4904.2  249.49  5064.1  251.49  5097.9  266.84
    5179  265.86  5504.3  264.19  5828.1  263.48  5951.3   262.8  6763.7  261.69
  6889.6  262.58  7238.8  267.43  7501.8  285.57  7896.4  298.19  8249.8  298.34
#Mann= 20 ,-1 , 0
  1226.7     .05       0  1366.5     .07       0  1697.6     .05       0
  2436.3     .05       0    2653    .035       0  2784.6     .05       0
  3484.9     .12       0  4070.5     .07       0  4252.2      .1       0
  4723.6     .12       0  4902.7     .05       0  5064.1      .1       0
    5179     .07       0  5504.3     .07       0  5828.1     .07       0
  5951.3     .05       0  6763.7     .07       0  6889.6     .12       0
  7238.8     .07       0  7501.8     .05       0
Bank Sta=4902.7,5064.1
XS Rating Curve= 0 ,0
Exp/Cntr=0.3,0.1

Type RM Length L Ch R = 1 ,90492   ,1433,1433,1433
BEGIN DESCRIPTION:
PEACH CREEK 29.0
END DESCRIPTION:
XS GIS Cut Line= 3
        2513925.       13752825.        2510725.       13754425.
      2509125.02     13756224.98
#Sta/Elev= 30
  1421.7  288.81  2207.9  273.69  2315.2  272.17  2608.8     268    3039  266.85
  3110.5  266.95  3212.9  266.86  3274.2  266.71    4204  262.29  4306.2  263.78
  4360.6  252.56  4373.3  262.23  4552.8  264.76  4887.6  266.04  4923.9  262.77
    4924  249.46  4925.5  247.46  5089.1  249.46    5106   265.2  5445.5  264.86
  5481.1  256.43  5504.9  264.75  5611.7  263.14    5702     263    6162  261.97
  6204.8  261.82  6394.7  260.68  6796.5  259.94  7124.7  283.59  7407.7  292.92
#Mann= 20 ,-1 , 0
  1421.7     .05       0  2207.9    .035       0  2315.2     .05       0
  2608.8     .07       0    3039    .035       0  3110.5     .05       0
  3212.9     .12       0  3274.2     .05       0    4204      .1       0
  4360.6    .035       0  4552.8      .1       0    4924     .05       0
  5089.1     .12       0  5504.9     .05       0  5611.7    .035       0
    5702     .05       0    6162     .07       0  6204.8     .05       0
  6394.7     .07       0  6796.5     .05       0
Bank Sta=4924,5089.1
XS Rating Curve= 0 ,0
Exp/Cntr=0.3,0.1

Type RM Length L Ch R = 1 ,89059   ,1433,1433,1433
BEGIN DESCRIPTION:
PEACH CREEK 28.0
END DESCRIPTION:
XS GIS Cut Line= 3
      2513575.03     13752174.99        2509975.       13753375.
      2508174.97     13755175.03
#Sta/Elev= 30
  1200.6  287.76    1662  279.61  1827.4  275.28  2254.7  267.52  2594.2   267.2
    2699  266.54  2926.7  267.81  3826.9  264.83    4061  261.07  4270.6  263.05
  4457.8  262.95  4468.3  260.77  4478.9  251.56  4489.4  251.73  4510.5  263.31
    4890  263.91  4910.2  248.66  4911.7  246.66  5075.3  248.66  5080.2  262.94
    5183  264.03  5494.8  262.58  5589.2   262.2  5723.6   261.6  6098.4  261.28
    6537  260.35    6870  267.24    7207  279.17  7361.7  285.74    7541  289.24
#Mann= 20 ,-1 , 0
  1200.6     .05       0    1662    .035       0  1827.4     .07       0
  2594.2    .035       0    2699     .07       0  2926.7     .05       0
  3826.9     .07       0    4061     .07       0  4270.6     .12       0
  4910.2     .05       0  5075.3      .1       0    5183     .05       0
  5494.8     .07       0  5589.2     .05       0  5723.6     .07       0
  6098.4     .05       0    6537    .035       0    6870    .035       0
    7207    .035       0  7361.7     .05       0
Bank Sta=4910.2,5075.3
XS Rating Curve= 0 ,0
Exp/Cntr=0.3,0.1

Type RM Length L Ch R = 1 ,87626   ,2876,2876,2876
BEGIN DESCRIPTION:
PEACH CREEK 27.0
END DESCRIPTION:
XS GIS Cut Line= 3
      2512874.98     13750125.02        2508875.       13753325.
      2507475.02     13754124.99
#Sta/Elev= 30
  -122.6  295.78   -44.7  293.87   168.6  289.45   624.1   272.9  1023.1  268.59
  1374.3  265.33  2277.4   263.2  2406.4  262.83  2500.3  262.47  2652.5  261.97
  2946.3   261.9  3284.6   262.6    3307  252.65  3348.7  250.15  3385.5  263.72
  3567.4  262.16  3696.4  261.91  3989.2  260.95    4523  262.04  4783.5  262.75
  4885.4  261.54  4899.8  259.66  4903.7  247.98  4905.2  245.98  5068.8  247.98
  5088.4  263.72  5103.2  263.32  5554.2  260.08  5837.9  260.94  6612.3  285.81
#Mann= 20 ,-1 , 0
  -122.6    .035       0   -44.7    .035       0   168.6     .05       0
  1023.1     .07       0  1374.3     .07       0  2277.4     .12       0
  2406.4      .1       0  2500.3     .12       0  2652.5    .035       0
  2946.3      .1       0  3567.4     .12       0  3696.4     .07       0
  3989.2     .12       0    4523     .07       0  4783.5      .1       0
  4903.7     .05       0  5068.8      .1       0  5103.2     .05       0
  5554.2     .12       0  5837.9     .05       0
Bank Sta=4903.7,5068.8
XS Rating Curve= 0 ,0
Exp/Cntr=0.3,0.1

Type RM Length L Ch R = 1 ,84750   ,2113,2113,2113
BEGIN DESCRIPTION:
PEACH CREEK 26.0
END DESCRIPTION:
XS GIS Cut Line= 3
      2512625.04     13748724.97        2508625.       13751925.
      2506926.33       13754141.
#Sta/Elev= 30
  -127.4   303.3    74.8  295.43   228.1  288.78   377.7  285.22   619.4  290.93
   962.4  282.59  1192.1   277.4  1550.6  269.28  2434.4   264.6  2734.1   262.4
  2966.5  260.57  3360.6  259.42  3494.4  261.59    3536  248.64  3579.3  261.44
  3744.9  260.74  4246.7  258.99  4596.9  259.85  4895.1   262.6  4919.9  246.52
  4921.4  244.52    5085  246.52  5316.1  250.75  5771.4  259.08  6054.9   258.2
  6129.1  253.16  6294.2  256.58  6963.2  281.55  7774.4  282.02  7787.3  281.49
#Mann= 20 ,-1 , 0
  -127.4     .07       0    74.8     .05       0   228.1     .07       0
   962.4     .12       0  1192.1     .07       0  1550.6     .05       0
  2434.4     .12       0  2734.1      .1       0  2966.5     .12       0
  3360.6      .1       0  3744.9     .12       0  4246.7     .07       0
  4596.9     .07       0  4919.9    .035       0    5085    .035       0
  5316.1     .07       0  5771.4     .12       0  6054.9     .07       0
  6294.2     .05       0  7774.4    .035       0
Bank Sta=4919.9,5085
XS Rating Curve= 0 ,0
Exp/Cntr=0.3,0.1

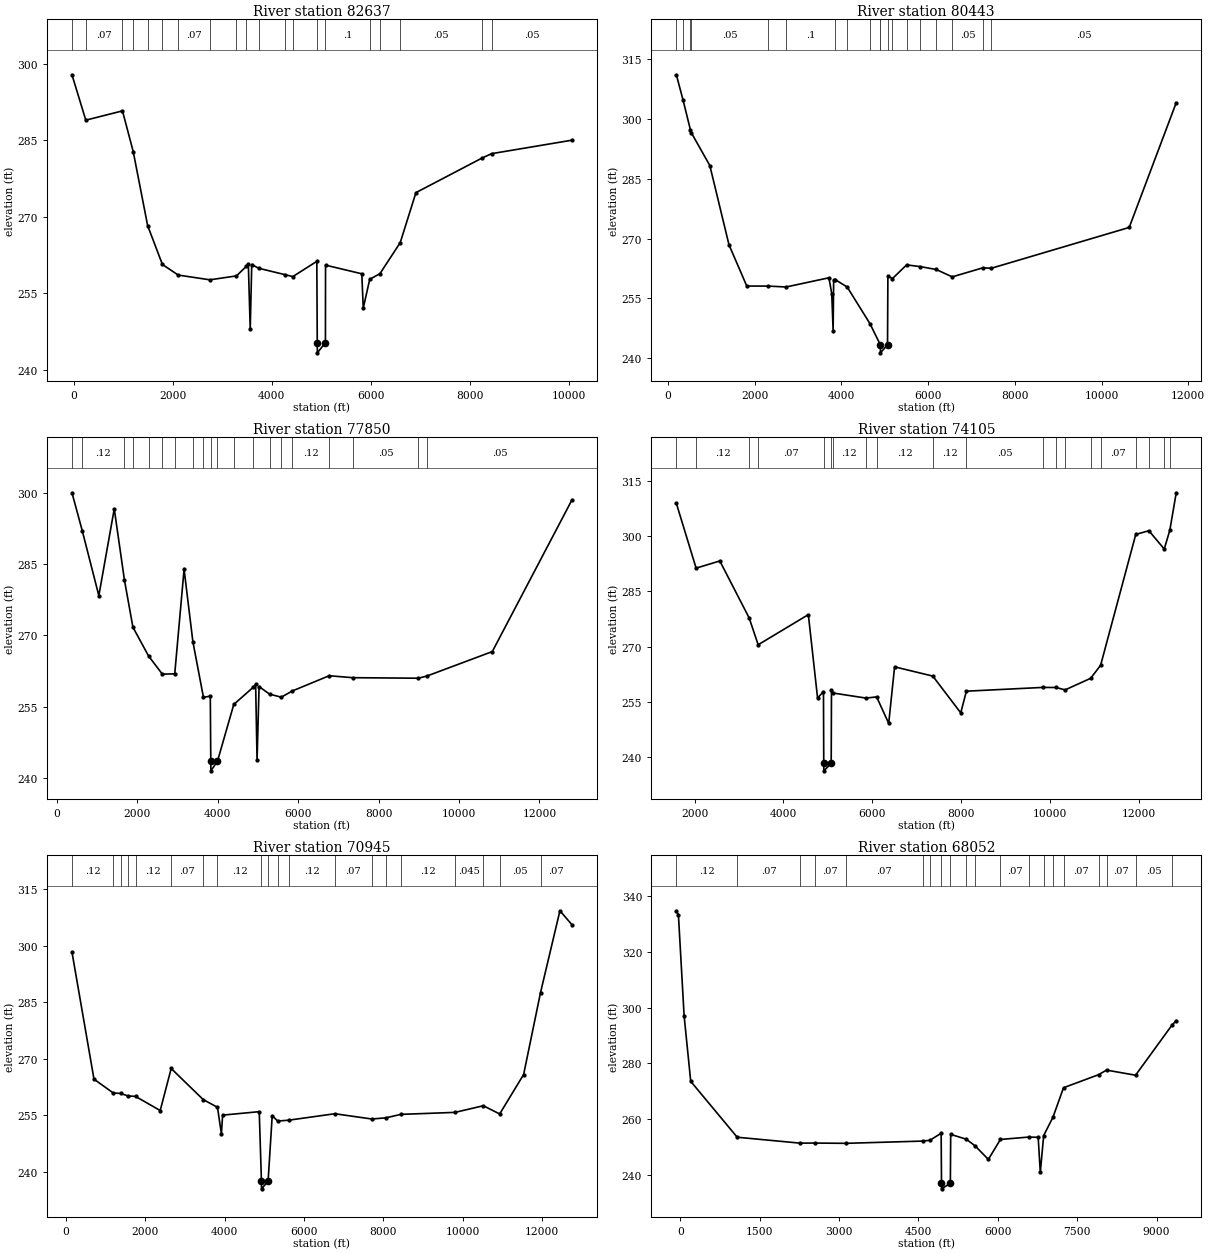
Type RM Length L Ch R = 1 ,82637   ,2194,2194,2194
BEGIN DESCRIPTION:
B19942
END DESCRIPTION:
XS GIS Cut Line= 4
      2512463.34     13748641.88      2508112.25     13750657.32
      2507716.69     13751504.94      2506116.31      13755571.8
#Sta/Elev= 30
   -35.6  297.83   243.7  288.93   984.8  290.75  1201.9  282.77  1493.3  268.25
  1792.1  260.63  2111.3  258.55  2752.4  257.62  3288.3  258.39  3488.6  260.27
  3528.3  260.63  3566.3  247.97    3597  260.62  3736.6  259.89  4273.4  258.62
  4426.7  258.25  4911.9  261.24  4920.8   245.3  4922.3   243.3  5085.9   245.3
  5088.1   260.5  5820.6   258.8  5850.3  252.08  5981.2  257.73    6186  258.81
  6597.1  264.91  6914.8  274.72    8254  281.52  8443.7  282.36 10065.4     285
#Mann= 20 ,-1 , 0
   -35.6     .05       0   243.7     .07       0   984.8     .05       0
  1201.9     .07       0  1493.3     .07       0  1792.1     .05       0
  2111.3     .07       0  2752.4     .05       0  3288.3     .05       0
  3488.6      .1       0  3736.6     .07       0  4273.4     .07       0
  4426.7     .12       0  4920.8     .05       0  5085.9      .1       0
  5981.2    .035       0    6186     .05       0  6597.1     .05       0
    8254    .035       0  8443.7     .05       0
Bank Sta=4920.8,5085.9
XS Rating Curve= 0 ,0
Exp/Cntr=0.3,0.1

Type RM Length L Ch R = 1 ,80443   ,2593,2593,2593
BEGIN DESCRIPTION:
B19941
END DESCRIPTION:
XS GIS Cut Line= 3
      2511304.08     13747361.74      2506686.02     13749965.91
      2504255.48     13755695.05
#Sta/Elev= 30
   197.6   311.1   349.7  304.87   521.2  297.32   546.6  296.49   969.6  288.33
  1411.6  268.43  1821.9  258.09  2318.2  258.09  2728.1  257.86  3715.7  260.17
  3780.7  256.16  3812.5  246.91  3824.4  259.53  3866.7  259.67  4137.1  257.84
    4661  248.67  4890.7  243.58  4901.3  243.34  4902.8  241.34  5066.6  243.34
    5075   260.7  5179.8  259.97  5507.1  263.41  5824.1  262.97  6188.5  262.25
  6558.1   260.4  7261.6  262.66  7463.2  262.57 10638.8   272.8 11722.7   304.1
#Mann= 19 ,-1 , 0
   197.6     .05       0   349.7    .035       0   521.2     .07       0
   546.6     .05       0  2318.2     .12       0  2728.1      .1       0
  3866.7     .07       0  4137.1     .12       0    4661     .07       0
  4890.7      .1       0  4901.3     .05       0  5066.6      .1       0
  5179.8     .05       0  5507.1     .12       0  5824.1     .07       0
  6188.5     .12       0  6558.1     .05       0  7261.6    .035       0
  7463.2     .05       0
Bank Sta=4901.3,5066.6
XS Rating Curve= 0 ,0
Exp/Cntr=0.3,0.1

Type RM Length L Ch R = 1 ,77850   ,3745,3745,3745
BEGIN DESCRIPTION:
B19940
END DESCRIPTION:
XS GIS Cut Line= 4
      2510505.47     13746493.69       2506338.8     13747847.85
      2505748.52     13748368.69      2502797.27     13755000.33
#Sta/Elev= 30
   377.6  299.99     632  292.05  1045.4  278.37  1428.8  296.61  1681.9  281.65
  1892.4  271.74  2281.8  265.68  2623.8  261.87  2932.4  261.93  3164.5  283.92
  3383.2  268.69  3646.6  256.97  3816.5  257.26  3828.4  243.54  3829.9  241.54
  3993.8  243.54  4400.1   255.5    4886  259.12  4943.7   259.7  4978.8  243.76
    5029  259.25  5289.3  257.67  5580.4  257.02  5855.5  258.33  6771.7  261.53
  7358.2  261.12  8990.8  261.01  9208.6  261.49 10826.8  266.61 12804.7  298.45
#Mann= 20 ,-1 , 0
   377.6     .07       0     632     .12       0  1681.9     .07       0
  1892.4     .05       0  2281.8     .07       0  2623.8     .05       0
  2932.4     .07       0  3383.2     .12       0  3646.6      .1       0
  3828.4     .05       0  3993.8      .1       0  4400.1     .05       0
    4886      .1       0  5289.3     .07       0  5580.4     .05       0
  5855.5     .12       0  6771.7     .07       0  7358.2     .05       0
  8990.8    .035       0  9208.6     .05       0
Bank Sta=3828.4,3993.8
XS Rating Curve= 0 ,0
Exp/Cntr=0.3,0.1

Type RM Length L Ch R = 1 ,74105   ,3160,3160,3160
BEGIN DESCRIPTION:
B19939
END DESCRIPTION:
XS GIS Cut Line= 3
      2510331.84     13746215.91      2505887.41     13746389.52
      2499220.75     13747708.96
#Sta/Elev= 30
    1590  308.87  2034.6  291.29  2567.6  293.24  3228.9  277.77  3430.2  270.52
  4559.1  278.69  4766.7  256.08  4899.4  257.83  4905.7  238.35  4907.2  236.35
  5073.1  238.35  5079.5  258.24  5110.1  257.45  5855.9  256.07  6094.8  256.39
  6366.5  249.22  6498.9  264.54  7358.5  262.03  7987.3  252.06  8113.5  257.94
  9829.4  258.96 10132.2  258.94   10334  258.29 10909.1  261.43 11133.1  264.97
 11923.2  300.42 12218.4  301.44 12564.3  296.47 12690.2  301.59 12833.8  311.72
#Mann= 20 ,-1 , 0
    1590     .07       0  2034.6     .12       0  3228.9     .12       0
  3430.2     .07       0  4905.7     .05       0  5073.1     .12       0
  5110.1     .12       0  5855.9    .035       0  6094.8     .12       0
  7358.5     .12       0  8113.5     .05       0  9829.4    .035       0
 10132.2    .035       0   10334     .05       0 10909.1     .05       0
 11133.1     .07       0 11923.2     .07       0 12218.4    .035       0
 12564.3    .035       0 12690.2     .05       0
Bank Sta=4905.7,5073.1
XS Rating Curve= 0 ,0
Exp/Cntr=0.3,0.1

Type RM Length L Ch R = 1 ,70945   ,2893,2893,2893
BEGIN DESCRIPTION:
B19938
END DESCRIPTION:
XS GIS Cut Line= 3
       2511512.4     13744653.41      2505748.52     13744306.19
      2499672.13     13747396.47
#Sta/Elev= 30
   153.8  298.36   708.3  264.61  1195.9  260.93  1379.8  260.83  1556.4  260.18
  1755.5  260.03  2376.3  256.28  2652.8  267.45  3456.9  259.21  3819.3  257.13
    3918  250.05  3948.1  255.06  4870.8  255.98  4926.3  237.48  4927.8  235.48
  5093.7  237.48  5197.4   254.9  5336.4  253.49  5608.5  253.71    6775  255.43
  7706.2  254.03  8060.4  254.34  8438.6  255.26  9800.9  255.79 10515.5  257.55
 10926.9  255.37 11530.3  265.84 11955.6   287.6 12444.4  309.34 12745.2  305.67
#Mann= 20 ,-1 , 0
   153.8     .12       0  1195.9     .07       0  1379.8     .12       0
  1556.4     .07       0  1755.5     .12       0  2652.8     .07       0
  3456.9     .07       0  3819.3     .12       0  4926.3     .05       0
  5093.7     .12       0  5336.4     .07       0  5608.5     .12       0
    6775     .07       0  7706.2     .12       0  8060.4     .07       0
  8438.6     .12       0  9800.9    .045       0 10515.5     .12       0
 10926.9     .05       0 11955.6     .07       0
Bank Sta=4926.3,5093.7
XS Rating Curve= 0 ,0
Exp/Cntr=0.3,0.1

Type RM Length L Ch R = 1 ,68052   ,2756,2756,2756
BEGIN DESCRIPTION:
PEACH CREEK 25.0
END DESCRIPTION:
XS GIS Cut Line= 3
      2511269.33     13744375.62      2506998.52      13742292.3
      2502311.07      13742604.8
#Sta/Elev= 30
   -77.4  334.81   -37.7   333.2    69.4  297.08   194.4  273.53    1073  253.45
    2261  251.33  2534.4  251.36  3126.5  251.26  4585.8  252.07  4715.8  252.36
  4928.5  254.87    4935  236.91  4936.5  234.91  5102.5  236.91  5108.9  254.48
  5401.8  252.75  5569.8  250.36  5820.5  245.49  6049.1  252.65  6582.1  253.51
  6762.6  253.42  6802.7  240.81  6866.6  254.06  7041.9  260.63  7241.8  271.23
  7904.3  275.92  8055.5  277.57  8603.6  275.73  9295.6  293.83  9372.3  295.33
#Mann= 20 ,-1 , 0
   -77.4     .12       0    1073     .07       0    2261     .12       0
  2534.4     .07       0  3126.5     .07       0  4585.8     .12       0
  4715.8     .05       0    4935     .05       0  5102.5     .12       0
  5401.8     .12       0  5569.8     .07       0  6049.1     .07       0
  6582.1      .1       0  6866.6     .07       0  7041.9     .05       0
  7241.8     .07       0  7904.3     .05       0  8055.5     .07       0
  8603.6     .05       0  9295.6     .07       0
Bank Sta=4935,5102.5
XS Rating Curve= 0 ,0
Exp/Cntr=0.3,0.1

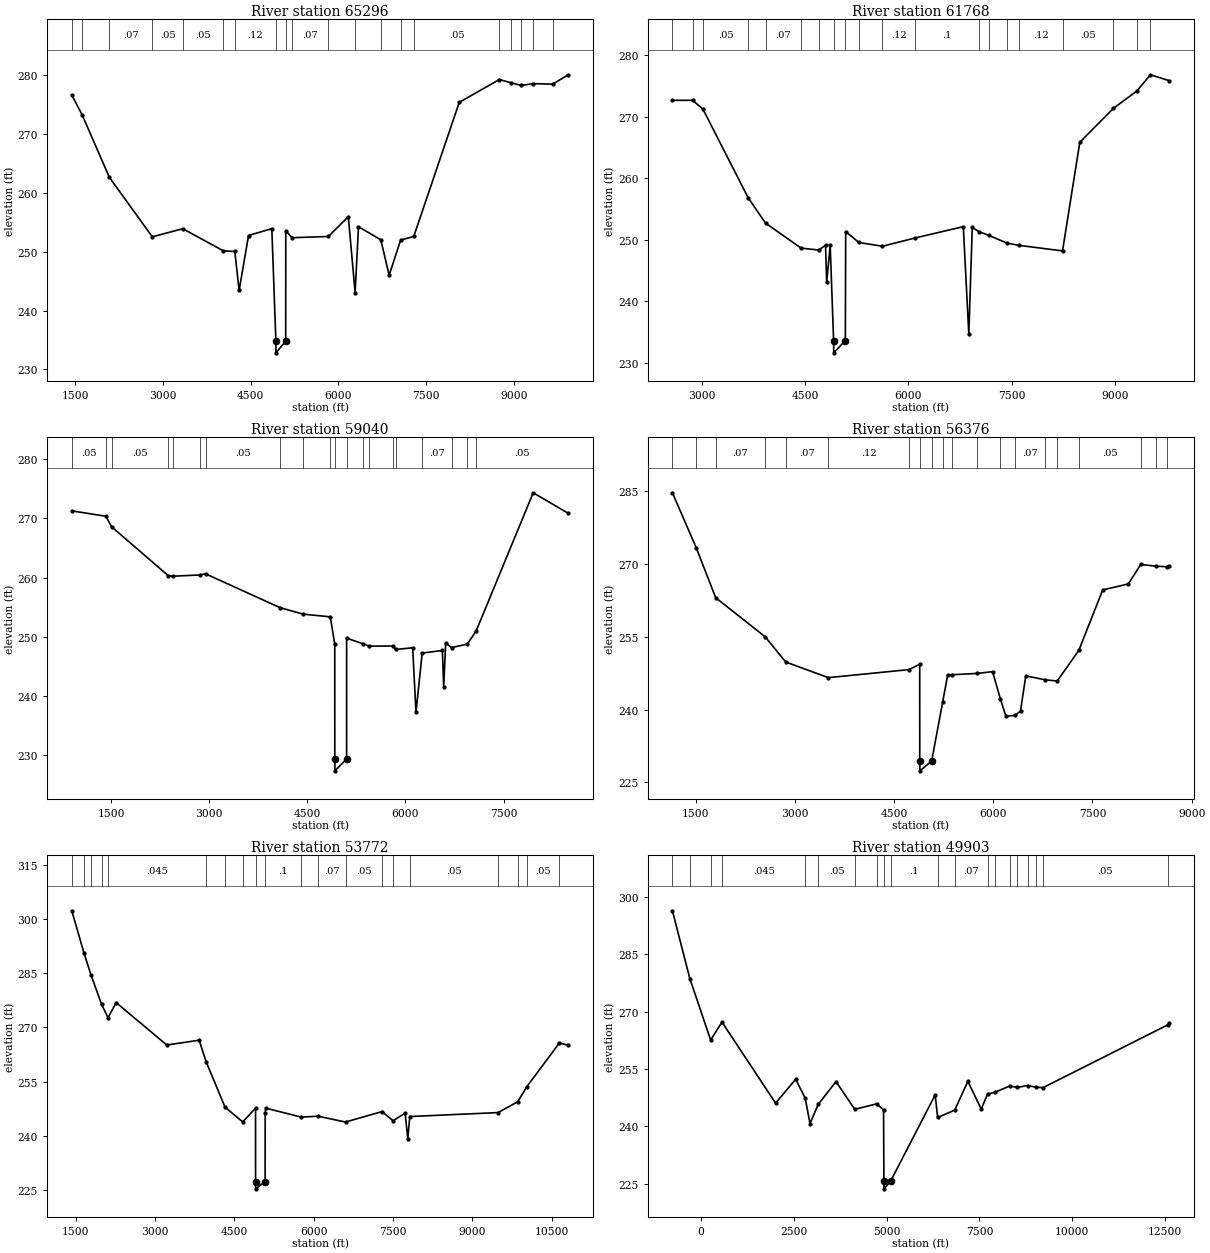
Type RM Length L Ch R = 1 ,65296   ,3528,3528,3528
BEGIN DESCRIPTION:
PEACH CREEK 24.0
END DESCRIPTION:
XS GIS Cut Line= 3
      2510436.06      13740729.8      2506790.19     13740452.02
      2502068.97     13741458.75
#Sta/Elev= 30
  1444.4  276.63  1620.4  273.31  2084.7  262.68  2820.6  252.54  3340.1  253.92
  4035.4  250.15  4230.1  250.05  4303.7  243.42  4464.2  252.76  4862.2  253.94
    4932  234.81  4933.5  232.81  5099.5  234.81  5100.8  253.61  5204.7  252.39
  5828.8   252.6  6169.5  255.96  6285.8  243.06  6343.3  254.26  6724.4  252.04
  6867.6  246.02  7063.4  251.99  7287.8   252.6  8065.2  275.41    8750  279.29
  8942.9  278.77  9124.8  278.28  9323.5  278.59  9661.5  278.51  9928.2   280.1
#Mann= 20 ,-1 , 0
  1444.4     .12       0  1620.4     .07       0  2084.7     .07       0
  2820.6     .05       0  3340.1     .05       0  4035.4     .12       0
  4230.1     .12       0    4932     .05       0  5099.5      .1       0
  5204.7     .07       0  5828.8     .12       0  6285.8     .05       0
  6724.4     .12       0  7063.4     .07       0  7287.8     .05       0
    8750     .05       0  8942.9     .07       0  9124.8     .05       0
  9323.5     .07       0  9661.5    .035       0
Bank Sta=4932,5099.5
XS Rating Curve= 0 ,0
Exp/Cntr=0.3,0.1

Type RM Length L Ch R = 1 ,61768   ,2728,2728,2728
BEGIN DESCRIPTION:
PEACH CREEK 23.0
END DESCRIPTION:
XS GIS Cut Line= 3
       2508838.8     13737222.85      2505679.08      13738854.8
      2502033.24     13738958.96
#Sta/Elev= 30
    2577  272.64  2869.1  272.65  3019.3  271.23  3676.3  256.79  3928.1  252.68
  4444.1  248.61  4699.9   248.3  4798.8  249.07  4815.4  243.09  4866.1  249.04
    4916  233.58  4917.5  231.58  5086.2  233.58  5091.2  251.31    5282  249.53
  5623.9  248.91  6093.6  250.25  6797.6   252.1  6877.7  234.62  6927.7  251.97
  7024.2  251.29  7170.7  250.67  7435.3  249.41  7612.5  249.05  8237.5  248.16
  8488.3  265.83  8976.2  271.34    9316  274.16  9513.1   276.8  9780.6  275.86
#Mann= 20 ,-1 , 0
    2577     .05       0  2869.1    .035       0  3019.3     .05       0
  3676.3     .07       0  3928.1     .07       0  4444.1     .12       0
  4699.9      .1       0    4916     .05       0  5086.2      .1       0
    5282     .07       0  5623.9     .12       0  6093.6      .1       0
  7024.2     .07       0  7170.7     .05       0  7435.3     .07       0
  7612.5     .12       0  8237.5     .05       0  8976.2    .035       0
    9316     .05       0  9513.1    .035       0
Bank Sta=4916,5086.2
XS Rating Curve= 0 ,0
Exp/Cntr=0.3,0.1

Type RM Length L Ch R = 1 ,59040   ,2664,2664,2664
BEGIN DESCRIPTION:
B19937
END DESCRIPTION:
XS GIS Cut Line= 3
      2509151.27     13736910.35      2505609.64     13736528.41
      2501618.25     13737083.73
#Sta/Elev= 30
   898.3  271.26  1418.6  270.35  1507.3  268.57  2376.1  260.29    2448  260.23
  2852.3  260.44    2944  260.63  4085.3  254.91  4439.9  253.82  4851.1  253.37
  4919.5  248.74  4920.2  229.38  4921.7  227.38  5100.4  229.38  5101.2  249.78
    5346  248.84  5449.9  248.42  5803.9  248.45    5849  247.87  6110.8  248.15
  6161.3  237.25  6256.3  247.25  6565.2   247.7  6585.4  241.56  6615.7  248.95
  6705.6  248.19  6946.8  248.76  7083.7  251.04  7954.3  274.31  8490.3  270.84
#Mann= 20 ,-1 , 0
   898.3     .05       0  1418.6    .035       0  1507.3     .05       0
  2376.1     .07       0    2448     .05       0  2852.3     .07       0
    2944     .05       0  4085.3     .07       0  4439.9     .05       0
  4851.1     .07       0  4920.2     .05       0  5100.4     .07       0
    5346      .1       0  5449.9     .12       0  5803.9     .07       0
    5849     .12       0  6256.3     .07       0  6705.6     .12       0
  6946.8     .07       0  7083.7     .05       0
Bank Sta=4920.2,5100.4
XS Rating Curve= 0 ,0
Exp/Cntr=0.3,0.1

Type RM Length L Ch R = 1 ,56376   ,2604,2604,2604
BEGIN DESCRIPTION:
PEACH CREEK 22.0
END DESCRIPTION:
XS GIS Cut Line= 3
      2508456.87     13734202.02      2503699.91      13734792.3
      2501478.83       13736354.
#Sta/Elev= 30
  1146.8  284.61  1505.9  273.32  1801.7  263.01  2549.1  254.98  2860.1  249.78
  3505.3  246.56  4727.2  248.22  4887.1  249.33  4887.7  229.38  4889.2  227.38
  5067.9  229.38  5233.1  241.47  5310.4  247.13  5379.8  247.16  5752.6  247.43
  5988.7  247.79  6107.6  242.15  6190.7  238.61  6326.7  238.78  6411.3  239.68
  6491.4  246.93  6781.8  246.12  6966.8  245.87  7293.3  252.18  7654.5  264.61
  8041.3  265.84  8230.8  269.86  8465.9  269.49  8630.4  269.39  8655.4  269.48
#Mann= 20 ,-1 , 0
  1146.8     .07       0  1505.9     .12       0  1801.7     .07       0
  2549.1     .05       0  2860.1     .07       0  3505.3     .12       0
  4727.2      .1       0  4887.7     .05       0  5067.9      .1       0
  5233.1     .07       0  5379.8     .07       0  5752.6     .12       0
  6107.6    .033       0  6326.7     .07       0  6781.8     .07       0
  6966.8     .12       0  7293.3     .05       0  8230.8     .07       0
  8465.9    .035       0  8630.4     .05       0
Bank Sta=4887.7,5067.9
XS Rating Curve= 0 ,0
Exp/Cntr=0.3,0.1

Type RM Length L Ch R = 1 ,53772   ,3869,3869,3869
BEGIN DESCRIPTION:
PEACH CREEK 21.0
END DESCRIPTION:
XS GIS Cut Line= 4
      2509331.71     13732985.46      2505898.79     13732635.72
      2502962.67     13733227.88      2501353.89     13735696.15
#Sta/Elev= 30
  1422.9  302.25    1652  290.63  1788.4   284.4  1985.8   276.4  2107.2   272.7
  2262.5  276.86  3218.9  265.15    3832  266.46  3963.9  260.53  4321.1  247.97
  4657.1  243.87  4899.1  247.72  4899.6  227.38  4901.1  225.38  5079.8  227.38
  5081.5  246.44  5091.7  247.69  5763.7  245.21  6077.7  245.46  6600.9  243.85
  7290.9  246.73  7500.8   244.2  7728.3  246.32  7779.1  239.27  7817.1  245.37
  9487.5  246.46  9859.5  249.46 10030.4  253.61 10647.6  265.71 10815.1  265.05
#Mann= 20 ,-1 , 0
  1422.9     .05       0    1652    .035       0  1788.4     .05       0
  1985.8     .12       0  2107.2    .045       0  3963.9     .07       0
  4321.1     .12       0  4657.1      .1       0  4899.6     .05       0
  5079.8      .1       0  5763.7     .12       0  6077.7     .07       0
  6600.9     .05       0  7290.9     .07       0  7500.8     .12       0
  7817.1     .05       0  9487.5     .07       0  9859.5     .05       0
 10030.4     .05       0 10647.6     .05       0
Bank Sta=4899.6,5079.8
XS Rating Curve= 0 ,0
Exp/Cntr=0.3,0.1

Type RM Length L Ch R = 1 ,49903   ,3164,3164,3164
BEGIN DESCRIPTION:
PEACH CREEK 20.0
END DESCRIPTION:
XS GIS Cut Line= 4
       2509596.2     13732368.39      2506422.68     13731244.44
      2502610.06     13731244.44      2498290.56     13735674.13
#Sta/Elev= 30
  -764.8  296.36  -295.8  278.63   264.7  262.55   570.5  267.24  2013.4  246.05
  2553.5   252.3  2810.8  247.34  2939.6  240.72  3158.8   245.7  3639.6   251.7
  4143.3  244.44    4734  245.86  4919.6  244.29  4929.5  225.64    4931  223.64
  5109.7  225.64  6309.6  248.21  6375.8   242.3    6835  244.22  7189.3  251.75
  7549.9   244.5  7719.2  248.42  7907.8  248.86  8317.4  250.53  8525.2  250.18
  8800.6  250.66  9028.9  250.21  9212.4   250.1 12564.9  266.49 12601.6  266.91
#Mann= 20 ,-1 , 0
  -764.8     .05       0  -295.8    .035       0   264.7     .05       0
   570.5    .045       0  2810.8     .07       0  3158.8     .05       0
  4143.3     .07       0    4734    .035       0  4929.5     .05       0
  5109.7      .1       0  6375.8     .12       0    6835     .07       0
  7719.2     .07       0  7907.8     .05       0  8317.4     .07       0
  8525.2     .05       0  8800.6     .12       0  9028.9     .07       0
  9212.4     .05       0 12564.9     .07       0
Bank Sta=4929.5,5109.7
XS Rating Curve= 0 ,0
Exp/Cntr=0.3,0.1

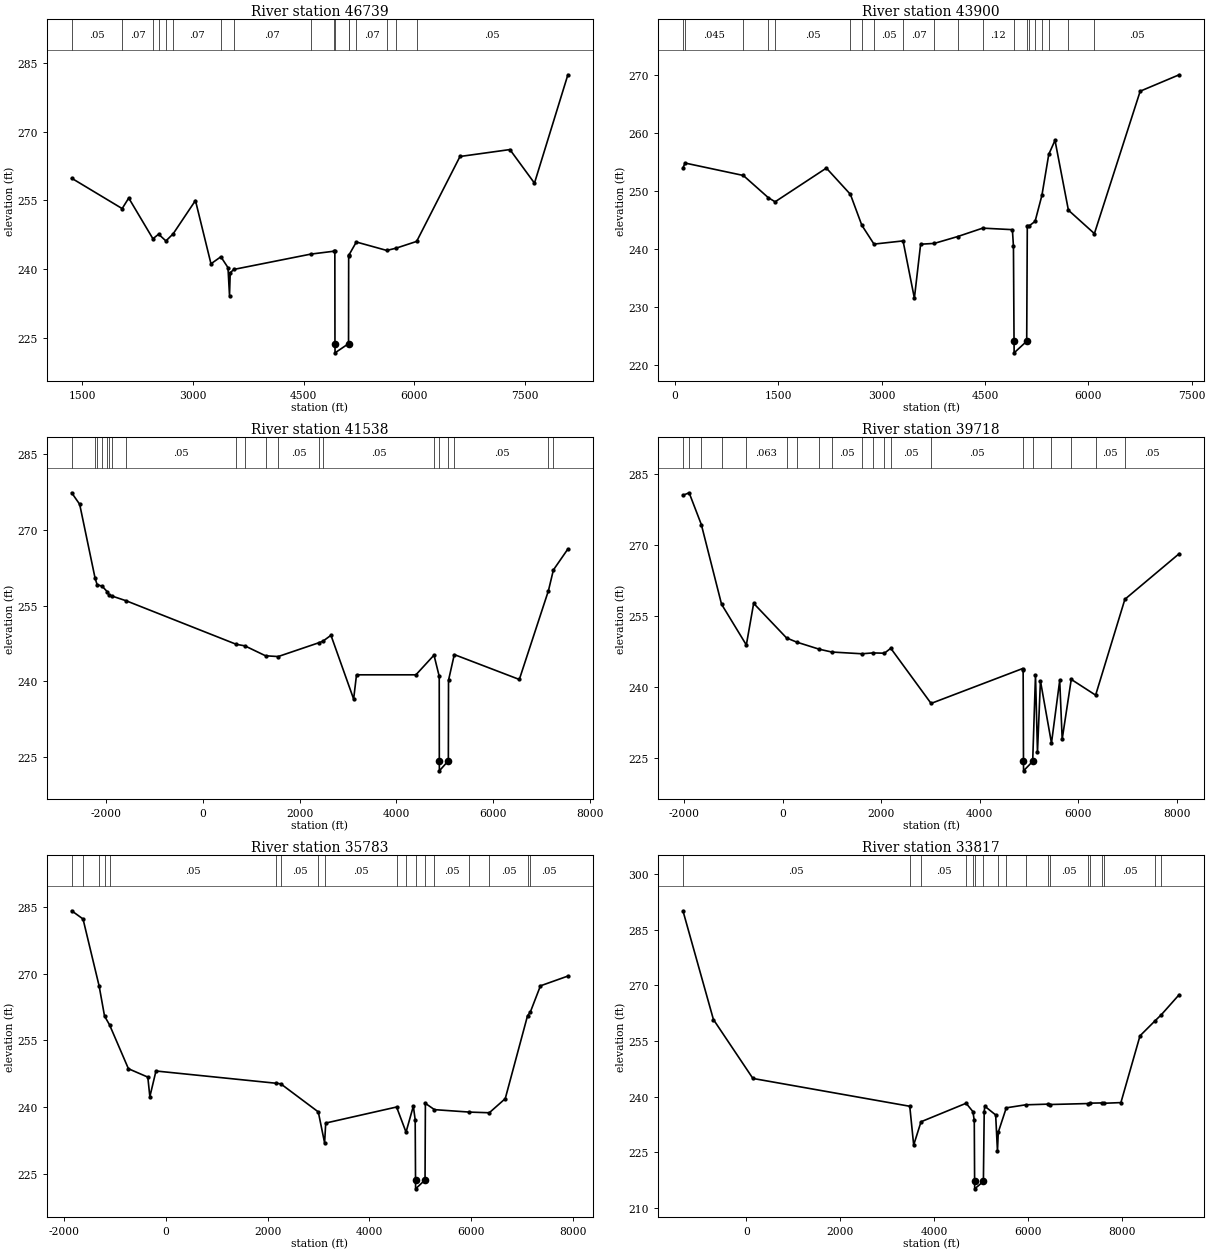
Type RM Length L Ch R = 1 ,46739   ,2839,2839,2839
BEGIN DESCRIPTION:
PEACH CREEK 19.0
END DESCRIPTION:
XS GIS Cut Line= 3
       2507899.2     13728710.04      2504483.31     13728886.34
      2501309.87     13727982.79
#Sta/Elev= 30
  1357.5  259.84  2041.4  253.22  2130.2  255.52    2458  246.64  2535.1  247.64
  2633.8  246.16  2732.5  247.73  3033.9  254.98  3244.2  241.18  3378.2  242.71
  3474.5  240.34  3495.2  234.26  3504.6  239.21  3552.8  239.95  4595.7  243.29
    4908  243.92  4921.7  244.06  4923.2  223.76  4924.7  221.76  5107.1  223.76
  5108.9  242.94  5111.1  243.05  5212.7  245.93  5625.1  244.09  5751.7  244.59
  6029.4  246.06  6616.5  264.58  7292.4  266.09  7625.1  258.77  8077.5   282.4
#Mann= 17 ,-1 , 0
  1357.5     .05       0  2041.4     .07       0    2458     .12       0
  2535.1     .07       0  2633.8     .12       0  2732.5     .07       0
  3378.2     .12       0  3552.8     .07       0  4595.7     .12       0
    4908      .1       0  4923.2     .05       0  5107.1      .1       0
  5111.1     .12       0  5212.7     .07       0  5625.1     .12       0
  5751.7     .07       0  6029.4     .05       0
Bank Sta=4923.2,5107.1
XS Rating Curve= 0 ,0
Exp/Cntr=0.3,0.1

Type RM Length L Ch R = 1 ,43900   ,2362,2362,2362
BEGIN DESCRIPTION:
PEACH CREEK 18.0
END DESCRIPTION:
XS GIS Cut Line= 3
      2508714.69     13726109.52      2504725.73     13726550.29
      2501552.24     13726880.86
#Sta/Elev= 30
     115  254.01   145.3  254.86     991  252.72  1353.5   248.9  1452.9  248.18
  2197.3  253.99  2545.8  249.47  2711.9  244.14  2888.6  240.89  3310.5  241.44
    3475  231.57  3565.6  240.87  3763.8  241.01  4103.3  242.19  4466.3  243.64
  4897.8  243.38  4913.2  240.52  4921.8  224.15  4923.3  222.15  5105.7  224.15
  5114.3  244.09  5143.7  244.05  5227.5  244.81  5326.8  249.31    5426  256.36
  5516.4  258.77    5711  246.74  6088.4   242.7  6753.1  267.24  7318.9  270.07
#Mann= 20 ,-1 , 0
     115     .05       0   145.3    .045       0     991     .05       0
  1353.5    .035       0  1452.9     .05       0  2545.8     .07       0
  2711.9     .12       0  2888.6     .05       0  3310.5     .07       0
  3763.8     .05       0  4103.3     .07       0  4466.3     .12       0
  4921.8     .05       0  5105.7      .1       0  5143.7     .07       0
  5227.5     .05       0  5326.8     .07       0    5426     .05       0
    5711     .07       0  6088.4     .05       0
Bank Sta=4921.8,5105.7
XS Rating Curve= 0 ,0
Exp/Cntr=0.3,0.1

Type RM Length L Ch R = 1 ,41538   ,1820,1820,1820
BEGIN DESCRIPTION:
B19936
END DESCRIPTION:
XS GIS Cut Line= 3
      2511535.56     13722389.47      2503557.71     13724901.83
      2501706.47     13725320.56
#Sta/Elev= 30
 -2717.1  277.35 -2551.4  275.07 -2233.1  260.45 -2190.9  259.15 -2086.7  258.84
 -1982.6  257.77 -1943.4   257.1 -1878.4  256.88   -1588  255.95     688  247.33
   864.2  247.03  1292.4  245.06  1553.4  244.91    2403  247.67  2480.5  247.96
  2645.4  249.12  3114.3  236.49  3173.8  241.29  4402.2  241.29  4776.2  245.19
  4884.5  240.98  4886.2  224.27  4887.7  222.27    5073  224.27  5076.7  240.21
    5196   245.3  6540.9  240.37  7143.9  257.99  7245.5  262.06    7545  266.21
#Mann= 20 ,-1 , 0
 -2717.1     .07       0 -2233.1     .12       0 -2190.9     .07       0
 -2086.7     .12       0 -1982.6     .07       0 -1943.4     .12       0
 -1878.4     .07       0   -1588     .05       0     688     .07       0
   864.2     .05       0  1292.4     .12       0  1553.4     .05       0
    2403    .035       0  2480.5     .05       0  4776.2     .07       0
  4886.2     .05       0    5073     .07       0    5196     .05       0
  7143.9    .035       0  7245.5     .05       0
Bank Sta=4886.2,5073
XS Rating Curve= 0 ,0
Exp/Cntr=0.3,0.1

Type RM Length L Ch R = 1 ,39718   ,3935,3935,3935
BEGIN DESCRIPTION:
B19935
END DESCRIPTION:
XS GIS Cut Line= 3
      2510830.37     13721441.81      2504262.93     13723028.58
       2500958.6     13723292.92
#Sta/Elev= 30
 -2020.9  280.41 -1895.1  280.94 -1647.5  274.22 -1237.5   257.4  -734.2  248.79
  -585.7  257.58    81.6  250.28   285.6   249.4   746.4  247.89   999.4   247.3
  1611.2  246.93  1833.8  247.11  2068.5  247.05  2197.3  248.09  3015.4  236.44
  4873.8  243.81  4883.9  243.56  4890.8   224.2  4892.3   222.2  5077.6   224.2
  5134.7  242.47  5174.8  226.13    5235   241.2    5459  228.06  5626.2   241.3
  5676.4  228.89  5860.1  241.52    6355  238.19  6948.9  258.44  8050.4  268.07
#Mann= 20 ,-1 , 0
 -2020.9    .035       0 -1895.1     .07       0 -1647.5     .07       0
 -1237.5    .035       0  -734.2    .063       0    81.6    .035       0
   285.6    .035       0   746.4     .05       0   999.4     .05       0
  1611.2     .07       0  1833.8     .05       0  2068.5    .035       0
  2197.3     .05       0  3015.4     .05       0  4890.8     .05       0
  5077.6      .1       0    5459     .12       0  5860.1     .07       0
    6355     .05       0  6948.9     .05       0
Bank Sta=4890.8,5077.6
XS Rating Curve= 0 ,0
Exp/Cntr=0.3,0.1

Type RM Length L Ch R = 1 ,35783   ,1966,1966,1966
BEGIN DESCRIPTION:
B19934
END DESCRIPTION:
XS GIS Cut Line= 3
      2510257.36     13720494.18       2503205.1     13721111.25
       2500979.6      13722609.6
#Sta/Elev= 30
 -1858.4  284.08 -1634.9  282.24 -1317.7  267.18 -1211.9  260.46 -1112.8  258.48
  -741.8  248.64  -360.3  246.76  -320.2  242.37  -199.7  248.13  2156.3  245.39
  2255.4  245.25  2993.7  238.95  3117.8  231.99  3139.7  236.45  4533.9  240.05
  4719.6  234.41  4863.4  240.24  4899.7   237.2  4906.6  223.69  4908.1  221.69
  5093.6  223.69  5100.5  240.87    5279  239.46  5967.8  238.91  6357.7  238.76
  6671.3  241.92  7109.8  260.52  7164.4  261.34    7364  267.24  7903.7  269.43
#Mann= 18 ,-1 , 0
 -1858.4     .05       0 -1634.9     .07       0 -1317.7     .05       0
 -1211.9    .035       0 -1112.8     .05       0  2156.3    .035       0
  2255.4     .05       0  2993.7     .07       0  3117.8     .05       0
  4533.9     .07       0  4719.6      .1       0  4906.6     .05       0
  5093.6      .1       0    5279     .05       0  5967.8     .07       0
  6357.7     .05       0  7109.8    .035       0  7164.4     .05       0
Bank Sta=4906.6,5093.6
XS Rating Curve= 0 ,0
Exp/Cntr=0.3,0.1

Type RM Length L Ch R = 1 ,33817   ,2271,2271,2271
BEGIN DESCRIPTION:
B19933
END DESCRIPTION:
XS GIS Cut Line= 3
      2510059.04     13718687.04      2502808.41     13719634.69
       2501067.4     13722389.45
#Sta/Elev= 30
 -1352.1  290.05  -702.6  260.77   138.2  244.91  3479.9  237.42  3563.4  226.99
    3720  233.25  4680.6  238.23  4825.4  235.98  4854.3  233.59  4861.6  217.19
  4863.1  215.19  5048.6  217.19  5066.1  236.01  5078.2  237.43  5309.9  235.09
  5348.4  225.34  5365.5  230.43  5536.2     237  5948.2  237.81  6423.4  237.99
  6464.1  237.89  7268.8  238.15  7324.1  238.26  7571.3  238.32    7626  238.23
  7978.1  238.41  8385.1  256.39  8709.2  260.47  8838.2  262.05    9219  267.46
#Mann= 18 ,-1 , 0
 -1352.1     .05       0  3479.9     .07       0    3720     .05       0
  4680.6     .07       0  4825.4      .1       0  4861.6     .05       0
  5048.6      .1       0  5365.5     .12       0  5536.2     .07       0
  5948.2     .05       0  6423.4     .07       0  6464.1     .05       0
  7268.8    .035       0  7324.1     .05       0  7571.3    .035       0
    7626     .05       0  8709.2    .035       0  8838.2     .05       0
Bank Sta=4861.6,5048.6
XS Rating Curve= 0 ,0
Exp/Cntr=0.3,0.1