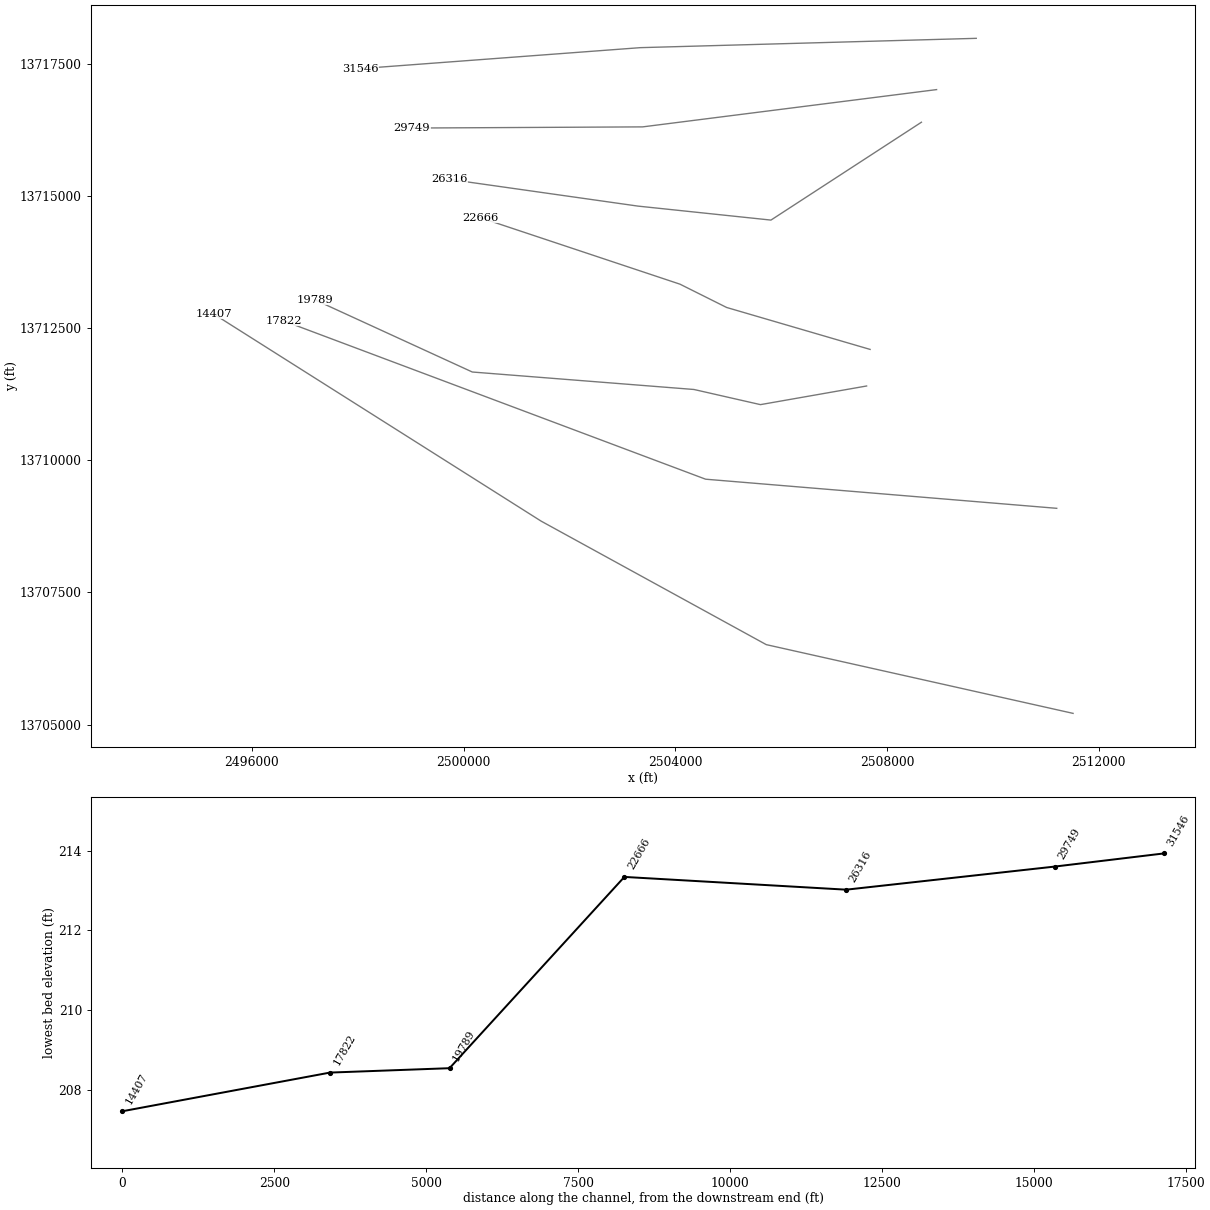
HEC-RAS study PEACH CREEK.prj: PEACH CREEK Base Level Engineering

--- PEACH CREEK.g01 (geometry) --- (continued)

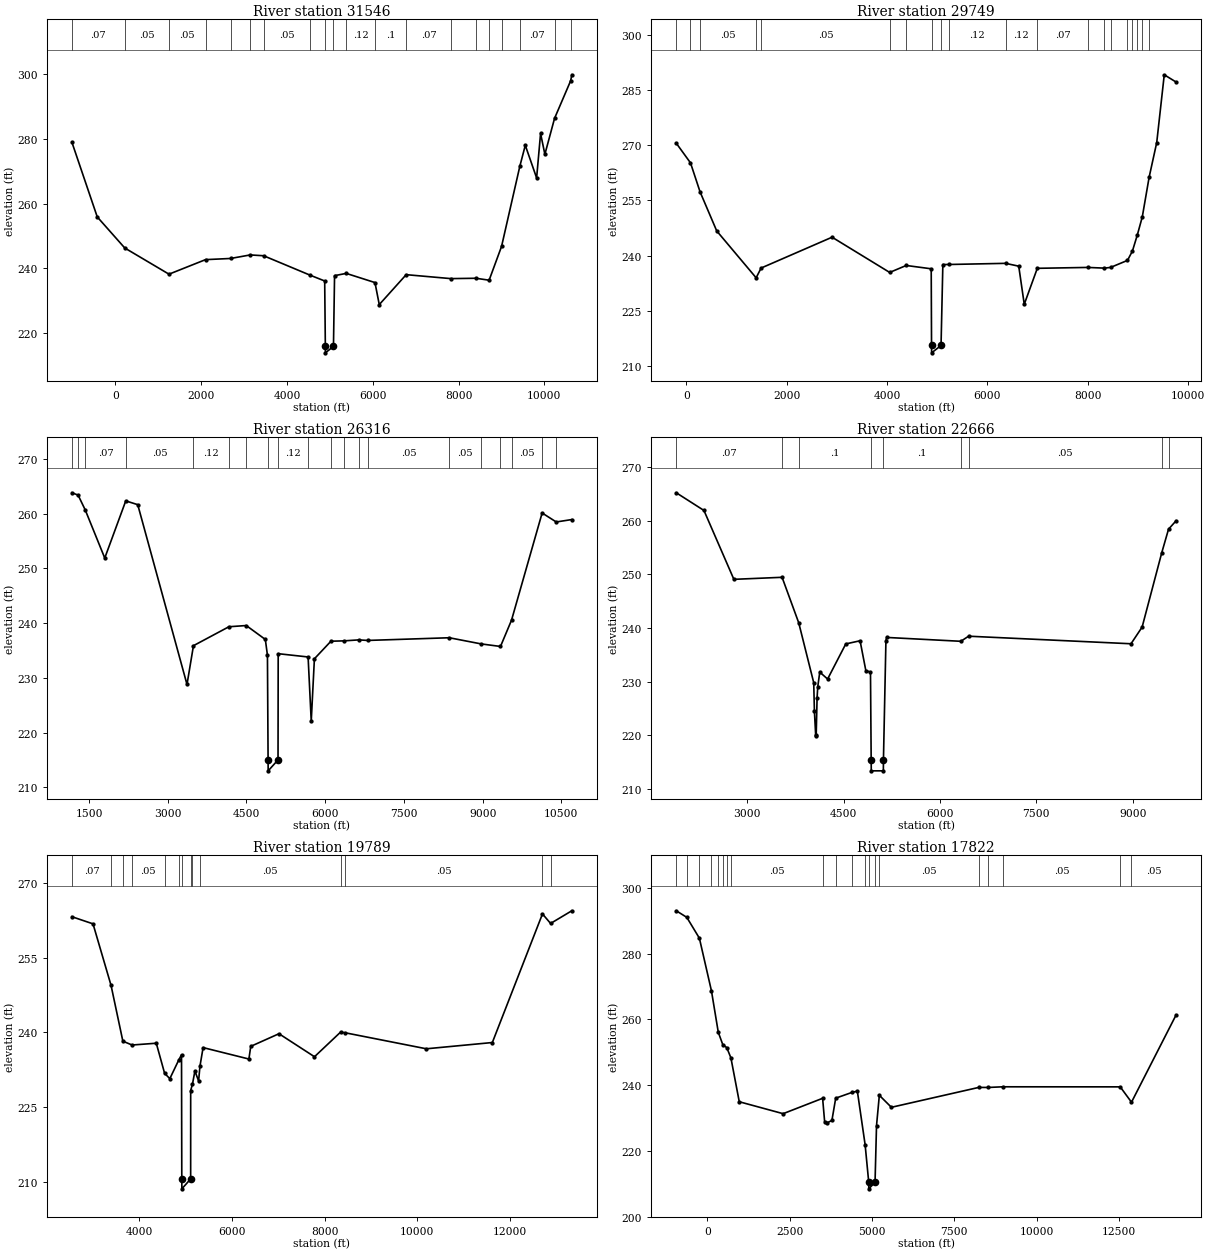
Type RM Length L Ch R = 1 ,31546   ,1797,1797,1797
BEGIN DESCRIPTION:
B19932
END DESCRIPTION:
XS GIS Cut Line= 3
       2509684.3     13717981.82      2503337.32     13717805.51
       2498049.1      13717408.9
#Sta/Elev= 30
 -1011.8  278.88  -422.3  255.88   219.2  246.29    1250  238.21  2102.3   242.7
  2686.1  243.06  3143.9  244.15  3456.1   243.9  4534.9  237.93  4879.8  236.11
  4895.2  215.93  4896.7  213.93  5084.5  215.93  5109.9  237.76  5382.9  238.45
    6052  235.62  6152.2  228.82  6779.7  238.06  7822.7  236.84    8407  236.95
  8713.3  236.35  9003.5  246.79  9429.5  271.54  9556.5  277.99  9820.6  267.91
  9912.8  281.65   10013  275.21 10238.4   286.3 10614.5  297.92 10640.7  299.76
#Mann= 20 ,-1 , 0
 -1011.8     .07       0   219.2     .05       0    1250     .05       0
  2102.3     .05       0  2686.1     .05       0  3143.9     .07       0
  3456.1     .05       0  4534.9     .12       0  4895.2     .05       0
  5084.5      .1       0  5382.9     .12       0    6052      .1       0
  6779.7     .07       0  7822.7     .12       0    8407     .07       0
  8713.3     .12       0  9003.5     .07       0  9429.5     .07       0
 10238.4     .05       0 10614.5     .05       0
Bank Sta=4895.2,5084.5
XS Rating Curve= 0 ,0
Exp/Cntr=0.3,0.1

Type RM Length L Ch R = 1 ,29749   ,3433,3433,3433
BEGIN DESCRIPTION:
B19931
END DESCRIPTION:
XS GIS Cut Line= 3
      2508935.07     13717012.14       2503381.4     13716306.91
      2499018.92     13716284.88
#Sta/Elev= 30
  -201.7  270.54    81.7   265.2   272.2  257.33   604.4  246.71  1389.8  233.98
  1488.7  236.63  2903.1  245.01  4051.3  235.44  4380.6  237.33  4878.8  236.43
  4885.2   215.6  4886.7   213.6  5074.6   215.6  5110.7  237.58  5235.8   237.6
  6360.3  237.91    6623  237.14    6733  226.79    6993  236.56  7998.5   236.8
  8331.4  236.61  8452.7   236.8  8790.1  238.71  8888.6  241.25    8987  245.65
  9085.4  250.54  9221.8  261.32    9373  270.73    9523  289.13  9759.1  287.15
#Mann= 20 ,-1 , 0
  -201.7     .07       0    81.7     .05       0   272.2     .05       0
  1389.8     .12       0  1488.7     .05       0  4051.3     .07       0
  4380.6     .12       0  4885.2     .05       0  5074.6      .1       0
  5235.8     .12       0  6360.3     .12       0    6993     .07       0
  7998.5     .05       0  8331.4     .07       0  8452.7     .05       0
  8790.1     .12       0  8888.6     .07       0    8987     .12       0
  9085.4     .05       0  9221.8     .05       0
Bank Sta=4885.2,5074.6
XS Rating Curve= 0 ,0
Exp/Cntr=0.3,0.1

Type RM Length L Ch R = 1 ,26316   ,3650,3650,3650
BEGIN DESCRIPTION:
B19930
END DESCRIPTION:
XS GIS Cut Line= 4
       2508648.5     13716395.04      2505805.61     13714543.85
      2503293.25     13714808.31      2499723.07     13715315.19
#Sta/Elev= 30
  1174.5  263.79  1290.8  263.37  1427.7  260.65  1799.2  251.87  2199.6  262.31
  2427.8  261.62  3366.5  228.79  3489.5  235.87  4165.1  239.33  4495.8  239.55
  4859.2  237.01  4899.4  234.13  4911.7  215.02  4913.2  213.02  5101.1  215.02
  5104.4  234.41  5674.2  233.81    5734  222.09  5794.3  233.48  6109.7  236.69
  6354.2  236.75  6638.9  236.93  6810.5  236.83  8365.2  237.32  8974.6  236.19
  9340.4  235.73  9550.7  240.53 10133.9   260.1 10402.7  258.46 10699.2   258.9
#Mann= 20 ,-1 , 0
  1174.5     .05       0  1290.8     .05       0  1427.7     .07       0
  2199.6     .05       0  3489.5     .12       0  4165.1     .07       0
  4495.8     .07       0  4911.7     .05       0  5101.1     .12       0
  5674.2      .1       0  6109.7     .07       0  6354.2     .07       0
  6638.9     .07       0  6810.5     .05       0  8365.2     .05       0
  8974.6     .07       0  9340.4     .07       0  9550.7     .05       0
 10133.9     .05       0 10402.7     .05       0
Bank Sta=4911.7,5101.1
XS Rating Curve= 0 ,0
Exp/Cntr=0.3,0.1

Type RM Length L Ch R = 1 ,22666   ,2877,2877,2877
BEGIN DESCRIPTION:
B19929
END DESCRIPTION:
XS GIS Cut Line= 4
      2507678.85     13712097.61      2504968.16     13712890.98
      2504086.63     13713331.75      2500319.02     13714587.62
#Sta/Elev= 30
    1894  265.22  2324.9  261.92  2790.7  249.07  3541.1  249.45  3800.6  240.95
  4033.7  229.79  4044.4   224.5  4065.3  219.75  4072.3  220.05  4086.1  226.95
  4096.5  229.02  4127.8  231.76  4249.9  230.47  4532.9  237.02  4755.4  237.61
  4844.9  232.06  4917.5  231.75  4928.2  215.34  4929.7  213.34  5117.7  213.34
  5119.2  215.34  5157.9  237.62  5169.2  238.23  6324.4  237.51  6444.6  238.46
  8973.4  237.05  9146.3  240.16  9452.8  254.07  9557.5  258.43  9675.4     260
#Mann= 9 ,-1 , 0
    1894     .07       0  3541.1     .12       0  3800.6      .1       0
  4928.2     .05       0  5119.2      .1       0  6324.4     .07       0
  6444.6     .05       0  9452.8    .035       0  9557.5     .05       0
Bank Sta=4928.2,5119.2
XS Rating Curve= 0 ,0
Exp/Cntr=0.3,0.1

Type RM Length L Ch R = 1 ,19789   ,1967,1967,1967
BEGIN DESCRIPTION:
B19928
END DESCRIPTION:
XS GIS Cut Line= 5
      2507612.71      13711405.6      2505607.26     13711052.99
      2504351.08     13711339.49      2500163.82     13711670.06
      2497189.34     13713036.12
#Sta/Elev= 30
  2542.7  263.29  2997.3  261.86  3386.6  249.49  3642.2  238.25  3841.1  237.48
  4364.1  237.84  4544.1  231.78  4656.8  230.71    4848  234.43  4909.4  235.52
  4915.2  210.54  4916.7  208.54  5106.8  210.54  5107.3  228.32  5146.1  229.61
  5198.4  232.25  5278.7  230.25  5306.9  233.17  5375.5  236.96    6365  234.66
  6405.1  237.21  7014.7  239.75    7782  235.12  8344.9  240.07  8451.8  239.93
 10198.4  236.72 11624.2  237.98 12707.2  263.86 12882.7  261.94 13340.8  264.49
#Mann= 14 ,-1 , 0
  2542.7     .07       0  3386.6     .05       0  3642.2    .035       0
  3841.1     .05       0  4544.1     .07       0    4848      .1       0
  4915.2     .05       0  5106.8      .1       0  5146.1     .07       0
  5306.9     .05       0  8344.9    .035       0  8451.8     .05       0
 12707.2    .035       0 12882.7     .05       0
Bank Sta=4915.2,5106.8
XS Rating Curve= 0 ,0
Exp/Cntr=0.3,0.1

Type RM Length L Ch R = 1 ,17822   ,3415,3415,3415
BEGIN DESCRIPTION:
B19927
END DESCRIPTION:
XS GIS Cut Line= 3
      2511204.95     13709091.59      2504571.47     13709642.55
      2496593.63     13712639.74
#Sta/Elev= 30
  -940.5  293.04    -621  291.04  -238.8   284.7     128  268.65   335.2  256.07
   470.4  252.35   592.5  251.39   717.9  248.31   972.2  234.93  2303.9   231.3
  3503.4  235.98  3564.9  228.86  3635.7  228.49  3785.7  229.24  3900.8  236.02
  4394.5  237.77  4558.3  238.16  4794.2  221.86    4904  210.43  4905.5  208.43
  5095.6  210.43  5140.3  227.65    5226  236.89  5591.9  233.24  8244.8  239.29
  8537.6  239.28  8973.8  239.48 12541.2  239.46 12883.4  234.79 14238.1  261.35
#Mann= 20 ,-1 , 0
  -940.5     .05       0    -621     .07       0  -238.8     .05       0
     128     .05       0   335.2     .07       0   470.4     .05       0
   592.5    .035       0   717.9     .05       0  3503.4    .033       0
  3900.8     .05       0  4394.5     .07       0  4794.2      .1       0
    4904     .05       0  5095.6      .1       0    5226     .05       0
  8244.8    .035       0  8537.6     .05       0  8973.8     .05       0
 12541.2     .12       0 12883.4     .05       0
Bank Sta=4904,5095.6
XS Rating Curve= 0 ,0
Exp/Cntr=0.3,0.1

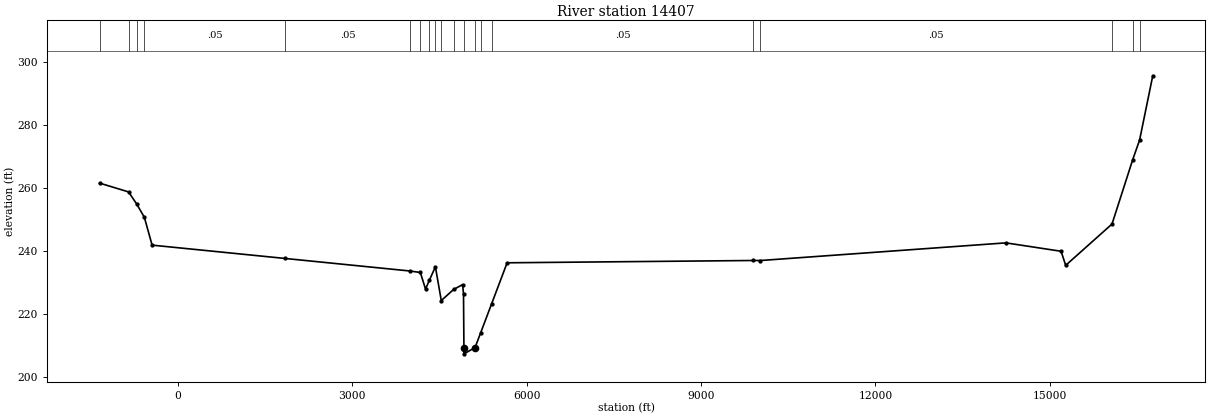
Type RM Length L Ch R = 1 ,14407   ,0,0,0
BEGIN DESCRIPTION:
B19926
END DESCRIPTION:
XS GIS Cut Line= 4
      2511513.51     13705212.86      2505717.46     13706513.11
      2501464.07     13708849.17      2495272.88     13712770.99
#Sta/Elev= 30
 -1348.5  261.52  -850.3  258.73    -712  254.93    -579   250.7  -445.5  241.88
  1844.3  237.66  3987.9   233.7    4170  233.22  4259.3  227.96  4327.4  230.85
    4429  235.03  4530.5  224.33  4742.1  227.84  4896.7  229.37  4912.8  226.46
  4920.1  209.46  4921.6  207.46  5112.1  209.46  5207.4   214.1  5398.3  223.39
  5663.2  236.29  9902.1  237.02 10020.8  237.01 14245.9   242.6 15195.9  239.94
 15274.7  235.48   16072  248.56   16428  268.93 16546.6  275.16 16773.1  295.51
#Mann= 20 ,-1 , 0
 -1348.5     .05       0  -850.3     .05       0    -712     .07       0
    -579     .05       0  1844.3     .05       0  3987.9     .07       0
    4170      .1       0  4327.4     .07       0    4429     .05       0
  4530.5     .07       0  4742.1      .1       0  4920.1     .05       0
  5112.1      .1       0  5207.4     .07       0  5398.3     .05       0
  9902.1    .035       0 10020.8     .05       0   16072     .12       0
   16428    .035       0 16546.6     .07       0
Bank Sta=4920.1,5112.1
XS Rating Curve= 0 ,0
Exp/Cntr=0.3,0.1

Chan Stop Cuts=-1
Use User Specified Reach Order=0
Composite Channel Slope=5