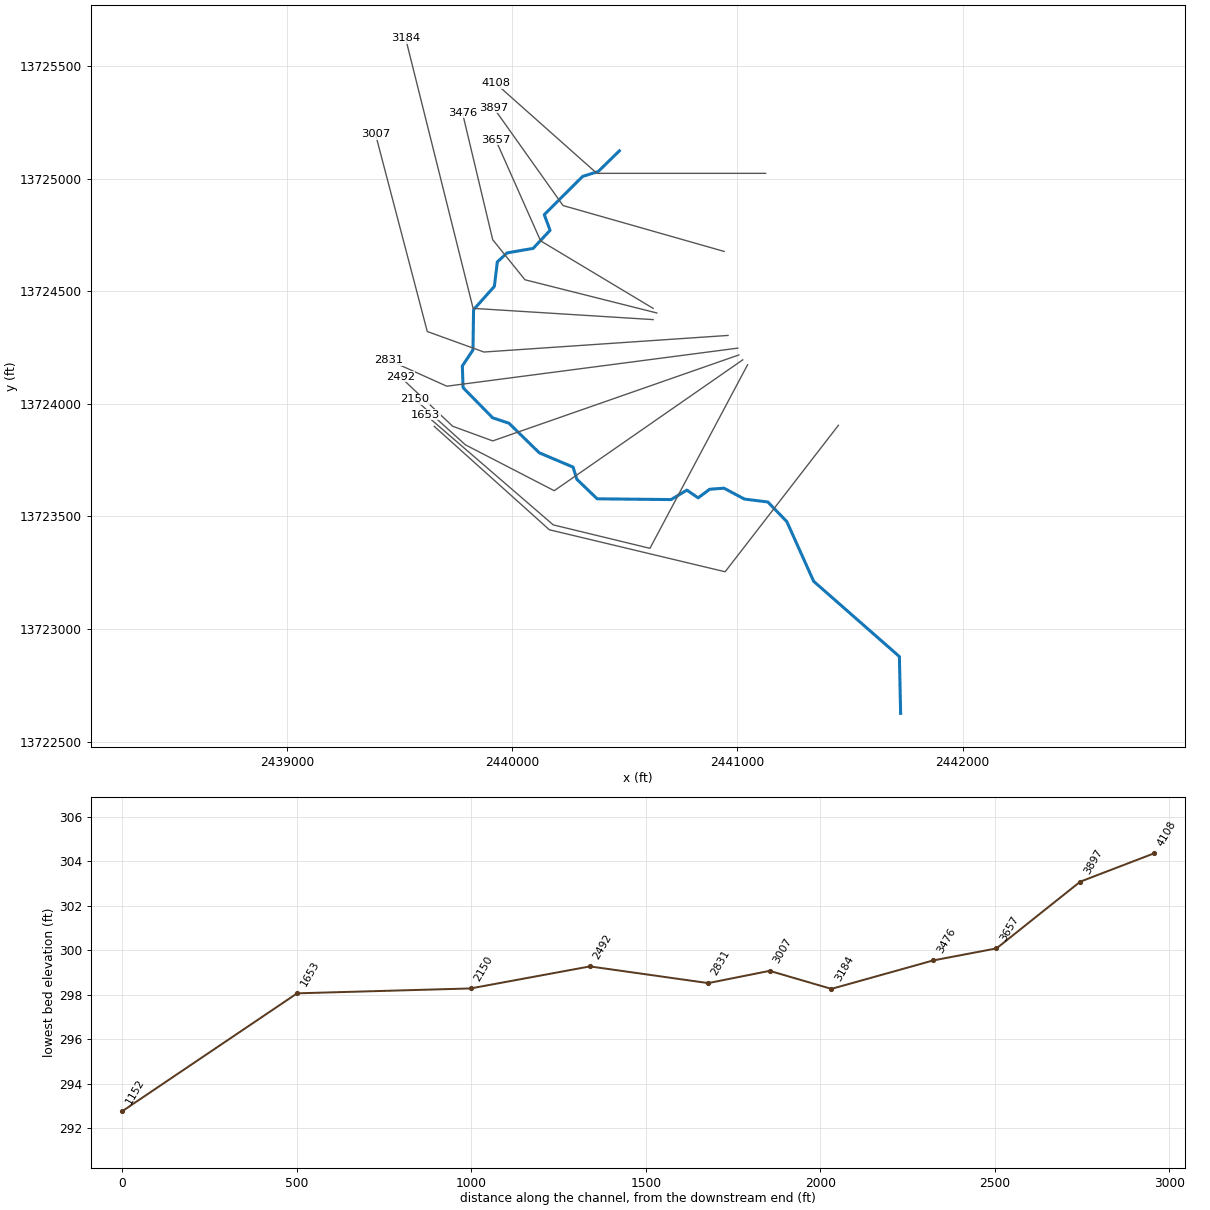
--- PECAN BRANCH TRIBUTARY 1.prj (project) ---

Proj Title=PECAN BRANCH TRIBUTARY 1 Base Level Engineering
Current Plan=p01
Default Exp/Contr=0.3,0.1
English Units
Geom File=g01
Flow File=f01
Plan File=p01
BEGIN DESCRIPTION:
PECAN BRANCH TRIBUTARY 1
END DESCRIPTION:

--- PECAN BRANCH TRIBUTARY 1.p01 (plan) ---

Plan Title=Multiple Run
Short Identifier=Multiple
Geom File=g01
Flow File=f01
Subcritical Flow
K Sum by GR= 0
Std Step Tol= 0.01
Critical Tol= 0.01
Num of Std Step Trials= 20
Max Error Tol= 0.3
Flow Tol Ratio= 0.001
Split Flow NTrial= 30
Split Flow Tol= 0.02
Split Flow Ratio= 0.02
Log Output Level= 0
Friction Slope Method= 1
Unsteady Friction Slope Method= 2
Unsteady Bridges Friction Slope Method= 1
Parabolic Critical Depth
Global Vel Dist=  1 , 1 , 1
Global Log Level= 0
CheckData=True
Encroach Param= -1, 0, 0, 0
BEGIN DESCRIPTION:
Multiple Run
END DESCRIPTION:

--- PECAN BRANCH TRIBUTARY 1.f01 (steady flow) ---

Flow Title=Multiple
Number of Profiles=7
Profile Names=10-year,25-year,50-year,1pct_min,100-year,1pct_plu,500-year
River Rch & RM= PECAN BRANCH TRI,Reach-1,4108
     781    1267    1709    1116    2227    4444    3743
Boundary for River Rch & Prof#=PECAN BRANCH TRI,Reach-1,1
Up Type=0
Dn Type=3
Dn Slope=0.005
Boundary for River Rch & Prof#=PECAN BRANCH TRI,Reach-1,2
Up Type=0
Dn Type=3
Dn Slope=0.005
Boundary for River Rch & Prof#=PECAN BRANCH TRI,Reach-1,3
Up Type=0
Dn Type=3
Dn Slope=0.005
Boundary for River Rch & Prof#=PECAN BRANCH TRI,Reach-1,4
Up Type=0
Dn Type=3
Dn Slope=0.005
Boundary for River Rch & Prof#=PECAN BRANCH TRI,Reach-1,5
Up Type=0
Dn Type=3
Dn Slope=0.005
Boundary for River Rch & Prof#=PECAN BRANCH TRI,Reach-1,6
Up Type=0
Dn Type=3
Dn Slope=0.005
Boundary for River Rch & Prof#=PECAN BRANCH TRI,Reach-1,7
Up Type=0
Dn Type=3
Dn Slope=0.005

--- PECAN BRANCH TRIBUTARY 1.g01 (geometry) ---

Geom Title=Existing Conditions

River Reach=PECAN BRANCH TRI,Reach-1
Reach XY= 30
      2440475.00     13725125.00      2440381.07     13725033.11
      2440311.79     13725011.37      2440141.39     13724841.67
      2440167.00     13724771.65      2440091.82     13724691.46
      2439976.25     13724671.49      2439932.73     13724631.50
      2439919.46     13724522.58      2439827.07     13724419.14
      2439824.48     13724240.22      2439777.16     13724169.02
      2439780.40     13724072.57      2439911.79     13723938.63
      2439984.68     13723914.22      2440118.95     13723783.14
      2440269.39     13723719.41      2440285.88     13723665.56
      2440376.45     13723578.53      2440705.02     13723575.18
      2440775.10     13723617.21      2440824.90     13723582.80
      2440876.50     13723621.07      2440940.06     13723625.70
      2441030.98     13723577.36      2441134.81     13723564.49
      2441219.17     13723477.31      2441338.62     13723211.79
      2441719.54     13722877.45      2441725.00     13722625.00

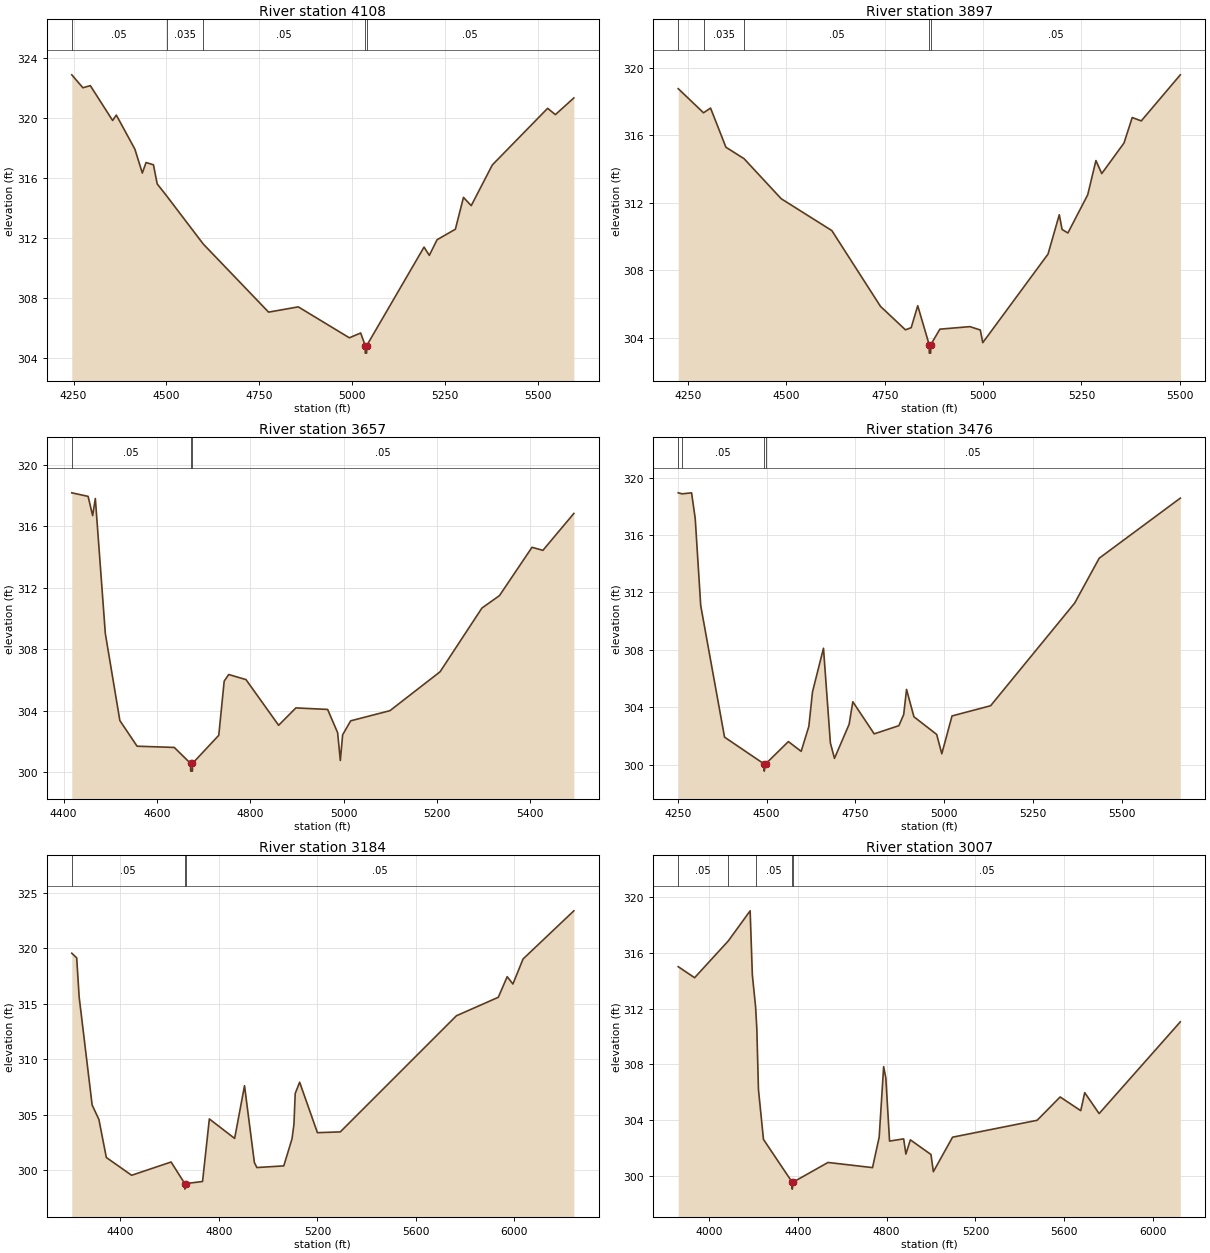
Type RM Length L Ch R = 1,4108,211,211,211
BEGIN DESCRIPTION:
PECAN BRANCH 3.0
END DESCRIPTION:
XS GIS Cut Line= 3
      2441124.96     13725025.00      2440375.00     13725025.00
      2439925.03     13725424.97
#Sta/Elev= 30
  4245.1  322.88  4275.1  322.02  4295.1  322.16  4355.1  319.84  4365.1  320.20
  4415.1  317.93  4435.1  316.34  4445.1  317.04  4465.1  316.89  4475.1  315.62
  4500.6  314.82  4599.0  311.62  4775.1  307.08  4855.1  307.43  4992.6  305.37
  5023.1  305.69  5035.3  304.85  5035.5  304.35  5039.0  304.35  5039.3  304.85
  5193.7  311.41  5207.9  310.86  5228.8  311.90  5278.1  312.60  5299.9  314.72
  5320.8  314.17  5377.6  316.88  5526.5  320.65  5547.4  320.23  5597.1  321.34
#Mann=5,-1,0
  4245.1    0.05       0  4500.6   0.035       0  4599.0    0.05       0
  5035.3    0.05       0  5039.3    0.05       0
Bank Sta=5035.3,5039.3
Exp/Cntr=0.3,0.1

Type RM Length L Ch R = 1,3897,240,240,240
BEGIN DESCRIPTION:
B20016
END DESCRIPTION:
XS GIS Cut Line= 3
      2440940.76     13724677.96      2440224.65     13724881.94
      2439916.49     13725315.98
#Sta/Elev= 30
  4224.7  318.75  4289.0  317.32  4306.9  317.60  4346.0  315.28  4392.2  314.60
  4486.5  312.23  4615.4  310.34  4739.1  305.85  4802.6  304.46  4817.2  304.59
  4833.8  305.89  4862.9  303.58  4863.2  303.08  4866.7  303.08  4867.0  303.58
  4890.1  304.50  4966.5  304.65  4993.0  304.45  4999.2  303.70  5165.2  308.95
  5193.8  311.28  5200.9  310.41  5215.7  310.20  5266.1  312.46  5287.0  314.49
  5301.8  313.72  5358.4  315.53  5379.3  317.04  5402.3  316.84  5501.6  319.57
#Mann=5,-1,0
  4224.7    0.05       0  4289.0   0.035       0  4392.2    0.05       0
  4862.9    0.05       0  4867.0    0.05       0
Bank Sta=4862.9,4867
Exp/Cntr=0.3,0.1

Type RM Length L Ch R = 1,3657,181,181,181
BEGIN DESCRIPTION:
PECAN BRANCH 2.0
END DESCRIPTION:
XS GIS Cut Line= 3
      2440625.00     13724425.00      2440125.00     13724725.00
      2439925.01     13725174.97
#Sta/Elev= 30
  4417.5  318.17  4452.5  317.94  4462.2  316.69  4468.0  317.80  4489.4  309.02
  4520.5  303.37  4557.4  301.70  4637.1  301.62  4672.0  300.58  4672.3  300.08
  4675.9  300.08  4676.1  300.58  4732.4  302.41  4744.0  305.93  4753.7  306.36
  4790.7  306.03  4860.6  303.06  4897.6  304.19  4965.6  304.09  4987.0  302.58
  4992.8  300.77  4997.7  302.44  5015.0  303.35  5099.1  304.01  5206.5  306.54
  5296.1  310.68  5333.7  311.49  5403.4  314.63  5426.7  314.43  5493.0  316.83
#Mann=3,-1,0
  4417.5    0.05       0  4672.0    0.05       0  4676.1    0.05       0
Bank Sta=4672,4676.1
Exp/Cntr=0.3,0.1

Type RM Length L Ch R = 1,3476,292,292,292
BEGIN DESCRIPTION:
B20015
END DESCRIPTION:
XS GIS Cut Line= 4
      2440641.34     13724404.51      2440055.38     13724552.08
      2439912.15     13724730.03      2439777.61     13725294.23
#Sta/Elev= 30
  4251.3  318.95  4262.4  318.88  4288.8  318.95  4299.1  317.16  4314.6  311.08
  4381.6  301.91  4493.0  300.04  4493.2  299.54  4497.1  300.04  4561.2  301.60
  4597.2  300.92  4618.8  302.66  4629.1  305.07  4660.0  308.11  4679.4  301.51
  4690.9  300.43  4732.2  302.81  4742.5  304.38  4802.7  302.14  4872.1  302.71
  4885.7  303.49  4893.7  305.24  4914.5  303.33  4978.5  302.10  4992.9  300.75
  5021.7  303.39  5130.2  304.10  5366.7  311.26  5435.8  314.39  5664.0  318.58
#Mann=4,-1,0
  4251.3   0.035       0  4262.4    0.05       0  4493.0    0.05       0
  4497.1    0.05       0
Bank Sta=4493,4497.1
Exp/Cntr=0.3,0.1

Type RM Length L Ch R = 1,3184,177,177,177
BEGIN DESCRIPTION:
PECAN BRANCH 1.0
END DESCRIPTION:
XS GIS Cut Line= 3
      2440624.99     13724375.00      2439825.00     13724425.00
      2439525.00     13725625.02
#Sta/Elev= 30
  4202.6  319.57  4222.6  319.15  4232.6  315.62  4285.3  305.86  4312.8  304.55
  4342.9  301.12  4445.6  299.51  4605.9  300.71  4661.4  298.76  4661.7  298.26
  4665.6  298.76  4733.6  298.95  4761.2  304.60  4863.9  302.84  4904.0  307.60
  4944.0  300.67  4954.1  300.21  5063.4  300.36  5096.9  302.81  5104.7  304.12
  5109.8  306.90  5127.8  307.92  5200.0  303.36  5292.8  303.43  5764.3  313.92
  5934.4  315.59  5970.5  317.45  5993.7  316.79  6034.9  319.05  6241.1  323.40
#Mann=3,-1,0
  4202.6    0.05       0  4661.4    0.05       0  4665.6    0.05       0
Bank Sta=4661.4,4665.6
Exp/Cntr=0.3,0.1

Type RM Length L Ch R = 1,3007,176,176,176
BEGIN DESCRIPTION:
B20014
END DESCRIPTION:
XS GIS Cut Line= 4
      2440958.15     13724304.69      2439873.09     13724230.90
      2439621.35     13724322.05      2439391.32     13725198.78
#Sta/Elev= 30
  3861.4  315.00  3935.1  314.21  4087.2  316.85  4185.3  319.00  4195.3  314.40
  4209.9  312.13  4215.4  310.57  4222.8  306.20  4245.4  302.63  4374.6  299.57
  4374.9  299.07  4378.8  299.57  4536.1  300.98  4736.6  300.61  4766.6  302.79
  4786.7  307.84  4796.7  307.02  4813.3  302.51  4876.9  302.67  4886.9  301.58
  4907.0  302.60  4999.9  301.55  5010.7  300.32  5097.2  302.79  5478.2  304.00
  5581.7  305.67  5674.6  304.69  5692.5  305.98  5757.4  304.48  6123.1  311.05
#Mann=5,-1,0
  3861.4    0.05       0  4087.2   0.035       0  4209.9    0.05       0
  4374.6    0.05       0  4378.8    0.05       0
Bank Sta=4374.6,4378.8
Exp/Cntr=0.3,0.1

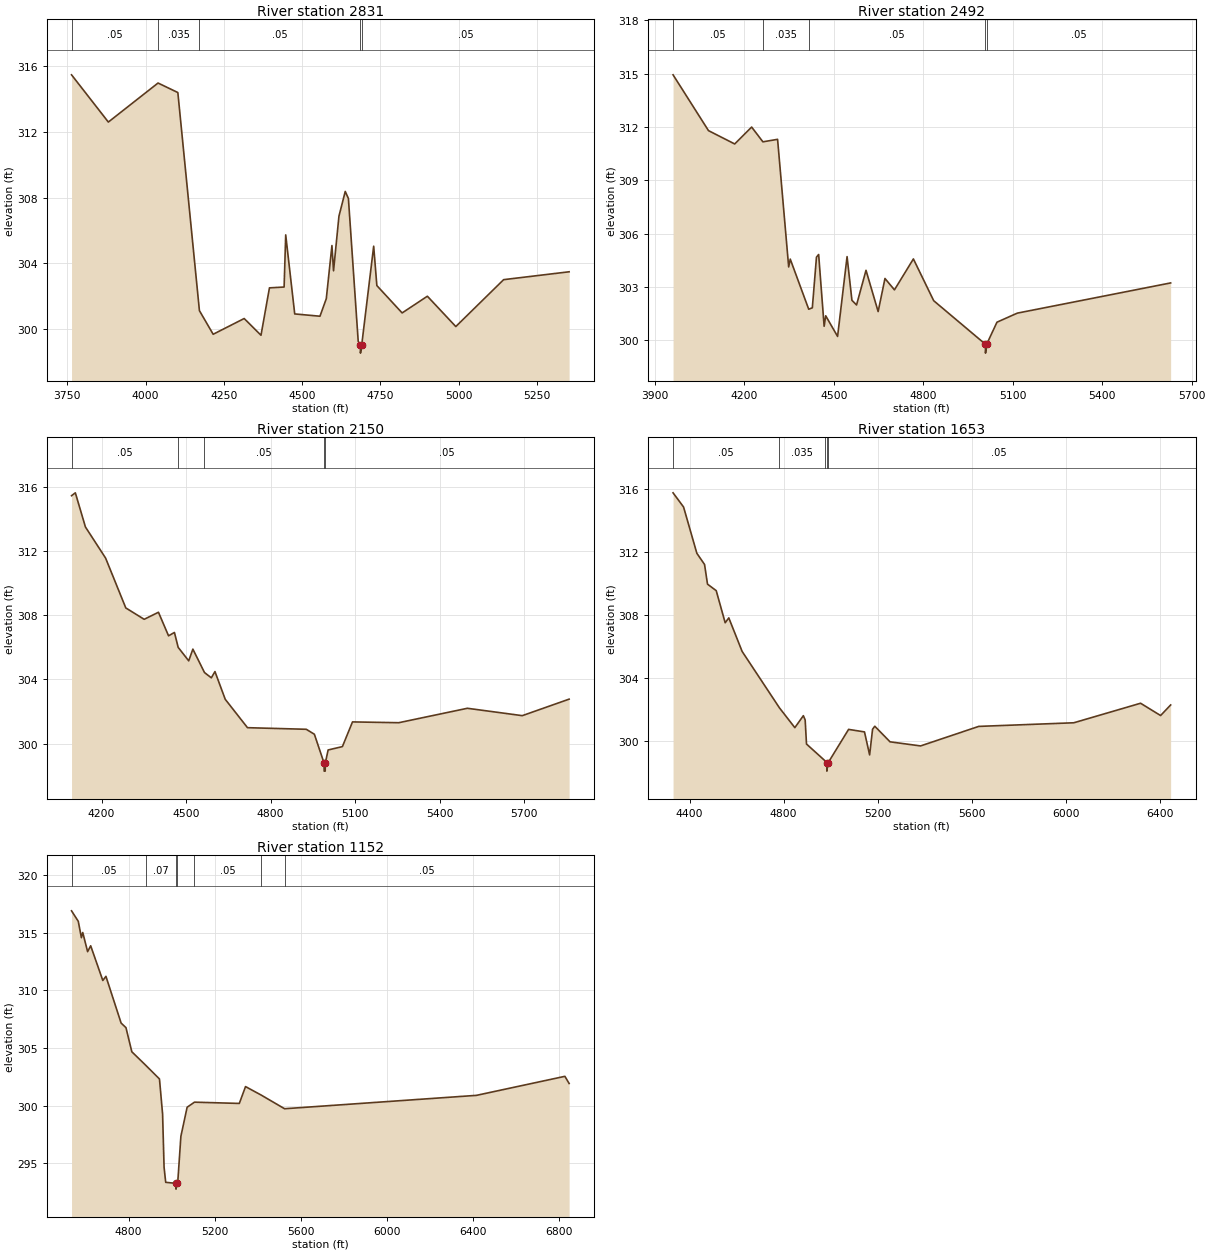
Type RM Length L Ch R = 1,2831,339,339,339
BEGIN DESCRIPTION:
B20013
END DESCRIPTION:
XS GIS Cut Line= 3
      2441001.54     13724248.26      2439708.16     13724078.99
      2439448.91     13724195.66
#Sta/Elev= 30
  3763.6  315.49  3881.1  312.61  4039.8  314.99  4103.0  314.41  4171.9  301.11
  4215.8  299.67  4314.8  300.63  4368.5  299.61  4395.5  302.50  4442.3  302.55
  4447.4  305.73  4476.2  300.91  4556.8  300.77  4577.0  301.84  4595.0  305.08
  4600.1  303.54  4617.4  306.87  4637.5  308.38  4647.6  307.95  4678.9  299.24
  4685.9  299.02  4686.1  298.52  4690.1  299.02  4728.3  305.04  4738.4  302.64
  4819.1  300.97  4899.7  301.99  4990.5  300.14  5143.2  303.00  5352.3  303.48
#Mann=5,-1,0
  3763.6    0.05       0  4039.8   0.035       0  4171.9    0.05       0
  4685.9    0.05       0  4690.1    0.05       0
Bank Sta=4685.9,4690.1
Exp/Cntr=0.3,0.1

Type RM Length L Ch R = 1,2492,342,342,342
BEGIN DESCRIPTION:
B20012
END DESCRIPTION:
XS GIS Cut Line= 4
      2441005.87     13724217.87      2439912.15     13723835.94
      2439734.20     13723901.04      2439501.18     13724121.12
#Sta/Elev= 30
  3961.0  314.93  4079.8  311.79  4167.7  311.04  4224.5  311.99  4262.3  311.16
  4311.5  311.30  4348.7  304.12  4354.0  304.56  4415.9  301.74  4428.0  301.82
  4441.9  304.67  4449.2  304.82  4467.6  300.78  4472.9  301.37  4512.7  300.21
  4544.5  304.70  4560.8  302.24  4576.3  301.98  4608.0  303.93  4648.7  301.61
  4671.6  303.47  4703.4  302.83  4766.9  304.57  4835.0  302.22  5008.4  299.77
  5008.7  299.27  5012.7  299.77  5047.1  301.01  5115.3  301.52  5629.5  303.22
#Mann=5,-1,0
  3961.0    0.05       0  4262.3   0.035       0  4415.9    0.05       0
  5008.4    0.05       0  5012.7    0.05       0
Bank Sta=5008.4,5012.7
Exp/Cntr=0.3,0.1

Type RM Length L Ch R = 1,2150,497,497,497
BEGIN DESCRIPTION:
B20011
END DESCRIPTION:
XS GIS Cut Line= 4
      2441023.24     13724196.17      2440185.59     13723614.58
      2439790.62     13723818.58      2439566.35     13724021.29
#Sta/Elev= 30
  4093.3  315.46  4106.8  315.64  4142.6  313.51  4214.2  311.57  4285.9  308.46
  4351.2  307.75  4401.9  308.19  4437.7  306.72  4458.6  306.93  4471.9  306.00
  4509.3  305.16  4524.1  305.89  4565.3  304.43  4589.6  304.10  4602.5  304.49
  4639.0  302.76  4718.0  300.99  4926.6  300.89  4955.5  300.58  4989.9  298.78
  4990.2  298.28  4993.9  298.28  4994.2  298.78  5004.3  299.60  5055.0  299.81
  5090.8  301.35  5255.0  301.30  5498.7  302.20  5693.6  301.74  5859.9  302.77
#Mann=5,-1,0
  4093.3    0.05       0  4471.9   0.035       0  4565.3    0.05       0
  4989.9    0.05       0  4994.2    0.05       0
Bank Sta=4989.9,4994.2
Exp/Cntr=0.3,0.1

Type RM Length L Ch R = 1,1653,501,501,501
BEGIN DESCRIPTION:
B20010
END DESCRIPTION:
XS GIS Cut Line= 4
      2441044.94     13724174.44      2440610.94     13723358.51
      2440181.25     13723462.67      2439612.67     13723953.13
#Sta/Elev= 30
  4329.9  315.73  4374.6  314.83  4431.2  311.89  4463.9  311.18  4476.5  309.93
  4513.5  309.52  4551.7  307.48  4567.1  307.79  4623.8  305.66  4782.5  302.08
  4848.1  300.82  4884.3  301.58  4892.0  301.31  4897.7  299.78  4976.3  298.72
  4984.1  298.56  4984.3  298.06  4988.4  298.56  5076.8  300.71  5144.4  300.55
  5166.3  299.09  5178.8  300.72  5188.3  300.91  5253.2  299.92  5383.1  299.66
  5630.6  300.90  6035.1  301.13  6319.2  302.37  6404.4  301.59  6447.1  302.26
#Mann=5,-1,0
  4329.9    0.05       0  4782.5   0.035       0  4976.3    0.05       0
  4984.1    0.05       0  4988.4    0.05       0
Bank Sta=4984.1,4988.4
Exp/Cntr=0.3,0.1

Type RM Length L Ch R = 1,1152,0,0,0
BEGIN DESCRIPTION:
B20009
END DESCRIPTION:
XS GIS Cut Line= 4
      2441448.62     13723905.39      2440945.14     13723254.34
      2440163.89     13723440.97      2439652.33     13723900.50
#Sta/Elev= 30
  4534.3  316.89  4565.6  315.98  4580.1  314.56  4586.4  315.01  4609.0  313.35
  4623.3  313.86  4679.7  310.85  4694.2  311.21  4764.8  307.16  4787.4  306.76
  4814.6  304.67  4879.8  303.49  4943.2  302.31  4957.7  299.27  4964.6  294.66
  4972.2  293.35  5019.8  293.26  5020.1  292.76  5024.2  293.26  5028.3  293.38
  5042.8  297.34  5071.8  299.86  5106.0  300.30  5314.5  300.19  5343.4  301.65
  5415.7  300.92  5525.0  299.73  6417.3  300.89  6828.5  302.54  6848.2  301.92
#Mann=7,-1,0
  4534.3    0.05       0  4879.8    0.07       0  5019.8    0.05       0
  5024.2    0.07       0  5106.0    0.05       0  5415.7   0.035       0
  5525.0    0.05       0
Bank Sta=5019.8,5024.2
Exp/Cntr=0.3,0.1

Chan Stop Cuts=-1