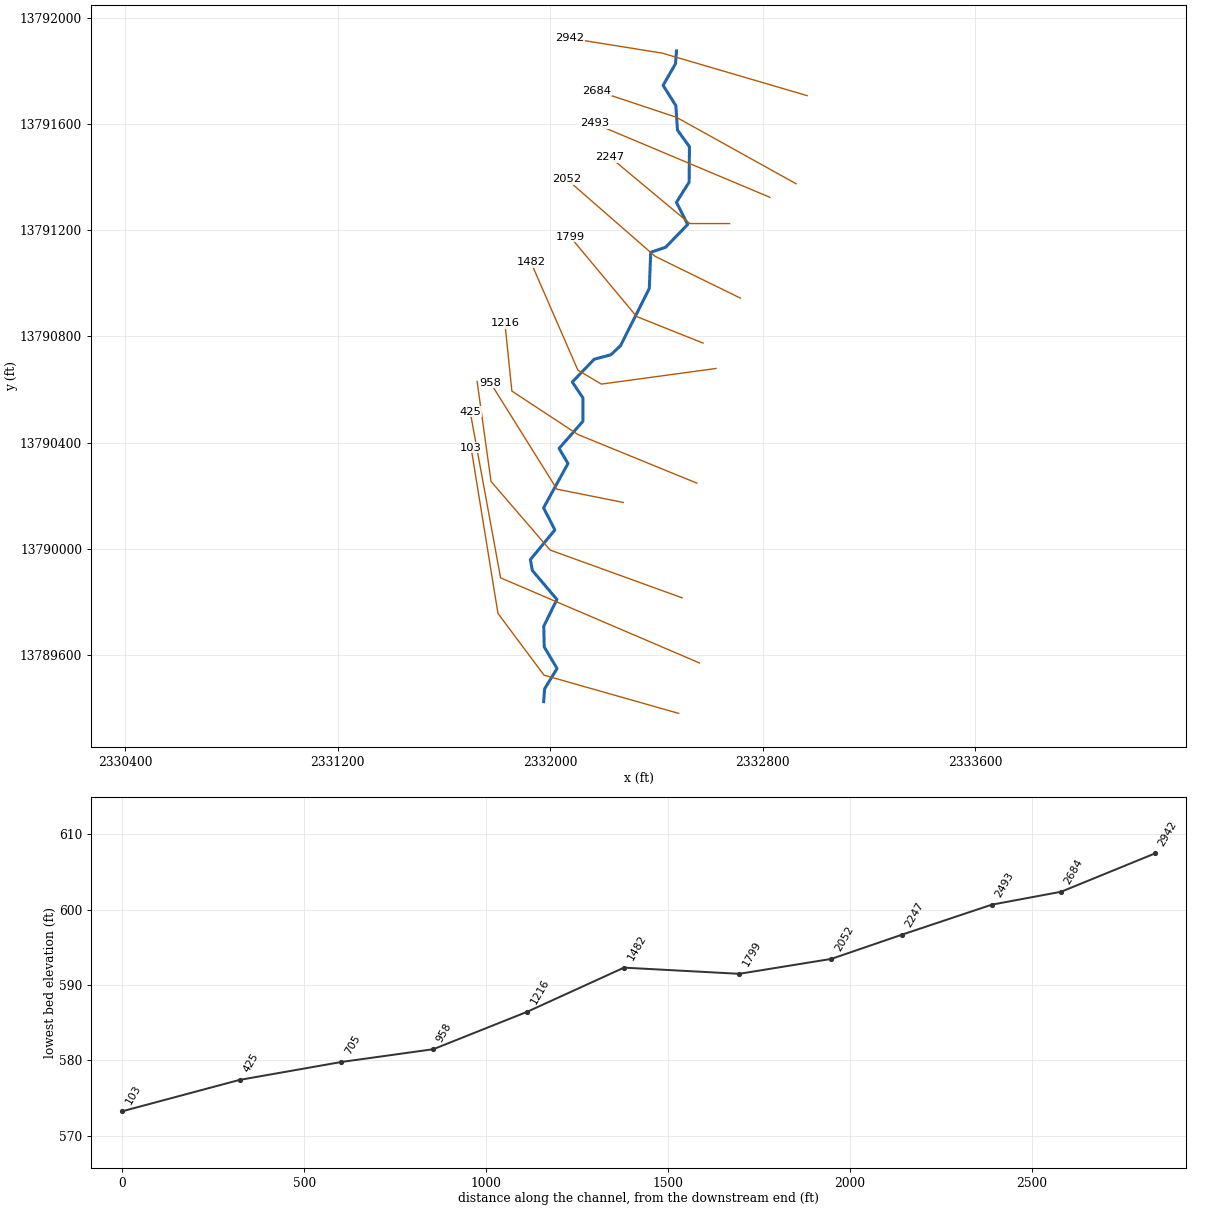
--- POLECAT CREEK 2.prj (project) ---

Proj Title=POLECAT CREEK 2 Base Level Engineering
Current Plan=p01
Default Exp/Contr=0.3,0.1
English Units
Geom File=g01
Flow File=f01
Plan File=p01
BEGIN DESCRIPTION:
POLECAT CREEK 2
END DESCRIPTION:

--- POLECAT CREEK 2.p01 (plan) ---

Plan Title=Multiple Run
Short Identifier=Multiple
Geom File=g01
Flow File=f01
Subcritical Flow
K Sum by GR= 0
Std Step Tol= 0.01
Critical Tol= 0.01
Num of Std Step Trials= 20
Max Error Tol= 0.3
Flow Tol Ratio= 0.001
Split Flow NTrial= 30
Split Flow Tol= 0.02
Split Flow Ratio= 0.02
Log Output Level= 0
Friction Slope Method= 1
Unsteady Friction Slope Method= 2
Unsteady Bridges Friction Slope Method= 1
Parabolic Critical Depth
Global Vel Dist=  1 , 1 , 1
Global Log Level= 0
CheckData=True
Encroach Param= -1, 0, 0, 0
BEGIN DESCRIPTION:
Multiple Run
END DESCRIPTION:

--- POLECAT CREEK 2.f01 (steady flow) ---

Flow Title=Multiple
Number of Profiles=7
Profile Names=10-year,25-year,50-year,1pct_min,100-year,1pct_plu,500-year
River Rch & RM= POLECAT CREEK 2,Reach-1,2942
     226     343     444     280     558    1114     870
Boundary for River Rch & Prof#=POLECAT CREEK 2,Reach-1,1
Up Type=0
Dn Type=3
Dn Slope=0.005
Boundary for River Rch & Prof#=POLECAT CREEK 2,Reach-1,2
Up Type=0
Dn Type=3
Dn Slope=0.005
Boundary for River Rch & Prof#=POLECAT CREEK 2,Reach-1,3
Up Type=0
Dn Type=3
Dn Slope=0.005
Boundary for River Rch & Prof#=POLECAT CREEK 2,Reach-1,4
Up Type=0
Dn Type=3
Dn Slope=0.005
Boundary for River Rch & Prof#=POLECAT CREEK 2,Reach-1,5
Up Type=0
Dn Type=3
Dn Slope=0.005
Boundary for River Rch & Prof#=POLECAT CREEK 2,Reach-1,6
Up Type=0
Dn Type=3
Dn Slope=0.005
Boundary for River Rch & Prof#=POLECAT CREEK 2,Reach-1,7
Up Type=0
Dn Type=3
Dn Slope=0.005

--- POLECAT CREEK 2.g01 (geometry) ---

Geom Title=Existing Conditions

River Reach=POLECAT CREEK 2,Reach-1
Reach XY= 30
      2332475.00     13791875.00      2332471.31     13791826.49
      2332424.66     13791745.17      2332472.62     13791669.03
      2332478.86     13791576.60      2332523.80     13791514.49
      2332522.72     13791380.93      2332474.79     13791304.79
      2332517.19     13791221.58      2332434.42     13791135.91
      2332378.08     13791116.69      2332372.75     13790980.94
      2332264.37     13790765.00      2332227.54     13790730.75
      2332165.29     13790714.21      2332082.79     13790628.43
      2332122.63     13790569.11      2332123.01     13790480.89
      2332033.01     13790378.33      2332066.75     13790321.77
      2331974.78     13790154.80      2332017.16     13790071.60
      2331924.90     13789959.64      2331932.48     13789918.96
      2332025.04     13789809.66      2331975.40     13789709.73
      2331977.19     13789630.97      2332025.47     13789550.00
      2331978.69     13789473.51      2331975.00     13789425.00

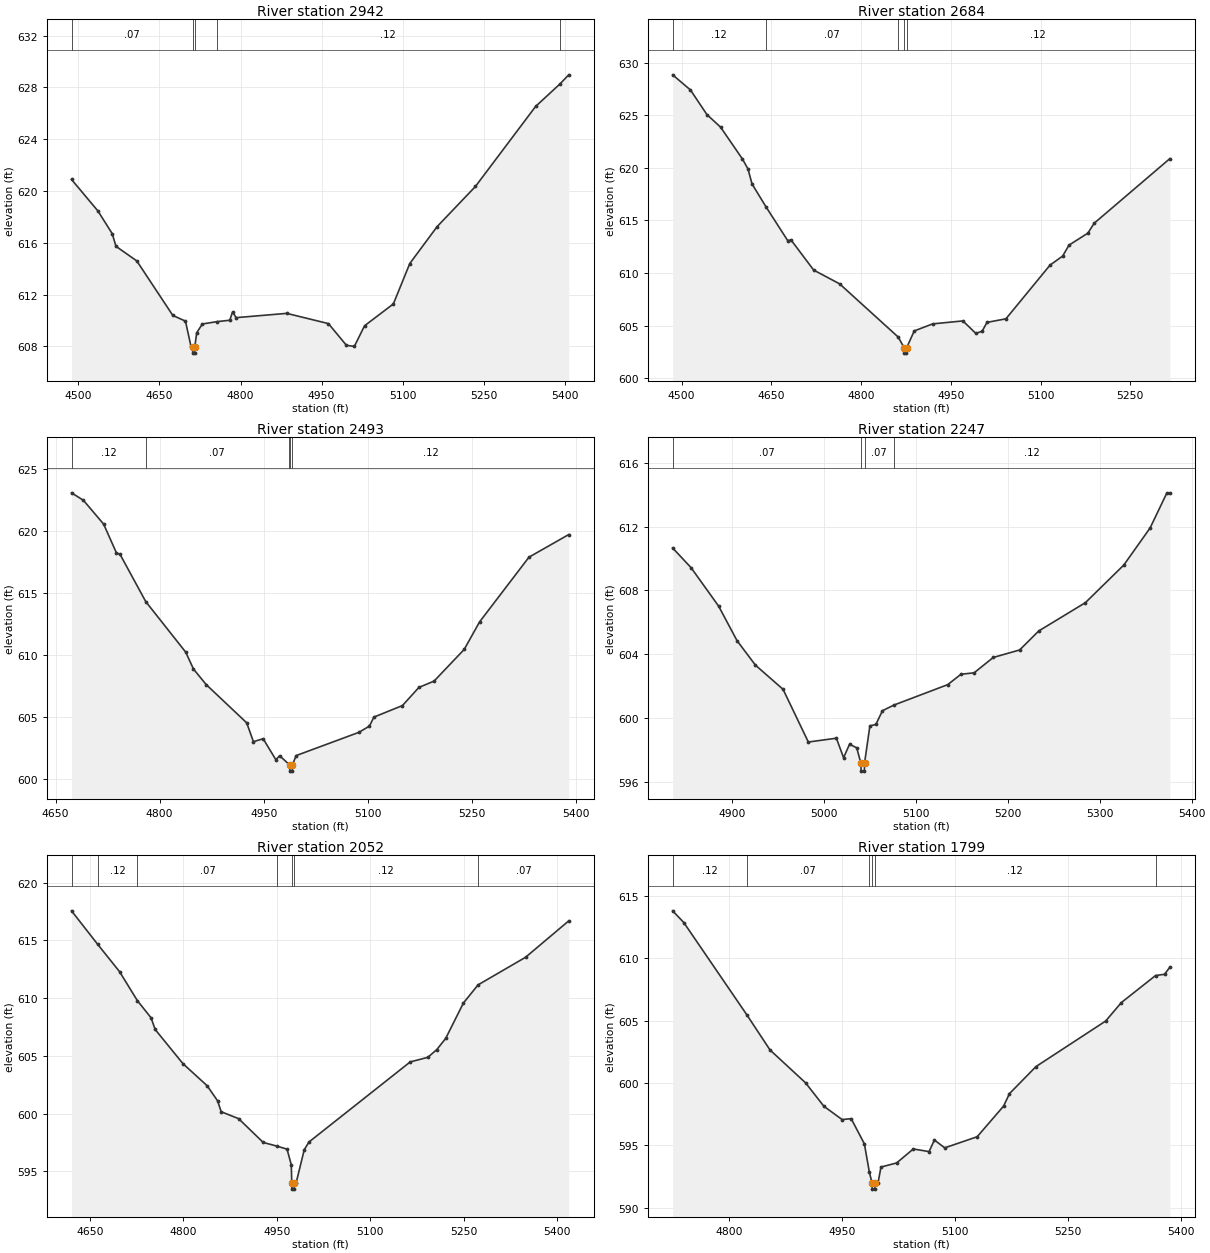
Type RM Length L Ch R = 1,2942,258,258,258
BEGIN DESCRIPTION:
B20109
END DESCRIPTION:
XS GIS Cut Line= 3
      2332967.34     13791706.43      2332421.18     13791866.67
      2332074.49     13791922.28
#Sta/Elev= 30
  4487.2  620.89  4536.0  618.46  4562.6  616.70  4569.4  615.73  4608.0  614.60
  4674.7  610.39  4698.1  609.95  4708.1  608.04  4711.4  607.98  4711.6  607.48
  4715.1  607.48  4715.4  607.98  4718.9  609.05  4729.3  609.73  4756.2  609.91
  4780.1  610.02  4785.3  610.66  4791.9  610.22  4885.5  610.55  4962.7  609.76
  4996.1  608.08  5010.7  608.00  5029.5  609.59  5082.9  611.28  5113.3  614.40
  5163.9  617.25  5234.8  620.35  5346.2  626.53  5391.1  628.26  5407.5  628.97
#Mann=5,-1,0
  4487.2    0.07       0  4711.4    0.05       0  4715.4    0.07       0
  4756.2    0.12       0  5391.1    0.07       0
Bank Sta=4711.4,4715.4
Exp/Cntr=0.3,0.1

Type RM Length L Ch R = 1,2684,191,191,191
BEGIN DESCRIPTION:
POLECAT CREEK 2 5.0
END DESCRIPTION:
XS GIS Cut Line= 3
      2332925.01     13791374.99      2332475.00     13791625.00
      2332175.02     13791724.99
#Sta/Elev= 30
  4485.2  628.83  4515.0  627.39  4542.4  625.06  4565.3  623.86  4601.9  620.83
  4611.1  619.89  4617.9  618.46  4641.2  616.29  4677.4  613.09  4683.1  613.14
  4720.9  610.28  4764.3  608.97  4862.3  603.91  4872.2  602.89  4872.4  602.39
  4875.9  602.39  4876.2  602.89  4889.0  604.50  4919.9  605.17  4970.3  605.45
  4992.0  604.26  5002.6  604.48  5010.5  605.31  5042.2  605.65  5115.9  610.75
  5137.0  611.61  5147.6  612.65  5179.2  613.79  5189.7  614.73  5316.2  620.87
#Mann=5,-1,0
  4485.2    0.12       0  4641.2    0.07       0  4862.3    0.12       0
  4872.2    0.05       0  4876.2    0.12       0
Bank Sta=4872.2,4876.2
Exp/Cntr=0.3,0.1

Type RM Length L Ch R = 1,2493,246,246,246
BEGIN DESCRIPTION:
B20108
END DESCRIPTION:
XS GIS Cut Line= 2
      2332826.71     13791323.76      2332166.12     13791601.74
#Sta/Elev= 30
  4673.1  623.08  4690.2  622.48  4719.4  620.56  4737.7  618.26  4743.1  618.12
  4780.1  614.32  4837.7  610.25  4848.9  608.89  4867.2  607.64  4925.6  604.56
  4935.3  603.04  4949.3  603.28  4967.6  601.59  4973.1  601.91  4986.3  601.23
  4987.6  601.17  4987.8  600.67  4991.3  600.67  4991.6  601.17  4996.8  601.92
  5087.2  603.79  5102.6  604.30  5108.9  605.02  5150.1  605.95  5173.8  607.41
  5195.7  607.92  5239.1  610.47  5261.3  612.69  5332.5  617.90  5389.8  619.72
#Mann=5,-1,0
  4673.1    0.12       0  4780.1    0.07       0  4986.3    0.12       0
  4987.6    0.05       0  4991.6    0.12       0
Bank Sta=4987.6,4991.6
Exp/Cntr=0.3,0.1

Type RM Length L Ch R = 1,2247,195,195,195
BEGIN DESCRIPTION:
POLECAT CREEK 2 4.0
END DESCRIPTION:
XS GIS Cut Line= 3
      2332675.00     13791225.00      2332525.00     13791225.00
      2332225.01     13791474.99
#Sta/Elev= 30
  4835.8  610.66  4855.8  609.43  4885.8  607.02  4905.8  604.86  4925.8  603.33
  4955.8  601.82  4983.3  598.52  5013.8  598.76  5021.6  597.54  5028.1  598.38
  5035.9  598.16  5040.4  597.20  5040.7  596.70  5044.2  596.70  5044.4  597.20
  5050.2  599.53  5056.7  599.62  5063.9  600.48  5076.2  600.83  5134.8  602.11
  5149.2  602.76  5163.5  602.85  5184.3  603.81  5213.0  604.28  5233.8  605.47
  5284.5  607.24  5326.2  609.59  5354.8  611.91  5373.1  614.11  5376.3  614.11
#Mann=4,-1,0
  4835.8    0.07       0  5040.4    0.05       0  5044.4    0.07       0
  5076.2    0.12       0
Bank Sta=5040.4,5044.4
Exp/Cntr=0.3,0.1

Type RM Length L Ch R = 1,2052,253,253,253
BEGIN DESCRIPTION:
B20107
END DESCRIPTION:
XS GIS Cut Line= 3
      2332715.53     13790944.36      2332395.02     13791101.35
      2332062.80     13791391.22
#Sta/Elev= 30
  4620.4  617.56  4662.5  614.65  4697.4  612.30  4726.0  609.79  4748.0  608.30
  4754.6  607.29  4799.2  604.33  4838.0  602.42  4854.8  601.11  4860.5  600.17
  4888.5  599.57  4928.0  597.51  4950.8  597.18  4966.2  596.93  4973.0  595.58
  4973.8  593.97  4974.0  593.47  4977.5  593.47  4977.8  593.97  4980.6  593.97
  4993.8  596.88  5001.4  597.55  5163.8  604.48  5192.2  604.88  5206.5  605.55
  5220.7  606.51  5249.2  609.58  5272.7  611.15  5348.9  613.54  5418.2  616.69
#Mann=7,-1,0
  4620.4    0.07       0  4662.5    0.12       0  4726.0    0.07       0
  4950.8    0.12       0  4973.8    0.05       0  4977.8    0.12       0
  5272.7    0.07       0
Bank Sta=4973.8,4977.8
Exp/Cntr=0.3,0.1

Type RM Length L Ch R = 1,1799,317,317,317
BEGIN DESCRIPTION:
POLECAT CREEK 2 3.0
END DESCRIPTION:
XS GIS Cut Line= 3
      2332574.98     13790775.01      2332325.00     13790875.00
      2332075.03     13791174.96
#Sta/Elev= 30
  4725.5  613.81  4740.3  612.87  4823.7  605.49  4854.7  602.65  4901.8  600.02
  4926.1  598.14  4950.3  597.07  4962.4  597.14  4979.9  595.12  4986.5  592.85
  4990.0  591.99  4990.3  591.49  4993.8  591.49  4994.0  591.99  4998.0  591.99
  5001.9  593.26  5022.7  593.59  5044.8  594.71  5065.7  594.50  5072.8  595.43
  5086.5  594.80  5129.5  595.69  5164.6  598.15  5172.4  599.15  5207.6  601.32
  5300.0  604.97  5320.8  606.45  5366.2  608.62  5378.1  608.72  5385.2  609.29
#Mann=6,-1,0
  4725.5    0.12       0  4823.7    0.07       0  4986.5    0.12       0
  4990.0    0.05       0  4994.0    0.12       0  5366.2    0.07       0
Bank Sta=4990,4994
Exp/Cntr=0.3,0.1

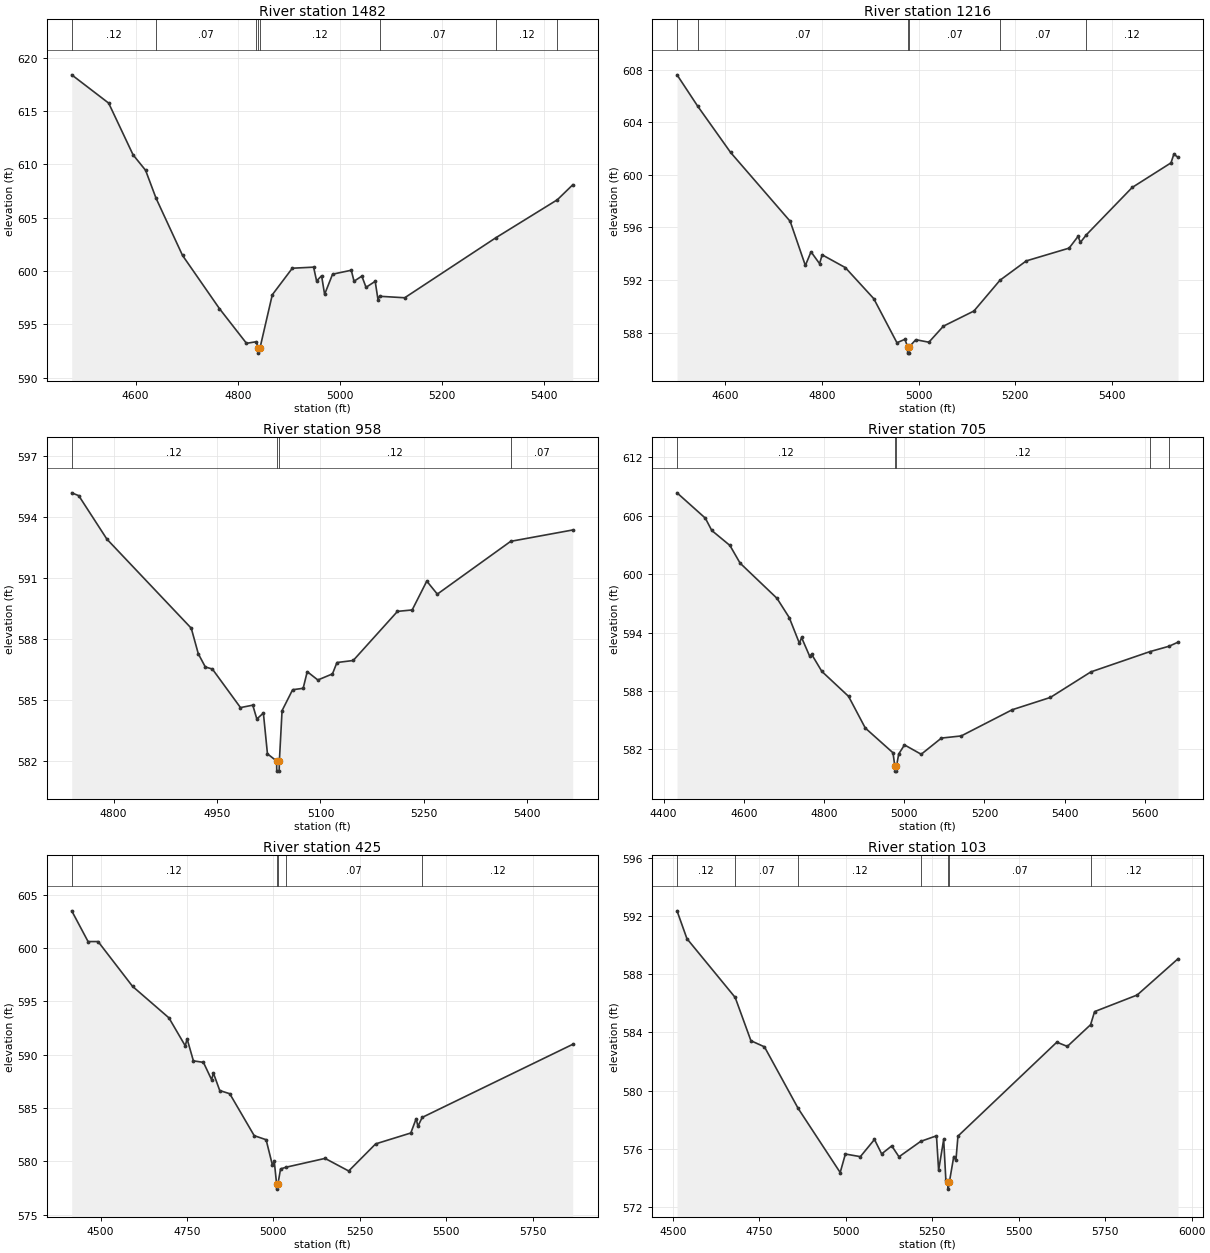
Type RM Length L Ch R = 1,1482,266,266,266
BEGIN DESCRIPTION:
B20106
END DESCRIPTION:
XS GIS Cut Line= 4
      2332623.97     13790679.44      2332192.24     13790620.56
      2332103.93     13790672.89      2331927.33     13791078.43
#Sta/Elev= 30
  4474.8  618.40  4547.1  615.75  4594.9  610.90  4619.4  609.45  4639.8  606.84
  4691.7  601.47  4764.0  596.48  4816.9  593.23  4836.3  593.38  4839.4  592.81
  4839.7  592.31  4843.4  592.81  4867.4  597.78  4906.6  600.27  4948.3  600.37
  4954.1  599.08  4963.9  599.56  4969.8  597.82  4985.4  599.71  5022.0  600.08
  5027.4  599.05  5042.7  599.53  5050.9  598.48  5068.8  599.04  5074.3  597.33
  5077.3  597.64  5126.6  597.50  5304.8  603.12  5425.4  606.69  5455.5  608.09
#Mann=8,-1,0
  4474.8    0.12       0  4639.8    0.07       0  4836.3    0.12       0
  4839.4    0.05       0  4843.4    0.12       0  5077.3    0.07       0
  5304.8    0.12       0  5425.4    0.07       0
Bank Sta=4839.4,4843.4
Exp/Cntr=0.3,0.1

Type RM Length L Ch R = 1,1216,258,258,258
BEGIN DESCRIPTION:
B20105
END DESCRIPTION:
XS GIS Cut Line= 4
      2332551.99     13790247.72      2332103.93     13790430.87
      2331855.36     13790594.40      2331829.20     13790849.48
#Sta/Elev= 30
  4499.6  607.60  4542.2  605.23  4610.6  601.70  4734.0  596.47  4765.5  593.11
  4777.2  594.15  4794.9  593.25  4800.3  593.92  4848.3  592.95  4907.2  590.59
  4955.2  587.24  4971.7  587.50  4977.2  586.95  4977.5  586.45  4981.0  586.45
  4981.2  586.95  4994.3  587.47  5021.4  587.28  5051.5  588.50  5114.7  589.65
  5168.7  591.99  5223.2  593.46  5311.9  594.43  5330.4  595.32  5335.4  594.87
  5347.6  595.44  5442.6  599.04  5523.0  600.91  5528.9  601.57  5537.6  601.33
#Mann=6,-1,0
  4499.6    0.12       0  4542.2    0.07       0  4977.2    0.05       0
  4981.2    0.07       0  5168.7    0.07       0  5347.6    0.12       0
Bank Sta=4977.2,4981.2
Exp/Cntr=0.3,0.1

Type RM Length L Ch R = 1,958,253,253,253
BEGIN DESCRIPTION:
POLECAT CREEK 2 1.0
END DESCRIPTION:
XS GIS Cut Line= 3
      2332275.02     13790175.00      2332025.00     13790225.00
      2331774.98     13790625.03
#Sta/Elev= 30
  4739.2  595.19  4749.4  595.05  4790.2  592.91  4912.6  588.52  4922.8  587.26
  4933.0  586.61  4943.2  586.51  4984.0  584.61  5001.8  584.73  5007.7  584.05
  5017.2  584.34  5023.1  582.33  5036.4  581.98  5036.6  581.48  5040.1  581.48
  5040.4  581.98  5044.3  584.46  5059.6  585.49  5074.9  585.56  5080.8  586.38
  5096.2  585.97  5117.4  586.27  5123.9  586.83  5147.5  586.93  5211.7  589.35
  5233.0  589.42  5254.2  590.84  5269.5  590.20  5375.9  592.80  5465.9  593.36
#Mann=4,-1,0
  4739.2    0.12       0  5036.4    0.05       0  5040.4    0.12       0
  5375.9    0.07       0
Bank Sta=5036.4,5040.4
Exp/Cntr=0.3,0.1

Type RM Length L Ch R = 1,705,280,280,280
BEGIN DESCRIPTION:
B20104
END DESCRIPTION:
XS GIS Cut Line= 4
      2332496.43     13789815.98      2331999.27     13789995.87
      2331776.87     13790254.25      2331724.56     13790630.22
#Sta/Elev= 30
  4433.5  608.33  4504.1  605.73  4520.1  604.47  4565.4  602.93  4590.7  601.12
  4682.7  597.51  4713.3  595.53  4738.7  592.89  4744.0  593.49  4764.0  591.59
  4769.3  591.75  4794.6  590.01  4861.2  587.45  4902.9  584.20  4972.0  581.66
  4976.6  580.28  4976.9  579.78  4980.4  579.78  4980.6  580.28  4986.3  581.54
  5000.6  582.47  5042.3  581.51  5092.7  583.17  5142.1  583.39  5269.4  586.08
  5364.4  587.34  5465.4  589.96  5611.8  592.03  5660.2  592.59  5682.7  593.01
#Mann=5,-1,0
  4433.5    0.12       0  4976.6    0.05       0  4980.6    0.12       0
  5611.8    0.07       0  5660.2    0.12       0
Bank Sta=4976.6,4980.6
Exp/Cntr=0.3,0.1

Type RM Length L Ch R = 1,425,322,322,322
BEGIN DESCRIPTION:
B20103
END DESCRIPTION:
XS GIS Cut Line= 3
      2332561.84     13789570.68      2331812.85     13789891.21
      2331698.37     13790515.91
#Sta/Elev= 30
  4416.6  603.48  4463.9  600.60  4492.9  600.60  4592.7  596.40  4697.9  593.45
  4745.1  590.83  4750.5  591.48  4768.7  589.42  4797.7  589.28  4821.3  587.66
  4826.7  588.27  4844.9  586.64  4873.9  586.34  4944.7  582.41  4979.1  582.03
  4997.3  579.66  5002.7  580.01  5009.4  577.90  5009.7  577.40  5013.4  577.90
  5020.9  579.29  5036.4  579.45  5149.7  580.28  5218.1  579.10  5296.1  581.64
  5397.8  582.66  5413.3  584.00  5418.4  583.29  5430.7  584.12  5866.4  590.97
#Mann=5,-1,0
  4416.6    0.12       0  5009.4    0.05       0  5013.4    0.12       0
  5036.4    0.07       0  5430.7    0.12       0
Bank Sta=5009.4,5013.4
Exp/Cntr=0.3,0.1

Type RM Length L Ch R = 1,103,0,0,0
BEGIN DESCRIPTION:
B20102
END DESCRIPTION:
XS GIS Cut Line= 4
      2332483.29     13789381.00      2331976.38     13789524.90
      2331803.03     13789757.12      2331701.79     13790380.93
#Sta/Elev= 30
  4512.0  592.35  4540.6  590.44  4680.2  586.40  4725.7  583.43  4764.8  583.01
  4862.3  578.78  4983.8  574.38  4998.8  575.65  5042.1  575.47  5082.9  576.65
  5103.7  575.66  5132.9  576.21  5153.8  575.46  5216.6  576.52  5262.2  576.90
  5268.4  574.53  5283.0  576.65  5289.3  573.87  5295.6  573.74  5295.9  573.24
  5299.6  573.74  5312.2  575.48  5318.5  575.24  5324.3  576.88  5610.2  583.33
  5640.6  583.04  5707.8  584.53  5719.4  585.43  5842.6  586.57  5960.7  589.06
#Mann=7,-1,0
  4512.0    0.12       0  4680.2    0.07       0  4862.3    0.12       0
  5216.6    0.07       0  5295.6    0.05       0  5299.6    0.07       0
  5707.8    0.12       0
Bank Sta=5295.6,5299.6
Exp/Cntr=0.3,0.1

Chan Stop Cuts=-1