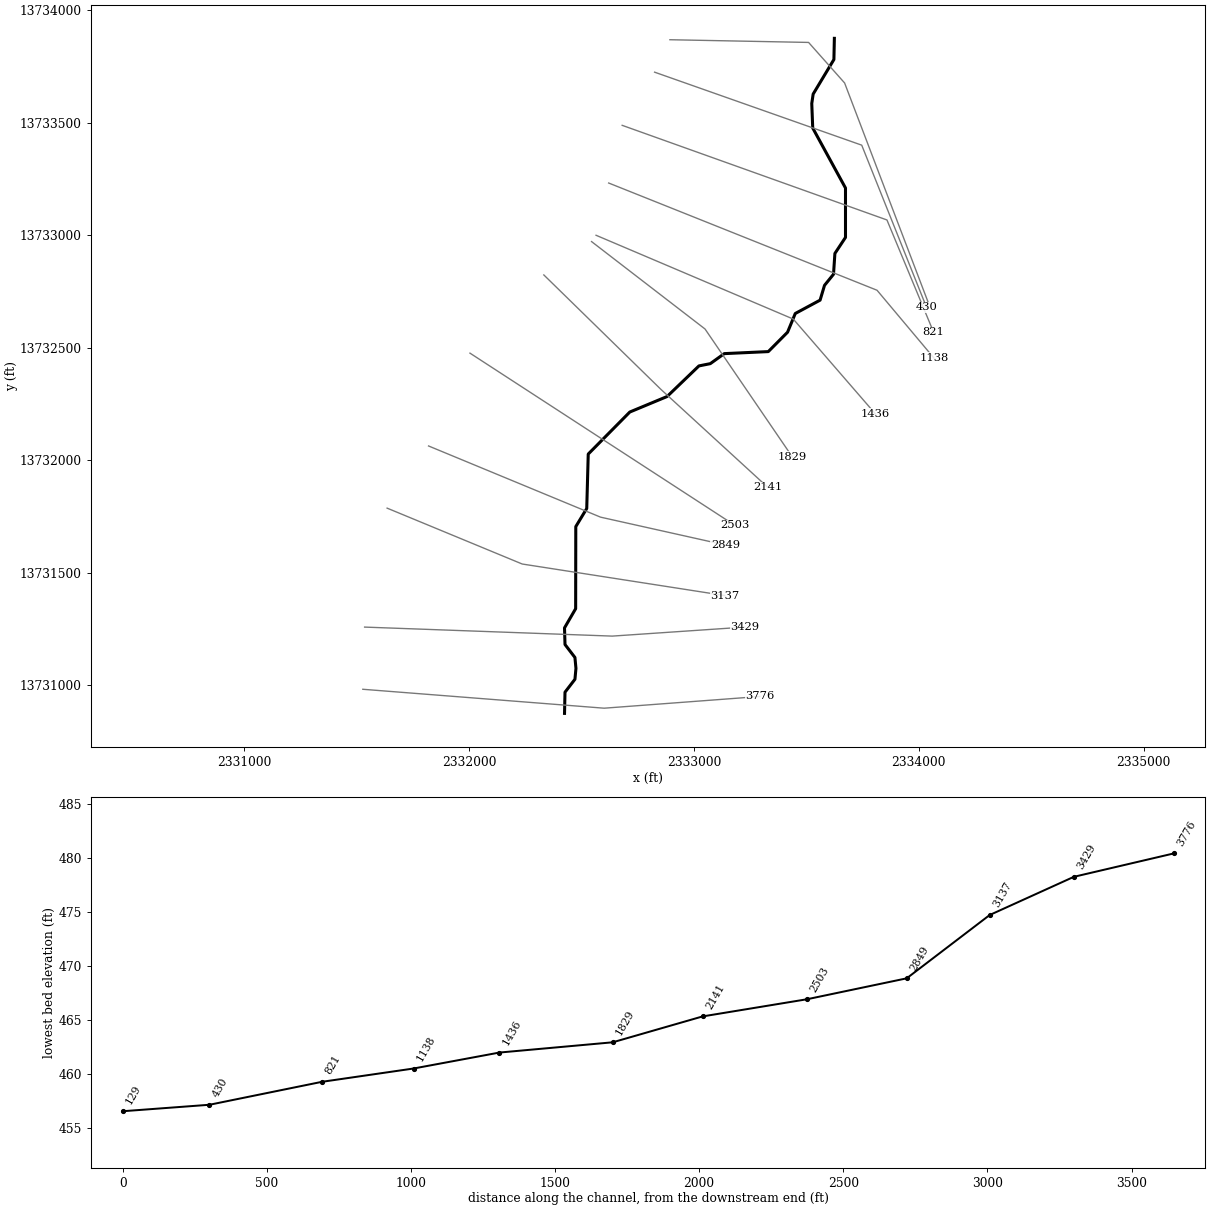
--- POLECAT CREEK 3.prj (project) ---

Proj Title=POLECAT CREEK 3 Base Level Engineering
Current Plan=p01
Default Exp/Contr=0.3,0.1
English Units
Geom File=g01
Flow File=f01
Plan File=p01
Y Axis Title=Elevation
X Axis Title(PF)=Main Channel Distance
X Axis Title(XS)=Station
BEGIN DESCRIPTION:
POLECAT CREEK 3
END DESCRIPTION:
DSS Export Rating Curves= 0
DSS Export Rating Curve Sorted= 0
DSS Export Volume Flow Curves= 0
DXF OffsetX= 0
DXF OffsetY= 0
DXF ScaleX= 1
DXF ScaleY= 10

--- POLECAT CREEK 3.p01 (plan) ---

Plan Title=Multiple Run
Short Identifier=Multiple
Geom File=g01
Flow File=f01
Subcritical Flow
K Sum by GR= 0
Std Step Tol= 0.01
Critical Tol= 0.01
Num of Std Step Trials= 20
Max Error Tol= 0.3
Flow Tol Ratio= 0.001
Split Flow NTrial= 30
Split Flow Tol= 0.02
Split Flow Ratio= 0.02
Log Output Level= 0
Friction Slope Method= 1
Unsteady Friction Slope Method= 2
Unsteady Bridges Friction Slope Method= 1
Parabolic Critical Depth
Global Vel Dist=  1 , 1 , 1
Global Log Level= 0
CheckData=True
Encroach Param= -1, 0, 0, 0
BEGIN DESCRIPTION:
Multiple Run
END DESCRIPTION:

--- POLECAT CREEK 3.f01 (steady flow) ---

Flow Title=Multiple
Number of Profiles=7
Profile Names=10-year,25-year,50-year,1pct_min,100-year,1pct_plu,500-year
River Rch & RM= POLECAT CREEK 3,Reach-1,3776
    1130    1917    2666    1795    3581    7146    6408
Boundary for River Rch & Prof#=POLECAT CREEK 3,Reach-1,1
Up Type=0
Dn Type=3
Dn Slope=0.005
Boundary for River Rch & Prof#=POLECAT CREEK 3,Reach-1,2
Up Type=0
Dn Type=3
Dn Slope=0.005
Boundary for River Rch & Prof#=POLECAT CREEK 3,Reach-1,3
Up Type=0
Dn Type=3
Dn Slope=0.005
Boundary for River Rch & Prof#=POLECAT CREEK 3,Reach-1,4
Up Type=0
Dn Type=3
Dn Slope=0.005
Boundary for River Rch & Prof#=POLECAT CREEK 3,Reach-1,5
Up Type=0
Dn Type=3
Dn Slope=0.005
Boundary for River Rch & Prof#=POLECAT CREEK 3,Reach-1,6
Up Type=0
Dn Type=3
Dn Slope=0.005
Boundary for River Rch & Prof#=POLECAT CREEK 3,Reach-1,7
Up Type=0
Dn Type=3
Dn Slope=0.005

--- POLECAT CREEK 3.g01 (geometry) ---

Geom Title=Existing Conditions
Program Version=4.10

River Reach=POLECAT CREEK 3 ,Reach-1
Reach XY= 30
        2332425.       13730875.      2332427.11     13730969.13
      2332471.33     13731026.58      2332475.82       13731075.
      2332471.29      13731123.4      2332427.17     13731180.97
      2332424.91      13731254.9      2332474.48     13731340.22
      2332475.07     13731704.97      2332523.78      13731785.5
      2332530.46     13732027.45      2332715.32     13732214.24
      2332881.06     13732283.14       2333022.7     13732419.17
      2333073.25     13732429.22       2333135.5      13732473.8
      2333331.21      13732482.8      2333416.84     13732568.95
      2333451.17     13732652.14      2333561.52     13732711.44
      2333581.15     13732777.15      2333621.18     13732826.58
      2333627.36     13732919.02      2333674.48     13732990.22
      2333674.49     13733209.79      2333528.74     13733476.56
       2333524.5     13733585.17       2333530.7     13733627.35
      2333622.93     13733780.86        2333625.       13733875.

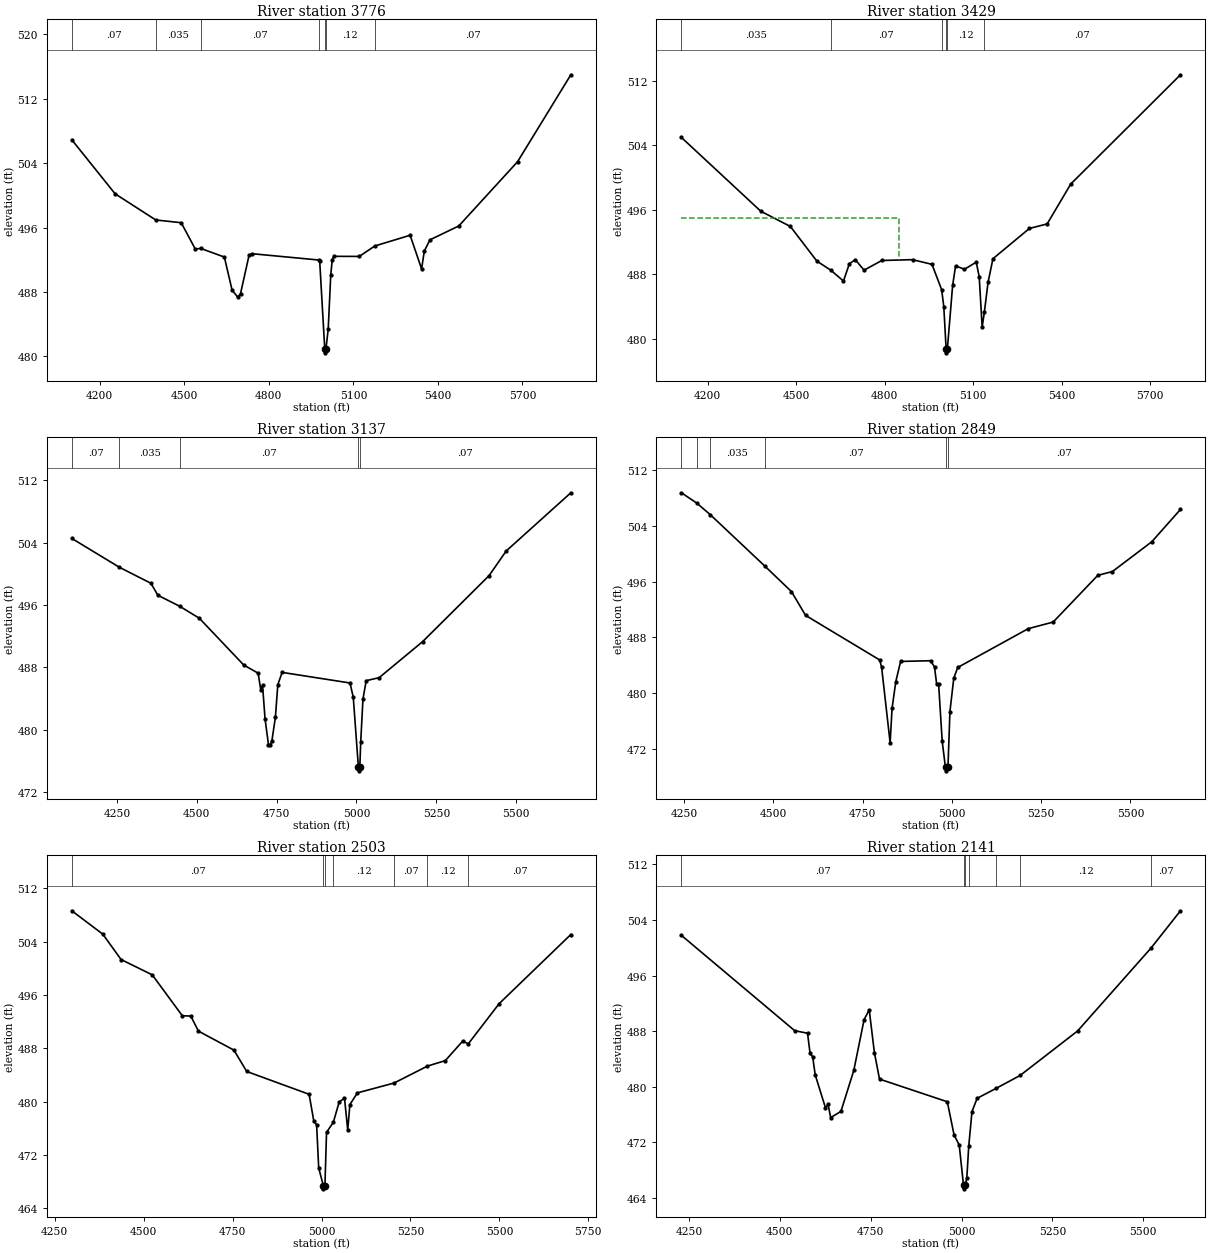
Type RM Length L Ch R = 1 ,3776    ,347,347,347
BEGIN DESCRIPTION:
B20121
END DESCRIPTION:
XS GIS Cut Line= 3
        2331528.     13730982.11      2332601.28     13730898.01
      2333293.66     13730950.04
#Sta/Elev= 30
  4100.7   506.9  4254.4  500.19  4398.6  496.94  4488.9   496.6    4539  493.32
  4557.7  493.41  4642.1  492.33  4669.4  488.23  4689.5  487.35  4699.5   487.8
  4729.6  492.53  4739.6  492.75  4978.1  491.96  4980.4  491.81  4998.3  480.93
  4998.6  480.43  5002.6  480.93  5010.5  483.35  5019.6  490.06  5024.7  491.98
  5030.5  492.42  5120.8  492.41  5176.1  493.71  5301.3  495.04  5341.9  490.86
  5351.5  493.06  5371.5  494.47  5473.8  496.19  5682.4  504.17  5871.6  514.98
#Mann= 7 ,-1 , 0
  4100.7     .07       0  4398.6    .035       0  4557.7     .07       0
  4978.1     .12       0  4998.3     .05       0  5002.6     .12       0
  5176.1     .07       0
Bank Sta=4998.3,5002.6
XS Rating Curve= 0 ,0
Exp/Cntr=0.3,0.1

Type RM Length L Ch R = 1 ,3429    ,292,292,292
BEGIN DESCRIPTION:
B20120
END DESCRIPTION:
XS GIS Cut Line= 3
      2331535.99     13731258.45      2332637.32      13731218.4
      2333226.01     13731258.44
#Sta/Elev= 30
  4111.2  504.96  4380.4  495.81  4480.5  493.93  4570.5  489.63  4617.8   488.5
  4660.6  487.16  4680.6   489.3  4700.6  489.81  4730.6  488.51  4790.7  489.71
  4894.9  489.81  4960.8  489.23  4993.6  486.08  5000.8  483.98  5008.7  478.76
    5009  478.26    5013  478.76  5030.8  486.62  5040.8  489.04  5070.8  488.62
  5110.9   489.5  5120.9  487.69  5130.9  481.46  5138.3  483.28  5150.9     487
  5167.5  489.93  5291.1  493.68  5351.3  494.24  5431.4  499.19  5803.3  512.73
#Mann= 6 ,-1 , 0
  4111.2    .035       0  4617.8     .07       0  4993.6     .12       0
  5008.7     .05       0    5013     .12       0  5138.3     .07       0
#XS Ineff= 2 , 0
       0    4850     495               0
Permanent Ineff=
       F       F
Bank Sta=5008.7,5013
XS Rating Curve= 0 ,0
Exp/Cntr=0.3,0.1

Type RM Length L Ch R = 1 ,3137    ,288,288,288
BEGIN DESCRIPTION:
B20119
END DESCRIPTION:
XS GIS Cut Line= 3
      2331636.07      13731787.1      2332236.84     13731538.79
      2333137.94     13731398.62
#Sta/Elev= 30
  4108.9  504.56    4258  500.85  4356.6   498.8  4378.3  497.26  4446.2  495.86
  4508.1  494.31  4647.2   488.3  4692.1  487.26  4700.4   485.1  4705.9  485.71
  4713.7  481.42  4724.4   478.1  4729.8     478  4735.3   478.6  4746.2  481.62
  4753.7  485.78  4767.2  487.36  4979.7     486  4989.9  484.16  5005.9  475.22
  5006.3  474.72  5010.4  475.22  5013.2  478.41  5020.2  483.93  5030.4   486.3
  5070.8  486.68    5207  491.31  5414.9  499.78  5468.6  502.95  5670.9  510.42
#Mann= 5 ,-1 , 0
  4108.9     .07       0    4258    .035       0  4446.2     .07       0
  5005.9     .05       0  5010.4     .07       0
Bank Sta=5005.9,5010.4
XS Rating Curve= 0 ,0
Exp/Cntr=0.3,0.1

Type RM Length L Ch R = 1 ,2849    ,346,346,346
BEGIN DESCRIPTION:
B20118
END DESCRIPTION:
XS GIS Cut Line= 3
      2331820.33     13732063.42      2332585.26     13731747.04
      2333140.93     13731623.11
#Sta/Elev= 30
  4242.9  508.75  4285.8  507.27  4323.2  505.63  4475.6  498.27    4551  494.57
  4590.4  491.16  4797.9  484.76  4803.3  483.74  4827.2  472.87  4832.6  477.83
  4843.1  481.66  4856.5  484.55  4940.5  484.65  4951.4  483.75  4957.5  481.28
  4962.9  481.32    4973  473.07  4981.4  469.61  4984.6  469.35  4984.9  468.85
  4989.1  469.35  4994.6  477.36  5005.3  482.13  5016.3  483.68  5213.8  489.25
  5283.6   490.2  5408.5   496.9  5449.5  497.45  5559.7  501.72    5640  506.36
#Mann= 6 ,-1 , 0
  4242.9    .035       0  4285.8     .07       0  4323.2    .035       0
  4475.6     .07       0  4984.6     .05       0  4989.1     .07       0
Bank Sta=4984.6,4989.1
XS Rating Curve= 0 ,0
Exp/Cntr=0.3,0.1

Type RM Length L Ch R = 1 ,2503    ,362,362,362
BEGIN DESCRIPTION:
B20117
END DESCRIPTION:
XS GIS Cut Line= 2
      2332004.53     13732475.94      2333180.97     13731711.66
#Sta/Elev= 30
  4297.9  508.61  4385.1   505.1  4436.4   501.3  4524.1     499  4608.5  492.87
  4632.4  492.82  4653.9  490.56  4753.5  487.72  4789.7  484.51    4965  481.09
  4978.2  477.07  4986.1  476.51    4992  470.03  5004.9  467.41  5005.2  466.91
  5009.5  467.41    5014  475.38  5033.1  476.89  5049.7  479.96  5064.5   480.5
  5073.6  475.73  5079.6  479.54  5100.7   481.3  5203.5  482.77  5297.8  485.32
  5347.9  486.14  5396.7  489.06  5412.5  488.66  5499.4  494.69  5700.8  505.05
#Mann= 7 ,-1 , 0
  4297.9     .07       0  5004.9     .05       0  5009.5     .07       0
  5033.1     .12       0  5203.5     .07       0  5297.8     .12       0
  5412.5     .07       0
Bank Sta=5004.9,5009.5
XS Rating Curve= 0 ,0
Exp/Cntr=0.3,0.1

Type RM Length L Ch R = 1 ,2141    ,312,312,312
BEGIN DESCRIPTION:
B20116
END DESCRIPTION:
XS GIS Cut Line= 3
      2332332.98     13732823.51      2332853.58     13732314.93
      2333329.22     13731879.26
#Sta/Elev= 30
  4229.5  501.79    4541  488.08  4576.4  487.71  4583.4  484.81  4590.5  484.34
  4597.5  481.73  4625.8  476.97    4633  477.46    4640  475.57  4668.3  476.46
  4703.7  482.37    4732  489.67  4746.1  491.07  4760.3  484.93  4774.4  481.11
  4960.9  477.85  4979.5  473.08  4993.7  471.62  5005.5  465.82  5005.8  465.32
  5010.2  465.82  5014.6  466.87  5019.8  471.42  5028.8  476.44    5043  478.35
  5094.9  479.77  5161.1  481.63  5319.2  488.03  5521.2  499.96  5602.3  505.33
#Mann= 7 ,-1 , 0
  4229.5     .07       0  5005.5     .05       0  5010.2     .07       0
  5019.8     .12       0  5094.9     .07       0  5161.1     .12       0
  5521.2     .07       0
Bank Sta=5005.5,5010.2
XS Rating Curve= 0 ,0
Exp/Cntr=0.3,0.1

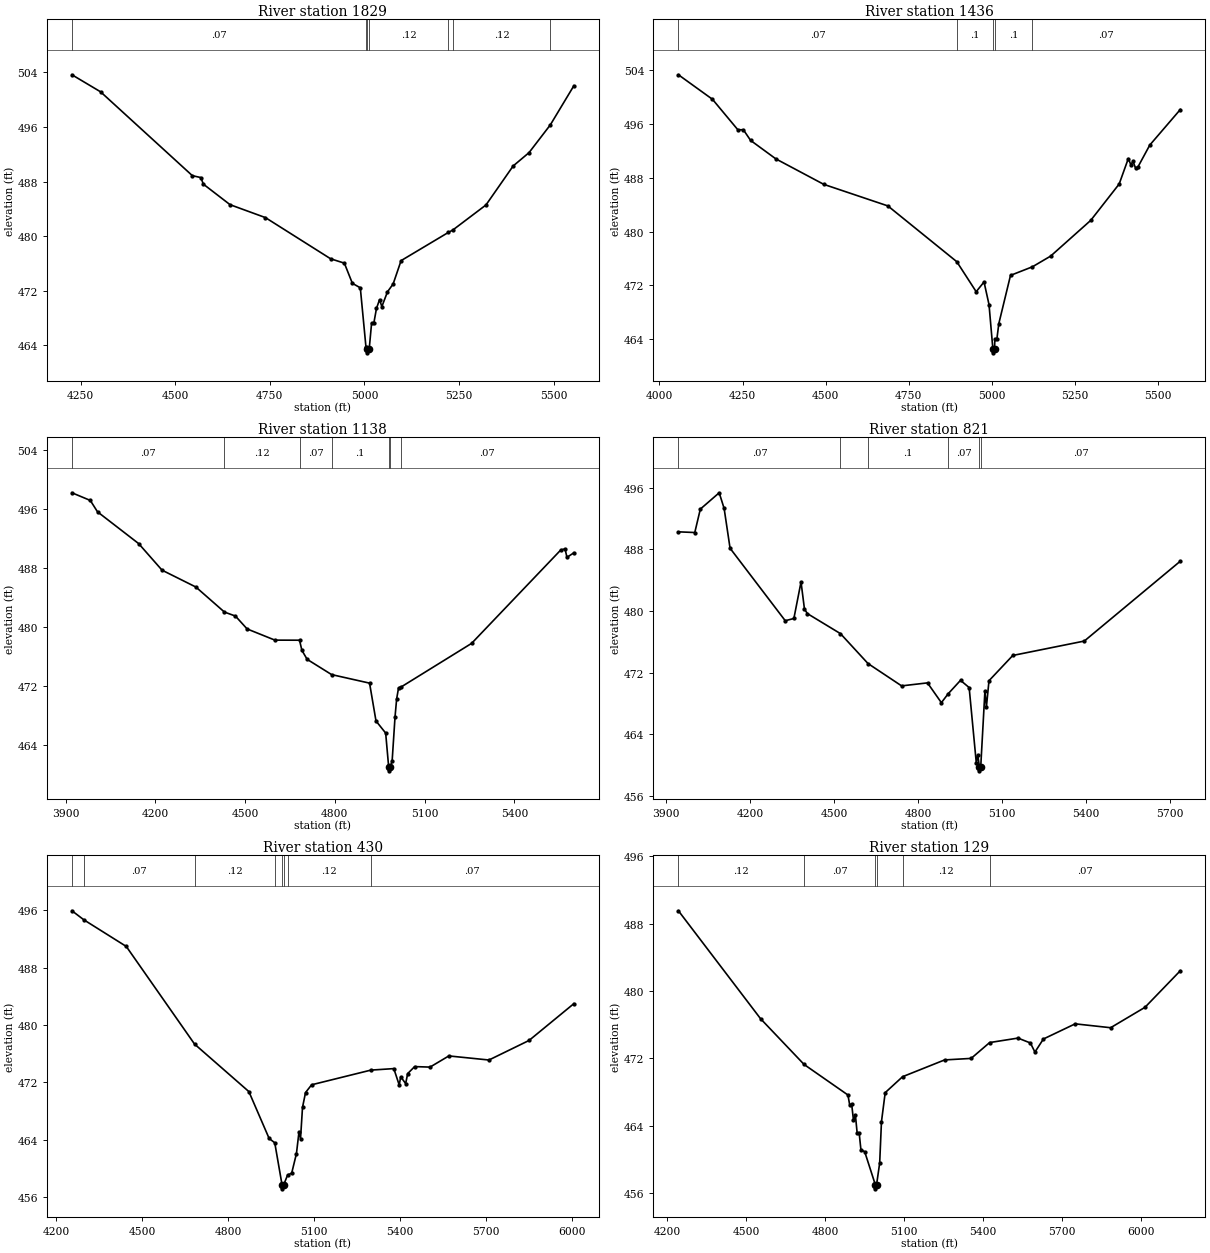
Type RM Length L Ch R = 1 ,1829    ,393,393,393
BEGIN DESCRIPTION:
B20115
END DESCRIPTION:
XS GIS Cut Line= 3
      2332545.18     13732971.75      2333049.82     13732583.25
      2333438.31     13732014.54
#Sta/Elev= 30
  4227.4  503.63  4302.9  501.14  4545.4  488.86  4567.9  488.58  4574.4  487.62
    4645  484.61  4738.4  482.72  4910.6  476.69  4946.9  476.05    4968   473.1
    4989  472.44  5003.8  463.84  5007.6  463.42  5007.9  462.92  5012.4  463.42
  5018.8  467.27  5024.9  467.33  5031.7  469.42  5039.8  470.71  5045.9  469.69
  5060.8  471.86  5075.7     473  5096.7  476.42  5221.3  480.54  5233.3   480.9
  5320.9  484.57  5392.7  490.28  5434.6  492.23  5490.8  496.29    5553  502.02
#Mann= 7 ,-1 , 0
  4227.4     .07       0  5003.8     .12       0  5007.6     .05       0
  5012.4     .12       0  5221.3     .07       0  5233.3     .12       0
  5490.8     .07       0
Bank Sta=5007.6,5012.4
XS Rating Curve= 0 ,0
Exp/Cntr=0.3,0.1

Type RM Length L Ch R = 1 ,1436    ,298,298,298
BEGIN DESCRIPTION:
B20114
END DESCRIPTION:
XS GIS Cut Line= 3
       2332565.2     13732999.77       2333442.3     13732627.31
      2333806.77     13732206.77
#Sta/Elev= 30
  4057.2  503.36  4159.6  499.71    4236  495.17  4252.5  495.18  4274.3  493.59
  4350.3  490.84  4494.3  487.05  4687.1  483.84  4894.3  475.54  4952.7  471.07
  4976.3  472.52  4991.3  469.15    5003  462.47  5003.4  461.97  5007.8  462.47
  5008.9  464.02  5014.9  464.02  5020.8  466.33  5055.9   473.5  5121.9  474.78
  5176.6  476.37  5297.2  481.69  5382.7   487.1  5410.2  490.89  5417.8  489.97
  5424.4  490.47  5432.1  489.45  5438.7   489.6  5474.8   492.9  5566.6  498.19
#Mann= 5 ,-1 , 0
  4057.2     .07       0  4894.3      .1       0    5003     .05       0
  5007.8      .1       0  5121.9     .07       0
Bank Sta=5003,5007.8
XS Rating Curve= 0 ,0
Exp/Cntr=0.3,0.1

Type RM Length L Ch R = 1 ,1138    ,317,317,317
BEGIN DESCRIPTION:
B20113
END DESCRIPTION:
XS GIS Cut Line= 3
      2332621.32     13733232.03      2333814.75     13732755.46
      2334067.03     13732455.12
#Sta/Elev= 30
  3921.5  498.25  3982.8  497.21    4007  495.66  4144.4  491.35  4222.6  487.74
  4335.7  485.45  4431.1  482.05  4467.8  481.51  4506.9  479.76  4599.8  478.24
    4682  478.23    4690  476.85  4707.5  475.63  4789.2  473.56  4916.1   472.4
  4937.6  467.26  4969.9  465.62    4980  460.99  4980.3  460.49  4984.8  460.99
  4991.5  461.81  5001.2  467.82  5006.6  470.26    5013  471.76  5020.8  471.86
  5257.1   477.8    5555  490.48  5569.3  490.63  5575.8  489.48  5598.8   490.1
#Mann= 7 ,-1 , 0
  3921.5     .07       0  4431.1     .12       0    4682     .07       0
  4789.2      .1       0    4980     .05       0  4984.8      .1       0
  5020.8     .07       0
Bank Sta=4980,4984.8
XS Rating Curve= 0 ,0
Exp/Cntr=0.3,0.1

Type RM Length L Ch R = 1 ,821     ,391,391,391
BEGIN DESCRIPTION:
B20112
END DESCRIPTION:
XS GIS Cut Line= 3
      2332681.39     13733488.34       2333858.8     13733067.84
      2334066.46     13732568.66
#Sta/Elev= 30
  3944.8  490.29  4003.2   490.2    4023  493.24  4090.3  495.36  4107.9  493.33
  4129.1  488.16    4326  478.75  4356.8  479.04  4382.3  483.78  4394.6  480.25
  4405.2  479.67  4523.1  477.07  4621.3  473.19  4741.2  470.29  4833.6  470.68
  4883.1  468.11  4907.2  469.26  4951.4  471.01  4982.2  470.07  5007.7  460.29
    5013  461.35  5018.7  459.76  5019.1  459.26  5023.5  459.76  5038.5  469.65
  5043.8  467.57    5053  470.96  5137.9  474.24  5393.1  476.11  5735.7  486.48
#Mann= 6 ,-1 , 0
  3944.8     .07       0  4523.1     .12       0  4621.3      .1       0
  4907.2     .07       0  5018.7     .05       0  5023.5     .07       0
Bank Sta=5018.7,5023.5
XS Rating Curve= 0 ,0
Exp/Cntr=0.3,0.1

Type RM Length L Ch R = 1 ,430     ,301,301,301
BEGIN DESCRIPTION:
B20111
END DESCRIPTION:
XS GIS Cut Line= 3
      2332825.59     13733724.62      2333746.67     13733400.24
      2334034.89     13732679.68
#Sta/Elev= 30
  4254.7  495.96  4296.2   494.7  4444.4  490.98  4682.9  477.34  4872.5  470.71
  4943.2  464.17  4962.9  463.56  4988.6  457.63  4988.9  457.13  4993.5  457.63
  5007.6  459.05    5022  459.32  5038.6  462.05  5047.6  465.12  5052.9  464.15
  5059.8  468.51  5070.4  470.58  5091.6  471.66  5298.5  473.71  5378.6  473.92
  5397.4  471.64  5402.8  472.77    5420  471.83    5427  473.22  5451.3   474.2
  5505.1  474.13  5570.8  475.69  5710.8  475.12  5850.8  477.85  6007.3  482.99
#Mann= 8 ,-1 , 0
  4254.7     .12       0  4296.2     .07       0  4682.9     .12       0
  4962.9      .1       0  4988.6     .05       0  4993.5      .1       0
  5007.6     .12       0  5298.5     .07       0
Bank Sta=4988.6,4993.5
XS Rating Curve= 0 ,0
Exp/Cntr=0.3,0.1

Type RM Length L Ch R = 1 ,129     ,0,0,0
BEGIN DESCRIPTION:
B20110
END DESCRIPTION:
XS GIS Cut Line= 4
      2332893.61     13733868.81      2333510.38      13733856.8
      2333670.57     13733676.58      2334042.89     13732699.74
#Sta/Elev= 30
    4244  489.51  4555.5  476.71  4720.7  471.28  4886.9  467.66  4893.6  466.47
  4901.1  466.56  4907.8  464.69  4915.3  465.25    4922   463.1  4929.5  463.15
  4936.2  461.14  4950.4  460.94  4990.6  457.03    4991  456.53  4995.5  457.03
  5007.3   459.6    5014  464.48  5028.2  467.94  5094.1  469.83  5253.5  471.82
  5354.1     472  5424.3  473.88  5531.8  474.41  5578.8  473.83    5596  472.75
  5628.1   474.3  5748.7   476.1  5883.1  475.64  6013.4  478.06  6147.4   482.4
#Mann= 6 ,-1 , 0
    4244     .12       0  4720.7     .07       0  4990.6     .05       0
  4995.5     .07       0  5094.1     .12       0  5424.3     .07       0
Bank Sta=4990.6,4995.5
XS Rating Curve= 0 ,0
Exp/Cntr=0.3,0.1

Chan Stop Cuts=-1
Use User Specified Reach Order=0
Composite Channel Slope=5