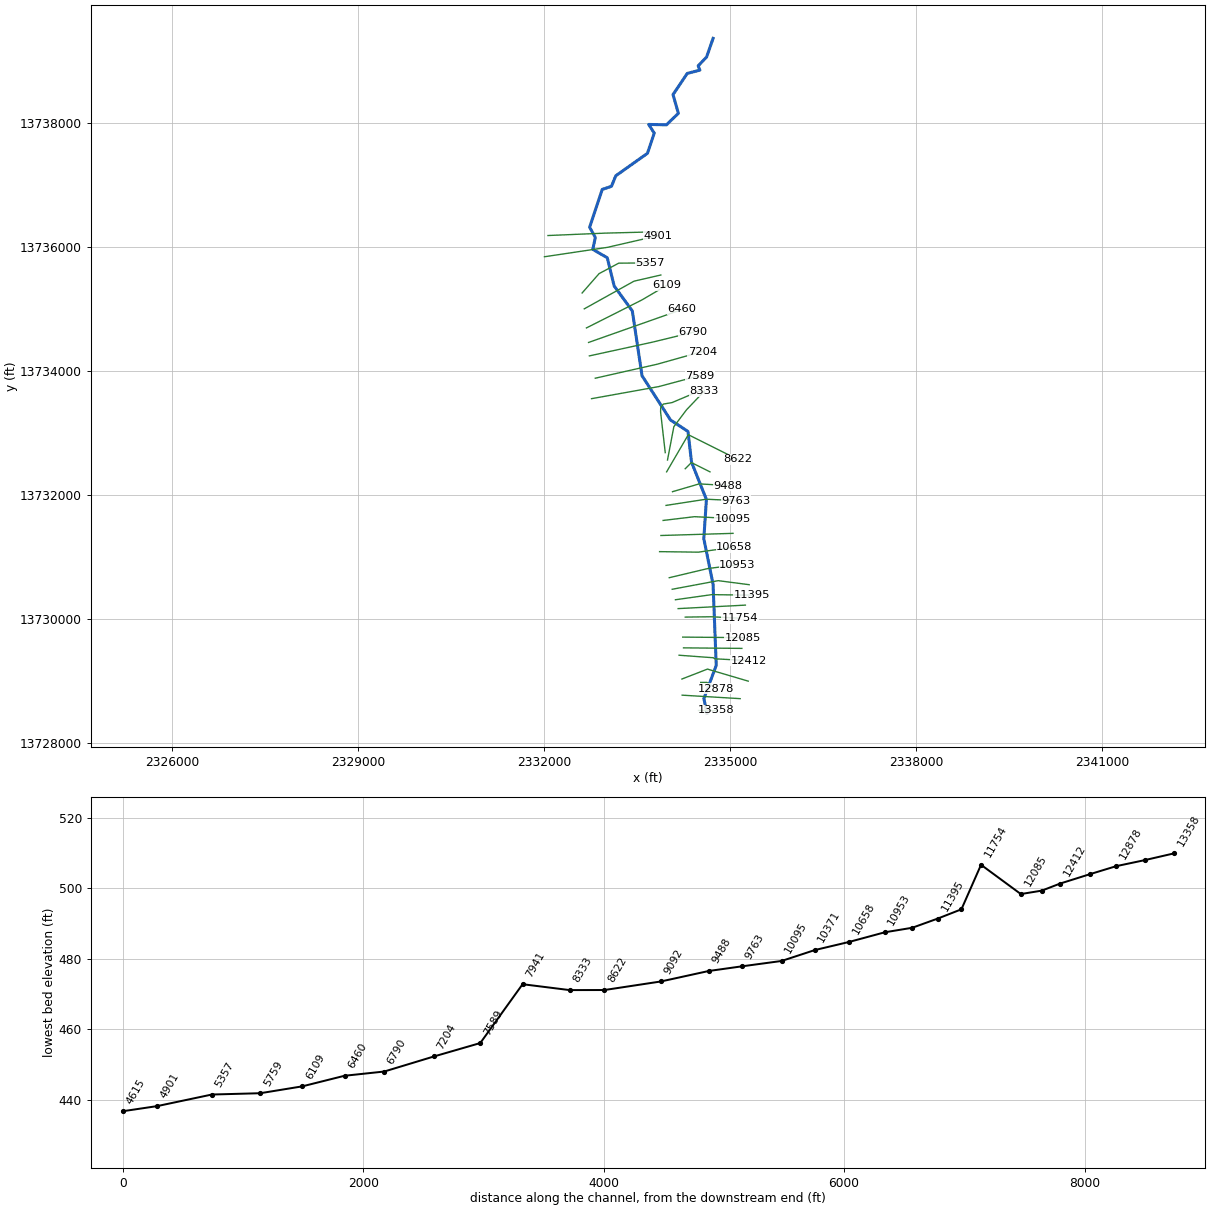
--- POLECAT CREEK.prj (project) ---

Proj Title=POLECAT CREEK Base Level Engineering
Current Plan=p01
Default Exp/Contr=0.3,0.1
English Units
Geom File=g01
Flow File=f01
Plan File=p01
Y Axis Title=Elevation
X Axis Title(PF)=Main Channel Distance
X Axis Title(XS)=Station
BEGIN DESCRIPTION:
POLECAT CREEK
END DESCRIPTION:
DSS Export Rating Curves= 0
DSS Export Rating Curve Sorted= 0
DSS Export Volume Flow Curves= 0
DXF OffsetX= 0
DXF OffsetY= 0
DXF ScaleX= 1
DXF ScaleY= 10

--- POLECAT CREEK.p01 (plan) ---

Plan Title=Multiple Run
Short Identifier=Multiple
Geom File=g01
Flow File=f01
Subcritical Flow
K Sum by GR= 0
Std Step Tol= 0.01
Critical Tol= 0.01
Num of Std Step Trials= 20
Max Error Tol= 0.3
Flow Tol Ratio= 0.001
Split Flow NTrial= 30
Split Flow Tol= 0.02
Split Flow Ratio= 0.02
Log Output Level= 0
Friction Slope Method= 1
Unsteady Friction Slope Method= 2
Unsteady Bridges Friction Slope Method= 1
Parabolic Critical Depth
Global Vel Dist=  1 , 1 , 1
Global Log Level= 0
CheckData=True
Encroach Param= -1, 0, 0, 0
BEGIN DESCRIPTION:
Multiple Run
END DESCRIPTION:

--- POLECAT CREEK.f01 (steady flow) ---

Flow Title=Multiple
Number of Profiles=7
Profile Names=10-year,25-year,50-year,1pct_min,100-year,1pct_plu,500-year
River Rch & RM= POLECAT CREEK,Reach-1,13358
    1079    1828    2538    1707    3406    6797    6081
River Rch & RM= POLECAT CREEK,Reach-1,12412
    1098    1852    2563    1717    3426    6836    6069
River Rch & RM= POLECAT CREEK,Reach-1,7589
    1989    3472    4921    3371    6726   13421   12463
River Rch & RM= POLECAT CREEK,Reach-1,4901
    2413    4252    6063    4175    8331   16623   15607
River Rch & RM= POLECAT CREEK,Reach-1,4026
    2356    4127    5859    4017    8015   15992   14879
Boundary for River Rch & Prof#=POLECAT CREEK,Reach-1,1
Up Type=0
Dn Type=3
Dn Slope=0.005
Boundary for River Rch & Prof#=POLECAT CREEK,Reach-1,2
Up Type=0
Dn Type=3
Dn Slope=0.005
Boundary for River Rch & Prof#=POLECAT CREEK,Reach-1,3
Up Type=0
Dn Type=3
Dn Slope=0.005
Boundary for River Rch & Prof#=POLECAT CREEK,Reach-1,4
Up Type=0
Dn Type=3
Dn Slope=0.005
Boundary for River Rch & Prof#=POLECAT CREEK,Reach-1,5
Up Type=0
Dn Type=3
Dn Slope=0.005
Boundary for River Rch & Prof#=POLECAT CREEK,Reach-1,6
Up Type=0
Dn Type=3
Dn Slope=0.005
Boundary for River Rch & Prof#=POLECAT CREEK,Reach-1,7
Up Type=0
Dn Type=3
Dn Slope=0.005

--- POLECAT CREEK.g01 (geometry) ---

Geom Title=Existing Conditions

River Reach=POLECAT CREEK,Reach-1
Reach XY= 30
      2334625.00     13728475.00      2334576.21     13728714.49
      2334775.41     13729250.00      2334724.48     13730559.78
      2334575.07     13731295.03      2334616.92     13731928.30
      2334377.07     13732530.86      2334319.48     13733027.44
      2334038.47     13733211.43      2333578.29     13733926.36
      2333421.45     13734973.53      2333128.62     13735376.50
      2333017.30     13735831.48      2332784.01     13735967.98
      2332824.51     13736159.78      2332732.53     13736324.99
      2332935.63     13736935.05      2333085.16     13736985.37
      2333154.43     13737155.41      2333665.70     13737518.31
      2333775.38     13737845.27      2333684.91     13737984.80
      2333973.50     13737978.46      2334163.90     13738164.94
      2334078.00     13738466.65      2334308.24     13738808.57
      2334511.53     13738861.24      2334484.31     13738931.66
      2334619.53     13739072.55      2334725.00     13739375.00

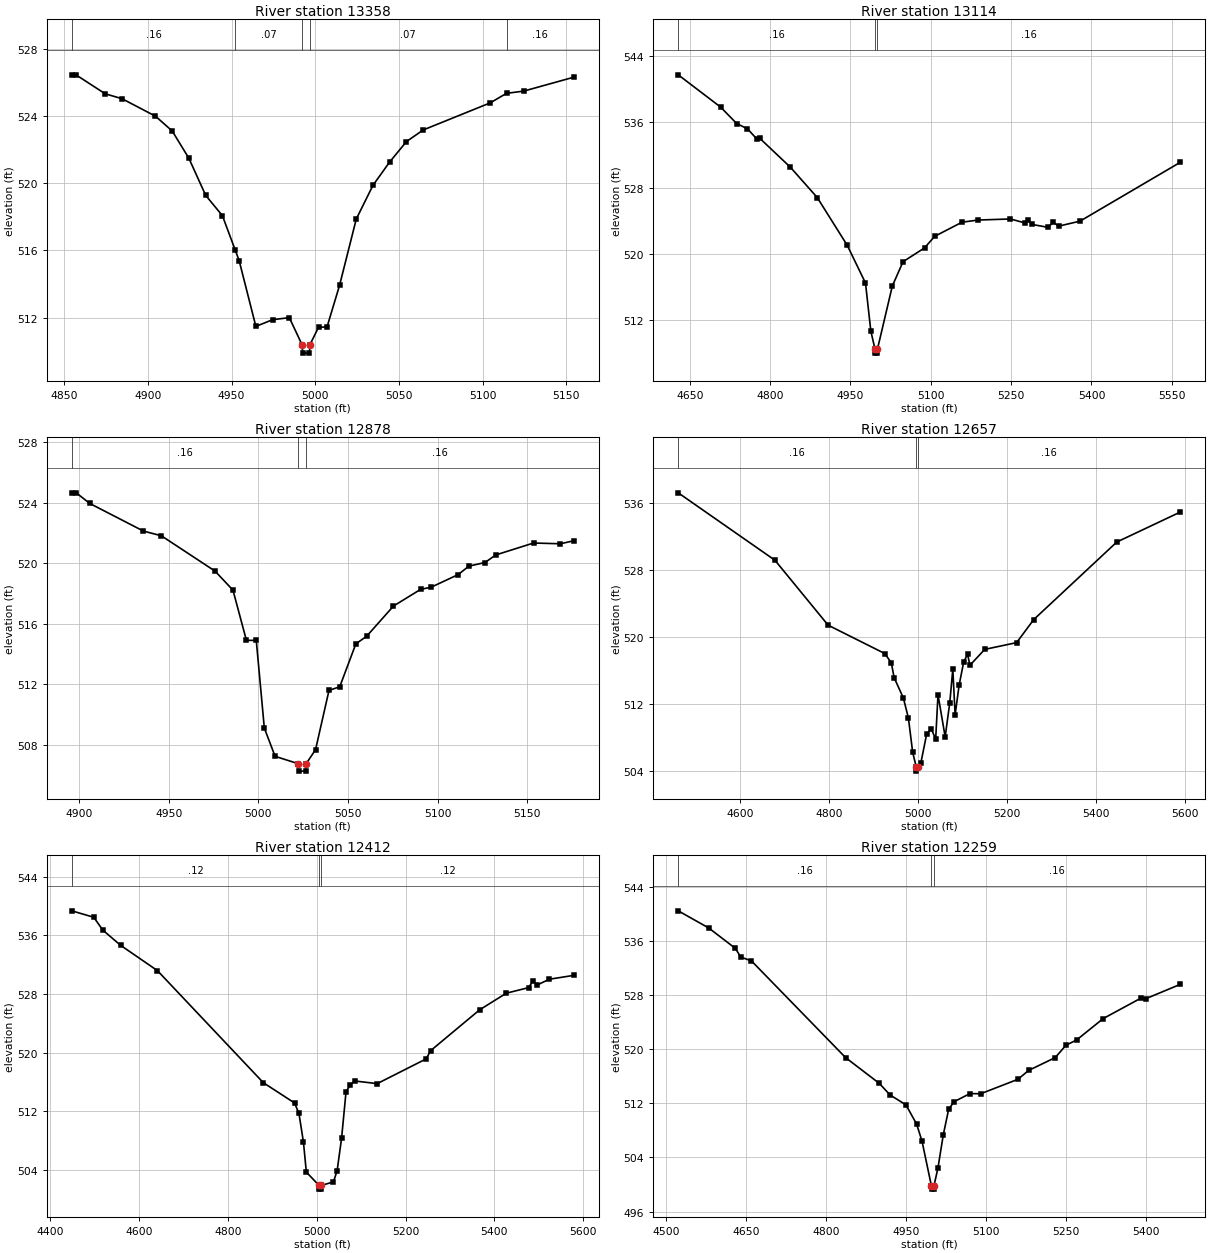
Type RM Length L Ch R = 1,13358,244,244,244
BEGIN DESCRIPTION:
POLECAT CREEK 27.0
END DESCRIPTION:
XS GIS Cut Line= 3
      2334475.03     13728525.00      2334625.00     13728525.00
      2334775.03     13728525.00
#Sta/Elev= 30
  4854.5  526.44  4857.0  526.44  4874.5  525.31  4884.5  525.02  4904.5  523.98
  4914.5  523.10  4924.5  521.47  4934.5  519.27  4944.5  518.06  4952.1  516.03
  4954.5  515.39  4964.5  511.47  4974.5  511.87  4984.5  511.99  4992.1  510.38
  4992.5  509.88  4996.5  509.88  4996.8  510.38  5002.0  511.43  5007.0  511.43
  5014.5  513.91  5024.5  517.86  5034.5  519.87  5044.5  521.26  5054.5  522.47
  5064.5  523.16  5104.5  524.77  5114.3  525.34  5124.5  525.47  5154.5  526.30
#Mann=5,-1,0
  4854.5    0.16       0  4952.1    0.07       0  4992.1    0.07       0
  4996.8    0.07       0  5114.3    0.16       0
Bank Sta=4992.1,4996.8
Exp/Cntr=0.3,0.1

Type RM Length L Ch R = 1,13114,236,236,236
BEGIN DESCRIPTION:
B20100
END DESCRIPTION:
XS GIS Cut Line= 2
      2334226.02     13728769.02      2335161.72     13728712.70
#Sta/Elev= 30
  4628.5  541.69  4707.6  537.78  4737.7  535.78  4757.7  535.15  4775.7  533.88
  4780.7  534.00  4837.9  530.49  4888.0  526.82  4944.1  521.02  4978.1  516.46
  4988.1  510.63  4995.8  508.46  4996.2  507.96  5000.2  507.96  5000.5  508.46
  5028.2  516.09  5048.2  519.04  5088.3  520.71  5107.4  522.12  5158.4  523.83
  5188.5  524.09  5248.6  524.22  5275.8  523.74  5280.8  524.15  5288.7  523.56
  5318.7  523.21  5328.7  523.81  5338.8  523.35  5378.8  523.96  5565.9  531.09
#Mann=3,-1,0
  4628.5    0.16       0  4995.8    0.07       0  5000.5    0.16       0
Bank Sta=4995.8,5000.5
Exp/Cntr=0.3,0.1

Type RM Length L Ch R = 1,12878,221,221,221
BEGIN DESCRIPTION:
POLECAT CREEK 26.0
END DESCRIPTION:
XS GIS Cut Line= 3
      2334524.99     13728975.00      2334625.00     13728975.00
      2334775.01     13728874.99
#Sta/Elev= 30
  4895.8  524.67  4898.3  524.67  4905.8  523.97  4935.8  522.14  4945.8  521.83
  4975.8  519.49  4985.8  518.23  4993.3  514.91  4998.8  514.91  5003.3  509.11
  5009.3  507.24  5022.0  506.76  5022.4  506.26  5026.4  506.26  5026.7  506.76
  5031.9  507.68  5039.4  511.60  5045.4  511.84  5054.4  514.68  5060.4  515.18
  5075.4  517.18  5090.5  518.28  5096.5  518.43  5111.5  519.26  5117.5  519.82
  5126.5  520.06  5132.5  520.56  5153.6  521.35  5168.6  521.30  5176.1  521.50
#Mann=3,-1,0
  4895.8    0.16       0  5022.0    0.07       0  5026.7    0.16       0
Bank Sta=5022,5026.7
Exp/Cntr=0.3,0.1

Type RM Length L Ch R = 1,12657,245,245,245
BEGIN DESCRIPTION:
B20099
END DESCRIPTION:
XS GIS Cut Line= 3
      2334221.68     13729029.43      2334634.03     13729190.02
      2335291.88     13728995.26
#Sta/Elev= 30
  4461.1  537.27  4678.5  529.20  4798.0  521.43  4925.5  518.03  4940.0  516.93
  4946.4  515.15  4967.2  512.71  4978.5  510.31  4988.1  506.21  4996.1  504.46
  4996.5  503.96  5000.8  504.46  5006.6  504.97  5019.4  508.36  5029.8  509.03
  5039.8  507.79  5045.0  513.12  5061.1  508.06  5071.5  512.15  5078.3  516.17
  5083.5  510.68  5092.4  514.22  5102.8  517.04  5111.5  517.94  5116.8  516.63
  5150.0  518.53  5221.7  519.34  5260.2  522.10  5446.9  531.38  5589.7  534.97
#Mann=3,-1,0
  4461.1    0.16       0  4996.1    0.07       0  5000.8    0.16       0
Bank Sta=4996.1,5000.8
Exp/Cntr=0.3,0.1

Type RM Length L Ch R = 1,12412,153,153,153
BEGIN DESCRIPTION:
POLECAT CREEK 25.0
END DESCRIPTION:
XS GIS Cut Line= 5
      2334175.26     13729413.98      2334703.04     13729375.00
      2334725.00     13729375.00      2334753.50     13729356.00
      2335296.80     13729327.18
#Sta/Elev= 30
  4449.2  539.37  4498.7  538.49  4519.1  536.73  4559.2  534.65  4641.8  531.20
  4880.1  515.88  4950.3  513.11  4960.3  511.67  4970.4  507.75  4976.9  503.66
  5005.5  501.83  5005.8  501.33  5009.9  501.33  5010.3  501.83  5037.9  502.32
  5046.2  503.86  5056.2  508.30  5066.2  514.64  5076.2  515.63  5086.2  516.11
  5136.3  515.75  5246.4  519.13  5256.4  520.25  5366.6  525.83  5426.7  528.11
  5476.8  528.87  5486.8  529.78  5496.8  529.25  5523.6  530.02  5578.7  530.55
#Mann=3,-1,0
  4449.2    0.12       0  5005.5    0.05       0  5010.3    0.12       0
Bank Sta=5005.5,5010.3
Exp/Cntr=0.3,0.1

Type RM Length L Ch R = 1,12259,174,174,174
BEGIN DESCRIPTION:
B20098
END DESCRIPTION:
XS GIS Cut Line= 2
      2334247.71     13729532.91      2335189.57     13729524.23
#Sta/Elev= 30
  4522.7  540.47  4580.0  537.93  4630.0  534.91  4640.0  533.63  4660.0  533.07
  4836.6  518.77  4900.0  514.95  4920.0  513.25  4950.0  511.77  4970.0  508.92
  4980.0  506.42  4997.6  499.82  4998.0  499.32  5002.1  499.32  5002.5  499.82
  5010.0  502.48  5020.0  507.38  5030.0  511.12  5040.0  512.24  5070.0  513.45
  5090.0  513.42  5160.0  515.56  5180.0  516.87  5230.0  518.77  5250.0  520.59
  5270.0  521.37  5320.0  524.54  5390.0  527.53  5400.0  527.48  5464.6  529.60
#Mann=3,-1,0
  4522.7    0.16       0  4997.6    0.07       0  5002.5    0.16       0
Bank Sta=4997.6,5002.5
Exp/Cntr=0.3,0.1

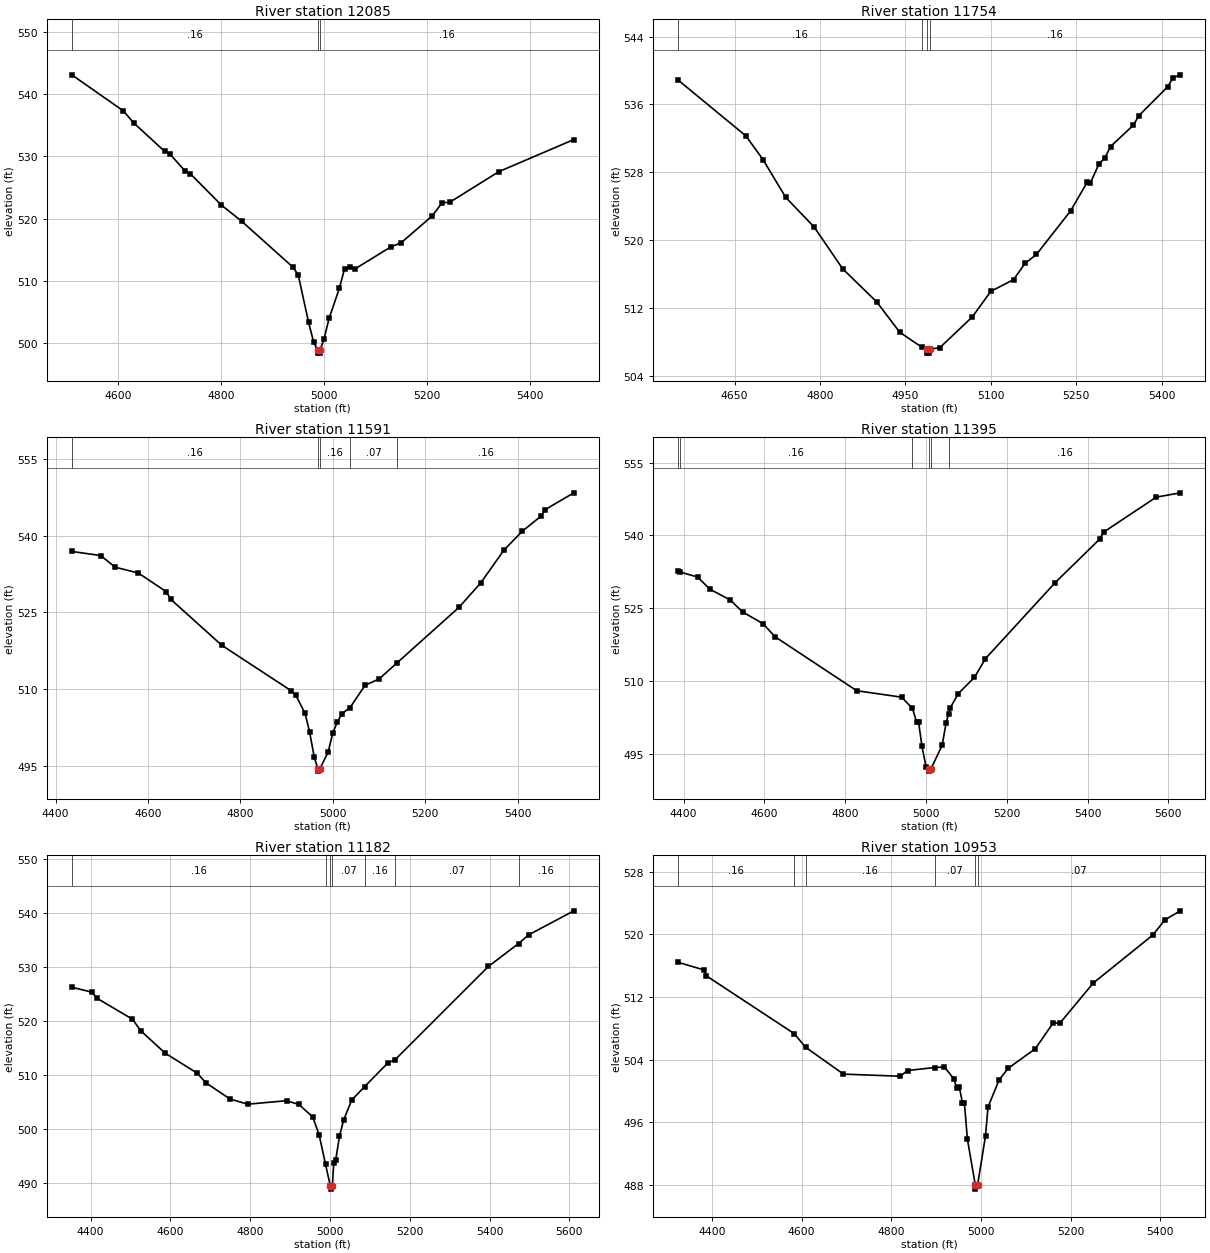
Type RM Length L Ch R = 1,12085,331,331,331
BEGIN DESCRIPTION:
B20096
END DESCRIPTION:
XS GIS Cut Line= 2
      2334234.71     13729706.52      2335210.68     13729697.84
#Sta/Elev= 30
  4509.7  543.11  4610.0  537.31  4630.0  535.38  4690.0  530.82  4700.0  530.43
  4730.0  527.63  4740.0  527.22  4800.0  522.20  4840.0  519.56  4940.0  512.15
  4950.0  510.90  4970.0  503.32  4980.0  500.09  4987.6  498.85  4987.9  498.35
  4992.1  498.35  4992.5  498.85  5000.0  500.63  5010.0  503.95  5030.0  508.81
  5040.0  511.93  5050.0  512.25  5060.0  511.88  5130.0  515.44  5150.0  516.10
  5210.0  520.39  5230.0  522.57  5244.0  522.59  5340.0  527.54  5485.7  532.70
#Mann=3,-1,0
  4509.7    0.16       0  4987.6    0.07       0  4992.5    0.16       0
Bank Sta=4987.6,4992.5
Exp/Cntr=0.3,0.1

Type RM Length L Ch R = 1,11754,163,163,163
BEGIN DESCRIPTION:
B20094
END DESCRIPTION:
XS GIS Cut Line= 3
      2334276.07     13730029.72      2334694.03     13730034.97
      2335157.48     13730012.23
#Sta/Elev= 30
  4551.0  538.86  4669.9  532.28  4699.9  529.49  4739.9  525.02  4789.9  521.52
  4839.9  516.60  4900.0  512.67  4940.0  509.12  4978.5  507.37  4987.5  507.15
  4987.9  506.65  4992.1  506.65  4992.4  507.15  5010.0  507.26  5067.7  510.93
  5100.1  513.94  5140.2  515.33  5160.2  517.24  5180.2  518.29  5240.3  523.44
  5269.9  526.87  5274.9  526.71  5290.3  529.00  5300.4  529.67  5310.4  531.03
  5350.4  533.54  5360.4  534.69  5410.5  538.06  5420.5  539.16  5433.0  539.49
#Mann=4,-1,0
  4551.0    0.16       0  4978.5    0.07       0  4987.5    0.07       0
  4992.4    0.16       0
Bank Sta=4987.5,4992.4
Exp/Cntr=0.3,0.1

Type RM Length L Ch R = 1,11591,196,196,196
BEGIN DESCRIPTION:
B20101
END DESCRIPTION:
XS GIS Cut Line= 2
      2334160.97     13730166.59      2335246.00     13730223.01
#Sta/Elev= 30
  4435.2  536.91  4497.6  536.11  4529.4  533.83  4579.4  532.69  4639.5  529.06
  4649.5  527.56  4759.7  518.60  4909.9  509.73  4919.9  508.86  4939.9  505.33
  4949.9  501.67  4959.9  496.77  4967.5  494.53  4967.9  494.03  4972.4  494.53
  4990.0  497.75  5000.0  501.47  5010.0  503.66  5020.0  505.22  5037.3  506.43
  5070.1  510.80  5100.1  512.01  5138.8  515.14  5273.3  526.01  5320.4  530.79
  5370.5  537.18  5410.5  540.88  5450.6  543.79  5459.7  545.07  5521.7  548.35
#Mann=5,-1,0
  4435.2    0.16       0  4967.5    0.07       0  4972.4    0.16       0
  5037.3    0.07       0  5138.8    0.16       0
Bank Sta=4967.5,4972.4
Exp/Cntr=0.3,0.1

Type RM Length L Ch R = 1,11395,213,213,213
BEGIN DESCRIPTION:
B20095
END DESCRIPTION:
XS GIS Cut Line= 3
      2334117.49     13730309.81      2334703.47     13730392.28
      2335354.56     13730383.60
#Sta/Elev= 30
  4386.7  532.73  4391.5  532.45  4434.7  531.43  4465.0  528.92  4515.5  526.69
  4545.8  524.24  4596.3  521.83  4626.6  519.10  4828.5  507.99  4939.6  506.66
  4966.6  504.34  4976.7  501.52  4981.7  501.52  4990.0  496.53  5000.0  492.35
  5007.5  491.91  5007.9  491.41  5012.4  491.91  5040.0  496.72  5050.0  501.40
  5055.9  503.21  5060.0  504.46  5080.0  507.39  5120.0  510.74  5147.3  514.61
  5320.0  530.29  5430.0  539.25  5440.0  540.70  5570.0  547.90  5629.6  548.79
#Mann=6,-1,0
  4386.7    0.07       0  4391.5    0.16       0  4966.6    0.07       0
  5007.5    0.07       0  5012.4    0.07       0  5055.9    0.16       0
Bank Sta=5007.5,5012.4
Exp/Cntr=0.3,0.1

Type RM Length L Ch R = 1,11182,229,229,229
BEGIN DESCRIPTION:
B20097
END DESCRIPTION:
XS GIS Cut Line= 3
      2334065.49     13730479.09      2334807.64     13730617.98
      2335306.78     13730552.87
#Sta/Elev= 30
  4352.7  526.23  4403.1  525.32  4415.2  524.22  4504.8  520.30  4525.5  518.17
  4586.2  514.04  4667.6  510.26  4688.4  508.54  4749.0  505.51  4793.6  504.54
  4891.4  505.19  4921.9  504.49  4956.6  502.18  4972.8  498.83  4988.8  493.38
  5000.9  489.29  5001.2  488.79  5005.8  489.29  5009.2  493.59  5014.3  494.22
  5023.7  498.61  5033.8  501.52  5054.2  505.30  5086.7  507.80  5145.4  512.23
  5162.1  512.72  5396.9  530.08  5472.6  534.34  5498.4  535.97  5611.1  540.40
#Mann=7,-1,0
  4352.7    0.16       0  4988.8    0.07       0  5000.9    0.07       0
  5005.8    0.07       0  5086.7    0.16       0  5162.1    0.07       0
  5472.6    0.16       0
Bank Sta=5000.9,5005.8
Exp/Cntr=0.3,0.1

Type RM Length L Ch R = 1,10953,295,295,295
BEGIN DESCRIPTION:
B20093
END DESCRIPTION:
XS GIS Cut Line= 3
      2334017.69     13730665.71      2334638.37     13730813.29
      2335115.83     13730874.06
#Sta/Elev= 30
  4325.1  516.43  4382.9  515.45  4388.0  514.70  4584.0  507.32  4609.1  505.59
  4693.5  502.17  4820.0  501.90  4836.3  502.63  4896.7  503.01  4918.5  503.08
  4939.1  501.60  4946.5  500.34  4951.7  500.56  4958.8  498.45  4963.1  498.45
  4969.8  493.84  4987.5  488.00  4987.8  487.50  4992.4  488.00  5010.1  494.30
  5015.7  497.97  5040.3  501.42  5060.5  502.91  5121.0  505.40  5161.3  508.73
  5175.5  508.64  5250.4  513.79  5383.1  519.91  5410.3  521.86  5444.4  523.00
#Mann=6,-1,0
  4325.1    0.16       0  4584.0    0.07       0  4609.1    0.16       0
  4896.7    0.07       0  4987.5    0.07       0  4992.4    0.07       0
Bank Sta=4987.5,4992.4
Exp/Cntr=0.3,0.1

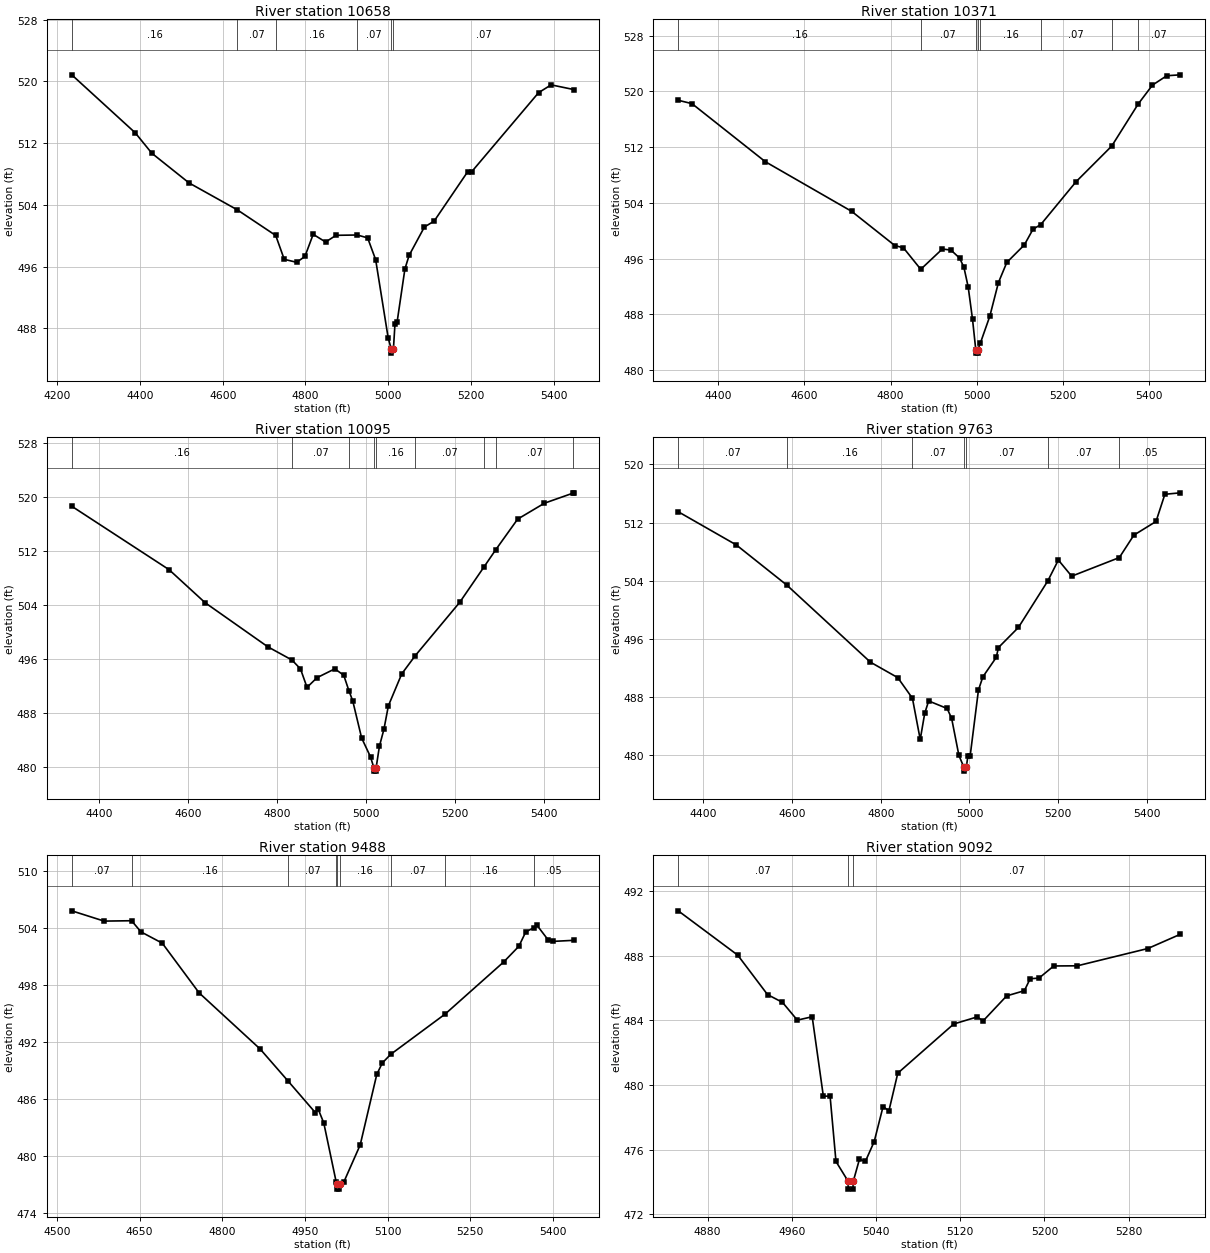
Type RM Length L Ch R = 1,10658,287,287,287
BEGIN DESCRIPTION:
B20092
END DESCRIPTION:
XS GIS Cut Line= 3
      2333861.48     13731086.73      2334486.46     13731078.05
      2335069.38     13731160.09
#Sta/Elev= 30
  4235.1  520.85  4388.6  513.33  4428.6  510.69  4518.6  506.84  4635.3  503.35
  4728.1  500.03  4748.7  496.94  4778.7  496.55  4798.7  497.31  4818.7  500.18
  4848.7  499.18  4874.0  500.05  4925.1  500.09  4950.3  499.72  4969.7  496.89
  5000.0  486.74  5007.6  485.28  5008.0  484.78  5012.6  485.28  5016.4  488.55
  5021.5  488.79  5040.4  495.68  5050.5  497.44  5087.6  501.13  5111.1  501.89
  5191.9  508.27  5202.0  508.30  5363.6  518.54  5393.9  519.55  5448.8  518.94
#Mann=6,-1,0
  4235.1    0.16       0  4635.3    0.07       0  4728.1    0.16       0
  4925.1    0.07       0  5007.6    0.07       0  5012.6    0.07       0
Bank Sta=5007.6,5012.6
Exp/Cntr=0.3,0.1

Type RM Length L Ch R = 1,10371,276,276,276
BEGIN DESCRIPTION:
B20091
END DESCRIPTION:
XS GIS Cut Line= 2
      2333883.19     13731347.14      2335046.37     13731381.87
#Sta/Elev= 30
  4308.0  518.72  4339.8  518.24  4509.9  509.91  4710.0  502.79  4810.0  497.89
  4830.0  497.56  4870.1  494.48  4920.1  497.39  4940.1  497.24  4960.1  496.09
  4970.1  494.78  4980.1  491.93  4990.1  487.31  4997.6  482.96  4998.0  482.46
  5002.2  482.46  5002.6  482.96  5008.0  483.85  5030.1  487.74  5050.1  492.57
  5069.6  495.47  5110.2  497.98  5130.2  500.22  5148.3  500.90  5230.2  507.05
  5312.8  512.16  5374.2  518.20  5407.2  520.90  5440.3  522.24  5471.7  522.37
#Mann=8,-1,0
  4308.0    0.16       0  4870.1    0.07       0  4997.6    0.07       0
  5002.6    0.07       0  5008.0    0.16       0  5148.3    0.07       0
  5312.8    0.16       0  5374.2    0.07       0
Bank Sta=4997.6,5002.6
Exp/Cntr=0.3,0.1

Type RM Length L Ch R = 1,10095,332,332,332
BEGIN DESCRIPTION:
B20090
END DESCRIPTION:
XS GIS Cut Line= 3
      2333917.90     13731590.20      2334425.69     13731650.96
      2335041.03     13731620.63
#Sta/Elev= 30
  4339.4  518.65  4558.0  509.24  4638.6  504.36  4779.6  497.81  4833.8  495.85
  4853.0  494.53  4867.7  491.79  4890.2  493.23  4930.2  494.54  4950.2  493.58
  4961.7  491.31  4970.3  489.80  4990.3  484.29  5010.3  481.48  5017.8  479.87
  5018.2  479.37  5022.5  479.37  5022.9  479.87  5030.3  483.07  5040.4  485.58
  5050.4  489.06  5080.4  493.79  5110.6  496.48  5210.6  504.40  5264.9  509.63
  5291.5  512.20  5340.7  516.74  5400.8  519.10  5466.1  520.62  5466.9  520.64
#Mann=9,-1,0
  4339.4    0.16       0  4833.8    0.07       0  4961.7    0.16       0
  5017.8    0.07       0  5022.9    0.16       0  5110.6    0.07       0
  5264.9    0.16       0  5291.5    0.07       0  5466.1   0.035       0
Bank Sta=5017.8,5022.9
Exp/Cntr=0.3,0.1

Type RM Length L Ch R = 1,9763,275,275,275
BEGIN DESCRIPTION:
B20089
END DESCRIPTION:
XS GIS Cut Line= 3
      2333965.67     13731833.26      2334612.33     13731933.08
      2335089.72     13731911.38
#Sta/Elev= 30
  4343.3  513.50  4474.2  508.94  4588.2  503.41  4776.7  492.82  4838.4  490.69
  4871.4  487.86  4889.0  482.19  4899.1  485.78  4908.0  487.49  4949.7  486.45
  4959.8  485.10  4976.2  480.00  4987.7  478.34  4988.1  477.84  4992.8  478.34
  4996.4  479.88  5001.5  479.88  5020.3  488.99  5030.3  490.81  5060.4  493.47
  5065.4  494.83  5110.4  497.59  5176.5  503.97  5200.5  506.86  5230.5  504.64
  5338.0  507.20  5370.7  510.28  5420.7  512.16  5440.7  515.90  5475.5  516.10
#Mann=7,-1,0
  4343.3    0.07       0  4588.2    0.16       0  4871.4    0.07       0
  4987.7    0.07       0  4992.8    0.07       0  5176.5    0.07       0
  5338.0    0.05       0
Bank Sta=4987.7,4992.8
Exp/Cntr=0.3,0.1

Type RM Length L Ch R = 1,9488,396,396,396
BEGIN DESCRIPTION:
B20088
END DESCRIPTION:
XS GIS Cut Line= 3
      2334069.83     13732054.62      2334499.48     13732180.48
      2334961.95     13732154.54
#Sta/Elev= 30
  4527.0  505.77  4585.7  504.69  4635.5  504.73  4652.5  503.56  4691.2  502.37
  4758.0  497.15  4868.7  491.25  4920.0  487.84  4968.9  484.56  4973.9  484.95
  4984.2  483.48  5006.9  477.22  5007.7  477.02  5008.1  476.52  5012.4  476.52
  5012.8  477.02  5020.3  477.23  5050.3  481.17  5080.4  488.58  5090.4  489.78
  5105.7  490.69  5204.4  494.92  5310.7  500.40  5338.1  502.04  5350.8  503.57
  5364.9  503.97  5370.8  504.27  5390.9  502.74  5400.9  502.56  5437.9  502.67
#Mann=9,-1,0
  4527.0    0.07       0  4635.5    0.16       0  4920.0    0.07       0
  5006.9    0.16       0  5007.7    0.07       0  5012.8    0.16       0
  5105.7    0.07       0  5204.4    0.16       0  5364.9    0.05       0
Bank Sta=5007.7,5012.8
Exp/Cntr=0.3,0.1

Type RM Length L Ch R = 1,9092,470,470,470
BEGIN DESCRIPTION:
POLECAT CREEK 18.0
END DESCRIPTION:
XS GIS Cut Line= 3
      2334275.03     13732425.03      2334375.00     13732525.00
      2334675.01     13732375.00
#Sta/Elev= 30
  4852.2  490.77  4908.7  488.03  4937.0  485.59  4951.2  485.11  4965.3  484.01
  4979.4  484.22  4990.0  479.31  4996.4  479.31  5002.0  475.27  5013.4  474.06
  5013.7  473.56  5018.1  473.56  5018.5  474.06  5024.3  475.41  5029.9  475.27
  5038.3  476.50  5046.7  478.66  5052.3  478.41  5060.7  480.73  5113.8  483.77
  5136.1  484.21  5141.7  483.96  5164.1  485.51  5180.9  485.83  5186.4  486.57
  5194.8  486.61  5208.8  487.36  5231.2  487.37  5298.2  488.44  5329.0  489.32
#Mann=3,-1,0
  4852.2    0.07       0  5013.4    0.07       0  5018.5    0.07       0
Bank Sta=5013.4,5018.5
Exp/Cntr=0.3,0.1

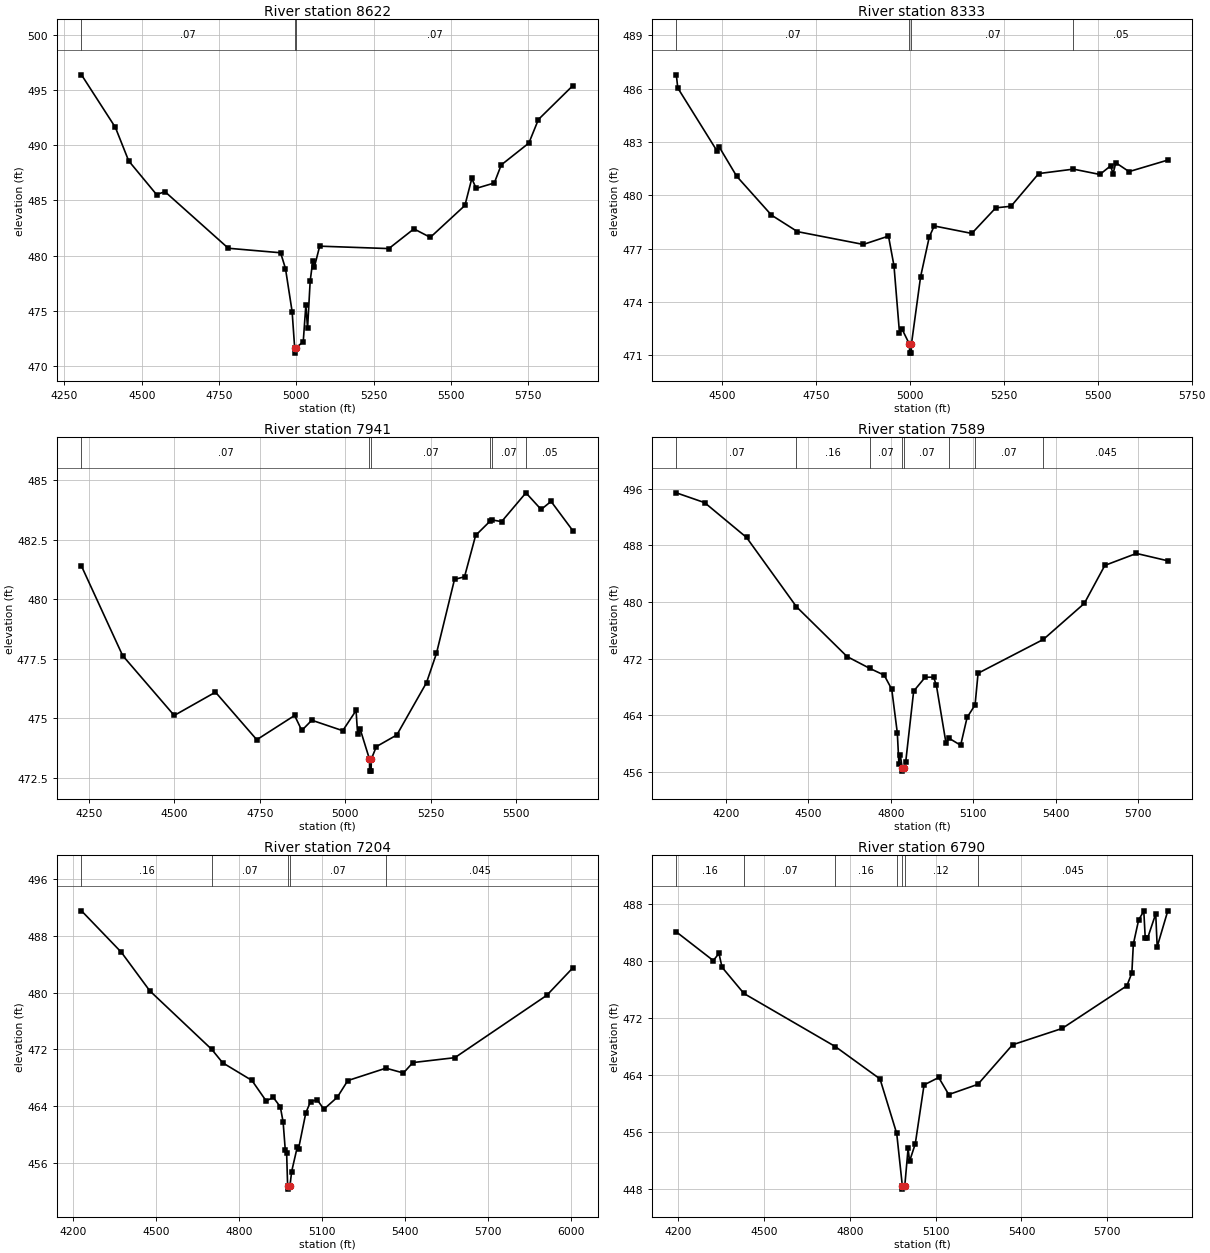
Type RM Length L Ch R = 1,8622,289,289,289
BEGIN DESCRIPTION:
POLECAT CREEK 17.0
END DESCRIPTION:
XS GIS Cut Line= 3
      2333974.99     13732374.98      2334325.00     13732975.00
      2335125.03     13732574.99
#Sta/Elev= 30
  4305.3  496.42  4414.9  491.64  4457.9  488.60  4548.0  485.54  4575.3  485.80
  4780.0  480.66  4949.1  480.25  4964.8  478.82  4986.3  474.91  4994.5  471.63
  4994.8  471.13  4999.6  471.63  5022.3  472.17  5030.7  475.49  5036.3  473.40
  5044.7  477.68  5053.0  479.48  5058.6  478.99  5075.4  480.85  5299.0  480.63
  5380.1  482.42  5433.2  481.65  5545.0  484.55  5567.3  487.00  5581.3  486.10
  5640.0  486.59  5662.4  488.23  5751.8  490.22  5782.6  492.36  5894.4  495.45
#Mann=3,-1,0
  4305.3    0.07       0  4994.5    0.07       0  4999.6    0.07       0
Bank Sta=4994.5,4999.6
Exp/Cntr=0.3,0.1

Type RM Length L Ch R = 1,8333,392,392,392
BEGIN DESCRIPTION:
B20087
END DESCRIPTION:
XS GIS Cut Line= 4
      2333989.26     13732566.23      2334091.47     13733104.08
      2334295.89     13733376.63      2334585.09     13733680.42
#Sta/Elev= 30
  4378.9  486.78  4382.8  486.04  4487.3  482.49  4492.4  482.74  4539.5  481.07
  4632.1  478.88  4701.3  477.95  4876.4  477.23  4943.4  477.70  4958.0  476.03
  4972.6  472.27  4978.8  472.49  4999.2  471.61  4999.6  471.11  5004.0  471.11
  5004.4  471.61  5028.8  475.41  5051.8  477.64  5065.0  478.27  5165.0  477.85
  5228.8  479.29  5269.4  479.38  5343.1  481.22  5435.3  481.47  5505.8  481.17
  5534.1  481.65  5541.0  481.22  5548.2  481.83  5583.4  481.33  5686.5  481.98
#Mann=4,-1,0
  4378.9    0.07       0  4999.2    0.07       0  5004.4    0.07       0
  5435.3    0.05       0
Bank Sta=4999.2,5004.4
Exp/Cntr=0.3,0.1

Type RM Length L Ch R = 1,7941,352,352,352
BEGIN DESCRIPTION:
B20086
END DESCRIPTION:
XS GIS Cut Line= 6
      2333952.76     13732685.50      2333877.32     13733345.00
      2333879.76     13733408.27      2333921.13     13733469.11
      2334062.27     13733493.44      2334517.32     13733685.68
#Sta/Elev= 30
  4228.2  481.40  4348.5  477.64  4499.5  475.12  4620.2  476.10  4741.0  474.10
  4851.7  475.12  4872.7  474.49  4902.0  474.92  4992.5  474.48  5031.5  475.33
  5036.0  474.35  5043.0  474.57  5070.8  473.28  5071.2  472.78  5075.6  472.78
  5076.0  473.28  5090.8  473.81  5150.7  474.30  5237.6  476.50  5266.7  477.73
  5319.5  480.84  5348.8  480.95  5381.3  482.69  5422.9  483.28  5429.5  483.34
  5457.3  483.27  5528.5  484.48  5572.9  483.78  5602.0  484.12  5666.1  482.88
#Mann=6,-1,0
  4228.2    0.07       0  5070.8    0.07       0  5076.0    0.07       0
  5422.9    0.05       0  5429.5    0.07       0  5528.5    0.05       0
Bank Sta=5070.8,5076
Exp/Cntr=0.3,0.1

Type RM Length L Ch R = 1,7589,385,385,385
BEGIN DESCRIPTION:
POLECAT CREEK 16.0
END DESCRIPTION:
XS GIS Cut Line= 3
      2332763.41     13733556.35      2333848.44     13733751.66
      2334511.29     13733929.28
#Sta/Elev= 30
  4019.8  495.44  4123.0  494.05  4275.4  489.13  4457.1  479.33  4641.2  472.29
  4723.7  470.62  4776.3  469.66  4803.8  467.67  4824.1  461.51  4829.9  457.15
  4835.0  458.37  4841.8  456.59  4842.2  456.09  4847.0  456.59  4854.6  457.36
  4883.6  467.40  4925.7  469.37  4956.2  469.37  4966.4  468.20  5001.0  460.12
  5012.7  460.73  5054.6  459.75  5078.1  463.68  5107.1  465.45  5118.0  469.93
  5355.9  474.72  5504.6  479.80  5579.4  485.18  5694.3  486.87  5808.5  485.83
#Mann=8,-1,0
  4019.8    0.07       0  4457.1    0.16       0  4723.7    0.07       0
  4841.8    0.07       0  4847.0    0.07       0  5012.7    0.16       0
  5107.1    0.07       0  5355.9   0.045       0
Bank Sta=4841.8,4847
Exp/Cntr=0.3,0.1

Type RM Length L Ch R = 1,7204,414,414,414
BEGIN DESCRIPTION:
B20085
END DESCRIPTION:
XS GIS Cut Line= 3
      2332824.13     13733887.07      2333822.39     13734112.77
      2334547.18     13734316.75
#Sta/Elev= 30
  4230.2  491.52  4374.5  485.67  4477.1  480.24  4701.2  471.98  4740.4  470.10
  4846.2  467.61  4897.5  464.73  4923.4  465.21  4948.8  463.90  4959.0  461.74
  4966.6  457.87  4971.7  457.33  4975.2  452.79  4975.7  452.29  4983.8  452.79
  4989.8  454.77  5009.8  458.17  5014.9  458.01  5041.0  463.04  5058.1  464.63
  5082.0  464.88  5106.4  463.56  5154.7  465.24  5192.7  467.59  5330.5  469.34
  5393.8  468.66  5427.9  470.13  5579.6  470.82  5911.9  479.61  6006.6  483.50
#Mann=5,-1,0
  4230.2    0.16       0  4701.2    0.07       0  4975.2    0.07       0
  4983.8    0.07       0  5330.5   0.045       0
Bank Sta=4975.2,4983.8
Exp/Cntr=0.3,0.1

Type RM Length L Ch R = 1,6790,330,330,330
BEGIN DESCRIPTION:
B20084
END DESCRIPTION:
XS GIS Cut Line= 3
      2332728.69     13734247.33      2333744.27     13734468.67
      2334403.98     13734629.26
#Sta/Elev= 30
  4193.2  484.05  4322.5  480.03  4342.2  481.03  4353.2  479.09  4429.6  475.42
  4749.2  467.98  4905.4  463.45  4963.8  455.81  4983.4  448.51  4983.9  448.01
  4992.1  448.51  5003.6  453.71  5008.7  451.91  5028.7  454.36  5059.4  462.61
  5110.6  463.65  5145.7  461.26  5247.5  462.69  5368.7  468.23  5542.1  470.52
  5768.6  476.50  5785.9  478.30  5791.1  482.33  5809.7  485.73  5827.7  486.96
  5832.8  483.13  5840.6  483.13  5869.4  486.59  5874.5  481.97  5911.6  487.00
#Mann=7,-1,0
  4193.2    0.16       0  4429.6    0.07       0  4749.2    0.16       0
  4963.8    0.12       0  4983.4    0.07       0  4992.1    0.12       0
  5247.5   0.045       0
Bank Sta=4983.4,4992.1
Exp/Cntr=0.3,0.1

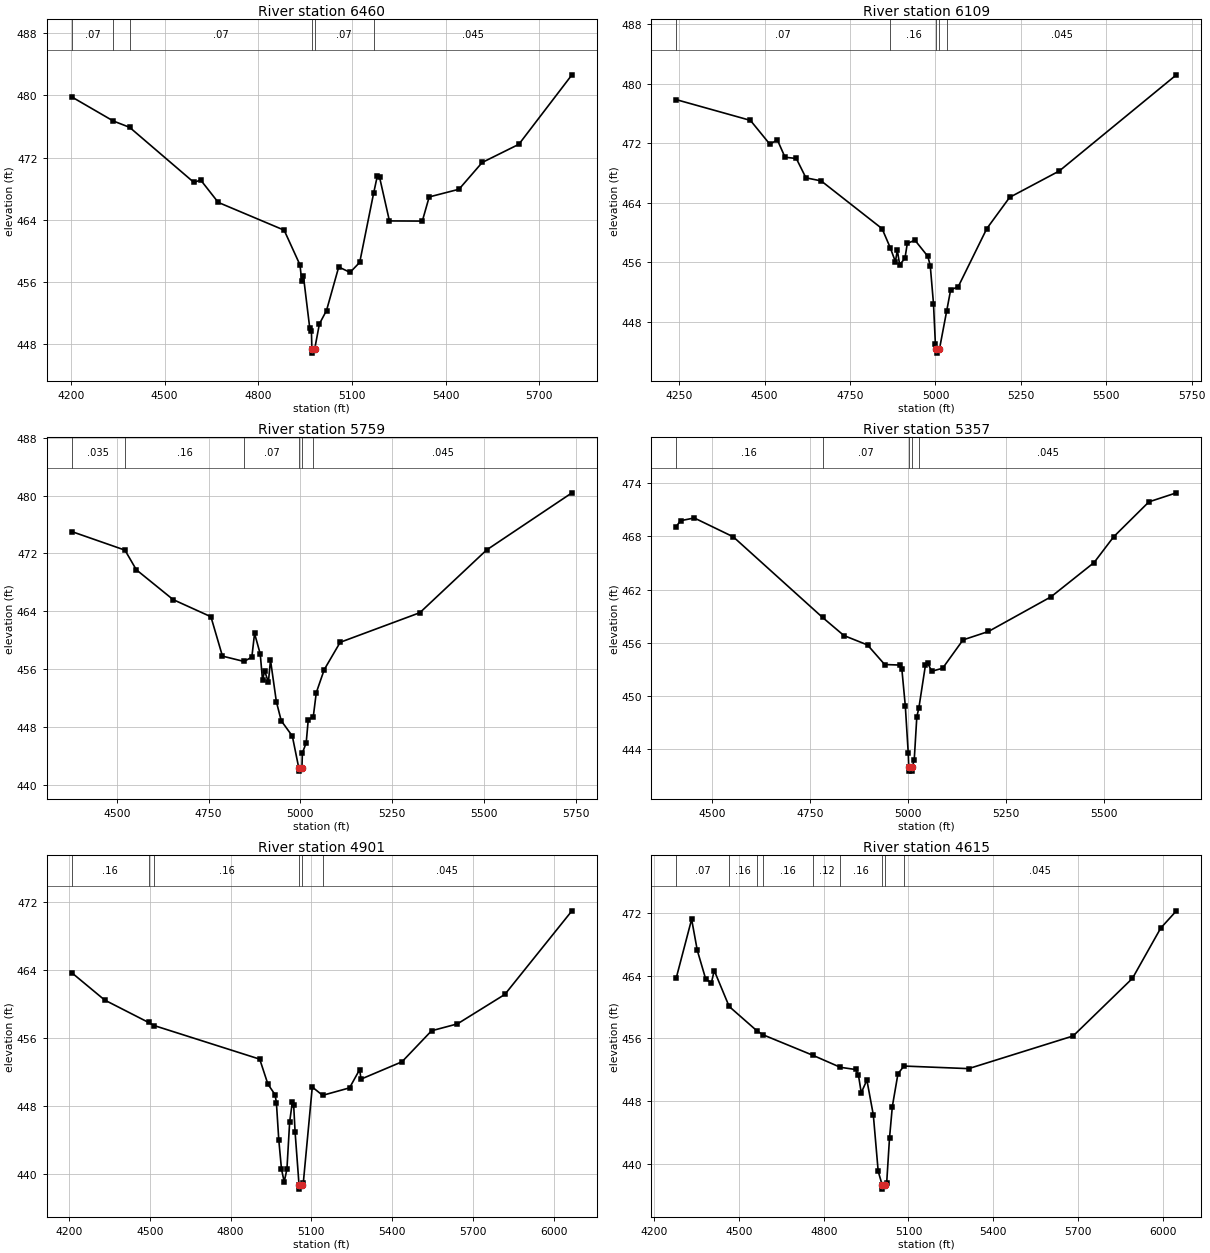
Type RM Length L Ch R = 1,6460,351,351,351
BEGIN DESCRIPTION:
B20083
END DESCRIPTION:
XS GIS Cut Line= 2
      2332715.66     13734464.34      2334226.00     13734998.17
#Sta/Elev= 30
  4202.6  479.82  4335.9  476.71  4388.0  475.90  4594.3  468.79  4615.5  469.12
  4671.8  466.23  4882.9  462.65  4933.7  458.17  4939.4  456.06  4944.7  456.72
  4965.0  450.01  4970.3  449.62  4971.8  447.31  4972.3  446.81  4980.6  447.31
  4995.9  450.58  5018.6  452.30  5057.7  457.91  5094.0  457.21  5124.9  458.50
  5169.4  467.40  5181.4  469.65  5188.3  469.50  5220.1  463.84  5325.4  463.82
  5347.4  466.93  5442.8  467.92  5517.1  471.37  5634.5  473.71  5804.5  482.66
#Mann=6,-1,0
  4202.6    0.07       0  4335.9    0.16       0  4388.0    0.07       0
  4971.8    0.07       0  4980.6    0.07       0  5169.4   0.045       0
Bank Sta=4971.8,4980.6
Exp/Cntr=0.3,0.1

Type RM Length L Ch R = 1,6109,350,350,350
BEGIN DESCRIPTION:
B20082
END DESCRIPTION:
XS GIS Cut Line= 3
      2332680.92     13734698.72      2333575.00     13735150.09
      2333974.33     13735384.49
#Sta/Elev= 30
  4240.8  477.87  4458.2  475.08  4514.9  471.89  4537.2  472.45  4559.5  470.13
  4592.6  469.96  4620.8  467.36  4665.3  466.95  4843.7  460.53  4868.0  457.93
  4882.7  456.09  4888.3  457.65  4895.1  455.70  4910.6  456.53  4917.5  458.55
  4939.9  458.98  4977.5  456.82  4984.7  455.58  4994.2  450.45  4999.8  445.00
  5002.7  444.31  5003.2  443.81  5011.5  444.31  5032.9  449.49  5044.4  452.30
  5066.7  452.74  5150.3  460.54  5217.2  464.74  5362.4  468.28  5705.4  481.20
#Mann=5,-1,0
  4240.8    0.07       0  4868.0    0.16       0  5002.7    0.07       0
  5011.5    0.16       0  5032.9   0.045       0
Bank Sta=5002.7,5011.5
Exp/Cntr=0.3,0.1

Type RM Length L Ch R = 1,5759,402,402,402
BEGIN DESCRIPTION:
B20081
END DESCRIPTION:
XS GIS Cut Line= 3
      2332646.16     13735006.85      2333449.13     13735453.91
      2333881.60     13735553.38
#Sta/Elev= 30
  4377.1  475.02  4522.2  472.45  4553.2  469.73  4653.5  465.60  4756.4  463.23
  4787.8  457.78  4846.5  457.04  4867.9  457.64  4875.3  460.92  4890.8  458.07
  4897.0  454.44  4902.7  455.74  4913.0  454.17  4918.7  457.23  4934.7  451.47
  4948.0  448.83  4978.2  446.71  4995.5  442.36  4996.0  441.86  5004.4  442.36
  5005.6  444.39  5015.9  445.75  5021.6  448.99  5035.2  449.36  5043.4  452.71
  5065.1  455.91  5108.5  459.69  5325.6  463.79  5507.4  472.47  5739.9  480.38
#Mann=6,-1,0
  4377.1   0.035       0  4522.2    0.16       0  4846.5    0.07       0
  4995.5    0.07       0  5004.4    0.07       0  5035.2   0.045       0
Bank Sta=4995.5,5004.4
Exp/Cntr=0.3,0.1

Type RM Length L Ch R = 1,5357,456,456,456
BEGIN DESCRIPTION:
B20080
END DESCRIPTION:
XS GIS Cut Line= 4
      2332611.47     13735262.95      2332884.89     13735575.44
      2333201.73     13735744.71      2333705.17     13735749.05
#Sta/Elev= 30
  4407.4  469.11  4418.6  469.77  4453.7  470.08  4553.3  467.95  4781.3  458.85
  4836.0  456.80  4896.2  455.74  4940.1  453.53  4978.3  453.47  4984.0  452.99
  4992.8  448.84  5000.3  443.51  5001.5  441.99  5002.0  441.49  5009.9  441.49
  5010.4  441.99  5015.5  442.70  5022.2  447.64  5027.4  448.62  5044.2  453.46
  5049.8  453.69  5060.4  452.77  5088.1  453.11  5140.2  456.31  5205.1  457.26
  5365.1  461.18  5475.1  465.05  5525.1  467.96  5615.1  471.90  5685.3  472.92
#Mann=5,-1,0
  4407.4    0.16       0  4781.3    0.07       0  5001.5    0.07       0
  5010.4    0.07       0  5027.4   0.045       0
Bank Sta=5001.5,5010.4
Exp/Cntr=0.3,0.1

Type RM Length L Ch R = 1,4901,286,286,286
BEGIN DESCRIPTION:
B20079
END DESCRIPTION:
XS GIS Cut Line= 3
      2332003.86     13735848.02      2333019.44     13735999.92
      2333830.50     13736186.42
#Sta/Elev= 30
  4209.4  463.68  4331.9  460.46  4495.1  457.82  4516.2  457.45  4908.2  453.50
  4938.6  450.56  4965.1  449.32  4970.2  448.38  4979.0  444.02  4989.1  440.55
  4999.2  439.06  5009.3  440.54  5019.5  446.13  5029.3  448.41  5034.3  448.13
  5039.7  444.90  5054.3  438.70  5054.8  438.20  5065.5  438.70  5070.0  438.88
  5103.5  450.22  5141.9  449.24  5242.0  450.12  5279.6  452.27  5284.7  451.15
  5436.9  453.19  5546.8  456.84  5642.8  457.65  5819.2  461.12  6068.5  470.96
#Mann=6,-1,0
  4209.4    0.16       0  4495.1    0.07       0  4516.2    0.16       0
  5054.3    0.07       0  5065.5    0.16       0  5141.9   0.045       0
Bank Sta=5054.3,5065.5
Exp/Cntr=0.3,0.1

Type RM Length L Ch R = 1,4615,272,272,272
BEGIN DESCRIPTION:
B20078
END DESCRIPTION:
XS GIS Cut Line= 3
      2332060.21     13736190.89      2332993.40     13736229.96
      2333830.51     13736251.64
#Sta/Elev= 30
  4277.4  463.64  4332.2  471.17  4352.3  467.20  4382.3  463.52  4402.3  463.09
  4412.3  464.63  4465.1  460.05  4563.5  456.94  4585.5  456.43  4760.4  453.84
  4858.8  452.29  4912.7  452.01  4922.8  451.32  4932.8  449.04  4952.8  450.66
  4975.6  446.21  4992.8  439.03  5007.2  437.25  5007.7  436.75  5018.5  437.25
  5022.8  437.50  5032.9  443.27  5042.9  447.29  5062.9  451.48  5084.3  452.45
  5313.0  452.12  5683.2  456.29  5893.2  463.64  5993.3  470.05  6048.8  472.25
#Mann=9,-1,0
  4277.4    0.07       0  4465.1    0.16       0  4563.5    0.07       0
  4585.5    0.16       0  4760.4    0.12       0  4858.8    0.16       0
  5007.2    0.07       0  5018.5    0.16       0  5084.3   0.045       0
Bank Sta=5007.2,5018.5
Exp/Cntr=0.3,0.1