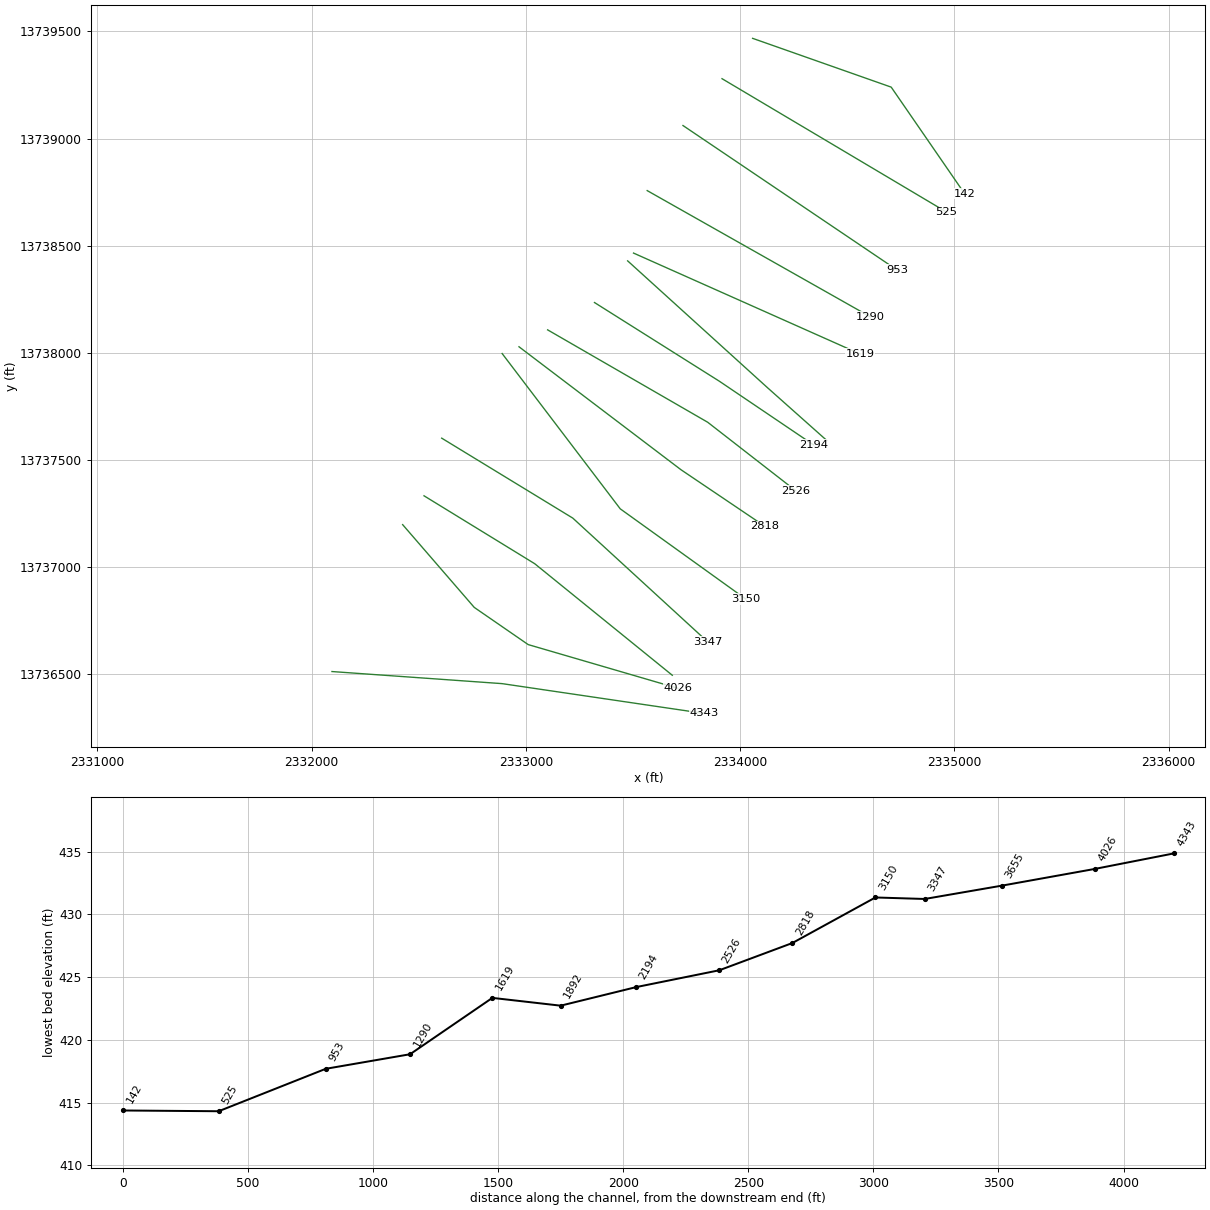
HEC-RAS study POLECAT CREEK.prj: POLECAT CREEK Base Level Engineering

--- POLECAT CREEK.g01 (geometry) --- (continued)

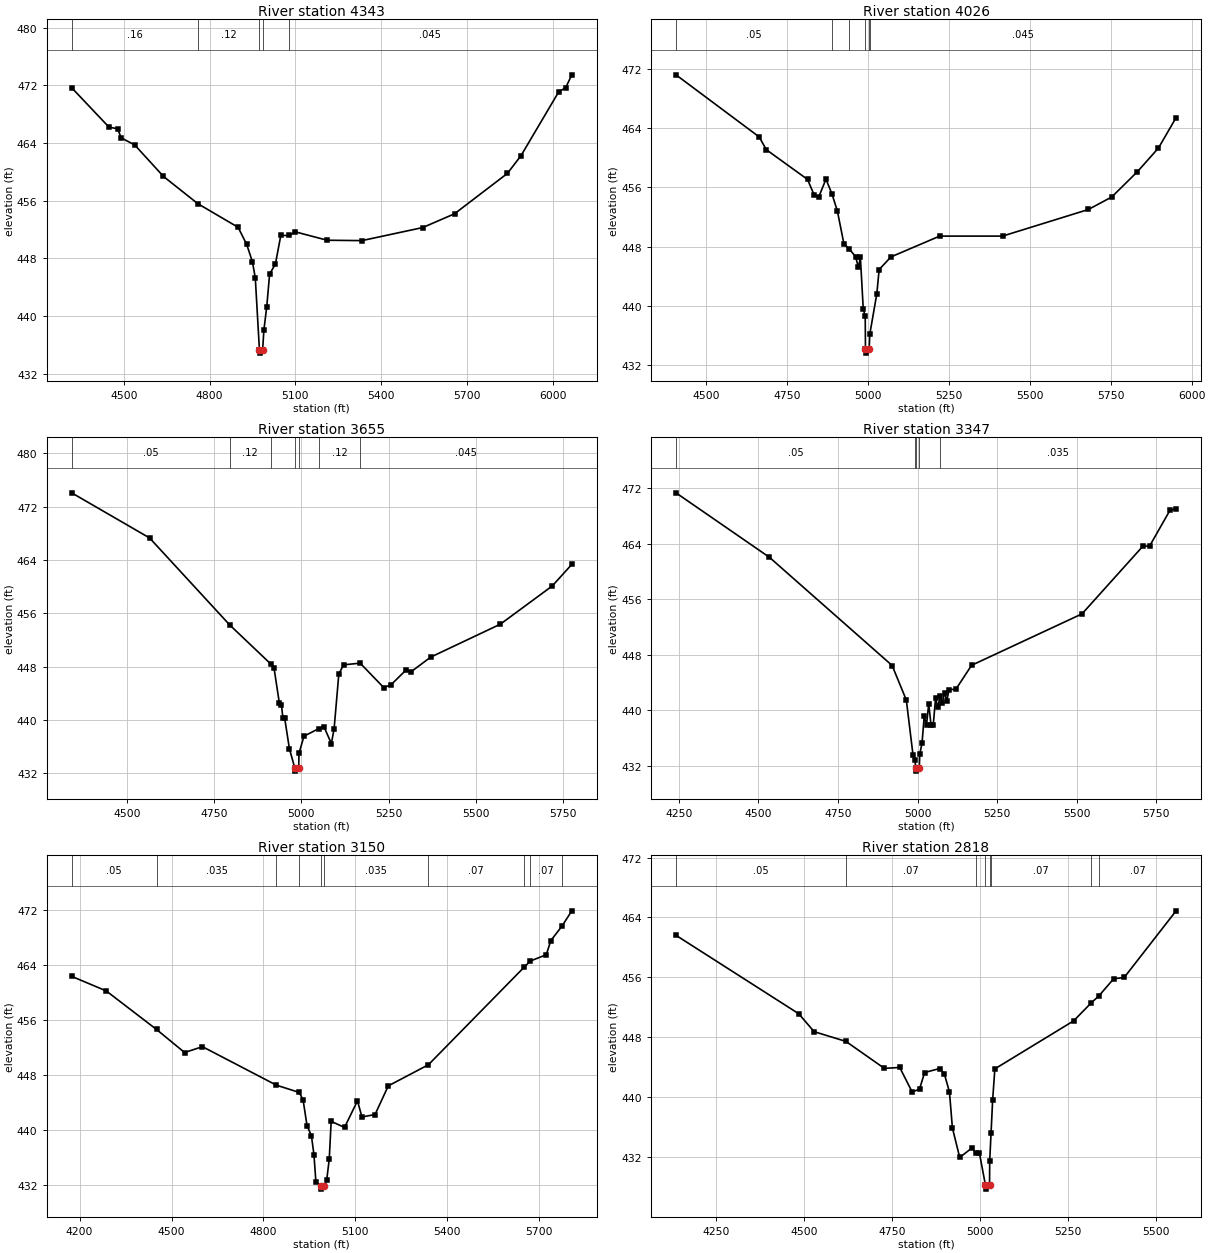
Type RM Length L Ch R = 1,4343,317,317,317
BEGIN DESCRIPTION:
B20077
END DESCRIPTION:
XS GIS Cut Line= 3
      2332094.93     13736512.08      2332889.23     13736455.65
      2333830.54     13736316.84
#Sta/Elev= 30
  4318.1  471.68  4448.5  466.21  4478.6  465.99  4491.1  464.73  4538.7  463.73
  4639.0  459.37  4759.1  455.59  4899.6  452.32  4929.7  449.95  4949.8  447.53
  4959.8  445.29  4974.2  435.36  4974.7  434.86  4985.5  435.36  4989.9  438.07
  4999.9  441.32  5009.9  445.84  5030.0  447.20  5049.0  451.19  5077.8  451.18
  5100.1  451.68  5211.2  450.52  5332.5  450.47  5544.8  452.28  5656.0  454.19
  5840.8  459.79  5888.5  462.26  6019.9  471.09  6044.7  471.70  6065.9  473.47
#Mann=5,-1,0
  4318.1    0.16       0  4759.1    0.12       0  4974.2    0.07       0
  4985.5    0.12       0  5077.8   0.045       0
Bank Sta=4974.2,4985.5
Exp/Cntr=0.3,0.1

Type RM Length L Ch R = 1,4026,371,371,371
BEGIN DESCRIPTION:
B20076
END DESCRIPTION:
XS GIS Cut Line= 4
      2332424.84     13737197.82      2332759.03     13736811.55
      2333010.76     13736637.94      2333709.53     13736433.95
#Sta/Elev= 30
  4407.5  471.17  4664.5  462.79  4686.4  461.07  4813.7  457.06  4834.5  454.93
  4848.8  454.74  4870.7  457.09  4889.2  455.10  4905.8  452.82  4926.3  448.33
  4942.2  447.70  4962.1  446.63  4970.9  445.19  4977.0  446.55  4985.8  439.59
  4991.9  438.58  4992.7  434.12  4993.2  433.62  5004.1  434.12  5006.0  436.17
  5027.7  441.62  5034.9  444.90  5071.3  446.60  5221.8  449.41  5416.0  449.41
  5681.1  453.00  5753.3  454.69  5832.7  458.11  5897.6  461.30  5952.0  465.40
#Mann=6,-1,0
  4407.5    0.05       0  4889.2    0.16       0  4942.2    0.12       0
  4992.7    0.07       0  5004.1    0.12       0  5006.0   0.045       0
Bank Sta=4992.7,5004.1
Exp/Cntr=0.3,0.1

Type RM Length L Ch R = 1,3655,308,308,308
BEGIN DESCRIPTION:
B20075
END DESCRIPTION:
XS GIS Cut Line= 3
      2332524.62     13737332.40      2333041.14     13737015.55
      2333683.47     13736494.74
#Sta/Elev= 30
  4342.0  474.09  4565.3  467.31  4794.9  454.24  4912.5  448.38  4921.7  447.81
  4937.2  442.45  4943.0  442.25  4947.3  440.22  4952.4  440.22  4965.8  435.66
  4981.1  432.79  4981.6  432.29  4992.5  432.79  4993.3  434.97  5007.6  437.54
  5049.8  438.67  5065.1  438.93  5086.0  436.43  5093.9  438.63  5107.4  446.88
  5121.1  448.25  5168.5  448.51  5236.2  444.83  5257.0  445.26  5300.1  447.48
  5313.4  447.17  5370.5  449.41  5570.2  454.36  5718.9  460.10  5774.9  463.34
#Mann=7,-1,0
  4342.0    0.05       0  4794.9    0.12       0  4912.5    0.16       0
  4981.1    0.07       0  4992.5    0.16       0  5049.8    0.12       0
  5168.5   0.045       0
Bank Sta=4981.1,4992.5
Exp/Cntr=0.3,0.1

Type RM Length L Ch R = 1,3347,197,197,197
BEGIN DESCRIPTION:
B20074
END DESCRIPTION:
XS GIS Cut Line= 3
      2332607.12     13737601.48      2333219.10     13737228.22
      2333848.43     13736650.97
#Sta/Elev= 30
  4241.0  471.36  4534.6  462.06  4919.9  446.46  4964.5  441.47  4985.5  433.54
  4991.6  432.79  4994.0  431.73  4994.5  431.23  5005.4  431.73  5006.5  433.63
  5013.8  435.28  5020.6  439.11  5028.0  437.93  5034.8  440.94  5042.2  437.83
  5049.0  437.89  5056.4  441.76  5063.2  440.47  5071.5  442.03  5077.4  441.05
  5084.8  442.56  5091.5  441.36  5098.9  443.00  5119.9  443.02  5169.4  446.49
  5516.4  453.91  5707.5  463.67  5728.5  463.68  5792.6  468.85  5811.8  469.04
#Mann=5,-1,0
  4241.0    0.05       0  4991.6    0.16       0  4994.0    0.07       0
  5005.4    0.16       0  5071.5   0.035       0
Bank Sta=4994,5005.4
Exp/Cntr=0.3,0.1

Type RM Length L Ch R = 1,3150,332,332,332
BEGIN DESCRIPTION:
B20073
END DESCRIPTION:
XS GIS Cut Line= 3
      2332889.20     13737996.49      2333440.45     13737271.62
      2334026.42     13736850.59
#Sta/Elev= 30
  4174.2  462.30  4287.0  460.18  4451.2  454.57  4542.8  451.22  4601.0  452.07
  4842.4  446.47  4917.2  445.41  4929.5  444.31  4942.4  440.56  4956.6  439.12
  4964.9  436.36  4971.2  432.43  4986.9  431.85  4987.4  431.35  4998.4  431.85
  5006.5  432.66  5014.8  435.70  5021.1  441.21  5064.7  440.32  5106.9  444.19
  5121.6  441.84  5164.3  442.20  5207.5  446.37  5338.4  449.44  5650.4  463.61
  5670.8  464.52  5723.2  465.45  5737.9  467.50  5774.3  469.60  5806.4  471.83
#Mann=10,-1,0
  4174.2    0.05       0  4451.2   0.035       0  4842.4    0.07       0
  4917.2   0.035       0  4986.9   0.035       0  4998.4   0.035       0
  5338.4    0.07       0  5650.4    0.16       0  5670.8    0.07       0
  5774.3    0.16       0
Bank Sta=4986.9,4998.4
Exp/Cntr=0.3,0.1

Type RM Length L Ch R = 1,2818,292,292,292
BEGIN DESCRIPTION:
B20072
END DESCRIPTION:
XS GIS Cut Line= 3
      2332967.93     13738028.03      2333724.23     13737453.96
      2334115.81     13737189.88
#Sta/Elev= 30
  4135.9  461.62  4485.0  451.14  4528.6  448.75  4619.0  447.45  4728.3  443.85
  4772.0  443.97  4807.3  440.70  4828.2  441.07  4842.7  443.29  4885.5  443.83
  4898.9  443.10  4913.4  440.69  4921.7  435.90  4942.5  431.95  4977.9  433.24
  4988.5  432.52  4998.7  432.50  5015.8  428.22  5016.3  427.72  5027.3  428.22
  5027.8  431.48  5031.6  435.20  5036.1  439.60  5042.4  443.78  5266.3  450.19
  5316.5  452.60  5337.4  453.49  5380.2  455.81  5410.2  455.99  5557.7  464.89
#Mann=8,-1,0
  4135.9    0.05       0  4619.0    0.07       0  4988.5    0.16       0
  5015.8    0.07       0  5027.3    0.16       0  5031.6    0.07       0
  5316.5    0.16       0  5337.4    0.07       0
Bank Sta=5015.8,5027.3
Exp/Cntr=0.3,0.1

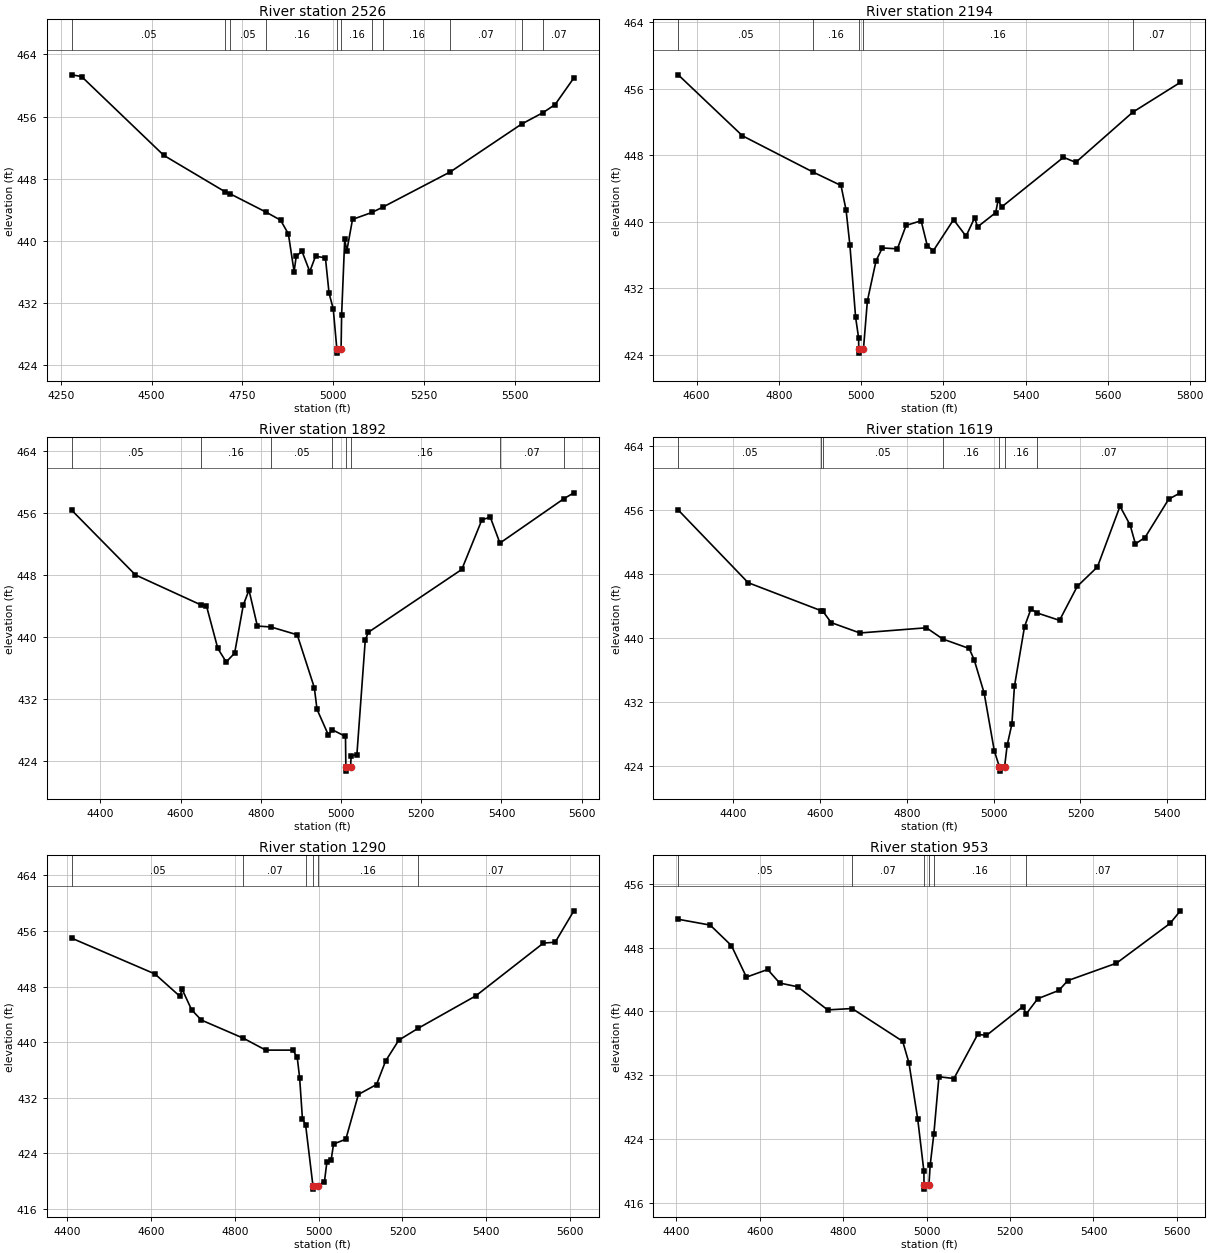
Type RM Length L Ch R = 1,2526,332,332,332
BEGIN DESCRIPTION:
B20071
END DESCRIPTION:
XS GIS Cut Line= 3
      2333101.58     13738106.99      2333848.76     13737675.69
      2334258.81     13737356.77
#Sta/Elev= 30
  4280.2  461.38  4307.2  461.16  4533.3  451.02  4702.7  446.31  4715.0  446.09
  4816.0  443.68  4855.0  442.67  4876.5  440.90  4892.3  436.04  4898.1  438.02
  4913.9  438.67  4935.4  436.05  4951.2  438.02  4978.5  437.82  4988.5  433.27
  5000.0  431.25  5010.0  426.05  5010.5  425.55  5021.6  426.05  5023.1  430.49
  5031.6  440.18  5037.4  438.73  5053.1  442.77  5106.5  443.66  5137.0  444.36
  5322.5  448.89  5518.5  455.04  5577.4  456.51  5610.8  457.55  5662.4  460.98
#Mann=11,-1,0
  4280.2    0.05       0  4702.7    0.07       0  4715.0    0.05       0
  4816.0    0.16       0  5010.0    0.07       0  5021.6    0.16       0
  5106.5    0.07       0  5137.0    0.16       0  5322.5    0.07       0
  5518.5    0.16       0  5577.4    0.07       0
Bank Sta=5010,5021.6
Exp/Cntr=0.3,0.1

Type RM Length L Ch R = 1,2194,302,302,302
BEGIN DESCRIPTION:
B20070
END DESCRIPTION:
XS GIS Cut Line= 3
      2333320.29     13738234.55      2333903.44     13737867.04
      2334343.39     13737569.70
#Sta/Elev= 30
  4555.6  457.68  4711.6  450.35  4883.1  445.99  4951.2  444.37  4963.5  441.43
  4972.9  437.16  4986.7  428.52  4994.1  426.00  4994.2  424.71  4994.7  424.21
  5005.8  424.71  5015.3  430.48  5036.5  435.34  5051.7  436.86  5088.2  436.75
  5109.4  439.57  5145.9  440.13  5161.2  437.08  5175.8  436.54  5224.8  440.26
  5255.1  438.27  5276.1  440.50  5283.0  439.39  5327.1  441.10  5333.1  442.61
  5342.0  441.80  5491.9  447.76  5521.8  447.15  5660.2  453.18  5775.9  456.77
#Mann=5,-1,0
  4555.6    0.05       0  4883.1    0.16       0  4994.2    0.07       0
  5005.8    0.16       0  5660.2    0.07       0
Bank Sta=4994.2,5005.8
Exp/Cntr=0.3,0.1

Type RM Length L Ch R = 1,1892,273,273,273
BEGIN DESCRIPTION:
B20069
END DESCRIPTION:
XS GIS Cut Line= 3
      2333475.14     13738428.98      2334128.20     13737836.67
      2334404.61     13737590.63
#Sta/Elev= 30
  4328.8  456.37  4487.4  448.04  4649.8  444.19  4664.5  444.06  4692.9  438.55
  4713.8  436.81  4734.8  437.94  4756.4  444.14  4770.6  446.08  4791.5  441.44
  4825.4  441.32  4890.9  440.31  4933.5  433.50  4940.2  430.70  4968.6  427.38
  4978.5  428.06  5011.2  427.20  5012.1  423.23  5012.6  422.73  5023.7  423.23
  5025.4  424.74  5039.6  424.84  5060.5  439.62  5068.0  440.63  5301.1  448.74
  5351.3  455.14  5372.2  455.48  5396.2  452.14  5555.9  457.87  5580.5  458.62
#Mann=8,-1,0
  4328.8    0.05       0  4649.8    0.16       0  4825.4    0.05       0
  4978.5    0.16       0  5012.1    0.07       0  5023.7    0.16       0
  5396.2    0.07       0  5555.9    0.05       0
Bank Sta=5012.1,5023.7
Exp/Cntr=0.3,0.1

Type RM Length L Ch R = 1,1619,329,329,329
BEGIN DESCRIPTION:
B20068
END DESCRIPTION:
XS GIS Cut Line= 2
      2333502.52     13738465.39      2334559.52     13737994.60
#Sta/Elev= 30
  4273.2  456.01  4434.3  446.92  4601.4  443.44  4606.1  443.38  4625.6  441.93
  4691.9  440.63  4845.2  441.28  4882.7  439.88  4943.7  438.69  4955.1  437.30
  4978.3  433.10  5001.6  425.89  5013.5  423.85  5014.0  423.35  5025.2  423.85
  5031.3  426.60  5042.2  429.25  5048.0  433.96  5071.3  441.43  5086.0  443.62
  5101.1  443.12  5151.9  442.21  5192.9  446.47  5239.3  448.89  5291.3  456.48
  5314.6  454.14  5326.8  451.78  5348.8  452.56  5403.5  457.36  5430.3  458.16
#Mann=7,-1,0
  4273.2    0.05       0  4601.4    0.16       0  4606.1    0.05       0
  4882.7    0.16       0  5013.5    0.07       0  5025.2    0.16       0
  5101.1    0.07       0
Bank Sta=5013.5,5025.2
Exp/Cntr=0.3,0.1

Type RM Length L Ch R = 1,1290,337,337,337
BEGIN DESCRIPTION:
B20067
END DESCRIPTION:
XS GIS Cut Line= 2
      2333566.32     13738756.96      2334608.13     13738167.72
#Sta/Elev= 30
  4411.6  454.96  4609.8  449.82  4669.0  446.62  4674.8  447.60  4697.3  444.66
  4720.3  443.19  4820.7  440.57  4874.0  438.86  4938.9  438.86  4949.1  437.80
  4954.8  434.88  4961.5  428.97  4969.0  428.12  4986.5  419.36  4987.0  418.86
  4998.2  419.36  5014.0  419.95  5019.8  422.78  5029.9  423.05  5035.7  425.35
  5064.9  426.04  5094.9  432.48  5138.1  433.91  5159.8  437.30  5191.3  440.30
  5237.9  442.02  5374.9  446.67  5536.0  454.26  5564.0  454.38  5608.5  458.90
#Mann=6,-1,0
  4411.6    0.05       0  4820.7    0.07       0  4969.0    0.16       0
  4986.5    0.07       0  4998.2    0.16       0  5237.9    0.07       0
Bank Sta=4986.5,4998.2
Exp/Cntr=0.3,0.1

Type RM Length L Ch R = 1,953,428,428,428
BEGIN DESCRIPTION:
B20066
END DESCRIPTION:
XS GIS Cut Line= 2
      2333733.36     13739060.70      2334731.32     13738387.31
#Sta/Elev= 30
  4404.3  451.56  4480.9  450.83  4531.8  448.26  4567.8  444.30  4618.7  445.26
  4647.5  443.56  4690.7  443.09  4762.6  440.19  4821.2  440.36  4942.5  436.25
  4957.5  433.54  4978.5  426.51  4993.4  419.93  4993.6  418.20  4994.1  417.70
  5005.4  418.20  5008.4  420.69  5017.3  424.67  5029.4  431.80  5065.4  431.58
  5122.4  437.12  5143.4  436.99  5230.3  440.59  5238.9  439.70  5266.3  441.59
  5317.2  442.64  5338.2  443.86  5455.1  446.05  5584.0  451.06  5608.2  452.62
#Mann=6,-1,0
  4404.3    0.05       0  4821.2    0.07       0  4993.6    0.07       0
  5005.4    0.07       0  5017.3    0.16       0  5238.9    0.07       0
Bank Sta=4993.6,5005.4
Exp/Cntr=0.3,0.1

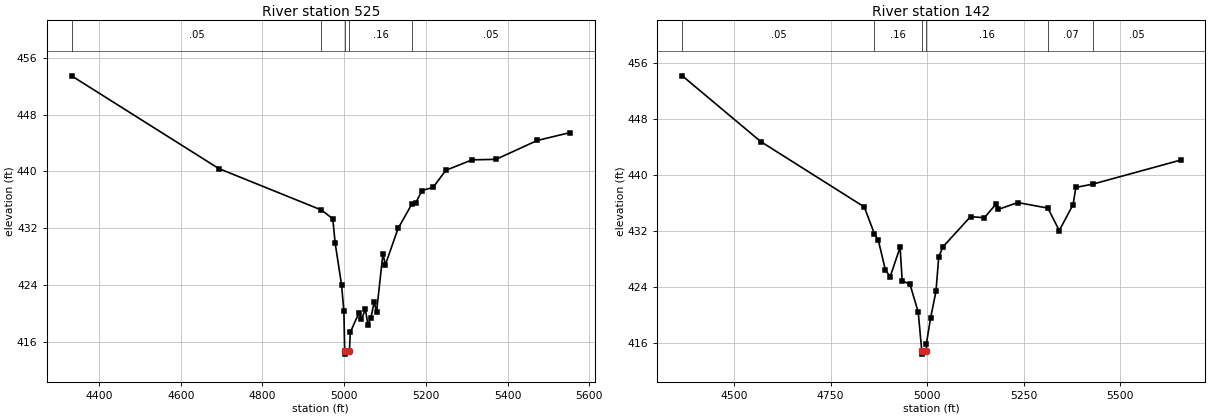
Type RM Length L Ch R = 1,525,383,383,383
BEGIN DESCRIPTION:
B20065
END DESCRIPTION:
XS GIS Cut Line= 2
      2333915.55     13739279.42      2334963.51     13738656.73
#Sta/Elev= 30
  4333.0  453.44  4693.0  440.41  4944.2  434.58  4972.1  433.35  4977.9  429.92
  4993.5  424.07  4999.3  420.34  5001.1  414.82  5001.6  414.32  5012.9  414.82
  5014.9  417.39  5036.4  420.15  5042.2  419.26  5052.0  420.62  5057.8  418.47
  5065.2  419.39  5073.4  421.64  5079.2  420.25  5094.8  428.46  5100.6  426.86
  5131.8  431.98  5165.6  435.42  5174.7  435.54  5190.3  437.32  5217.5  437.76
  5248.7  440.16  5313.0  441.63  5371.4  441.70  5472.7  444.36  5552.0  445.45
#Mann=5,-1,0
  4333.0    0.05       0  4944.2    0.16       0  5001.1    0.07       0
  5012.9    0.16       0  5165.6    0.05       0
Bank Sta=5001.1,5012.9
Exp/Cntr=0.3,0.1

Type RM Length L Ch R = 1,142,0,0,0
BEGIN DESCRIPTION:
B20064
END DESCRIPTION:
XS GIS Cut Line= 3
      2334058.36     13739467.71      2334705.29     13739239.92
      2335048.52     13738741.78
#Sta/Elev= 30
  4365.8  454.22  4569.3  444.80  4837.3  435.45  4863.5  431.61  4873.6  430.71
  4892.3  426.36  4904.6  425.49  4930.2  429.68  4935.5  424.90  4955.9  424.35
  4977.1  420.39  4986.2  414.88  4986.7  414.38  4998.0  414.88  4998.3  415.87
  5008.9  419.50  5023.1  423.37  5030.2  428.28  5040.8  429.72  5112.6  434.06
  5148.4  433.91  5178.2  435.83  5184.2  435.09  5235.0  436.08  5313.1  435.28
  5342.5  432.07  5378.3  435.78  5385.5  438.25  5430.3  438.73  5656.6  442.15
#Mann=6,-1,0
  4365.8    0.05       0  4863.5    0.16       0  4986.2    0.07       0
  4998.0    0.16       0  5313.1    0.07       0  5430.3    0.05       0
Bank Sta=4986.2,4998
Exp/Cntr=0.3,0.1

Chan Stop Cuts=-1