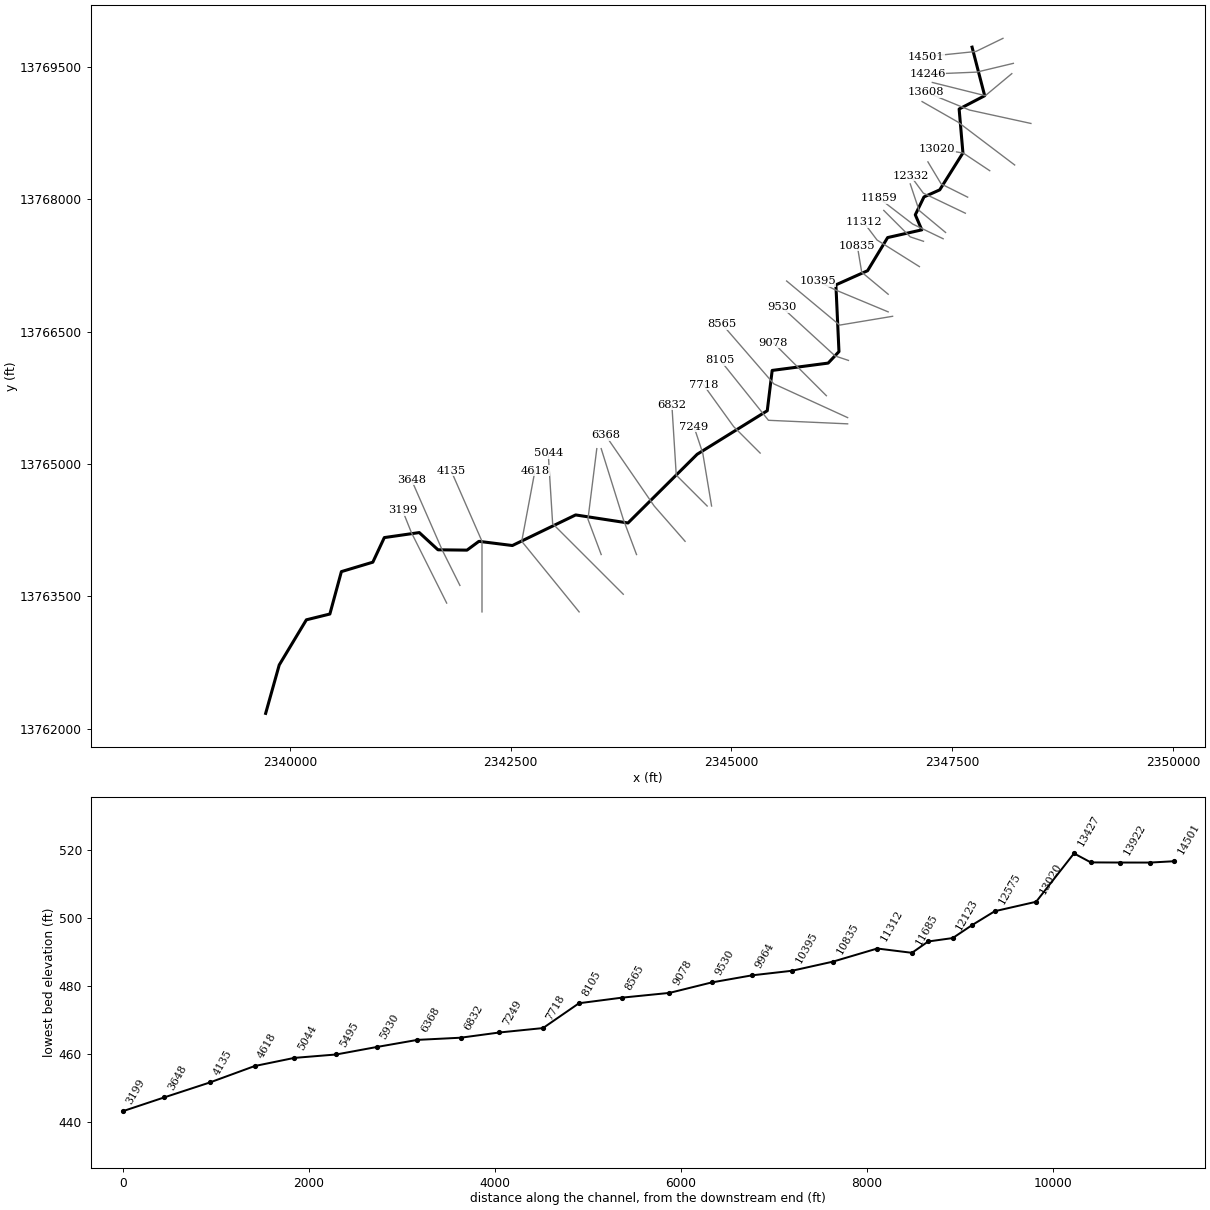
--- RED BRANCH 2.prj (project) ---

Proj Title=RED BRANCH 2 Base Level Engineering
Current Plan=p01
Default Exp/Contr=0.3,0.1
English Units
Geom File=g01
Flow File=f01
Plan File=p01
Y Axis Title=Elevation
X Axis Title(PF)=Main Channel Distance
X Axis Title(XS)=Station
BEGIN DESCRIPTION:
RED BRANCH 2
END DESCRIPTION:
DSS Export Rating Curves= 0
DSS Export Rating Curve Sorted= 0
DSS Export Volume Flow Curves= 0
DXF OffsetX= 0
DXF OffsetY= 0
DXF ScaleX= 1
DXF ScaleY= 10

--- RED BRANCH 2.p01 (plan) ---

Plan Title=Multiple Run
Program Version=4.10
Short Identifier=Multiple
Geom File=g01
Flow File=f01
Subcritical Flow
K Sum by GR= 0
Std Step Tol= 0.01
Critical Tol= 0.01
Num of Std Step Trials= 20
Max Error Tol= 0.3
Flow Tol Ratio= 0.001
Split Flow NTrial= 30
Split Flow Tol= 0.02
Split Flow Ratio= 0.02
Log Output Level= 0
Friction Slope Method= 1
Unsteady Friction Slope Method= 2
Unsteady Bridges Friction Slope Method= 1
Parabolic Critical Depth
Global Vel Dist= 1 , 1 , 1
Global Log Level= 0
CheckData=True
Encroach Param=-1 ,0,0, 0
BEGIN DESCRIPTION:
Multiple Run
END DESCRIPTION:
Computation Interval=1HOUR
Output Interval=1HOUR
Run HTab= 0
Run UNet= 0
Run PostProcess= 0
Run WQNet= 0
UNET Theta= 1
UNET Theta Warmup= 1
UNET ZTol= 0.02
UNET ZSATol= 0.05
UNET MxIter= 20
UNET MaxInSteps= 0
UNET DtIC= 0
UNET DtMin= 0
UNET MaxCRTS= 20
UNET WFStab= 2
UNET SFStab= 1
UNET WFX= 1
UNET SFX= 1
UNET DSS MLevel= 4
UNET DZMax Abort= 100
UNET Convert EG Bridges= 0
UNET Use Existing IB Tables=-1
UNET Froude Reduction=False
UNET Froude Limit= 1
UNET Froude Power= 10
UNET Time Slicing=0,0, 5
UNET Junction Losses=0
Instantaneous Interval=1HOUR
Write IC File= 0
Write IC File at Sim End=0
Echo Input=False
Echo Parameters=False
Echo Output=False
Write Detailed= 0
WQ AD Non Conservative
WQ ULTIMATE=-1
WQ Max Comp Step=1HOUR
WQ Output Interval=15MIN
WQ Output Selected Increments= 0
WQ Output face flow=0
WQ Output face velocity=0
WQ Output face area=0
WQ Output face dispersion=0
WQ Output cell volume=0
WQ Output cell surface area=0
WQ Output cell continuity=0
WQ Output cumulative cell continuity=0
WQ Output face conc=0
WQ Output face dconc_dx=0
WQ Output face courant=0
WQ Output face peclet=0
WQ Output face adv mass=0
WQ Output face disp mass=0
WQ Output cell mass=0
WQ Output cell source sink temp=0
WQ Output cell source sink nsm=0
WQ Output MaxMinRange=-1
WQ Daily Max Min Mean=-1
WQ Daily Range=0
WQ Daily Time=0
WQ Create Restart=0
WQ Fixed Restart=0
WQ System Summary=0
WQ Use Fixed Temperature=0
Sorting and Armoring Iterations= 10
XS Update Threshold= 0.02
Hydraulics Update Threshold= 0.02
Energy Slope Method= 1
Volume Change Method= 0
XS Weighting Method= 0
Number of US Weighted Cross Sections= 1
Number of DS Weighted Cross Sections= 1
Upstream XS Weight=0.25
Main XS Weight=0.5
Downstream XS Weight=0.25
Number of DS XS's Weighted with US Boundary= 1
Upstream Boundary Weight= 1
Weight of XSs Associated with US Boundary= 0
Number of US XS's Weighted with DS Boundary= 1
Downstream Boundary Weight= 0.5
Weight of XSs Associated with DS Boundary= 0.5
Sediment Output Level= 4
Mass or Volume Output= 0
Output Increment Type= 1
Profile and TS Output Increment= 10
XS Output Flag= 0
XS Output Increment= 10
Disregard all LS=0
Disregard all Conn=0
Disregard all Breaches=0
Disregard all Pumps=0

--- RED BRANCH 2.f01 (steady flow) ---

Flow Title=Multiple
Number of Profiles=7
Profile Names=10-year,25-year,50-year,1pct_min,100-year,1pct_plu,500-year
River Rch & RM= RED BRANCH 2,Reach-1,14501
     580     935    1255     817    1630    3251    2721
River Rch & RM= RED BRANCH 2,Reach-1,6832
     982    1626    2223    1469    2931    5849    5054
Boundary for River Rch & Prof#=RED BRANCH 2,Reach-1,1
Up Type=0
Dn Type=3
Dn Slope=0.005
Boundary for River Rch & Prof#=RED BRANCH 2,Reach-1,2
Up Type=0
Dn Type=3
Dn Slope=0.005
Boundary for River Rch & Prof#=RED BRANCH 2,Reach-1,3
Up Type=0
Dn Type=3
Dn Slope=0.005
Boundary for River Rch & Prof#=RED BRANCH 2,Reach-1,4
Up Type=0
Dn Type=3
Dn Slope=0.005
Boundary for River Rch & Prof#=RED BRANCH 2,Reach-1,5
Up Type=0
Dn Type=3
Dn Slope=0.005
Boundary for River Rch & Prof#=RED BRANCH 2,Reach-1,6
Up Type=0
Dn Type=3
Dn Slope=0.005
Boundary for River Rch & Prof#=RED BRANCH 2,Reach-1,7
Up Type=0
Dn Type=3
Dn Slope=0.005

--- RED BRANCH 2.g01 (geometry) ---

Geom Title=Existing Conditions

River Reach=RED BRANCH 2,Reach-1
Reach XY= 30
      2347725.00     13769725.00      2347867.80     13769174.70
      2347578.51     13769023.75      2347621.45     13768526.47
      2347358.73     13768107.79      2347180.41     13768027.71
      2347082.10     13767825.00      2347155.74     13767654.52
      2346768.83     13767567.14      2346541.74     13767191.63
      2346182.81     13767031.19      2346217.65     13766274.91
      2346095.17     13766144.60      2345461.24     13766061.53
      2345405.57     13765604.91      2344611.76     13765111.38
      2343828.41     13764332.82      2343235.55     13764423.90
      2342519.06     13764077.25      2342140.16     13764124.61
      2342005.02     13764024.96      2341676.55     13764028.75
      2341464.72     13764224.01      2341068.81     13764167.15
      2340938.64     13763888.44      2340582.74     13763781.55
      2340452.15     13763300.91      2340186.11     13763235.32
      2339878.61     13762723.50      2339725.00     13762175.00

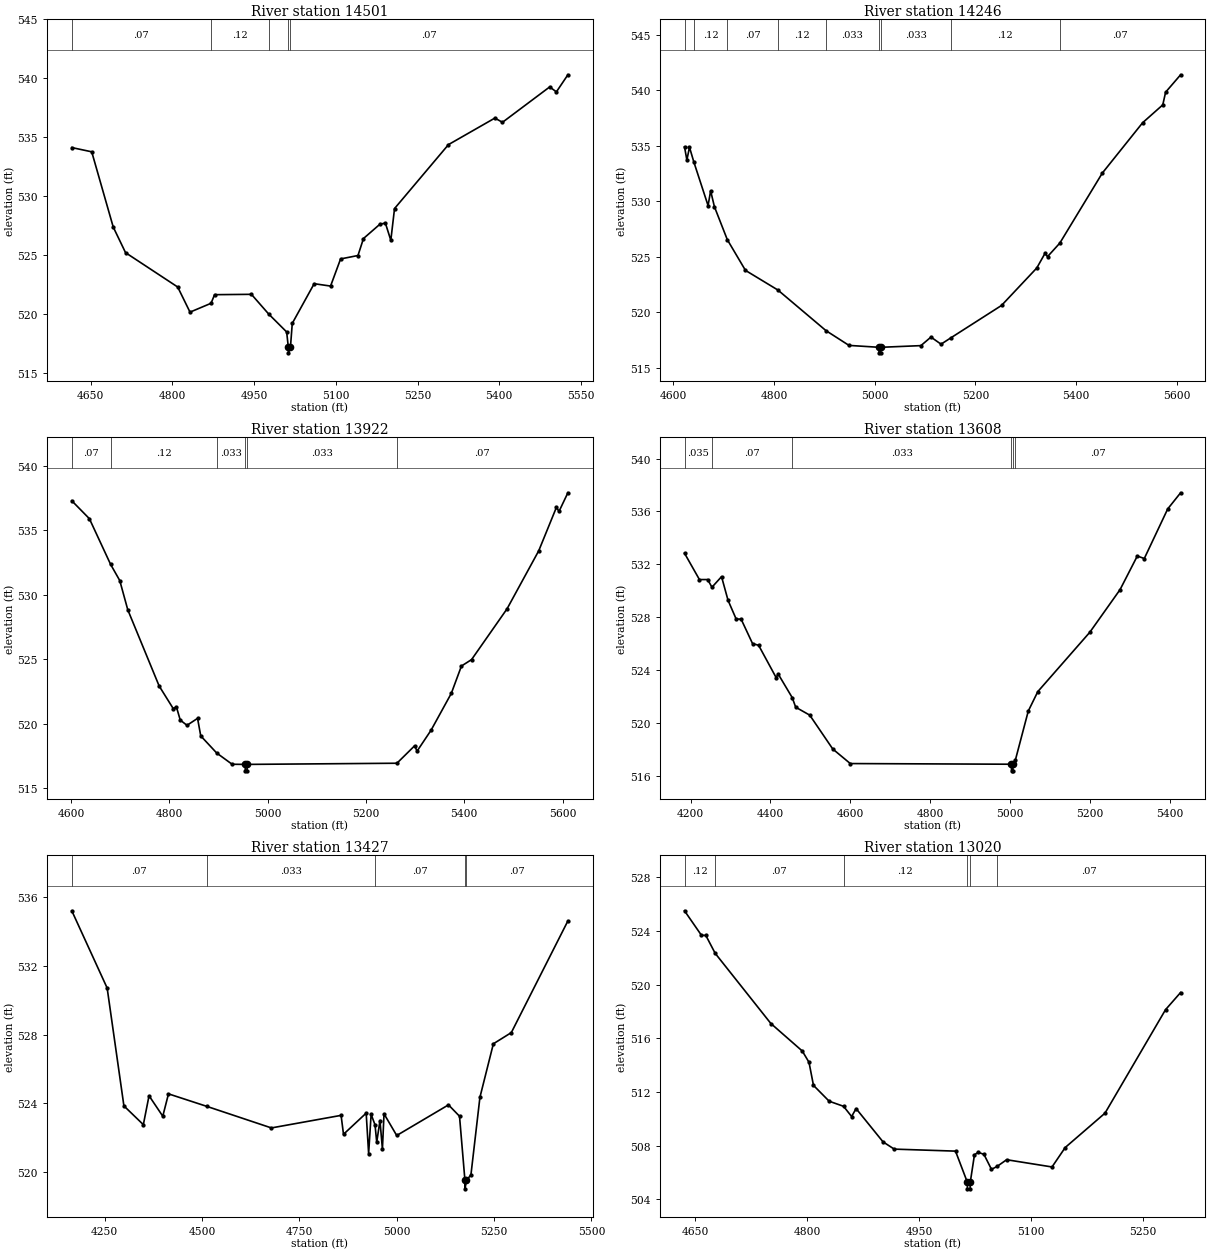
Type RM Length L Ch R = 1,14501,255,255,255
BEGIN DESCRIPTION:
RED BRANCH 2 29.0
END DESCRIPTION:
XS GIS Cut Line= 3
      2348075.00     13769825.00      2347768.85     13769676.02
      2347201.73     13769617.55
#Sta/Elev= 30
  4615.3  534.13  4651.9  533.77  4691.4  527.39  4714.0  525.22  4809.7  522.31
  4832.3  520.18  4870.9  520.93  4877.4  521.66  4945.0  521.69  4976.7  520.02
  5009.7  518.50  5012.7  517.23  5013.0  516.73  5016.7  517.23  5020.0  519.23
  5060.2  522.59  5090.3  522.39  5108.7  524.69  5140.6  524.98  5150.7  526.42
  5180.8  527.63  5190.9  527.73  5200.9  526.27  5207.7  528.96  5306.7  534.38
  5391.9  536.63  5405.8  536.27  5492.5  539.27  5504.8  538.85  5525.9  540.30
#Mann=5,-1,0
  4615.3    0.07       0  4870.9    0.12       0  4976.7    0.07       0
  5012.7    0.05       0  5016.7    0.07       0
Bank Sta=5012.7,5016.7
Exp/Cntr=0.3,0.1

Type RM Length L Ch R = 1,14246,324,324,324
BEGIN DESCRIPTION:
B20157
END DESCRIPTION:
XS GIS Cut Line= 3
      2348192.73     13769541.54      2347777.62     13769442.15
      2347219.65     13769418.78
#Sta/Elev= 30
  4622.3  534.91  4627.0  533.72  4632.2  534.87  4640.7  533.56  4669.1  529.61
  4674.2  530.94  4681.7  529.51  4707.3  526.54  4743.4  523.77  4807.8  522.00
  4903.3  518.34  4949.0  517.01  5008.5  516.84  5008.7  516.34  5012.2  516.34
  5012.5  516.84  5091.8  516.99  5111.8  517.76  5131.8  517.12  5150.9  517.68
  5251.9  520.61  5322.0  523.99  5338.2  525.30  5343.3  525.01  5367.7  526.23
  5452.1  532.54  5532.2  537.08  5572.2  538.69  5577.8  539.83  5607.6  541.40
#Mann=9,-1,0
  4622.3    0.07       0  4640.7    0.12       0  4707.3    0.07       0
  4807.8    0.12       0  4903.3   0.033       0  5008.5   0.033       0
  5012.5   0.033       0  5150.9    0.12       0  5367.7    0.07       0
Bank Sta=5008.5,5012.5
Exp/Cntr=0.3,0.1

Type RM Length L Ch R = 1,13922,314,314,314
BEGIN DESCRIPTION:
RED BRANCH 2 28.0
END DESCRIPTION:
XS GIS Cut Line= 3
      2348174.99     13769424.99      2347875.00     13769175.00
      2347274.97     13769325.01
#Sta/Elev= 30
  4601.7  537.30  4637.5  535.91  4680.6  532.37  4699.3  531.11  4715.6  528.84
  4779.4  522.93  4808.0  521.18  4814.5  521.31  4822.3  520.29  4836.0  519.88
  4857.5  520.42  4864.0  519.06  4896.5  517.73  4927.8  516.86  4954.4  516.85
  4954.7  516.35  4958.2  516.35  4958.4  516.85  5263.0  516.94  5298.9  518.29
  5304.0  517.88  5332.4  519.50  5373.6  522.36  5394.2  524.48  5414.8  524.98
  5487.0  528.92  5551.4  533.42  5587.5  536.80  5592.6  536.47  5610.7  537.92
#Mann=6,-1,0
  4601.7    0.07       0  4680.6    0.12       0  4896.5   0.033       0
  4954.4   0.033       0  4958.4   0.033       0  5263.0    0.07       0
Bank Sta=4954.4,4958.4
Exp/Cntr=0.3,0.1

Type RM Length L Ch R = 1,13608,181,181,181
BEGIN DESCRIPTION:
B20156
END DESCRIPTION:
XS GIS Cut Line= 3
      2348391.55     13768860.39      2347695.76     13769012.41
      2347204.67     13769214.11
#Sta/Elev= 30
  4184.6  532.84  4222.0  530.85  4242.5  530.85  4253.4  530.27  4277.4  531.07
  4293.7  529.28  4314.1  527.86  4326.4  527.86  4355.1  526.01  4370.3  525.88
  4414.2  523.44  4419.3  523.71  4454.6  521.92  4463.2  521.20  4498.4  520.60
  4556.1  518.04  4600.0  516.94  5003.7  516.89  5004.0  516.39  5007.5  516.39
  5007.7  516.89  5013.8  517.22  5046.0  520.91  5069.9  522.38  5200.3  526.87
  5276.0  530.09  5319.2  532.63  5336.7  532.44  5395.4  536.19  5427.7  537.41
#Mann=6,-1,0
  4184.6   0.035       0  4253.4    0.07       0  4454.6   0.033       0
  5003.7   0.033       0  5007.7   0.033       0  5013.8    0.07       0
Bank Sta=5003.7,5007.7
Exp/Cntr=0.3,0.1

Type RM Length L Ch R = 1,13427,407,407,407
BEGIN DESCRIPTION:
RED BRANCH 2 27.0
END DESCRIPTION:
XS GIS Cut Line= 3
      2348207.35     13768389.74      2347567.14     13768875.02
      2347158.92     13769108.28
#Sta/Elev= 30
  4166.0  535.20  4256.8  530.71  4299.8  523.86  4349.7  522.77  4364.3  524.45
  4399.6  523.26  4414.2  524.56  4513.0  523.83  4678.4  522.58  4857.3  523.31
  4863.5  522.21  4921.7  523.44  4928.0  521.09  4934.4  523.37  4944.4  522.76
  4948.8  521.75  4957.1  523.01  4963.4  521.35  4967.5  523.40  5000.1  522.14
  5133.0  523.92  5161.3  523.26  5175.2  519.54  5175.4  519.04  5179.2  519.54
  5190.6  519.85  5213.7  524.36  5248.2  527.47  5294.3  528.12  5439.5  534.61
#Mann=5,-1,0
  4166.0    0.07       0  4513.0   0.033       0  4944.4    0.07       0
  5175.2    0.05       0  5179.2    0.07       0
Bank Sta=5175.2,5179.2
Exp/Cntr=0.3,0.1

Type RM Length L Ch R = 1,13020,445,445,445
BEGIN DESCRIPTION:
RED BRANCH 2 26.0
END DESCRIPTION:
XS GIS Cut Line= 3
      2347925.04     13768324.98      2347625.00     13768525.00
      2347325.04     13768574.99
#Sta/Elev= 30
  4635.4  525.51  4658.0  523.69  4664.0  523.67  4676.5  522.34  4751.1  517.11
  4793.2  515.06  4802.2  514.22  4808.2  512.50  4829.2  511.32  4848.5  510.94
  4859.3  510.18  4865.3  510.77  4901.4  508.29  4916.4  507.75  4998.5  507.60
  5014.3  505.29  5014.5  504.79  5018.0  504.79  5018.3  505.29  5023.9  507.33
  5028.9  507.51  5036.6  507.36  5046.7  506.24  5054.2  506.46  5067.0  506.96
  5127.8  506.42  5145.5  507.87  5198.8  510.43  5279.9  518.14  5300.1  519.42
#Mann=6,-1,0
  4635.4    0.12       0  4676.5    0.07       0  4848.5    0.12       0
  5014.3    0.05       0  5018.3    0.12       0  5054.2    0.07       0
Bank Sta=5014.3,5018.3
Exp/Cntr=0.3,0.1

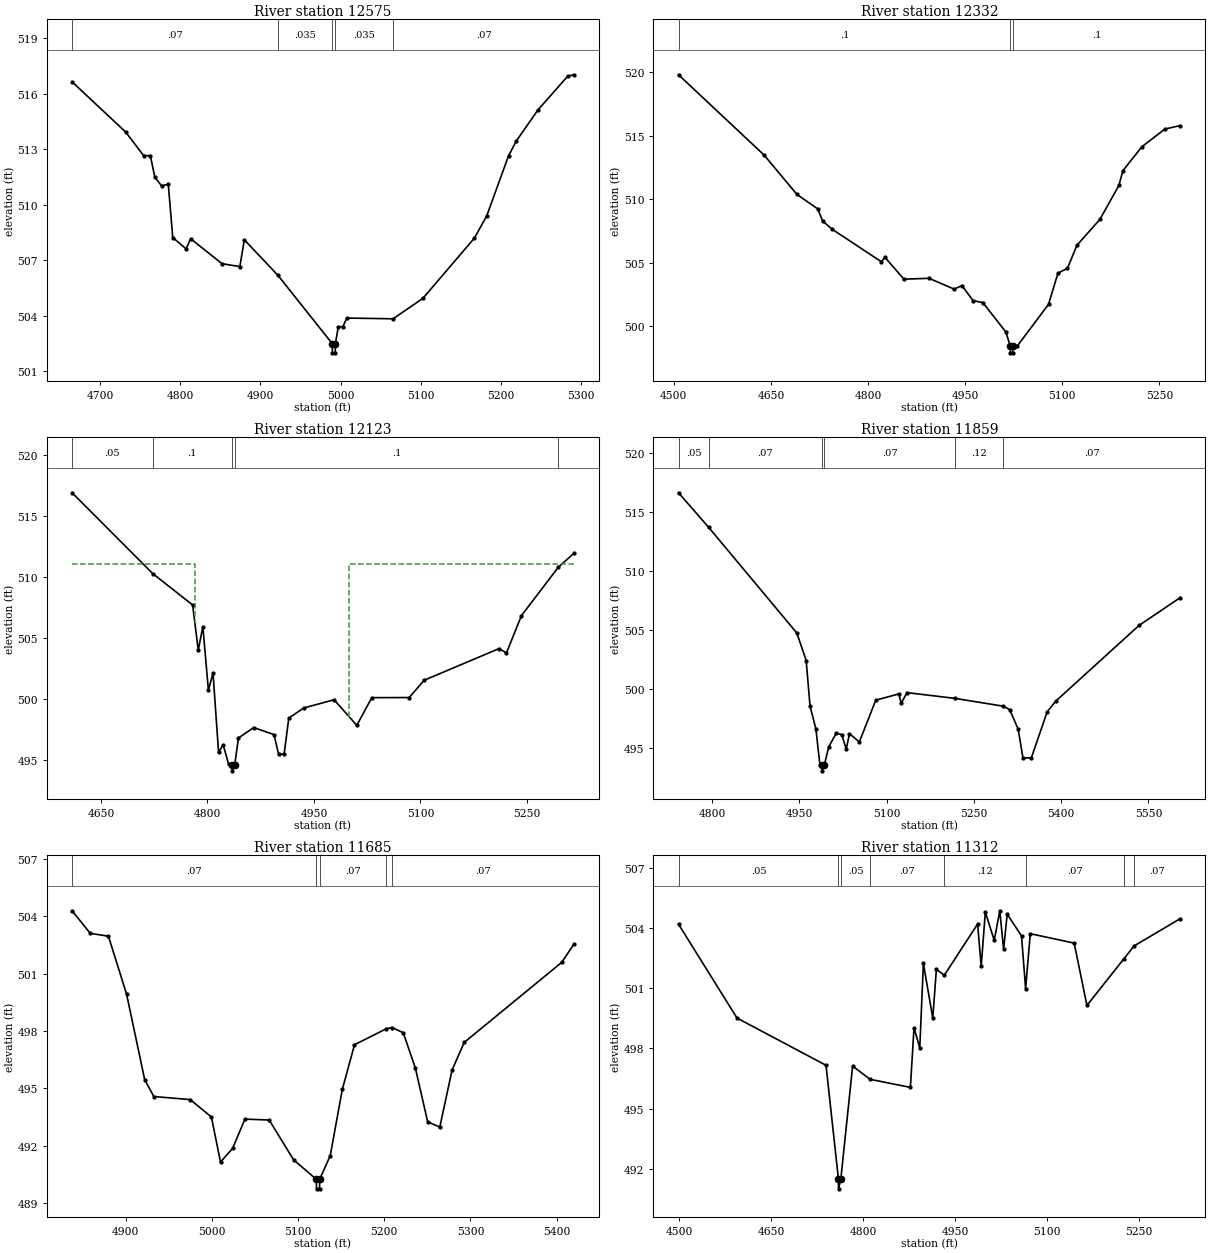
Type RM Length L Ch R = 1,12575,243,243,243
BEGIN DESCRIPTION:
RED BRANCH 2 25.0
END DESCRIPTION:
XS GIS Cut Line= 3
      2347674.99     13768025.01      2347375.00     13768175.00
      2347225.02     13768424.96
#Sta/Elev= 30
  4664.6  516.65  4731.7  513.93  4754.0  512.66  4762.4  512.66  4768.0  511.49
  4776.4  511.03  4784.8  511.11  4790.4  508.23  4807.1  507.62  4812.7  508.17
  4851.9  506.82  4874.2  506.66  4879.8  508.11  4921.8  506.19  4989.6  502.50
  4989.9  502.00  4993.4  502.00  4993.6  502.50  4997.2  503.41  5002.9  503.41
  5007.8  503.88  5065.7  503.84  5103.0  504.95  5167.2  508.20  5182.7  509.41
  5209.9  512.65  5219.6  513.45  5246.8  515.14  5283.8  516.95  5291.5  517.03
#Mann=5,-1,0
  4664.6    0.07       0  4921.8   0.035       0  4989.6   0.035       0
  4993.6   0.035       0  5065.7    0.07       0
Bank Sta=4989.6,4993.6
Exp/Cntr=0.3,0.1

Type RM Length L Ch R = 1,12332,209,209,209
BEGIN DESCRIPTION:
B20155
END DESCRIPTION:
XS GIS Cut Line= 3
      2347648.99     13767843.07      2347172.48     13768071.09
      2347026.31     13768269.88
#Sta/Elev= 30
  4507.3  519.78  4639.2  513.48  4690.1  510.38  4722.4  509.23  4729.9  508.28
  4744.5  507.64  4820.6  505.08  4826.1  505.43  4855.4  503.71  4894.1  503.78
  4933.0  502.93  4945.0  503.21  4962.1  502.03  4977.3  501.87  5013.0  499.55
  5019.7  498.42  5019.9  497.92  5023.4  497.92  5023.7  498.42  5030.1  498.43
  5078.7  501.73  5093.3  504.18  5108.0  504.57  5122.6  506.38  5158.1  508.41
  5187.4  511.08  5193.6  512.24  5222.9  514.12  5258.4  515.51  5282.3  515.79
#Mann=3,-1,0
  4507.3     0.1       0  5019.7    0.05       0  5023.7     0.1       0
Bank Sta=5019.7,5023.7
Exp/Cntr=0.3,0.1

Type RM Length L Ch R = 1,12123,264,264,264
BEGIN DESCRIPTION:
RED BRANCH 2 24.0
END DESCRIPTION:
XS GIS Cut Line= 3
      2347424.98     13767625.02      2347125.00     13767875.00
      2347025.00     13768174.99
#Sta/Elev= 30
  4609.4  516.89  4722.9  510.27  4779.2  507.69  4787.1  503.99  4793.6  505.91
  4801.4  500.70  4807.9  502.12  4815.7  495.61  4822.2  496.23  4830.0  494.61
  4834.5  494.59  4834.8  494.09  4838.5  494.59  4843.7  496.78  4865.2  497.64
  4893.8  497.06  4900.3  495.44  4908.1  495.47  4914.6  498.41  4935.5  499.24
  4978.4  499.92  5010.4  497.82  5031.5  500.09  5084.2  500.10  5105.3  501.52
  5210.7  504.11  5221.2  503.76  5242.3  506.82  5294.4  510.80  5316.1  511.92
#Mann=5,-1,0
  4609.4    0.05       0  4722.9     0.1       0  4834.5    0.05       0
  4838.5     0.1       0  5294.4   0.035       0
#XS Ineff=2,0
    0.00 4782.30  511.08 5000.10    0.00  511.08
Permanent Ineff=
       F       F
Bank Sta=4834.5,4838.5
Exp/Cntr=0.3,0.1

Type RM Length L Ch R = 1,11859,174,174,174
BEGIN DESCRIPTION:
B20154
END DESCRIPTION:
XS GIS Cut Line= 3
      2347397.56     13767553.67      2347052.62     13767720.29
      2346672.62     13768012.60
#Sta/Elev= 30
  4742.3  516.65  4793.9  513.73  4945.7  504.76  4961.7  502.43  4968.3  498.58
  4978.4  496.63  4985.3  493.60  4988.9  493.58  4989.1  493.08  4992.9  493.58
  5000.6  495.13  5013.5  496.28  5022.8  496.15  5030.5  494.91  5036.1  496.23
  5053.1  495.53  5081.3  499.07  5120.9  499.60  5125.0  498.80  5135.0  499.71
  5217.7  499.22  5300.5  498.56  5311.6  498.26  5326.1  496.61  5334.3  494.17
  5348.8  494.19  5376.0  498.09  5390.5  498.98  5533.7  505.40  5604.8  507.77
#Mann=6,-1,0
  4742.3    0.05       0  4793.9    0.07       0  4988.9    0.05       0
  4992.9    0.07       0  5217.7    0.12       0  5300.5    0.07       0
Bank Sta=4988.9,4992.9
Exp/Cntr=0.3,0.1

Type RM Length L Ch R = 1,11685,373,373,373
BEGIN DESCRIPTION:
RED BRANCH 2 23.0
END DESCRIPTION:
XS GIS Cut Line= 3
      2347175.02     13767524.99      2347025.00     13767575.00
      2346725.00     13767875.00
#Sta/Elev= 30
  4837.7  504.29  4858.8  503.11  4879.9  502.96  4901.0  499.92  4922.0  495.45
  4932.6  494.57  4974.8  494.41  4999.4  493.50  5010.0  491.14  5024.1  491.86
  5038.3  493.39  5066.5  493.34  5094.8  491.26  5121.1  490.24  5121.4  489.74
  5124.9  489.74  5125.1  490.24  5137.3  491.47  5151.4  494.95  5165.5  497.28
  5202.1  498.11  5209.1  498.18  5222.1  497.91  5236.2  496.05  5250.4  493.25
  5264.5  492.97  5278.7  495.95  5292.8  497.40  5406.0  501.59  5420.1  502.54
#Mann=5,-1,0
  4837.7    0.07       0  5121.1    0.05       0  5125.1    0.07       0
  5202.1    0.12       0  5209.1    0.07       0
Bank Sta=5121.1,5125.1
Exp/Cntr=0.3,0.1

Type RM Length L Ch R = 1,11312,477,477,477
BEGIN DESCRIPTION:
RED BRANCH 2 22.0
END DESCRIPTION:
XS GIS Cut Line= 3
      2347128.66     13767237.91      2346649.20     13767539.04
      2346497.46     13767740.39
#Sta/Elev= 30
  4498.9  504.18  4594.3  499.51  4739.4  497.16  4759.6  491.51  4759.8  491.01
  4763.6  491.51  4782.8  497.12  4811.4  496.46  4877.0  496.06  4882.9  499.03
  4892.3  498.02  4898.2  502.23  4913.5  499.51  4919.4  501.94  4932.3  501.64
  4986.6  504.19  4992.5  502.08  4999.2  504.79  5013.7  503.38  5022.8  504.85
  5029.0  502.93  5034.9  504.68  5058.2  503.60  5064.9  500.98  5072.5  503.71
  5144.1  503.24  5164.9  500.14  5224.9  502.45  5241.8  503.10  5317.2  504.46
#Mann=8,-1,0
  4498.9    0.05       0  4759.6    0.05       0  4763.6    0.05       0
  4811.4    0.07       0  4932.3    0.12       0  5064.9    0.07       0
  5224.9    0.12       0  5241.8    0.07       0
Bank Sta=4759.6,4763.6
Exp/Cntr=0.3,0.1

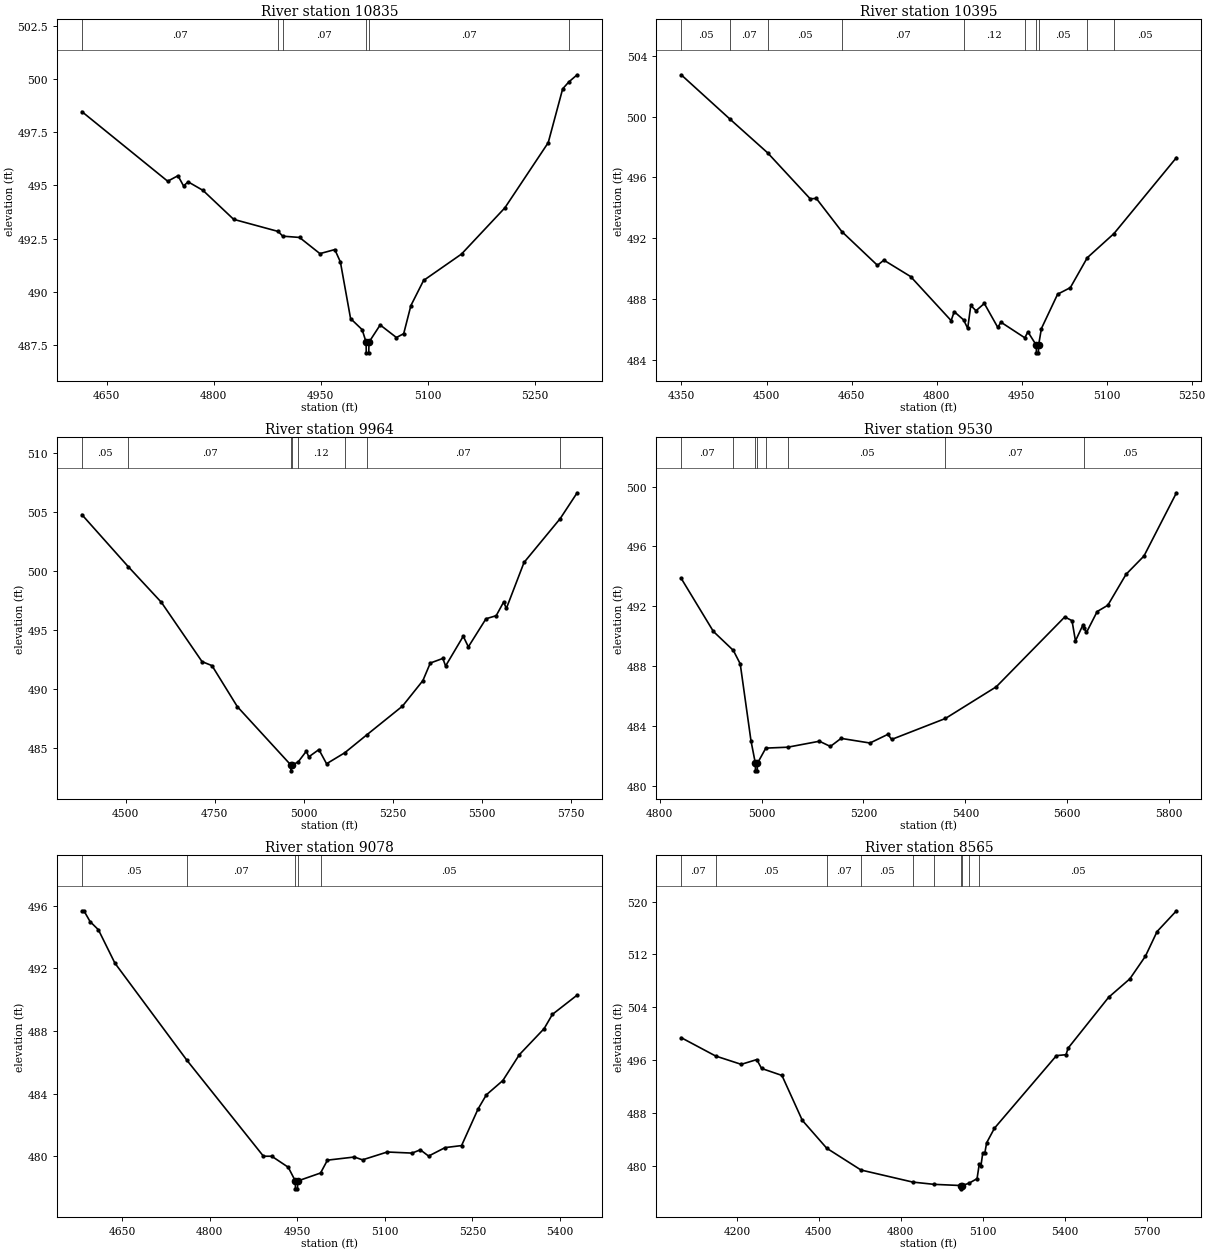
Type RM Length L Ch R = 1,10835,440,440,440
BEGIN DESCRIPTION:
RED BRANCH 2 21.0
END DESCRIPTION:
XS GIS Cut Line= 3
      2346775.03     13766924.98      2346475.00     13767175.00
      2346425.00     13767475.01
#Sta/Elev= 30
  4615.0  498.47  4735.4  495.20  4749.8  495.46  4757.6  494.98  4764.1  495.17
  4784.9  494.77  4827.9  493.41  4890.5  492.84  4896.7  492.62  4920.3  492.56
  4948.9  491.80  4969.8  491.99  4977.6  491.41  4991.9  488.75  5008.1  488.23
  5013.7  487.64  5013.9  487.14  5017.4  487.14  5017.7  487.64  5033.4  488.45
  5056.2  487.86  5066.4  488.04  5076.5  489.36  5094.3  490.54  5147.5  491.78
  5208.3  493.95  5269.1  497.01  5289.4  499.54  5297.9  499.86  5309.7  500.20
#Mann=6,-1,0
  4615.0    0.07       0  4890.5    0.12       0  4896.7    0.07       0
  5013.7    0.05       0  5017.7    0.07       0  5297.9    0.12       0
Bank Sta=5013.7,5017.7
Exp/Cntr=0.3,0.1

Type RM Length L Ch R = 1,10395,431,431,431
BEGIN DESCRIPTION:
RED BRANCH 2 20.0
END DESCRIPTION:
XS GIS Cut Line= 3
      2346775.02     13766724.99      2346175.00     13766975.00
      2345975.03     13767074.98
#Sta/Elev= 30
  4349.5  502.75  4436.2  499.81  4501.8  497.62  4577.0  494.59  4587.9  494.61
  4632.9  492.43  4695.7  490.21  4707.0  490.55  4754.2  489.47  4825.7  486.57
  4831.1  487.16  4847.6  486.62  4854.9  486.06  4860.3  487.57  4869.5  487.22
  4884.2  487.70  4908.0  486.12  4913.4  486.47  4955.6  485.44  4961.1  485.83
  4975.9  484.95  4976.1  484.45  4979.6  484.45  4979.9  484.95  4984.9  486.05
  5013.5  488.31  5035.9  488.74  5065.8  490.71  5112.9  492.30  5223.1  497.30
#Mann=10,-1,0
  4349.5    0.05       0  4436.2    0.07       0  4501.8    0.05       0
  4632.9    0.07       0  4847.6    0.12       0  4955.6    0.05       0
  4975.9    0.05       0  4979.9    0.05       0  5065.8    0.07       0
  5112.9    0.05       0
Bank Sta=4975.9,4979.9
Exp/Cntr=0.3,0.1

Type RM Length L Ch R = 1,9964,434,434,434
BEGIN DESCRIPTION:
RED BRANCH 2 19.0
END DESCRIPTION:
XS GIS Cut Line= 3
      2346825.04     13766675.01      2346225.00     13766575.00
      2345625.03     13767074.97
#Sta/Elev= 30
  4377.0  504.80  4506.9  500.40  4600.1  497.37  4714.1  492.35  4742.0  492.01
  4813.0  488.54  4963.0  483.60  4963.3  483.10  4967.0  483.60  4983.6  483.85
  5006.8  484.77  5013.3  484.28  5041.9  484.90  5063.4  483.70  5114.4  484.63
  5175.5  486.13  5276.3  488.58  5333.5  490.74  5354.4  492.23  5389.5  492.62
  5397.3  491.98  5446.8  494.50  5461.1  493.60  5510.6  495.98  5539.2  496.24
  5560.0  497.39  5567.8  496.86  5617.3  500.75  5718.9  504.47  5766.3  506.65
#Mann=8,-1,0
  4377.0    0.05       0  4506.9    0.07       0  4963.0    0.05       0
  4967.0    0.07       0  4983.6    0.12       0  5114.4    0.05       0
  5175.5    0.07       0  5718.9    0.05       0
Bank Sta=4963,4967
Exp/Cntr=0.3,0.1

Type RM Length L Ch R = 1,9530,452,452,452
BEGIN DESCRIPTION:
RED BRANCH 2 18.0
END DESCRIPTION:
XS GIS Cut Line= 3
      2346324.99     13766175.00      2346175.00     13766225.00
      2345575.04     13766774.97
#Sta/Elev= 30
  4842.3  493.87  4905.5  490.32  4944.7  489.05  4958.2  488.15  4979.3  483.01
  4987.9  481.50  4988.1  481.00  4991.6  481.00  4991.9  481.50  5008.4  482.52
  5051.3  482.58  5113.6  482.98  5135.1  482.63  5156.1  483.17  5212.8  482.86
  5248.0  483.44  5255.4  483.10  5360.8  484.50  5460.7  486.62  5595.1  491.29
  5609.3  491.04  5616.1  489.69  5630.3  490.72  5633.4  490.52  5637.7  490.25
  5658.7  491.65  5679.6  492.07  5715.4  494.14  5750.5  495.36  5814.3  499.59
#Mann=8,-1,0
  4842.3    0.07       0  4944.7    0.05       0  4987.9    0.05       0
  4991.9    0.05       0  5008.4    0.07       0  5051.3    0.05       0
  5360.8    0.07       0  5633.4    0.05       0
Bank Sta=4987.9,4991.9
Exp/Cntr=0.3,0.1

Type RM Length L Ch R = 1,9078,513,513,513
BEGIN DESCRIPTION:
RED BRANCH 2 17.0
END DESCRIPTION:
XS GIS Cut Line= 3
      2346074.99     13765775.01      2345775.00     13766075.00
      2345475.01     13766374.99
#Sta/Elev= 30
  4581.0  495.67  4584.5  495.67  4595.1  494.98  4609.3  494.46  4637.6  492.33
  4760.8  486.14  4892.1  480.01  4906.3  480.01  4934.5  479.31  4946.7  478.43
  4946.9  477.93  4950.4  477.93  4950.7  478.43  4989.9  478.94  5001.7  479.76
  5047.7  479.96  5061.8  479.78  5104.2  480.28  5146.7  480.21  5160.8  480.42
  5175.0  480.02  5203.2  480.56  5231.5  480.69  5259.8  483.03  5274.0  483.93
  5302.2  484.84  5330.5  486.49  5372.9  488.15  5387.1  489.06  5429.5  490.29
#Mann=5,-1,0
  4581.0    0.05       0  4760.8    0.07       0  4946.7    0.05       0
  4950.7    0.07       0  4989.9    0.05       0
Bank Sta=4946.7,4950.7
Exp/Cntr=0.3,0.1

Type RM Length L Ch R = 1,8565,460,460,460
BEGIN DESCRIPTION:
RED BRANCH 2 16.0
END DESCRIPTION:
XS GIS Cut Line= 3
      2346315.89     13765526.68      2345479.33     13765909.68
      2344894.78     13766584.94
#Sta/Elev= 30
  3996.3  499.40  4122.5  496.62  4216.1  495.36  4273.1  496.08  4290.6  494.74
  4365.2  493.68  4439.7  486.89  4529.1  482.67  4654.5  479.37  4844.3  477.54
  4921.8  477.20  5020.5  477.02  5020.7  476.52  5024.5  477.02  5050.1  477.37
  5079.5  478.06  5087.4  480.22  5093.7  480.02  5100.3  481.90  5108.0  481.96
  5114.6  483.49  5143.1  485.69  5370.1  496.68  5405.2  496.82  5412.8  497.81
  5561.0  505.50  5638.9  508.30  5695.9  511.73  5738.6  515.46  5809.5  518.60
#Mann=10,-1,0
  3996.3    0.07       0  4122.5    0.05       0  4529.1    0.07       0
  4654.5    0.05       0  4844.3    0.07       0  4921.8    0.05       0
  5020.5    0.05       0  5024.5    0.05       0  5050.1    0.07       0
  5087.4    0.05       0
Bank Sta=5020.5,5024.5
Exp/Cntr=0.3,0.1

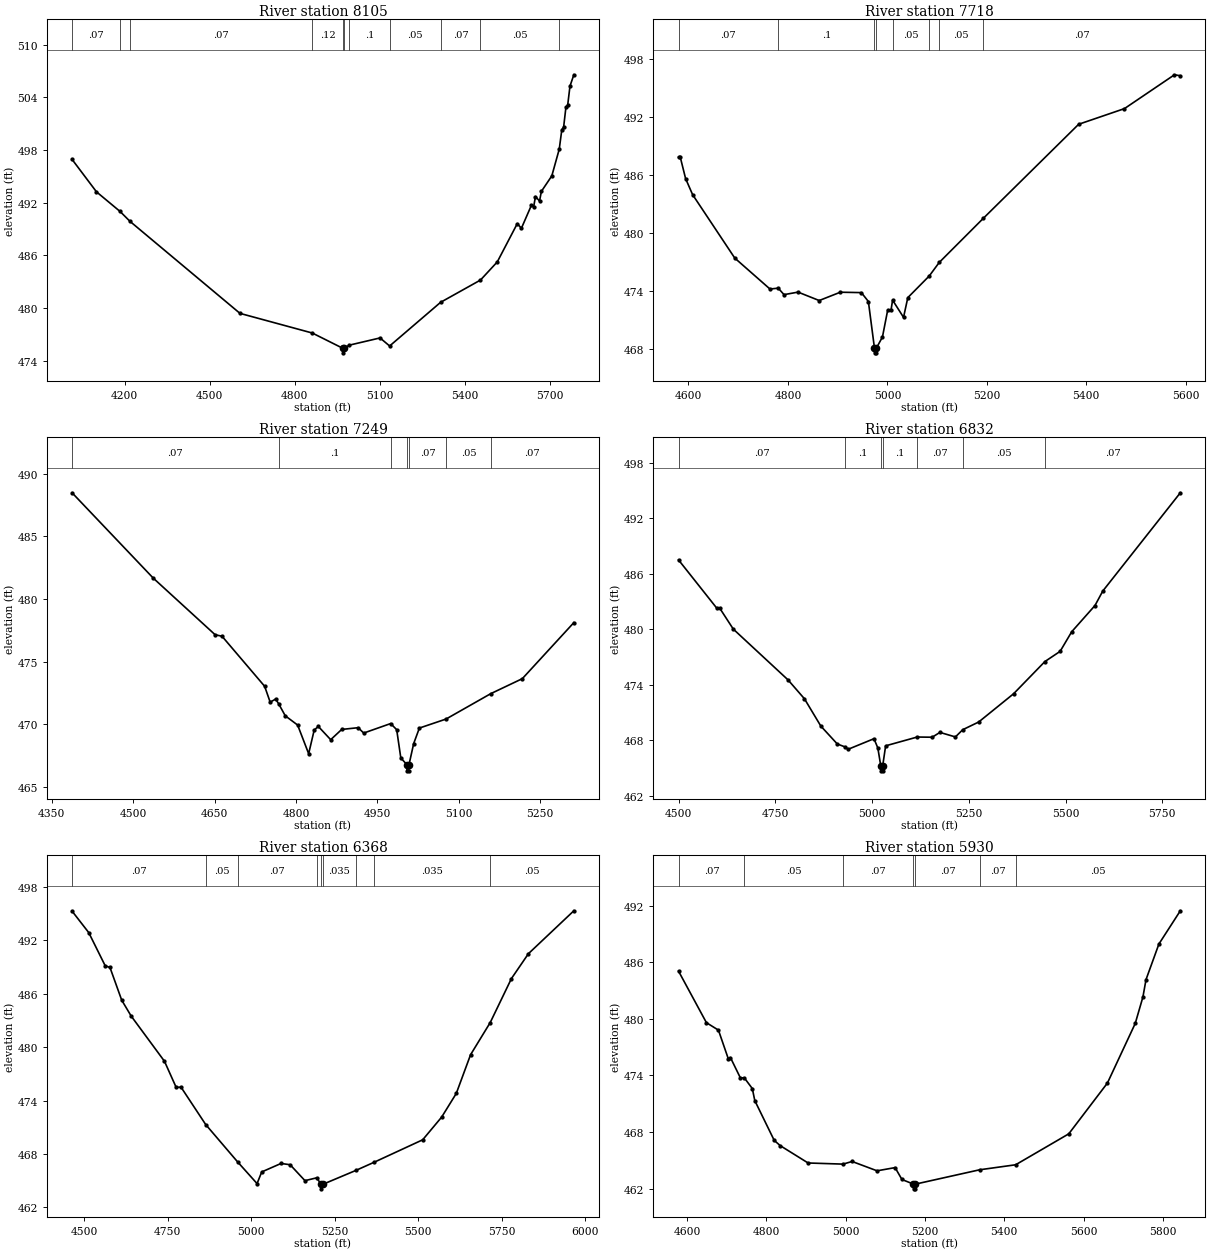
Type RM Length L Ch R = 1,8105,387,387,387
BEGIN DESCRIPTION:
RED BRANCH 2 15.0
END DESCRIPTION:
XS GIS Cut Line= 3
      2346315.86     13765456.14      2345418.85     13765496.45
      2344875.01     13766174.99
#Sta/Elev= 30
  4015.2  496.94  4101.2  493.24  4184.4  491.00  4219.4  489.87  4606.7  479.38
  4861.4  477.14  4970.1  475.38  4970.3  474.88  4974.1  475.38  4990.9  475.75
  5100.1  476.58  5133.8  475.66  5313.3  480.64  5453.8  483.18  5513.0  485.25
  5583.5  489.62  5597.9  489.08  5633.1  491.70  5641.1  491.53  5647.5  492.70
  5661.9  492.19  5668.3  493.29  5705.1  495.06  5731.3  498.11  5740.3  500.32
  5746.7  500.62  5754.7  502.86  5761.1  503.15  5769.1  505.30  5782.7  506.59
#Mann=11,-1,0
  4015.2    0.07       0  4184.4    0.12       0  4219.4    0.07       0
  4861.4    0.12       0  4970.1    0.05       0  4974.1    0.12       0
  4990.9     0.1       0  5133.8    0.05       0  5313.3    0.07       0
  5453.8    0.05       0  5731.3    0.07       0
Bank Sta=4970.1,4974.1
Exp/Cntr=0.3,0.1

Type RM Length L Ch R = 1,7718,469,469,469
BEGIN DESCRIPTION:
RED BRANCH 2 14.0
END DESCRIPTION:
XS GIS Cut Line= 3
      2345325.01     13765124.99      2345025.00     13765425.00
      2344683.10     13765899.60
#Sta/Elev= 30
  4580.0  487.79  4583.5  487.79  4594.2  485.58  4608.3  483.92  4693.1  477.36
  4763.9  474.16  4780.5  474.25  4792.1  473.58  4820.4  473.84  4862.9  472.97
  4905.3  473.83  4947.7  473.79  4961.8  472.87  4974.0  468.06  4974.2  467.56
  4977.7  467.56  4978.0  468.06  4990.1  469.20  5000.7  472.00  5007.4  472.00
  5010.5  473.01  5032.5  471.23  5041.1  473.27  5084.2  475.51  5104.3  476.91
  5193.3  481.49  5384.7  491.20  5476.8  492.82  5577.4  496.32  5589.2  496.22
#Mann=8,-1,0
  4580.0    0.07       0  4780.5     0.1       0  4974.0    0.05       0
  4978.0     0.1       0  5010.5    0.05       0  5084.2    0.07       0
  5104.3    0.05       0  5193.3    0.07       0
Bank Sta=4974,4978
Exp/Cntr=0.3,0.1

Type RM Length L Ch R = 1,7249,417,417,417
BEGIN DESCRIPTION:
RED BRANCH 2 13.0
END DESCRIPTION:
XS GIS Cut Line= 3
      2344775.00     13764525.01      2344675.00     13765125.00
      2344575.00     13765425.00
#Sta/Elev= 30
  4387.4  488.49  4536.9  481.67  4651.0  477.14  4663.7  477.02  4742.2  473.02
  4752.4  471.75  4762.5  472.00  4767.9  471.63  4780.2  470.66  4803.0  469.92
  4823.3  467.63  4833.5  469.52  4841.1  469.81  4863.9  468.75  4884.2  469.57
  4914.6  469.71  4924.7  469.28  4974.4  470.04  4985.5  469.55  4993.1  467.29
  5004.2  466.76  5004.5  466.26  5008.0  466.26  5008.2  466.76  5016.8  468.44
  5027.3  469.68  5076.4  470.40  5158.8  472.43  5217.0  473.63  5311.9  478.11
#Mann=7,-1,0
  4387.4    0.07       0  4767.9     0.1       0  4974.4    0.07       0
  5004.2    0.05       0  5008.2    0.07       0  5076.4    0.05       0
  5158.8    0.07       0
Bank Sta=5004.2,5008.2
Exp/Cntr=0.3,0.1

Type RM Length L Ch R = 1,6832,464,464,464
BEGIN DESCRIPTION:
RED BRANCH 2 12.0
END DESCRIPTION:
XS GIS Cut Line= 3
      2344725.02     13764524.98      2344375.00     13764875.00
      2344325.00     13765675.04
#Sta/Elev= 30
  4500.1  487.49  4599.1  482.27  4606.2  482.30  4641.6  480.02  4783.0  474.54
  4825.4  472.50  4867.8  469.55  4910.3  467.62  4929.9  467.31  4938.5  467.05
  5005.1  468.19  5015.1  467.18  5022.8  465.22  5023.2  464.72  5027.2  464.72
  5027.5  465.22  5035.2  467.42  5116.8  468.37  5155.4  468.35  5175.5  468.87
  5215.5  468.38  5234.4  469.16  5275.6  469.99  5365.8  473.04  5446.8  476.52
  5486.1  477.62  5516.1  479.74  5576.2  482.57  5596.3  484.13  5796.7  494.74
#Mann=7,-1,0
  4500.1    0.07       0  4929.9     0.1       0  5022.8    0.05       0
  5027.5     0.1       0  5116.8    0.07       0  5234.4    0.05       0
  5446.8    0.07       0
Bank Sta=5022.8,5027.5
Exp/Cntr=0.3,0.1

Type RM Length L Ch R = 1,6368,438,438,438
BEGIN DESCRIPTION:
RED BRANCH 2 11.0
END DESCRIPTION:
XS GIS Cut Line= 3
      2344475.02     13764124.98      2344125.00     13764525.00
      2343574.98     13765325.03
#Sta/Elev= 30
  4463.3  495.28  4513.2  492.87  4562.5  489.14  4576.8  488.95  4611.9  485.28
  4640.3  483.49  4740.0  478.41  4775.1  475.47  4789.4  475.51  4863.5  471.30
  4958.9  467.11  5017.2  464.67  5031.2  465.98  5088.9  466.93  5116.2  466.79
  5160.6  465.00  5196.0  465.32  5208.9  464.58  5209.3  464.08  5213.7  464.58
  5313.1  466.15  5366.7  467.05  5513.1  469.59  5569.9  472.14  5613.7  474.80
  5656.5  479.15  5715.3  482.76  5778.9  487.71  5829.7  490.50  5965.7  495.32
#Mann=9,-1,0
  4463.3    0.07       0  4863.5    0.05       0  4958.9    0.07       0
  5196.0   0.035       0  5208.9    0.05       0  5213.7   0.035       0
  5313.1    0.07       0  5366.7   0.035       0  5715.3    0.05       0
Bank Sta=5208.9,5213.7
Exp/Cntr=0.3,0.1

Type RM Length L Ch R = 1,5930,435,435,435
BEGIN DESCRIPTION:
RED BRANCH 2 10.0
END DESCRIPTION:
XS GIS Cut Line= 3
      2343925.01     13763974.97      2343775.00     13764375.00
      2343524.99     13765175.02
#Sta/Elev= 30
  4578.7  485.05  4649.0  479.59  4679.3  478.80  4704.2  475.76  4709.6  475.89
  4734.5  473.75  4744.6  473.74  4764.7  472.61  4771.0  471.33  4819.9  467.12
  4835.0  466.56  4905.4  464.72  4993.5  464.60  5016.4  464.88  5079.3  463.89
  5124.8  464.23  5142.1  462.97  5171.2  462.48  5171.5  461.98  5175.6  461.98
  5176.0  462.48  5338.1  464.00  5428.8  464.53  5562.8  467.81  5660.2  473.19
  5730.4  479.51  5749.8  482.32  5757.6  484.16  5790.1  487.93  5844.1  491.45
#Mann=7,-1,0
  4578.7    0.07       0  4744.6    0.05       0  4993.5    0.07       0
  5171.2    0.05       0  5176.0    0.07       0  5338.1    0.07       0
  5428.8    0.05       0
Bank Sta=5171.2,5176
Exp/Cntr=0.3,0.1

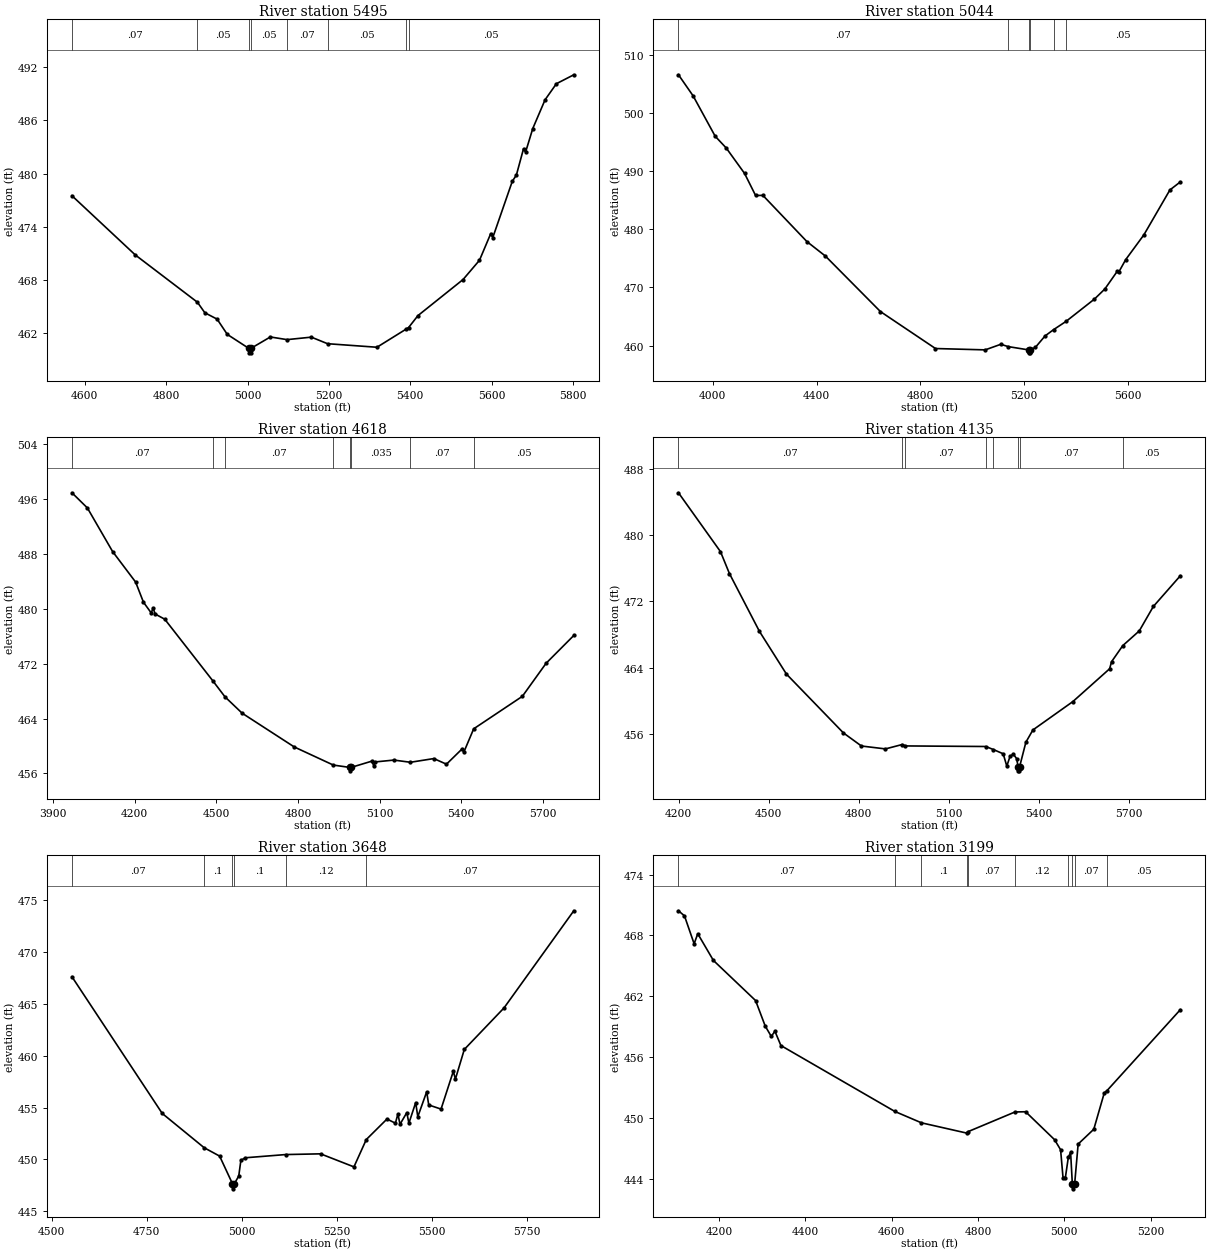
Type RM Length L Ch R = 1,5495,451,451,451
BEGIN DESCRIPTION:
RED BRANCH 2 9.0
END DESCRIPTION:
XS GIS Cut Line= 3
      2343524.98     13763975.04      2343375.00     13764375.00
      2343475.00     13765175.02
#Sta/Elev= 30
  4568.5  477.50  4724.2  470.82  4876.8  465.49  4895.1  464.30  4925.3  463.58
  4950.3  461.86  5003.3  460.28  5003.6  459.78  5007.8  459.78  5008.2  460.28
  5056.1  461.57  5097.1  461.27  5156.9  461.55  5196.7  460.81  5318.1  460.41
  5389.6  462.45  5395.8  462.63  5418.9  463.98  5529.8  468.05  5570.1  470.22
  5597.8  473.23  5602.8  472.78  5650.7  479.12  5660.8  479.83  5678.4  482.81
  5683.5  482.43  5701.1  485.08  5731.3  488.32  5759.1  490.13  5801.9  491.14
#Mann=8,-1,0
  4568.5    0.07       0  4876.8    0.05       0  5003.3    0.05       0
  5008.2    0.05       0  5097.1    0.07       0  5196.7    0.05       0
  5389.6    0.07       0  5395.8    0.05       0
Bank Sta=5003.3,5008.2
Exp/Cntr=0.3,0.1

Type RM Length L Ch R = 1,5044,426,426,426
BEGIN DESCRIPTION:
RED BRANCH 2 8.0
END DESCRIPTION:
XS GIS Cut Line= 3
      2343774.98     13763525.02      2342975.00     13764325.00
      2342925.00     13765125.00
#Sta/Elev= 30
  3868.3  506.53  3924.8  502.90  4009.7  495.97  4052.1  493.96  4122.8  489.59
  4165.3  485.80  4193.5  485.81  4363.2  477.87  4434.0  475.40  4646.1  465.86
  4858.2  459.51  5049.7  459.28  5109.9  460.24  5138.3  459.84  5217.6  459.27
  5218.0  458.77  5222.2  458.77  5222.5  459.27  5242.6  459.69  5280.2  461.67
  5312.9  462.75  5360.7  464.16  5470.6  468.01  5510.6  469.74  5558.2  472.77
  5563.2  472.57  5590.8  474.78  5660.9  479.04  5761.1  486.75  5801.2  488.13
#Mann=6,-1,0
  3868.3    0.07       0  5138.3    0.05       0  5217.6    0.05       0
  5222.5    0.05       0  5312.9    0.07       0  5360.7    0.05       0
Bank Sta=5217.6,5222.5
Exp/Cntr=0.3,0.1

Type RM Length L Ch R = 1,4618,483,483,483
BEGIN DESCRIPTION:
RED BRANCH 2 7.0
END DESCRIPTION:
XS GIS Cut Line= 3
      2343274.99     13763325.01      2342625.00     13764125.00
      2342775.00     13764924.99
#Sta/Elev= 30
  3969.3  496.94  4026.0  494.73  4118.7  488.37  4203.4  483.91  4232.2  480.97
  4260.9  479.40  4267.4  480.14  4275.3  479.25  4310.5  478.49  4486.8  469.52
  4531.8  467.17  4594.9  464.78  4786.7  459.85  4930.2  457.21  4990.4  456.87
  4990.8  456.37  4995.4  456.87  5071.3  457.78  5078.9  457.11  5084.0  457.67
  5152.7  457.94  5213.5  457.62  5299.4  458.16  5346.0  457.34  5404.5  459.61
  5409.6  459.08  5446.0  462.50  5624.9  467.24  5712.3  472.07  5814.0  476.12
#Mann=8,-1,0
  3969.3    0.07       0  4486.8   0.035       0  4531.8    0.07       0
  4930.2   0.035       0  4990.4   0.035       0  4995.4   0.035       0
  5213.5    0.07       0  5446.0    0.05       0
Bank Sta=4990.4,4995.4
Exp/Cntr=0.3,0.1

Type RM Length L Ch R = 1,4135,487,487,487
BEGIN DESCRIPTION:
RED BRANCH 2 6.0
END DESCRIPTION:
XS GIS Cut Line= 3
      2342175.00     13763324.98      2342175.00     13764125.00
      2341825.01     13764924.97
#Sta/Elev= 30
  4199.5  485.12  4339.5  478.01  4369.5  475.35  4469.5  468.37  4559.5  463.21
  4749.5  456.10  4809.5  454.52  4889.5  454.17  4945.4  454.70  4956.3  454.53
  5224.0  454.46  5249.7  454.09  5282.1  453.58  5294.2  452.09  5305.1  453.29
  5316.4  453.52  5327.0  452.99  5331.8  452.02  5332.2  451.52  5336.5  451.52
  5336.9  452.02  5357.8  454.98  5381.2  456.46  5514.5  459.89  5636.9  463.85
  5643.5  464.71  5680.8  466.65  5735.9  468.43  5782.7  471.38  5872.7  475.09
#Mann=8,-1,0
  4199.5    0.07       0  4945.4   0.035       0  4956.3    0.07       0
  5224.0    0.12       0  5249.7    0.07       0  5331.8    0.05       0
  5336.9    0.07       0  5680.8    0.05       0
Bank Sta=5331.8,5336.9
Exp/Cntr=0.3,0.1

Type RM Length L Ch R = 1,3648,449,449,449
BEGIN DESCRIPTION:
RED BRANCH 2 5.0
END DESCRIPTION:
XS GIS Cut Line= 3
      2341925.02     13763624.97      2341725.00     13764025.00
      2341374.98     13764825.04
#Sta/Elev= 30
  4553.2  467.63  4790.8  454.43  4901.1  451.12  4941.8  450.31  4975.5  447.65
  4975.9  447.15  4980.7  447.65  4992.1  448.39  4997.7  449.90  5009.4  450.15
  5115.5  450.46  5207.4  450.53  5295.2  449.27  5327.7  451.91  5382.1  453.89
  5404.3  453.49  5410.9  454.38  5416.4  453.38  5434.3  454.51  5439.8  453.49
  5457.7  455.48  5463.2  454.11  5486.6  456.52  5492.0  455.25  5524.4  454.85
  5556.7  458.50  5562.2  457.75  5585.6  460.61  5690.1  464.62  5873.7  474.00
#Mann=6,-1,0
  4553.2    0.07       0  4901.1     0.1       0  4975.5    0.05       0
  4980.7     0.1       0  5115.5    0.12       0  5327.7    0.07       0
Bank Sta=4975.5,4980.7
Exp/Cntr=0.3,0.1

Type RM Length L Ch R = 1,3199,456,456,456
BEGIN DESCRIPTION:
RED BRANCH 2 4.0
END DESCRIPTION:
XS GIS Cut Line= 3
      2341774.98     13763425.04      2341375.00     13764225.00
      2341275.02     13764474.96
#Sta/Elev= 30
  4105.5  470.43  4119.4  469.93  4141.8  467.18  4150.2  468.17  4186.5  465.54
  4284.3  461.59  4306.7  459.07  4320.7  458.06  4329.1  458.57  4343.0  457.16
  4607.2  450.67  4668.9  449.55  4773.8  448.54  4777.4  448.69  4885.8  450.62
  4910.4  450.64  4977.5  447.89  4991.5  446.90  4997.1  444.16  5002.6  444.16
  5009.4  446.15  5014.7  446.65  5018.7  443.55  5019.1  443.05  5024.1  443.55
  5032.2  447.46  5068.5  448.92  5092.8  452.50  5099.3  452.73  5269.1  460.69
#Mann=10,-1,0
  4105.5    0.07       0  4607.2    0.12       0  4668.9     0.1       0
  4773.8    0.12       0  4777.4    0.07       0  4885.8    0.12       0
  5009.4    0.07       0  5018.7    0.05       0  5024.1    0.07       0
  5099.3    0.05       0
Bank Sta=5018.7,5024.1
Exp/Cntr=0.3,0.1