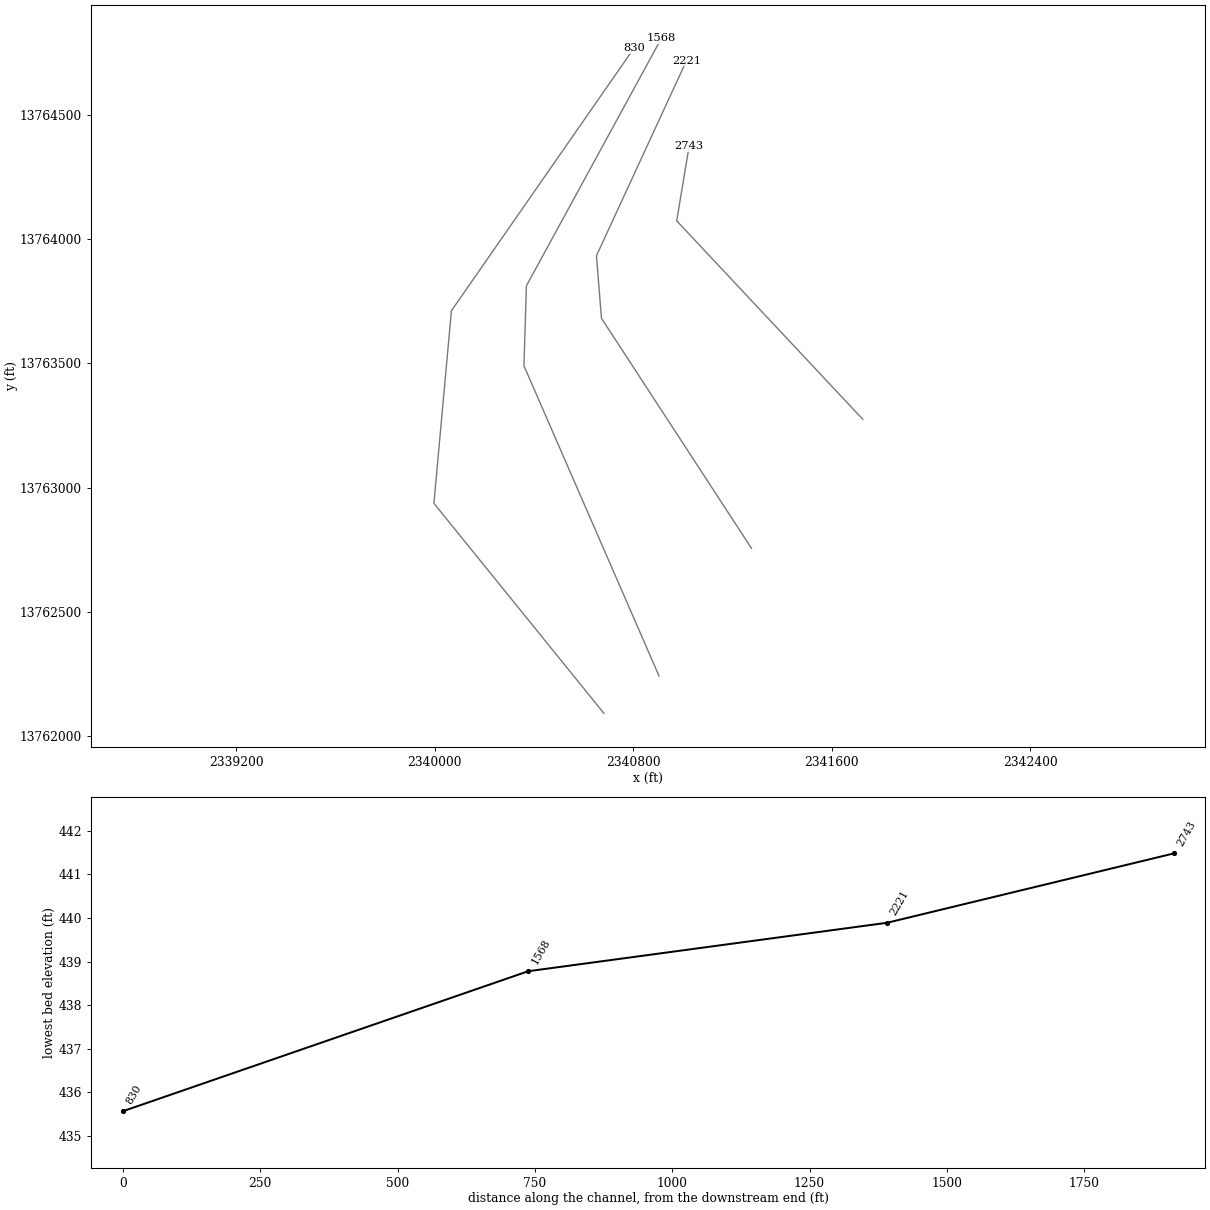
HEC-RAS study RED BRANCH 2.prj: RED BRANCH 2 Base Level Engineering

--- RED BRANCH 2.g01 (geometry) --- (continued)

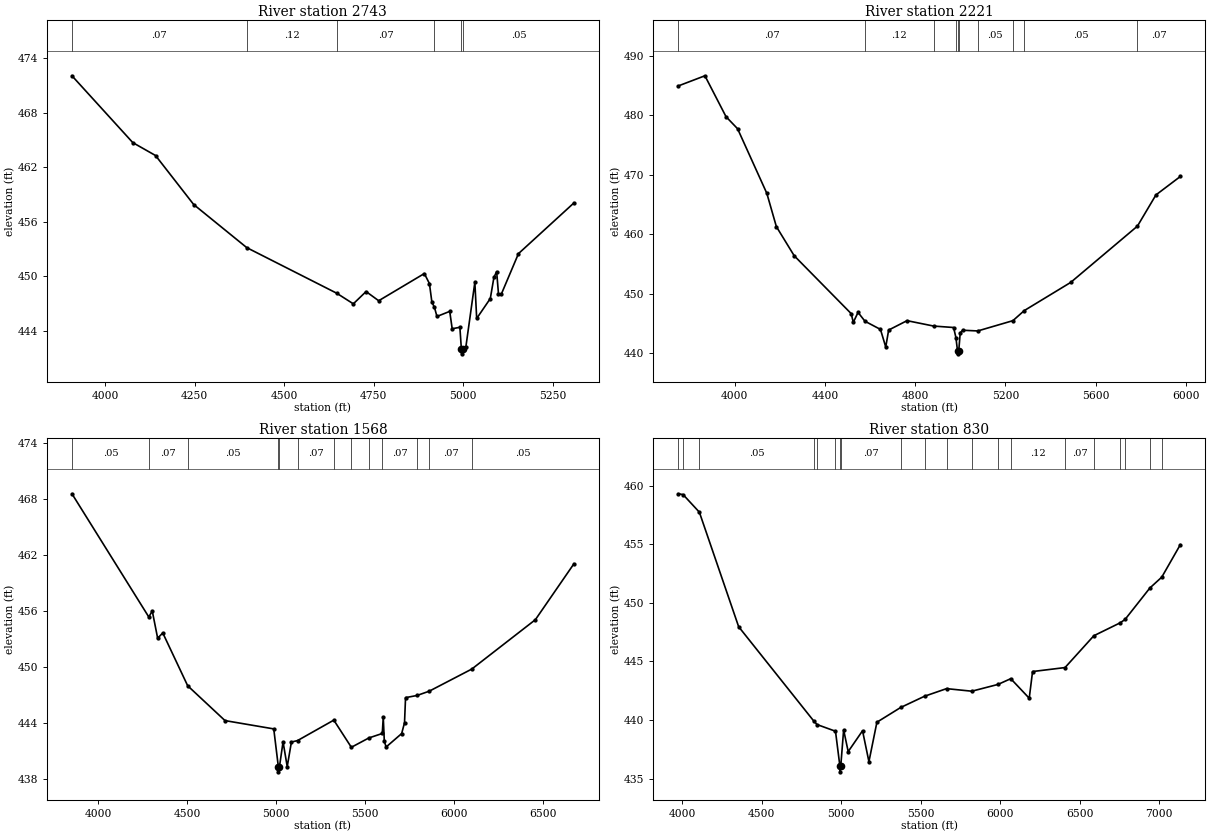
Type RM Length L Ch R = 1,2743,522,522,522
BEGIN DESCRIPTION:
RED BRANCH 2 3.0
END DESCRIPTION:
XS GIS Cut Line= 3
      2341725.03     13763274.96      2340975.00     13764075.00
      2341025.00     13764375.03
#Sta/Elev= 30
  3907.7  472.06  4077.5  464.71  4141.0  463.29  4247.5  457.90  4395.6  453.16
  4646.5  448.15  4693.0  446.98  4728.6  448.33  4763.8  447.32  4891.2  450.31
  4905.4  449.21  4912.3  447.16  4919.4  446.60  4926.4  445.59  4962.1  446.15
  4968.9  444.24  4990.4  444.40  4994.6  441.98  4995.0  441.48  5000.0  441.98
  5006.9  442.18  5032.2  449.35  5037.3  445.37  5075.3  447.56  5085.4  449.89
  5093.0  450.52  5098.1  448.10  5105.7  448.01  5153.9  452.50  5308.5  458.07
#Mann=6,-1,0
  3907.7    0.07       0  4395.6    0.12       0  4646.5    0.07       0
  4919.4    0.05       0  4994.6    0.05       0  5000.0    0.05       0
Bank Sta=4994.6,5000
Exp/Cntr=0.3,0.1

Type RM Length L Ch R = 1,2221,653,653,653
BEGIN DESCRIPTION:
B20153
END DESCRIPTION:
XS GIS Cut Line= 4
      2341276.44     13762754.98      2340671.70     13763682.25
      2340651.54     13763934.22      2341014.31     13764720.22
#Sta/Elev= 30
  3750.0  484.96  3867.5  486.66  3961.1  479.78  4012.4  477.75  4142.1  466.88
  4184.3  461.29  4263.4  456.39  4516.2  446.65  4525.4  445.18  4546.5  446.86
  4577.3  445.37  4645.9  444.00  4669.3  441.04  4682.2  443.89  4763.7  445.47
  4882.0  444.56  4970.2  444.32  4980.5  442.62  4987.5  440.39  4987.9  439.89
  4993.0  440.39  4999.5  443.40  5010.3  443.86  5077.2  443.74  5233.2  445.47
  5283.4  447.16  5489.3  451.90  5785.3  461.37  5867.4  466.62  5975.5  469.72
#Mann=10,-1,0
  3750.0    0.07       0  4577.3    0.12       0  4882.0    0.07       0
  4980.5    0.12       0  4987.5    0.05       0  4993.0    0.12       0
  5077.2    0.05       0  5233.2    0.07       0  5283.4    0.05       0
  5785.3    0.07       0
Bank Sta=4987.5,4993
Exp/Cntr=0.3,0.1

Type RM Length L Ch R = 1,1568,738,738,738
BEGIN DESCRIPTION:
B20152
END DESCRIPTION:
XS GIS Cut Line= 4
      2340903.53     13762240.94      2340359.25     13763490.75
      2340369.33     13763813.28      2340913.28     13764810.51
#Sta/Elev= 30
  3851.6  468.57  4283.7  455.37  4303.2  456.01  4333.4  453.10  4362.3  453.66
  4502.3  448.00  4712.1  444.27  4986.2  443.38  5012.3  439.28  5012.7  438.78
  5017.9  439.28  5038.5  441.99  5061.9  439.34  5085.4  441.97  5120.0  442.13
  5323.8  444.32  5422.4  441.41  5520.9  442.41  5596.3  442.89  5601.8  444.63
  5607.8  442.06  5617.9  441.44  5705.3  442.88  5721.4  444.04  5727.1  446.73
  5791.5  446.96  5860.2  447.42  6099.5  449.79  6457.1  455.08  6673.4  461.06
#Mann=13,-1,0
  3851.6    0.05       0  4283.7    0.07       0  4502.3    0.05       0
  5012.3    0.05       0  5017.9    0.05       0  5120.0    0.07       0
  5323.8    0.12       0  5422.4     0.1       0  5520.9    0.12       0
  5596.3    0.07       0  5791.5    0.05       0  5860.2    0.07       0
  6099.5    0.05       0
Bank Sta=5012.3,5017.9
Exp/Cntr=0.3,0.1

Type RM Length L Ch R = 1,830,0,0,0
BEGIN DESCRIPTION:
B20151
END DESCRIPTION:
XS GIS Cut Line= 4
      2340681.80     13762089.77      2339996.41     13762936.41
      2340066.97     13763712.49      2340802.45     13764770.37
#Sta/Elev= 30
  3975.1  459.33  4004.5  459.26  4106.8  457.76  4354.0  447.97  4825.4  439.93
  4847.1  439.61  4963.1  439.04  4990.7  436.07  4991.1  435.57  4996.3  436.07
  5014.3  439.15  5043.0  437.30  5133.3  439.08  5173.4  436.44  5223.6  439.81
  5373.3  441.07  5523.2  442.03  5661.8  442.68  5820.5  442.46  5985.5  443.04
  6065.5  443.53  6181.7  441.86  6202.7  444.14  6406.9  444.48  6588.2  447.20
  6753.4  448.30  6784.4  448.59  6940.7  451.28  7015.6  452.21  7132.1  454.98
#Mann=20,-1,0
  3975.1    0.05       0  4004.5    0.07       0  4106.8    0.05       0
  4825.4    0.07       0  4847.1    0.05       0  4963.1    0.07       0
  4990.7    0.05       0  4996.3    0.07       0  5373.3    0.05       0
  5523.2    0.12       0  5661.8     0.1       0  5820.5    0.12       0
  5985.5    0.05       0  6065.5    0.12       0  6406.9    0.07       0
  6588.2    0.05       0  6753.4    0.07       0  6784.4    0.05       0
  6940.7    0.07       0  7015.6    0.05       0
Bank Sta=4990.7,4996.3
Exp/Cntr=0.3,0.1

Chan Stop Cuts=-1