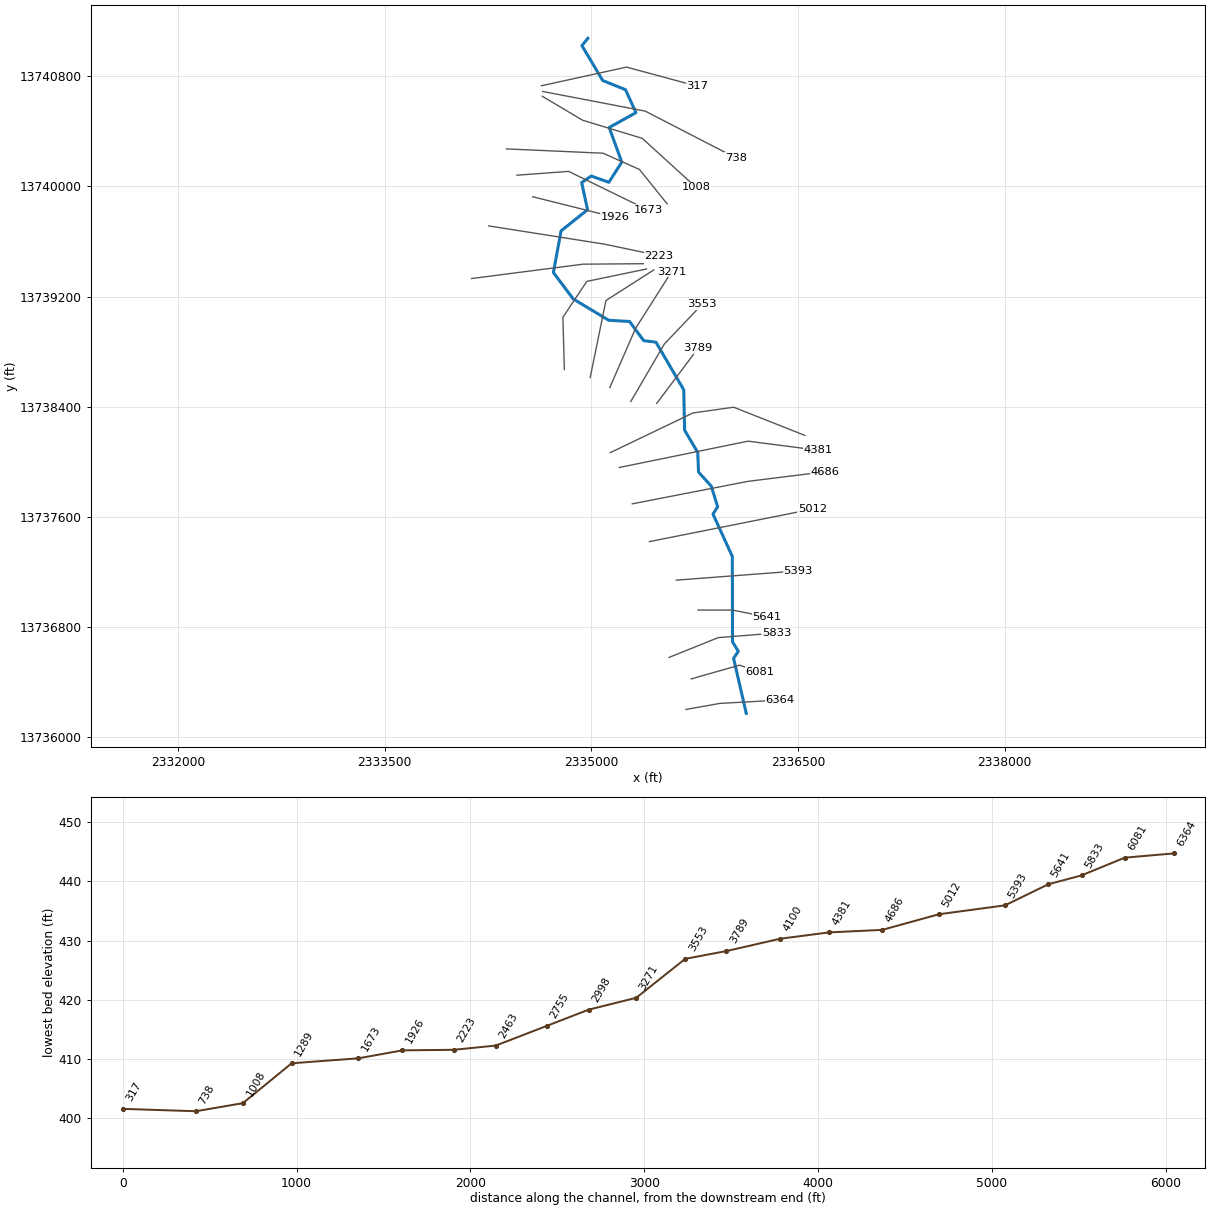
--- ROCKY CREEK 2.prj (project) ---

Proj Title=ROCKY CREEK 2 Base Level Engineering
Current Plan=p01
Default Exp/Contr=0.3,0.1
English Units
Geom File=g01
Flow File=f01
Plan File=p01
Y Axis Title=Elevation
X Axis Title(PF)=Main Channel Distance
X Axis Title(XS)=Station
BEGIN DESCRIPTION:
ROCKY CREEK 2
END DESCRIPTION:
DSS Export Rating Curves= 0
DSS Export Rating Curve Sorted= 0
DSS Export Volume Flow Curves= 0
DXF OffsetX= 0
DXF OffsetY= 0
DXF ScaleX= 1
DXF ScaleY= 10

--- ROCKY CREEK 2.p01 (plan) ---

Plan Title=Multiple Run
Short Identifier=Multiple
Geom File=g01
Flow File=f01
Subcritical Flow
K Sum by GR= 0
Std Step Tol= 0.01
Critical Tol= 0.01
Num of Std Step Trials= 20
Max Error Tol= 0.3
Flow Tol Ratio= 0.001
Split Flow NTrial= 30
Split Flow Tol= 0.02
Split Flow Ratio= 0.02
Log Output Level= 0
Friction Slope Method= 1
Unsteady Friction Slope Method= 2
Unsteady Bridges Friction Slope Method= 1
Parabolic Critical Depth
Global Vel Dist=  1 , 1 , 1
Global Log Level= 0
CheckData=True
Encroach Param= -1, 0, 0, 0
BEGIN DESCRIPTION:
Multiple Run
END DESCRIPTION:

--- ROCKY CREEK 2.f01 (steady flow) ---

Flow Title=Multiple
Number of Profiles=7
Profile Names=10-year,25-year,50-year,1pct_min,100-year,1pct_plu,500-year
River Rch & RM= ROCKY CREEK 2,Reach-1,6364
     865    1435    1964    1302    2598    5183    4503
River Rch & RM= ROCKY CREEK 2,Reach-1,2463
    2788    4914    7005    4819    9615   19184   17972
Boundary for River Rch & Prof#=ROCKY CREEK 2,Reach-1,1
Up Type=0
Dn Type=3
Dn Slope=0.005
Boundary for River Rch & Prof#=ROCKY CREEK 2,Reach-1,2
Up Type=0
Dn Type=3
Dn Slope=0.005
Boundary for River Rch & Prof#=ROCKY CREEK 2,Reach-1,3
Up Type=0
Dn Type=3
Dn Slope=0.005
Boundary for River Rch & Prof#=ROCKY CREEK 2,Reach-1,4
Up Type=0
Dn Type=3
Dn Slope=0.005
Boundary for River Rch & Prof#=ROCKY CREEK 2,Reach-1,5
Up Type=0
Dn Type=3
Dn Slope=0.005
Boundary for River Rch & Prof#=ROCKY CREEK 2,Reach-1,6
Up Type=0
Dn Type=3
Dn Slope=0.005
Boundary for River Rch & Prof#=ROCKY CREEK 2,Reach-1,7
Up Type=0
Dn Type=3
Dn Slope=0.005

--- ROCKY CREEK 2.g01 (geometry) ---

Geom Title=Existing Conditions
Program Version=4.10

River Reach=ROCKY CREEK 2   ,Reach-1
Reach XY= 30
        2336125.       13736175.      2336032.79      13736575.1
      2336067.21      13736624.9      2336025.18     13736694.98
      2336023.78      13737314.5      2335883.24     13737621.77
      2335917.21      13737674.9      2335871.38      13737823.5
      2335778.56     13737926.47      2335772.75     13738069.07
      2335677.24     13738230.93      2335671.25     13738523.45
      2335469.48     13738869.72      2335380.54     13738880.29
      2335277.46     13739019.54      2335126.47     13739028.55
      2334868.93     13739183.13        2334725.       13739375.
      2334780.73     13739677.55      2334973.04     13739830.88
      2334929.99     13740027.62      2334999.86     13740075.52
      2335127.55     13740029.99      2335221.33     13740176.58
      2335129.95     13740427.57      2335324.14     13740535.31
      2335248.58     13740702.15      2335083.01     13740768.62
      2334932.27     13741021.67        2334975.       13741075.

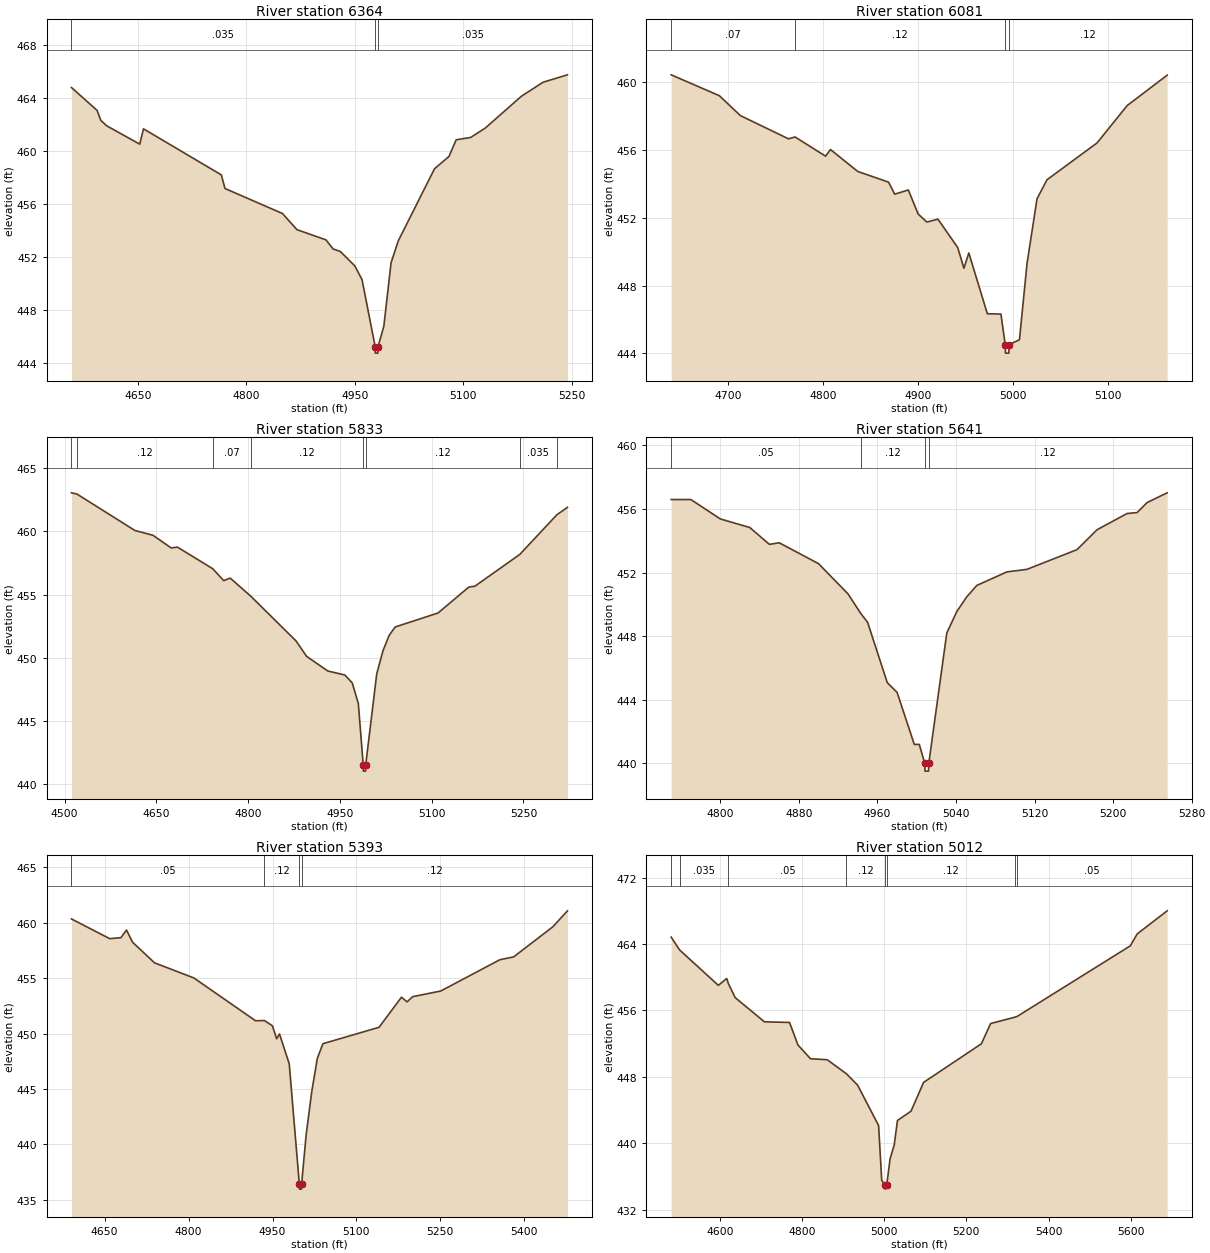
Type RM Length L Ch R = 1 ,6364    ,283,283,283
BEGIN DESCRIPTION:
B20210
END DESCRIPTION:
XS GIS Cut Line= 3
      2335687.08     13736203.39      2335933.85     13736247.41
      2336368.63     13736271.42
#Sta/Elev= 30
    4558  464.81  4593.5  463.08  4598.6  462.33  4606.7  461.92  4652.5  460.53
  4657.6  461.69  4765.3  458.21  4770.4  457.18  4849.9  455.29  4869.9  454.07
    4910   453.3    4920  452.61    4930  452.42    4950  451.33    4960  450.29
  4978.1  445.24  4978.3  444.74  4981.8  444.74  4982.1  445.24  4990.1  446.76
  5000.1  451.56  5010.1  453.22  5060.2  458.67  5080.2   459.6  5090.2  460.86
  5110.3  461.04  5130.3  461.74  5180.4  464.15  5210.4  465.21  5244.1  465.77
#Mann= 3 ,-1 , 0
    4558    .035       0  4978.1    .035       0  4982.1    .035       0
Bank Sta=4978.1,4982.1
XS Rating Curve= 0 ,0
Exp/Cntr=0.3,0.1

Type RM Length L Ch R = 1 ,6081    ,248,248,248
BEGIN DESCRIPTION:
ROCKY CREEK 2 13.0
END DESCRIPTION:
XS GIS Cut Line= 3
      2335724.99       13736425.        2336075.       13736525.
      2336224.98     13736475.01
#Sta/Elev= 30
  4640.3  460.41    4691  459.18  4713.1  458.01  4763.8  456.64  4770.7  456.75
  4802.8  455.62    4808  456.01  4836.6  454.72  4869.1  454.09  4875.6  453.38
  4889.9  453.63  4900.3  452.21  4909.4  451.74  4921.1  451.91  4941.9  450.24
  4948.4  449.02  4953.6  449.92  4973.1  446.34  4987.4  446.32  4991.9  444.52
  4992.2  444.02  4995.7  444.02    4996  444.52  5006.9  444.81  5014.9  449.31
  5025.4  453.11  5035.9  454.23  5088.6   456.4  5120.3   458.6  5162.4  460.39
#Mann= 4 ,-1 , 0
  4640.3     .07       0  4770.7     .12       0  4991.9     .05       0
    4996     .12       0
Bank Sta=4991.9,4996
XS Rating Curve= 0 ,0
Exp/Cntr=0.3,0.1

Type RM Length L Ch R = 1 ,5833    ,192,192,192
BEGIN DESCRIPTION:
B20211
END DESCRIPTION:
XS GIS Cut Line= 3
       2335564.2     13736581.07      2335921.39     13736724.91
       2336345.7     13736758.47
#Sta/Elev= 30
  4511.3  463.06  4520.4  462.96    4615  460.08  4644.6   459.7  4674.2   458.7
  4684.6  458.76  4742.3  457.05  4760.1  456.11  4770.8  456.31  4804.6  454.87
  4878.3  451.34  4895.6  450.12  4930.1  448.96  4958.1  448.64  4970.2  448.02
  4980.2  446.39  4988.2  441.53  4988.5  441.03    4992  441.03  4992.3  441.53
  5010.3  448.73  5020.4  450.54  5030.4  451.76  5040.4  452.44  5110.6  453.55
  5160.8   455.6  5170.8  455.67  5244.3  458.19  5304.9  461.33    5322  461.91
#Mann= 8 ,-1 , 0
  4511.3     .07       0  4520.4     .12       0  4742.3     .07       0
  4804.6     .12       0  4988.2     .05       0  4992.3     .12       0
  5244.3    .035       0  5304.9     .12       0
Bank Sta=4988.2,4992.3
XS Rating Curve= 0 ,0
Exp/Cntr=0.3,0.1

Type RM Length L Ch R = 1 ,5641    ,248,248,248
BEGIN DESCRIPTION:
ROCKY CREEK 2 12.0
END DESCRIPTION:
XS GIS Cut Line= 3
        2335775.       13736925.        2336025.       13736925.
      2336275.04     13736874.99
#Sta/Elev= 30
    4750  456.59    4770  456.59    4800  455.37    4830  454.83    4850  453.77
    4860  453.87    4900  452.56    4930  450.66  4942.9  449.44    4950  448.87
    4970  445.08    4980  444.47  4997.5   441.2  5002.6   441.2  5008.1  440.02
  5008.4  439.52    5012  439.52  5012.3  440.02  5030.6   448.2  5040.8  449.55
    5051  450.48  5061.2  451.19  5091.8  452.04  5112.2   452.2  5163.2  453.44
  5183.6  454.69  5214.2  455.71  5224.4  455.77  5234.6   456.4    5255  457.01
#Mann= 4 ,-1 , 0
    4750     .05       0  4942.9     .12       0  5008.1     .05       0
  5012.3     .12       0
Bank Sta=5008.1,5012.3
XS Rating Curve= 0 ,0
Exp/Cntr=0.3,0.1

Type RM Length L Ch R = 1 ,5393    ,381,381,381
BEGIN DESCRIPTION:
B20212
END DESCRIPTION:
XS GIS Cut Line= 2
       2335616.9     13737142.05      2336500.76     13737209.12
#Sta/Elev= 30
  4590.7  460.33    4659  458.55  4679.1  458.64  4689.1  459.33  4699.9  458.23
  4739.2  456.37  4809.4  455.01  4919.7  451.15  4935.5  451.17  4949.8   450.7
  4957.4  449.53  4962.5  449.96  4979.9  447.27  4997.9  436.47  4998.2  435.97
  5001.8  435.97  5002.1  436.47    5010  440.79    5020  444.71  5030.1  447.76
  5040.1  449.08  5140.4  450.56  5180.5  453.27  5190.5  452.85  5200.5  453.32
  5250.7  453.83  5356.3  456.65  5381.1  456.91  5451.3  459.63  5477.1  461.06
#Mann= 4 ,-1 , 0
  4590.7     .05       0  4935.5     .12       0  4997.9     .05       0
  5002.1     .12       0
Bank Sta=4997.9,5002.1
XS Rating Curve= 0 ,0
Exp/Cntr=0.3,0.1

Type RM Length L Ch R = 1 ,5012    ,326,326,326
BEGIN DESCRIPTION:
B20213
END DESCRIPTION:
XS GIS Cut Line= 2
      2335422.44     13737421.75      2336606.53     13737657.87
#Sta/Elev= 30
  4481.5  464.82  4501.9  463.28  4596.3  459.01  4616.7  459.84  4620.4  459.26
  4637.1  457.54  4708.4  454.62  4769.6  454.54    4790  451.83  4820.6  450.17
  4861.4  450.05  4908.2  448.35  4935.3  446.99  4986.4  442.12    4994  435.52
    5002  434.96  5002.3  434.46  5006.2  434.96  5014.3   438.1  5024.5  439.81
  5032.3  442.73  5065.3  443.85  5095.9  447.32  5236.6  451.97  5259.1  454.41
  5319.1  455.19  5323.8  455.27  5599.1  463.77    5616  465.21  5688.9  467.99
#Mann= 8 ,-1 , 0
  4481.5     .05       0  4501.9    .035       0  4620.4     .05       0
  4908.2     .12       0    5002     .05       0  5006.2     .12       0
  5319.1     .07       0  5323.8     .05       0
Bank Sta=5002,5006.2
XS Rating Curve= 0 ,0
Exp/Cntr=0.3,0.1

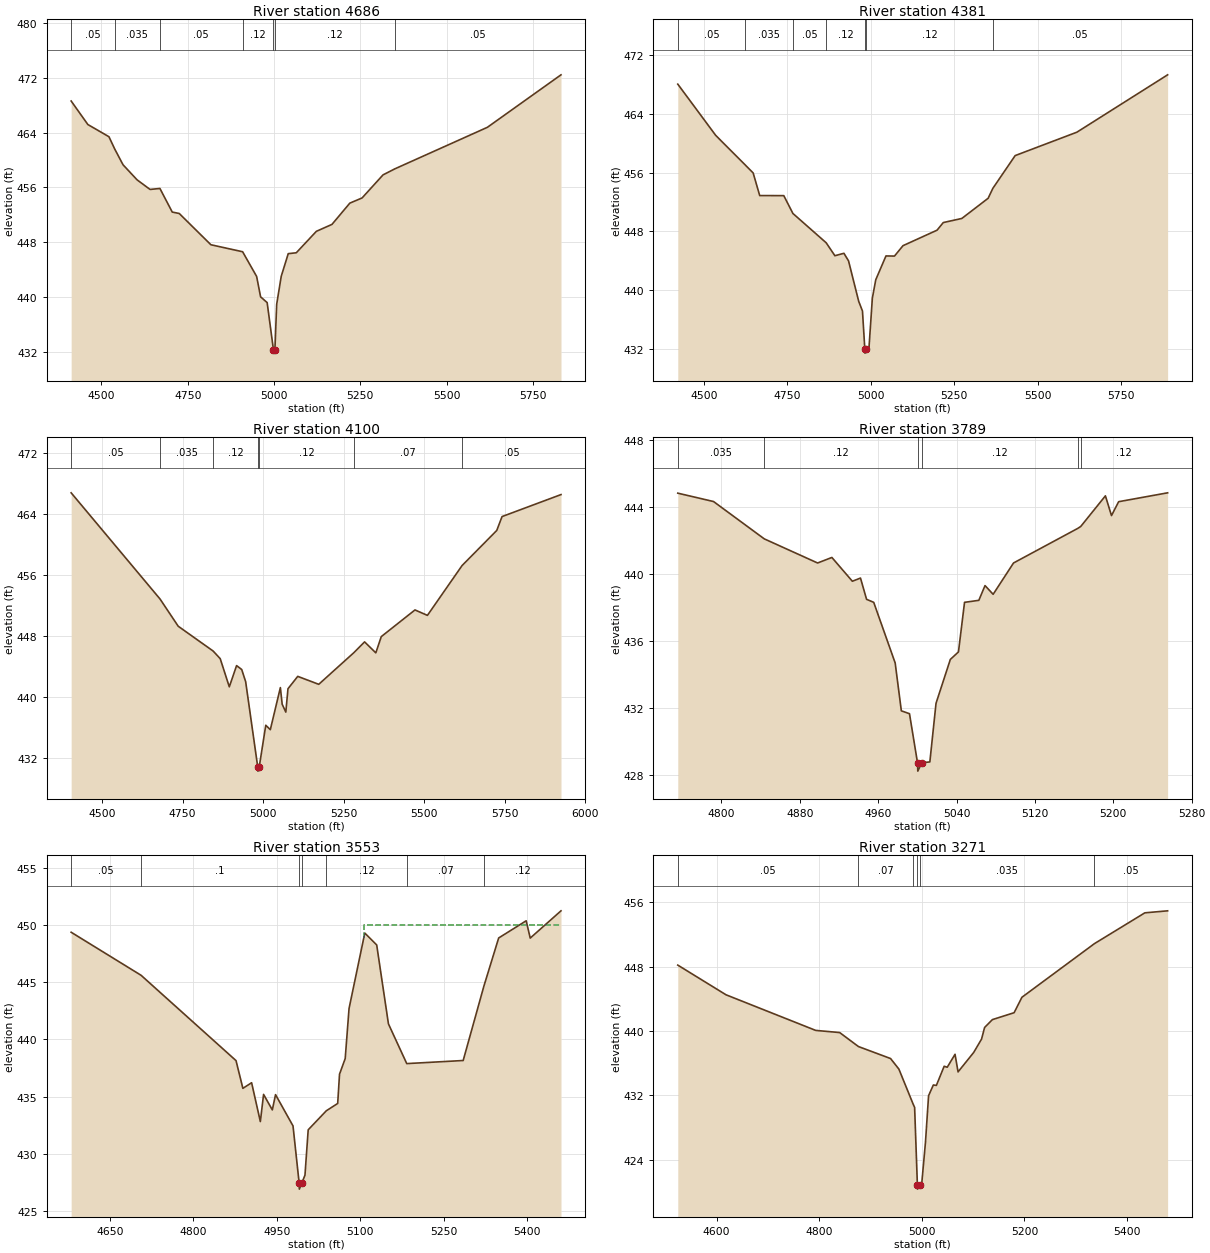
Type RM Length L Ch R = 1 ,4686    ,305,305,305
BEGIN DESCRIPTION:
B20214
END DESCRIPTION:
XS GIS Cut Line= 3
       2335297.5     13737696.06      2336137.74     13737859.25
       2336696.8      13737928.7
#Sta/Elev= 30
  4412.1   468.6  4460.5  465.17  4521.6  463.39  4538.6  461.57  4562.4   459.3
  4603.1   457.1  4640.7   455.7  4669.3  455.84    4705   452.4  4725.3  452.19
    4817  447.63  4908.9  446.61  4949.5  443.01    4961  440.03    4980  439.19
  4998.2  432.32  4998.5  431.82  5002.5  432.32  5007.6  438.94  5020.8  443.03
  5041.1  446.33  5064.4  446.46  5122.6  449.59  5167.8   450.6  5219.5   453.7
  5255.1  454.46  5315.7  457.82  5349.4  458.69    5618  464.76  5831.4  472.42
#Mann= 7 ,-1 , 0
  4412.1     .05       0  4538.6    .035       0  4669.3     .05       0
  4908.9     .12       0  4998.2     .05       0  5002.5     .12       0
  5349.4     .05       0
Bank Sta=4998.2,5002.5
XS Rating Curve= 0 ,0
Exp/Cntr=0.3,0.1

Type RM Length L Ch R = 1 ,4381    ,281,281,281
BEGIN DESCRIPTION:
B20215
END DESCRIPTION:
XS GIS Cut Line= 3
       2335203.7     13737959.94      2336137.74     13738150.92
      2336648.14     13738084.95
#Sta/Elev= 30
  4421.9  468.07  4535.5  461.09  4624.3  457.04  4647.8  455.96  4667.4  452.88
  4739.6  452.87  4766.9  450.44  4866.7  446.44  4892.7  444.68  4919.8  445.01
  4933.6  443.98  4964.2  438.45  4975.4  437.14  4982.5   431.9  4982.8   431.4
  4986.8   431.9  4994.8  432.06    5005  438.89  5015.2   441.4  5045.8  444.65
  5071.3  444.63  5096.9  446.05  5198.9  448.16  5217.6   449.2  5273.2  449.76
    5352  452.51  5366.2  453.87    5433  458.33    5618  461.52  5889.9  469.34
#Mann= 7 ,-1 , 0
  4421.9     .05       0  4624.3    .035       0  4766.9     .05       0
  4866.7     .12       0  4982.5     .05       0  4986.8     .12       0
  5366.2     .05       0
Bank Sta=4982.5,4986.8
XS Rating Curve= 0 ,0
Exp/Cntr=0.3,0.1

Type RM Length L Ch R = 1 ,4100    ,311,311,311
BEGIN DESCRIPTION:
B20216
END DESCRIPTION:
XS GIS Cut Line= 4
      2335137.75     13738067.59      2335738.43     13738355.78
      2336033.57     13738397.44      2336550.42     13738192.79
#Sta/Elev= 30
  4404.2  466.78  4680.1  452.87  4736.4  449.31  4844.8  446.06  4866.8  445.06
    4895  441.37  4917.6  444.15  4933.5  443.64  4945.8  442.04  4983.4  430.83
  4983.7  430.33  4987.7  430.83  5008.2  436.34  5022.3  435.76  5053.5  441.27
  5059.1  439.09  5070.4  438.06  5077.1  441.12  5107.4  442.74  5172.6   441.7
  5282.2  445.87  5314.8  447.26  5349.7  445.82  5366.7  447.95  5471.2  451.44
  5509.9  450.73  5617.5  457.26    5725  461.85  5741.5  463.67  5924.4  466.55
#Mann= 7 ,-1 , 0
  4404.2     .05       0  4680.1    .035       0  4844.8     .12       0
  4983.4     .05       0  4987.7     .12       0  5282.2     .07       0
  5617.5     .05       0
Bank Sta=4983.4,4987.7
XS Rating Curve= 0 ,0
Exp/Cntr=0.3,0.1

Type RM Length L Ch R = 1 ,3789    ,236,236,236
BEGIN DESCRIPTION:
ROCKY CREEK 2 8.0
END DESCRIPTION:
XS GIS Cut Line= 3
      2335474.98     13738424.98        2335625.       13738625.
      2335774.98     13738824.98
#Sta/Elev= 30
  4755.4  444.84  4791.9  444.34  4843.7  442.11  4898.1  440.67  4912.7     441
  4933.6  439.58  4941.9  439.77  4948.1   438.5  4955.4  438.32  4977.3   434.7
  4983.6  431.84  4991.9  431.67  5000.1  428.74  5000.4  428.24  5004.5  428.74
  5012.7  428.79    5019  432.29  5033.6  434.91  5041.9  435.36  5048.1  438.32
  5062.7  438.44    5069  439.32  5077.3   438.8  5098.1  440.67  5163.5  442.73
  5166.7  442.85  5191.9  444.68  5198.1   443.5  5205.4  444.33  5255.4  444.86
#Mann= 6 ,-1 , 0
  4755.4    .035       0  4843.7     .12       0  5000.1     .05       0
  5004.5     .12       0  5163.5     .07       0  5166.7     .12       0
Bank Sta=5000.1,5004.5
XS Rating Curve= 0 ,0
Exp/Cntr=0.3,0.1

Type RM Length L Ch R = 1 ,3553    ,282,282,282
BEGIN DESCRIPTION:
B20217
END DESCRIPTION:
XS GIS Cut Line= 3
      2335287.03     13738439.09       2335530.1     13738855.78
      2335804.43     13739143.99
#Sta/Elev= 30
  4580.3  449.36    4706   445.6  4876.6  438.15  4888.9  435.73  4904.6  436.22
  4920.3  432.83  4926.1   435.2  4941.8  433.85  4947.6  435.18    4979  432.45
  4990.1  427.43  4990.4  426.93  4994.6  427.43  5000.5  428.15  5006.3  432.11
  5038.8  433.77  5059.3  434.41  5062.6  436.97  5072.8  438.33  5079.7   442.7
    5108  449.29  5129.4  448.25  5150.5  441.36  5183.4  437.89  5284.8  438.16
    5322  444.65  5348.6  448.86    5398  450.36  5405.3  448.85  5460.6  451.23
#Mann= 7 ,-1 , 0
  4580.3     .05       0    4706      .1       0  4990.1     .05       0
  4994.6      .1       0  5038.8     .12       0  5183.4     .07       0
    5322     .12       0
#XS Ineff= 2 , 0
       0                    5106       0     450
Permanent Ineff=
       F       F
Bank Sta=4990.1,4994.6
XS Rating Curve= 0 ,0
Exp/Cntr=0.3,0.1

Type RM Length L Ch R = 1 ,3271    ,273,273,273
BEGIN DESCRIPTION:
B20218
END DESCRIPTION:
XS GIS Cut Line= 3
      2335134.26     13738539.78      2335321.77     13738970.36
      2335582.17     13739380.07
#Sta/Elev= 30
  4524.2  448.21  4618.2  444.52  4793.1  440.09  4839.9  439.82  4876.5  438.08
  4939.1  436.59  4955.3  435.28    4983  430.94    4986  430.51  4991.4  420.85
  4991.7  420.35  4995.9  420.85  4999.6  420.85  5007.2  426.22  5013.2  431.97
  5022.5   433.3  5028.4  433.25  5043.6  435.63  5049.6  435.51  5064.8  437.12
  5070.7  434.93  5101.2  437.35  5116.5  439.01  5122.4  440.45  5137.6  441.43
    5180  442.29  5195.2  444.21  5336.6  450.88  5434.9  454.71  5479.3  454.96
#Mann= 6 ,-1 , 0
  4524.2     .05       0  4876.5     .07       0    4983    .035       0
  4991.4    .035       0  4995.9    .035       0  5336.6     .05       0
Bank Sta=4991.4,4995.9
XS Rating Curve= 0 ,0
Exp/Cntr=0.3,0.1

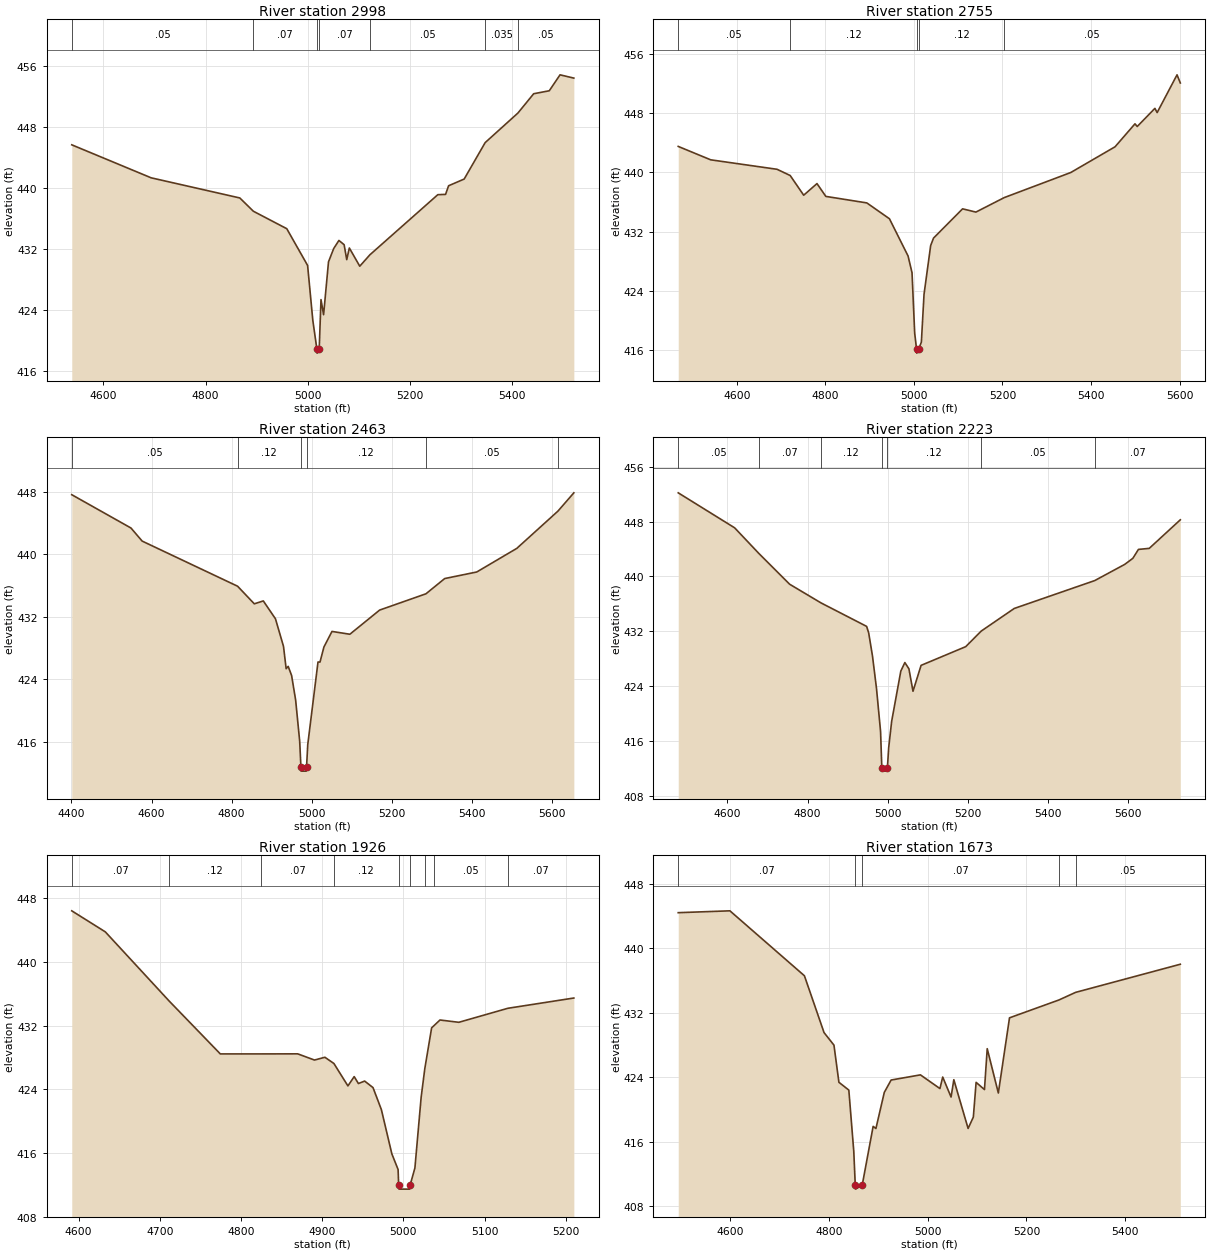
Type RM Length L Ch R = 1 ,2998    ,243,243,243
BEGIN DESCRIPTION:
B20219
END DESCRIPTION:
XS GIS Cut Line= 3
       2334991.9     13738612.67      2335106.49     13739171.75
      2335453.68     13739393.95
#Sta/Elev= 30
  4538.2  445.67  4693.7  441.34  4867.2   438.7  4893.7  436.96  4959.1  434.67
  4999.9  429.85  5010.1  422.65  5018.1  418.85  5018.4  418.35  5022.6  418.85
  5026.1  425.37  5031.2  423.39  5040.8  430.32    5051  432.07  5061.2  433.13
  5071.4  432.57  5076.5  430.61  5081.6  432.14    5102  429.75  5121.9  431.25
  5254.8  439.13    5270  439.17  5275.9   440.3  5306.4  441.18  5347.5  445.96
  5411.5  449.83  5442.5  452.37    5473  452.76  5494.1  454.85  5521.1  454.42
#Mann= 7 ,-1 , 0
  4538.2     .05       0  4893.7     .07       0  5018.1     .05       0
  5022.6     .07       0  5121.9     .05       0  5347.5    .035       0
  5411.5     .05       0
Bank Sta=5018.1,5022.6
XS Rating Curve= 0 ,0
Exp/Cntr=0.3,0.1

Type RM Length L Ch R = 1 ,2755    ,292,292,292
BEGIN DESCRIPTION:
B20220
END DESCRIPTION:
XS GIS Cut Line= 4
      2334804.41     13738671.74      2334793.99     13739050.22
       2334967.6     13739310.64      2335400.82     13739400.75
#Sta/Elev= 30
  4467.7  443.51    4541   441.7    4691  440.42  4720.6  439.58  4751.1  436.92
  4781.1  438.49  4801.1  436.76  4893.7  435.88  4944.8  433.74  4986.8  428.72
  4995.8  426.45  5001.8   418.3  5006.1  416.09  5006.4  415.59  5010.6  416.09
  5016.9  417.08  5022.9  423.53  5037.9  430.12  5044.4  431.13    5110  435.08
  5140.1  434.64  5204.2   436.6  5354.2  439.98  5454.4  443.46  5499.4  446.56
  5504.5   446.2  5544.4  448.65  5549.5  448.08  5594.4  453.18  5601.8  452.08
#Mann= 5 ,-1 , 0
  4467.7     .05       0  4720.6     .12       0  5006.1     .05       0
  5010.6     .12       0  5204.2     .05       0
Bank Sta=5006.1,5010.6
XS Rating Curve= 0 ,0
Exp/Cntr=0.3,0.1

Type RM Length L Ch R = 1 ,2463    ,240,240,240
BEGIN DESCRIPTION:
B20221
END DESCRIPTION:
XS GIS Cut Line= 3
      2334130.78     13739331.47      2334939.82     13739435.64
      2335377.29     13739439.11
#Sta/Elev= 30
  4400.9  447.62  4548.7  443.36  4576.6  441.69  4814.8  435.92  4856.5  433.67
    4879  434.04  4909.3  431.76  4929.4  428.23    4936  425.37  4941.1  425.67
  4949.6  424.51  4959.7  421.37  4969.8   416.1  4972.9  412.78  4973.4  412.28
  4986.4  412.28  4986.9  412.78  4989.9  415.66  5015.5  426.23  5020.5  426.22
  5030.3  428.15  5050.4  430.14    5095  429.78  5169.4  432.87  5284.9  434.95
  5331.8   436.9  5411.8  437.74  5511.8  440.76  5614.4  445.52  5654.1  447.86
#Mann= 6 ,-1 , 0
  4400.9     .05       0  4814.8     .12       0  4972.9     .05       0
  4986.9     .12       0  5284.9     .05       0  5614.4     .07       0
Bank Sta=4972.9,4986.9
XS Rating Curve= 0 ,0
Exp/Cntr=0.3,0.1

Type RM Length L Ch R = 1 ,2223    ,297,297,297
BEGIN DESCRIPTION:
B20222
END DESCRIPTION:
XS GIS Cut Line= 3
       2334255.8     13739713.42       2335092.6     13739581.47
      2335490.98     13739498.33
#Sta/Elev= 30
    4477   452.2  4617.9  447.09  4678.9  443.32  4755.2  438.86  4833.3  436.14
  4947.6   432.7  4952.7  431.75  4962.1  428.42  4972.2  423.66  4982.4  417.36
  4985.5  412.07    4986  411.57    4999  411.57  4999.5  412.07  5002.6  414.95
  5010.1  418.84    5033  426.18  5043.1  427.42  5053.2  426.51  5063.4  423.23
  5083.6  427.01    5195  429.74  5233.9  432.02  5316.4  435.32  5517.4  439.39
  5592.2  441.75  5612.6  442.64  5626.5  443.94  5653.5  444.09  5731.1  448.26
#Mann= 7 ,-1 , 0
    4477     .05       0  4678.9     .07       0  4833.3     .12       0
  4985.5     .05       0  4999.5     .12       0  5233.9     .05       0
  5517.4     .07       0
Bank Sta=4985.5,4999.5
XS Rating Curve= 0 ,0
Exp/Cntr=0.3,0.1

Type RM Length L Ch R = 1 ,1926    ,253,253,253
BEGIN DESCRIPTION:
ROCKY CREEK 2 4.0
END DESCRIPTION:
XS GIS Cut Line= 3
      2334574.97     13739925.01        2334975.       13739825.
        2335175.       13739775.
#Sta/Elev= 30
  4591.5  446.42  4632.8  443.78  4711.5  435.09  4774.5  428.45  4824.5  428.45
  4869.8  428.46  4890.5  427.68  4903.3  428.03  4914.4  427.25  4931.7  424.43
  4939.4   425.6  4944.6  424.73  4952.3  425.04  4962.6  424.22  4972.9  421.46
  4985.8   415.9  4993.5  413.93  4994.2  411.97  4994.7  411.47  5007.8  411.47
  5008.3  411.97  5014.2  414.12  5021.9  423.01  5026.4   426.6  5034.8  431.72
  5037.7     432  5045.1  432.71  5068.3  432.42  5128.7  434.18    5210  435.47
#Mann= 9 ,-1 , 0
  4591.5     .07       0  4711.5     .12       0  4824.5     .07       0
  4914.4     .12       0  4994.2     .05       0  5008.3     .12       0
  5026.4     .07       0  5037.7     .05       0  5128.7     .07       0
Bank Sta=4994.2,5008.3
XS Rating Curve= 0 ,0
Exp/Cntr=0.3,0.1

Type RM Length L Ch R = 1 ,1673    ,384,384,384
BEGIN DESCRIPTION:
B20223
END DESCRIPTION:
XS GIS Cut Line= 3
      2334460.66     13740081.47      2334835.66     13740109.25
      2335410.99     13739828.51
#Sta/Elev= 30
  4495.3  444.44  4599.9  444.67  4750.7  436.61  4790.4  429.56  4810.5     428
  4820.5  423.39  4840.6  422.42  4850.6  414.82  4853.6  410.63  4854.1  410.13
  4867.7  410.63  4889.8  417.92  4895.4  417.65  4912.4  422.14  4926.2  423.67
  4985.5  424.31    5025  422.61  5030.6  424.04  5047.5  421.56  5053.1  423.71
    5082  417.66  5092.6  419.07  5098.2  423.38  5115.1  422.49  5120.7  427.56
  5143.2  422.06  5165.8  431.39    5266  433.61  5299.6  434.55  5511.5  438.04
#Mann= 5 ,-1 , 0
  4495.3     .07       0  4853.6     .05       0  4867.7     .07       0
    5266     .07       0  5299.6     .05       0
Bank Sta=4853.6,4867.7
XS Rating Curve= 0 ,0
Exp/Cntr=0.3,0.1

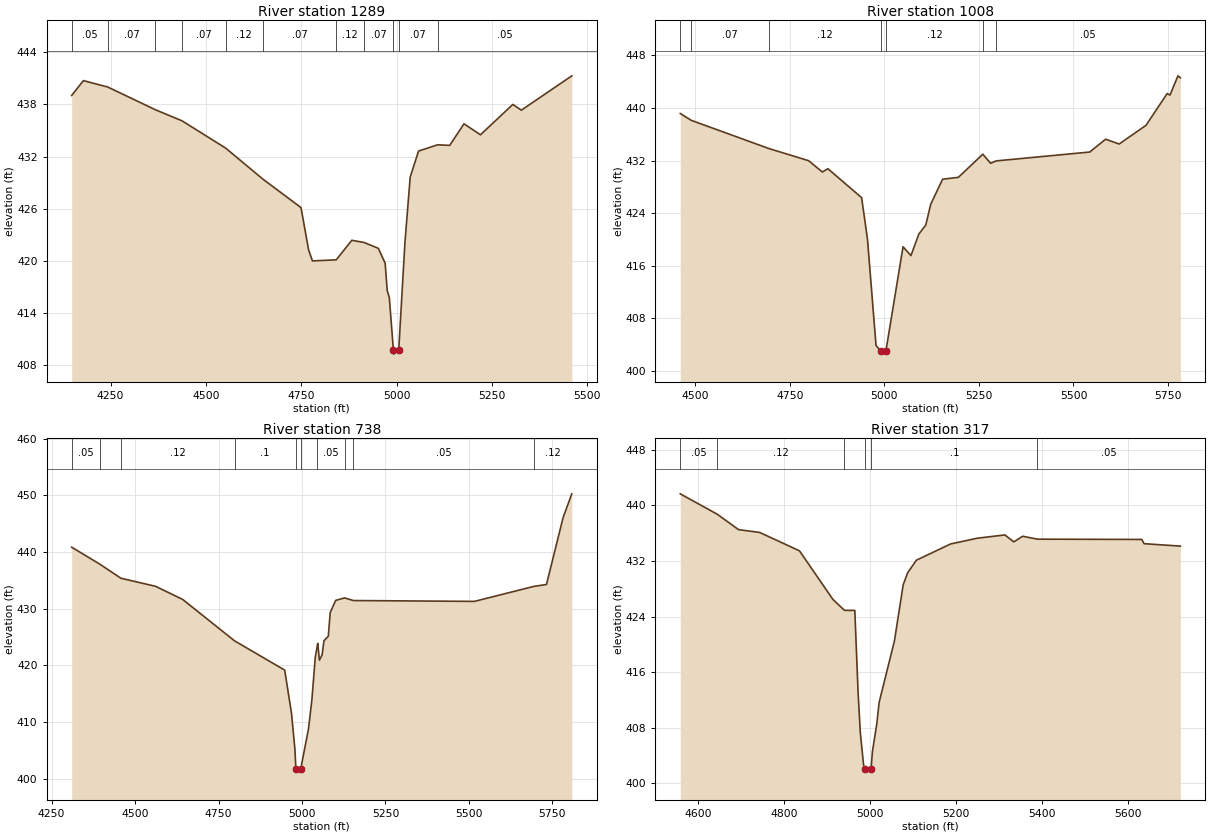
Type RM Length L Ch R = 1 ,1289    ,281,281,281
BEGIN DESCRIPTION:
B20224
END DESCRIPTION:
XS GIS Cut Line= 4
      2334384.28     13740272.44      2335085.66     13740241.19
      2335349.55     13740123.14      2335550.44     13739873.75
#Sta/Elev= 30
    4148  439.03  4178.8  440.74  4242.7     440  4367.5  437.39  4437.2  436.12
  4551.4  432.99    4650  429.39  4749.3  426.14  4769.3  421.27  4779.3  420.01
  4841.6  420.13  4882.6  422.38  4915.2  422.12  4952.2  421.45  4969.9  419.75
  4975.4  416.59  4980.9  415.79  4991.5  409.79    4992  409.29  5005.6  409.79
  5021.8   422.1  5035.6  429.64  5057.5  432.64  5107.6  433.36  5139.2  433.29
  5176.7  435.77  5219.9  434.51  5304.7     438  5327.1  437.34  5459.4  441.29
#Mann= 11 ,-1 , 0
    4148     .05       0  4242.7     .07       0  4367.5     .12       0
  4437.2     .07       0  4551.4     .12       0    4650     .07       0
  4841.6     .12       0  4915.2     .07       0  4991.5     .05       0
  5005.6     .07       0  5107.6     .05       0
Bank Sta=4991.5,5005.6
XS Rating Curve= 0 ,0
Exp/Cntr=0.3,0.1

Type RM Length L Ch R = 1 ,1008    ,270,270,270
BEGIN DESCRIPTION:
B20225
END DESCRIPTION:
XS GIS Cut Line= 4
      2334644.67      13740654.4      2334936.35     13740480.78
      2335370.38     13740348.83      2335761.35     13739992.46
#Sta/Elev= 30
  4460.6  439.15  4489.6  438.11  4694.4  433.83    4800  431.97  4836.2  430.25
  4850.9  430.75    4940  426.35  4955.4  420.09  4978.1  403.87  4990.1  403.05
  4990.6  402.55  5004.3  403.05  5049.5  418.88  5070.4  417.54  5091.3  420.82
  5109.6  422.18  5122.6  425.33    5154  429.15  5195.8  429.44  5260.4  432.96
  5280.9  431.58  5295.7  431.94  5543.1  433.29    5585  435.24  5620.8  434.51
  5691.7  437.35  5747.8  442.19  5755.2  441.95  5776.2  444.88  5782.7  444.58
#Mann= 7 ,-1 , 0
  4460.6     .05       0  4489.6     .07       0  4694.4     .12       0
  4990.1     .05       0  5004.3     .12       0  5260.4      .1       0
  5295.7     .05       0
Bank Sta=4990.1,5004.3
XS Rating Curve= 0 ,0
Exp/Cntr=0.3,0.1

Type RM Length L Ch R = 1 ,738     ,421,421,421
BEGIN DESCRIPTION:
B20226
END DESCRIPTION:
XS GIS Cut Line= 3
      2334648.21      13740689.1      2335391.21     13740546.75
      2336050.46     13740206.71
#Sta/Elev= 30
  4310.1  440.86  4395.2  437.84  4457.3  435.39  4561.4  433.96  4642.8  431.64
  4797.9  424.35  4948.3  419.18  4968.7  411.54  4978.8  405.27  4981.9  401.69
  4982.4  401.19  4996.1  401.69  5019.6  408.84  5029.8     414  5039.9  421.46
  5044.3  422.92  5047.2  423.89  5052.3  420.93  5060.3  421.87    5066  424.38
  5078.9  425.15  5084.6  429.33  5101.1  431.48  5127.7  431.91  5154.2  431.45
  5516.5   431.3  5694.3  433.94  5732.5  434.28  5782.4   446.1  5808.4  450.27
#Mann= 10 ,-1 , 0
  4310.1     .05       0  4395.2     .07       0  4457.3     .12       0
  4797.9      .1       0  4981.9     .05       0  4996.1      .1       0
  5044.3     .05       0  5127.7     .12       0  5154.2     .05       0
  5694.3     .12       0
Bank Sta=4981.9,4996.1
XS Rating Curve= 0 ,0
Exp/Cntr=0.3,0.1

Type RM Length L Ch R = 1 ,317     ,0,0,0
BEGIN DESCRIPTION:
B20227
END DESCRIPTION:
XS GIS Cut Line= 3
      2334637.78     13740730.79       2335255.8     13740866.19
      2335769.68     13740727.31
#Sta/Elev= 30
  4557.8  441.67    4644  438.73  4693.7  436.51  4742.7  436.11  4835.5  433.46
  4913.3  426.47  4940.3  424.89  4964.4  424.88  4972.1  412.99  4977.2  407.29
  4984.9  402.57  4988.1  402.09  4988.6  401.59  5002.3  402.09  5005.4  404.54
  5015.6  408.56  5021.1  411.65  5056.6  420.46  5077.1  428.57  5087.3  430.28
  5107.8  432.11  5187.5  434.45  5249.6  435.28    5314  435.75  5334.7  434.75
  5355.4  435.56  5389.9  435.14  5632.9   435.1    5638  434.49  5722.8  434.14
#Mann= 6 ,-1 , 0
  4557.8     .05       0    4644     .12       0  4940.3      .1       0
  4988.1     .05       0  5002.3      .1       0  5389.9     .05       0
Bank Sta=4988.1,5002.3
XS Rating Curve= 0 ,0
Exp/Cntr=0.3,0.1

Chan Stop Cuts=-1
Use User Specified Reach Order=0
Composite Channel Slope=5