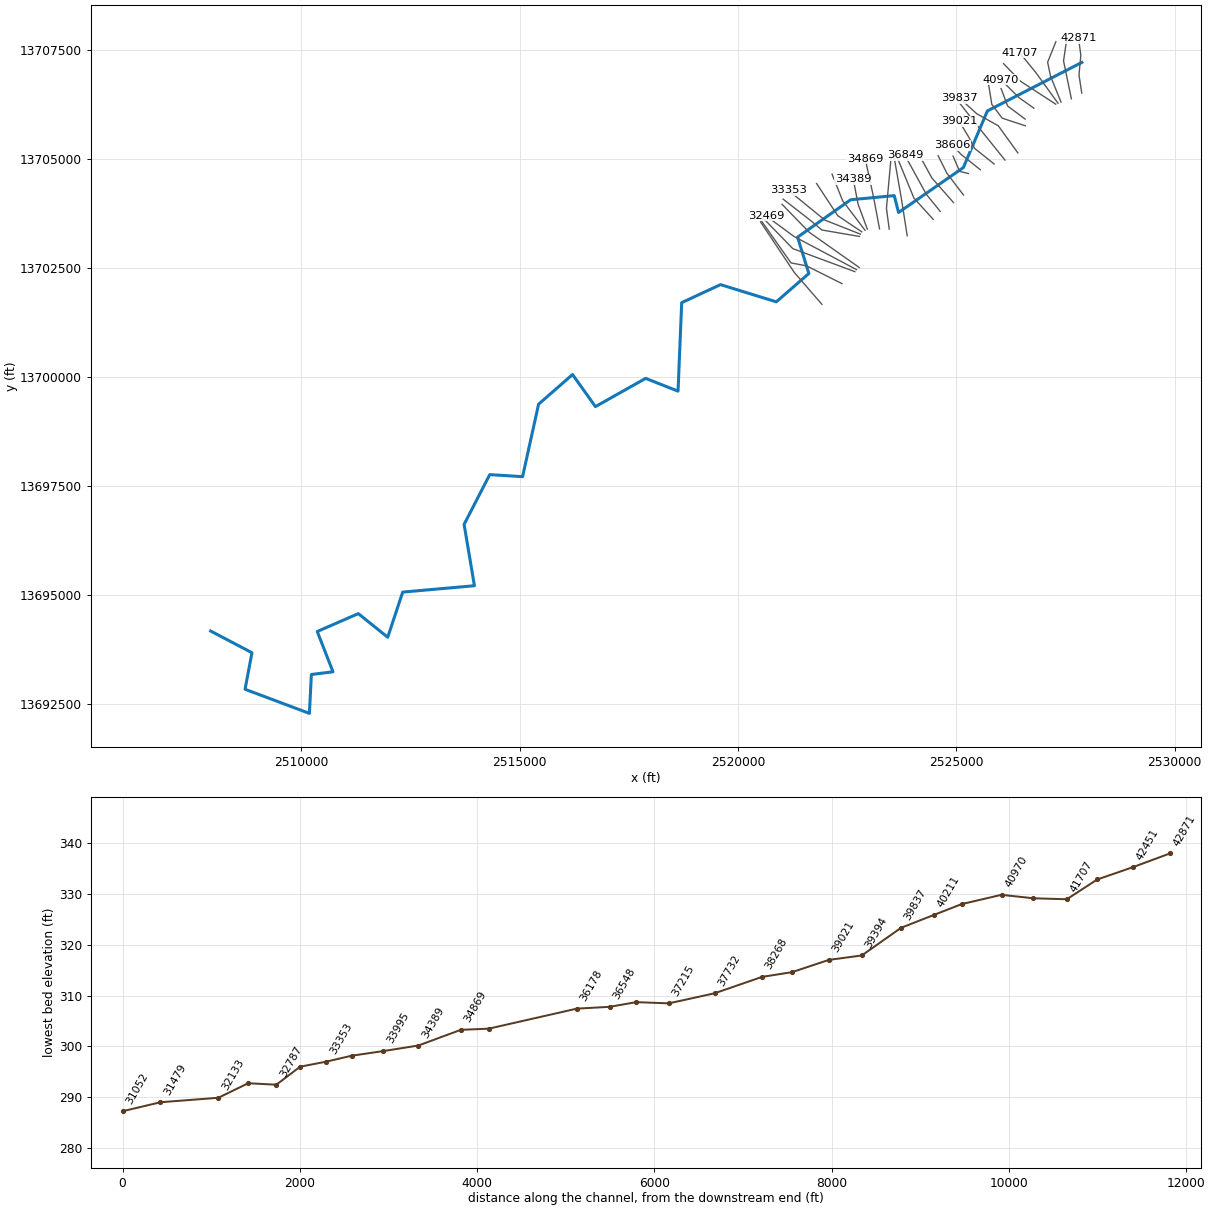
--- ROCKY CREEK 3.prj (project) ---

Proj Title=ROCKY CREEK 3 Base Level Engineering
Current Plan=p01
Default Exp/Contr=0.3,0.1
English Units
Geom File=g01
Flow File=f01
Plan File=p01
Y Axis Title=Elevation
X Axis Title(PF)=Main Channel Distance
X Axis Title(XS)=Station
BEGIN DESCRIPTION:
ROCKY CREEK 3
END DESCRIPTION:
DSS Export Rating Curves= 0
DSS Export Rating Curve Sorted= 0
DSS Export Volume Flow Curves= 0
DXF OffsetX= 0
DXF OffsetY= 0
DXF ScaleX= 1
DXF ScaleY= 10

--- ROCKY CREEK 3.p01 (plan) ---

Plan Title=Multiple Run
Short Identifier=Multiple
Geom File=g01
Flow File=f01
Subcritical Flow
K Sum by GR= 0
Std Step Tol= 0.01
Critical Tol= 0.01
Num of Std Step Trials= 20
Max Error Tol= 0.3
Flow Tol Ratio= 0.001
Split Flow NTrial= 30
Split Flow Tol= 0.02
Split Flow Ratio= 0.02
Log Output Level= 0
Friction Slope Method= 1
Unsteady Friction Slope Method= 2
Unsteady Bridges Friction Slope Method= 1
Parabolic Critical Depth
Global Vel Dist=  1 , 1 , 1
Global Log Level= 0
CheckData=True
Encroach Param= -1, 0, 0, 0
BEGIN DESCRIPTION:
Multiple Run
END DESCRIPTION:

--- ROCKY CREEK 3.f01 (steady flow) ---

Flow Title=Multiple
Number of Profiles=7
Profile Names=10-year,25-year,50-year,1pct_min,100-year,1pct_plu,500-year
River Rch & RM= ROCKY CREEK 3,Reach-1,42871
    1058    1768    2435    1625    3242    6468    5688
River Rch & RM= ROCKY CREEK 3,Reach-1,41707
    1495    2537    3529    2375    4739    9457    8464
River Rch & RM= ROCKY CREEK 3,Reach-1,39394
    1696    2879    4003    2690    5368   10711    9562
River Rch & RM= ROCKY CREEK 3,Reach-1,34389
    1911    3254    4535    3052    6090   12151   10881
River Rch & RM= ROCKY CREEK 3,Reach-1,31479
    2081    3550    4953    3336    6656   13280   11910
River Rch & RM= ROCKY CREEK 3,Reach-1,28441
    2236    3806    5302    3563    7109   14185   12664
River Rch & RM= ROCKY CREEK 3,Reach-1,23507
    2387    4061    5653    3794    7571   15106   13456
River Rch & RM= ROCKY CREEK 3,Reach-1,18398
    2418    4089    5669    3788    7557   15079   13308
River Rch & RM= ROCKY CREEK 3,Reach-1,7734
    2476    4177    5778    3851    7684   15331   13464
Boundary for River Rch & Prof#=ROCKY CREEK 3,Reach-1,1
Up Type=0
Dn Type=3
Dn Slope=0.005
Boundary for River Rch & Prof#=ROCKY CREEK 3,Reach-1,2
Up Type=0
Dn Type=3
Dn Slope=0.005
Boundary for River Rch & Prof#=ROCKY CREEK 3,Reach-1,3
Up Type=0
Dn Type=3
Dn Slope=0.005
Boundary for River Rch & Prof#=ROCKY CREEK 3,Reach-1,4
Up Type=0
Dn Type=3
Dn Slope=0.005
Boundary for River Rch & Prof#=ROCKY CREEK 3,Reach-1,5
Up Type=0
Dn Type=3
Dn Slope=0.005
Boundary for River Rch & Prof#=ROCKY CREEK 3,Reach-1,6
Up Type=0
Dn Type=3
Dn Slope=0.005
Boundary for River Rch & Prof#=ROCKY CREEK 3,Reach-1,7
Up Type=0
Dn Type=3
Dn Slope=0.005

--- ROCKY CREEK 3.g01 (geometry) ---

Geom Title=Existing Conditions
Program Version=4.10

River Reach=ROCKY CREEK 3   ,Reach-1
Reach XY= 30
        2527875.       13707225.      2525711.67     13706111.61
      2525161.38     13704811.78      2523677.42     13703780.41
       2523578.7     13704167.35      2522581.16     13704073.25
      2521364.51     13703214.48      2521623.04     13702380.88
      2520877.28     13701730.08      2519600.04      13702125.5
       2518711.2     13701711.81      2518627.48     13699680.46
      2517885.26     13699974.02      2516735.71     13699325.72
       2516211.3     13700062.04      2515433.95     13699381.69
      2515067.33     13697718.48      2514315.15     13697764.52
      2513728.08     13696623.32      2513964.52      13695215.2
      2512322.46      13695069.3      2511978.44     13694032.79
      2511305.02     13694575.04      2510365.18     13694164.54
      2510725.11      13693240.2      2510230.71     13693177.59
      2510185.19     13692285.77      2508711.76     13692838.61
      2508869.64      13693677.7        2507925.       13694175.

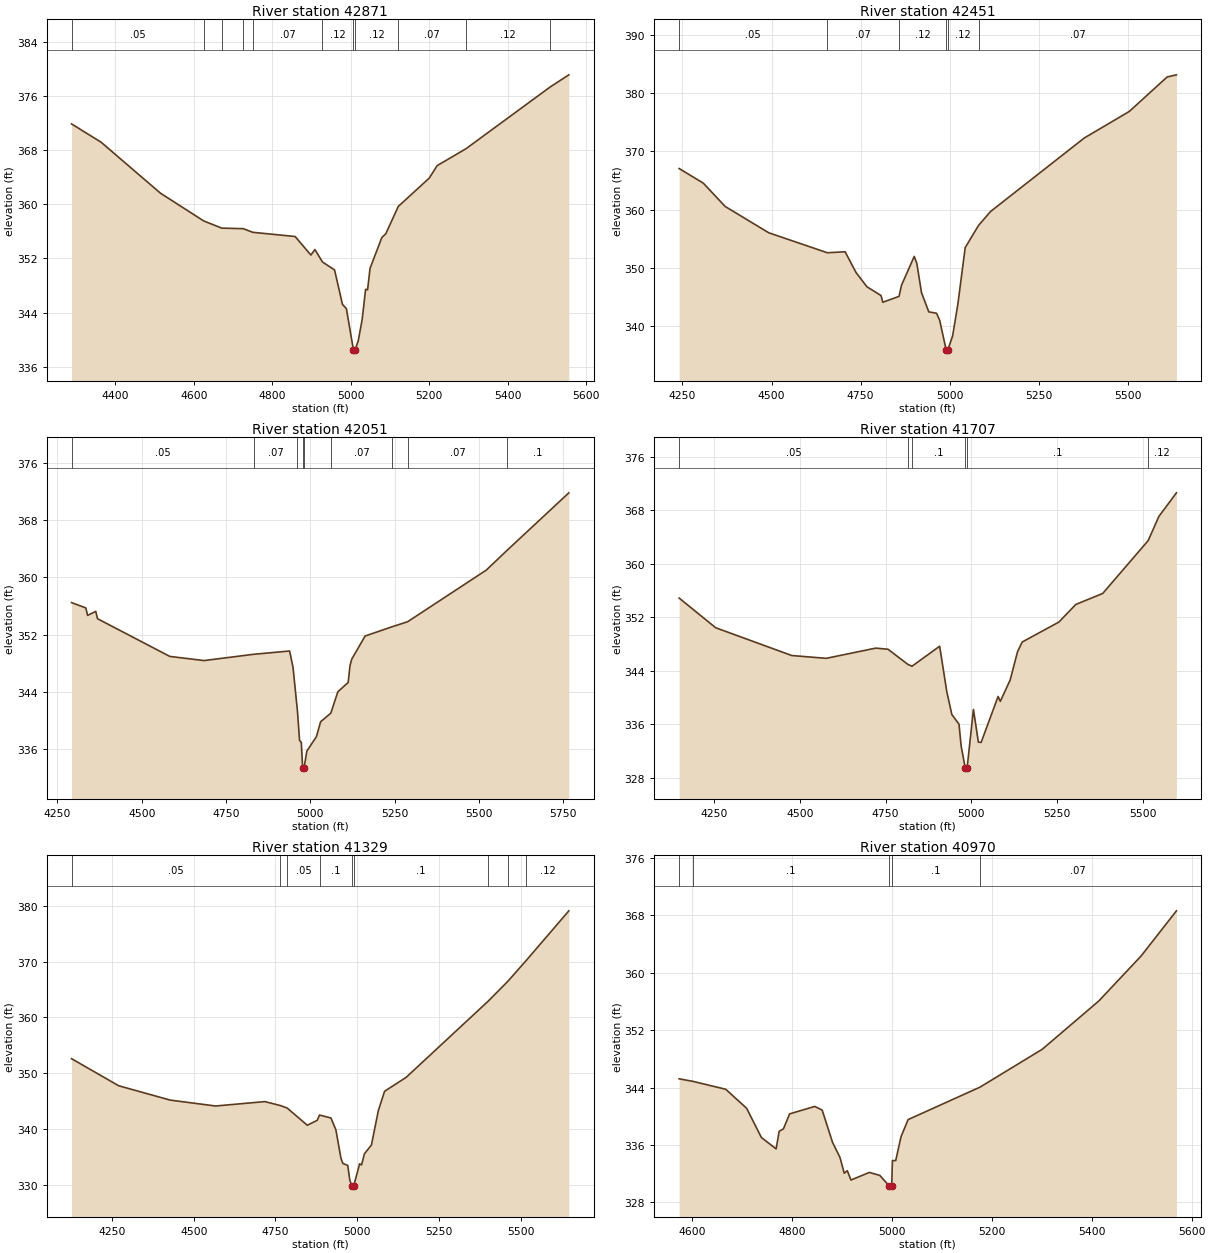
Type RM Length L Ch R = 1 ,42871   ,420,420,420
BEGIN DESCRIPTION:
B20278
END DESCRIPTION:
XS GIS Cut Line= 4
       2527872.7     13706520.67      2527809.32     13706937.86
      2527851.57     13707391.99      2527798.77     13707777.43
#Sta/Elev= 30
  4288.4  371.87  4363.6  369.17  4515.3  361.62  4625.3  357.53  4671.2  356.47
  4725.9  356.39  4750.2  355.85  4858.1  355.23  4898.3  352.49  4908.4  353.31
  4927.7  351.47  4958.6  350.29  4978.7   345.2  4988.7  344.58  5006.6   338.5
  5006.9     338  5010.9   338.5  5018.8  339.79  5028.9  342.97  5037.7  347.43
  5042.7  347.36    5049  350.53  5079.1  355.09  5089.1  355.64    5121  359.68
  5199.8  363.86    5220   365.7  5293.9  368.22  5507.8  377.32  5555.5  379.12
#Mann= 11 ,-1 , 0
  4288.4     .05       0  4625.3     .12       0  4671.2     .07       0
  4725.9     .12       0  4750.2     .07       0  4927.7     .12       0
  5006.6     .05       0  5010.9     .12       0    5121     .07       0
  5293.9     .12       0  5507.8     .07       0
Bank Sta=5006.6,5010.9
XS Rating Curve= 0 ,0
Exp/Cntr=0.3,0.1

Type RM Length L Ch R = 1 ,42451   ,400,400,400
BEGIN DESCRIPTION:
B20282
END DESCRIPTION:
XS GIS Cut Line= 3
      2527635.07     13706388.66      2527455.53     13707259.97
      2527529.34     13707760.85
#Sta/Elev= 30
  4240.7  367.06  4308.4  364.55  4369.9  360.53  4492.2     356  4656.7  352.56
  4706.6  352.73  4737.3  349.15  4767.9   346.7  4807.3   345.2  4812.4  344.04
    4858  345.05  4864.9  346.97  4900.6  351.93  4907.9  350.72    4921  345.69
  4941.5  342.38  4963.3  342.15  4972.1  340.92  4990.4  335.78  4990.7  335.28
  4994.7  335.78  5008.4  338.26  5023.1  343.72  5043.6  353.44  5081.4  357.29
    5115  359.67    5378  372.32  5504.1  376.88  5610.5  382.82  5636.6  383.19
#Mann= 6 ,-1 , 0
  4240.7     .05       0  4656.7     .07       0    4858     .12       0
  4990.4     .05       0  4994.7     .12       0  5081.4     .07       0
Bank Sta=4990.4,4994.7
XS Rating Curve= 0 ,0
Exp/Cntr=0.3,0.1

Type RM Length L Ch R = 1 ,42051   ,344,344,344
BEGIN DESCRIPTION:
B20281
END DESCRIPTION:
XS GIS Cut Line= 4
      2527397.46     13706314.73      2527159.82      13706900.9
      2527091.18     13707228.29      2527279.91     13707700.13
#Sta/Elev= 30
  4291.8  356.48  4334.1  355.74  4339.5  354.69  4363.6  355.25    4369  354.22
  4583.4  348.94  4685.1  348.36  4832.3  349.24  4938.7   349.7  4948.9  347.39
    4962  341.27  4968.2  337.18  4973.3   336.9  4977.4  333.37  4977.7  332.87
  4981.7  333.37  4989.8  335.67  5018.1  337.69  5030.7  339.79  5060.9  340.99
  5081.8  343.99  5112.4  345.29  5117.9  347.66    5123  348.56  5162.7   351.8
  5242.4  353.09  5288.8   353.8    5522  361.03  5583.7   363.8    5767  371.86
#Mann= 9 ,-1 , 0
  4291.8     .05       0  4832.3     .07       0    4962     .12       0
  4977.4     .05       0  4981.7     .12       0  5060.9     .07       0
  5242.4      .1       0  5288.8     .07       0  5583.7      .1       0
Bank Sta=4977.4,4981.7
XS Rating Curve= 0 ,0
Exp/Cntr=0.3,0.1

Type RM Length L Ch R = 1 ,41707   ,378,378,378
BEGIN DESCRIPTION:
B20280
END DESCRIPTION:
XS GIS Cut Line= 3
      2527328.78     13706288.38      2526821.87     13706990.67
      2526452.21     13707444.82
#Sta/Elev= 30
  4147.1  354.85  4253.9  350.41  4475.9  346.26  4576.5  345.84  4721.2  347.37
  4756.8   347.2  4814.7  344.94  4826.8  344.66  4907.6  347.65  4928.5  340.84
  4943.2  337.44  4964.1     336  4970.3  332.73  4982.2  329.48  4982.6  328.98
  4987.8  329.48  5006.2   338.2  5020.7  333.31  5028.6  333.27  5078.2  340.14
  5084.6  339.41  5113.4   342.6  5134.9  346.83  5148.6  348.28  5255.6  351.26
  5305.1   353.9  5383.4  355.53  5516.3  363.44  5547.5  367.05  5598.8  370.58
#Mann= 6 ,-1 , 0
  4147.1     .05       0  4814.7     .07       0  4826.8      .1       0
  4982.2     .05       0  4987.8      .1       0  5516.3     .12       0
Bank Sta=4982.2,4987.8
XS Rating Curve= 0 ,0
Exp/Cntr=0.3,0.1

Type RM Length L Ch R = 1 ,41329   ,359,359,359
BEGIN DESCRIPTION:
B20279
END DESCRIPTION:
XS GIS Cut Line= 3
      2527276.02     13706267.22      2526473.36     13706790.01
      2526082.62     13707196.59
#Sta/Elev= 30
  4126.1  352.57  4270.5  347.71    4428  345.14  4566.9  344.08  4717.8  344.87
  4765.3  344.16  4785.9  343.72  4847.6  340.63  4877.8  341.51    4885  342.46
    4920  341.93  4935.1   339.8  4950.3  334.77  4956.2  333.79  4971.4  333.42
  4977.3  330.93  4983.6  329.67  4984.1  329.17  4989.3  329.67  5007.6  333.71
  5013.5  333.51  5022.4  335.51  5043.8  337.09  5064.9  343.24    5084  346.72
    5150  349.22  5400.3  362.84    5461  366.43    5518  370.22  5647.9  379.09
#Mann= 9 ,-1 , 0
  4126.1     .05       0  4765.3     .07       0  4785.9     .05       0
    4885      .1       0  4983.6     .05       0  4989.3      .1       0
  5400.3     .12       0    5461     .07       0    5518     .12       0
Bank Sta=4983.6,4989.3
XS Rating Curve= 0 ,0
Exp/Cntr=0.3,0.1

Type RM Length L Ch R = 1 ,40970   ,448,448,448
BEGIN DESCRIPTION:
ROCKY CREEK 3 58.0
END DESCRIPTION:
XS GIS Cut Line= 3
      2526775.02     13706174.98        2526425.       13706425.
      2526025.02     13706824.98
#Sta/Elev= 30
  4573.8  345.23  4601.7  344.87  4667.2  343.77    4709  341.12  4738.5  337.05
    4768  335.46  4774.1  337.91  4782.7  338.26    4795  340.34  4845.4  341.38
  4860.2  340.87  4881.1  336.35  4895.8  334.28  4904.4  332.07  4910.5  332.42
  4917.9  331.12  4954.8  332.18  4975.7  331.76  4993.7  330.35  4994.2  329.85
  4999.4  330.35  5000.9  333.83  5007.5  333.83  5018.1  337.16  5032.2  339.54
  5176.3  344.07  5300.9  349.35  5414.1  356.08  5498.9  362.36  5569.6  368.65
#Mann= 5 ,-1 , 0
  4573.8     .07       0  4601.7      .1       0  4993.7     .05       0
  4999.4      .1       0  5176.3     .07       0
Bank Sta=4993.7,4999.4
XS Rating Curve= 0 ,0
Exp/Cntr=0.3,0.1

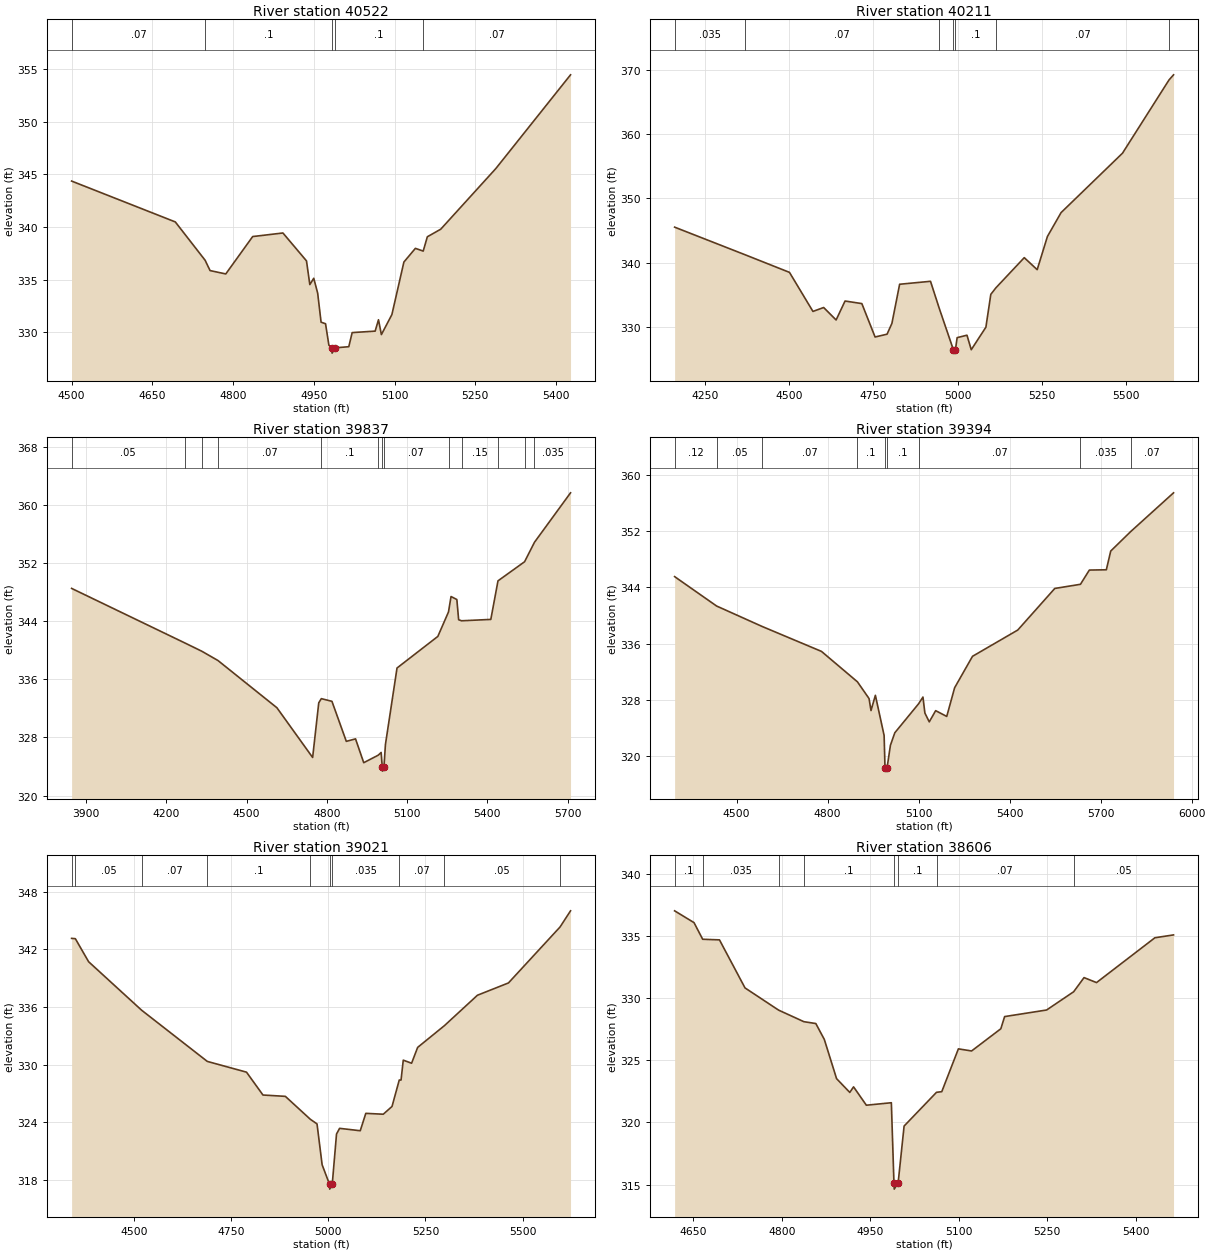
Type RM Length L Ch R = 1 ,40522   ,311,311,311
BEGIN DESCRIPTION:
ROCKY CREEK 3 57.0
END DESCRIPTION:
XS GIS Cut Line= 3
      2526575.02     13705924.99        2526175.       13706225.
      2526025.01     13706624.98
#Sta/Elev= 30
  4499.9  344.37  4692.6  340.49    4748  336.85  4757.2  335.87  4786.4  335.55
  4836.4   339.1  4892.6  339.44  4936.4  336.79  4942.6  334.54  4949.9  335.14
  4957.2  333.72  4963.5  330.97  4971.8  330.82    4978  328.79  4983.5  328.53
    4984  328.03  4989.3  328.53    5015  328.64  5021.3  329.98    5064  330.12
  5070.2   331.2  5075.6  329.79  5095.1  331.69  5117.4  336.68  5138.8  337.98
  5153.3  337.72    5161  339.08  5185.9   339.8  5288.3  345.56  5427.1  354.46
#Mann= 5 ,-1 , 0
  4499.9     .07       0    4748      .1       0  4983.5     .05       0
  4989.3      .1       0  5153.3     .07       0
Bank Sta=4983.5,4989.3
XS Rating Curve= 0 ,0
Exp/Cntr=0.3,0.1

Type RM Length L Ch R = 1 ,40211   ,374,374,374
BEGIN DESCRIPTION:
B20277
END DESCRIPTION:
XS GIS Cut Line= 4
      2526578.96     13705770.88      2526050.92     13705945.13
       2525813.3     13706261.96      2525728.82     13706784.69
#Sta/Elev= 30
  4159.7  345.53  4368.1  341.25  4500.8  338.49  4570.5  332.41  4602.3  333.02
  4639.3  331.08  4665.8  334.03  4715.7  333.63    4755  328.43  4790.6  328.87
    4805  330.55  4827.9  336.64  4919.6   337.1  4945.7  332.87  4987.7  326.42
  4988.2  325.92  4993.5  326.42  4998.7  328.33  5027.9  328.71  5040.6  326.45
  5084.1  329.96  5098.7  335.07  5113.7  336.08    5198  340.78  5236.4  338.91
  5266.8  344.08  5307.3  347.79  5489.7  357.04  5627.8  368.44  5641.3  369.24
#Mann= 7 ,-1 , 0
  4159.7    .035       0  4368.1     .07       0  4945.7      .1       0
  4987.7     .05       0  4993.5      .1       0  5113.7     .07       0
  5627.8     .12       0
Bank Sta=4987.7,4993.5
XS Rating Curve= 0 ,0
Exp/Cntr=0.3,0.1

Type RM Length L Ch R = 1 ,39837   ,443,443,443
BEGIN DESCRIPTION:
B20276
END DESCRIPTION:
XS GIS Cut Line= 4
      2526409.98      13705147.8      2525961.15     13705770.87
      2525470.07     13706045.46      2525074.05     13706404.52
#Sta/Elev= 30
  3846.2  348.52  4269.4  341.01  4332.8  339.87  4393.3  338.59  4613.6  332.09
  4747.2  325.24  4770.1  332.77  4779.7  333.34  4819.4  332.97  4873.1  327.46
  4907.6   327.8  4938.2  324.52  4992.2  325.55  5003.3  325.93  5007.6  323.86
  5008.1  323.36  5013.7  323.86  5019.3  327.01  5062.7  337.56  5215.3  341.91
  5255.1  345.28  5264.6   347.4  5286.3  346.99    5293  344.21  5303.8  344.06
  5413.3  344.25  5440.1  349.56  5539.5  352.19  5576.5  354.87  5711.3  361.68
#Mann= 13 ,-1 , 0
  3846.2     .05       0  4269.4     .07       0  4332.8     .05       0
  4393.3     .07       0  4779.7      .1       0  4992.2     .07       0
  5007.6     .05       0  5013.7     .07       0  5255.1    .033       0
  5303.8     .15       0  5440.1    .035       0  5539.5     .07       0
  5576.5    .035       0
Bank Sta=5007.6,5013.7
XS Rating Curve= 0 ,0
Exp/Cntr=0.3,0.1

Type RM Length L Ch R = 1 ,39394   ,373,373,373
BEGIN DESCRIPTION:
B20275
END DESCRIPTION:
XS GIS Cut Line= 3
      2526114.27      13704984.1      2525533.43     13705707.51
       2525090.9     13706271.21
#Sta/Elev= 30
  4295.9  345.52  4434.2  341.35  4584.2  338.45  4779.9  334.91  4898.5  330.59
  4936.7  328.22  4943.2  326.52  4957.6  328.68  4986.4  322.98  4989.3  318.42
  4989.8  317.92  4996.2  318.42  5007.2  321.59  5021.6  323.36  5100.1  327.48
  5114.4  328.43  5120.8  326.16  5135.2  324.91  5156.3   326.5  5192.8  325.68
  5218.8  329.75  5277.7  334.21  5426.9  337.94  5548.9  343.84  5633.5  344.43
  5662.8  346.45  5718.8  346.49  5733.3  349.15  5798.8   351.9  5940.3  357.41
#Mann= 9 ,-1 , 0
  4295.9     .12       0  4434.2     .05       0  4584.2     .07       0
  4898.5      .1       0  4989.3     .05       0  4996.2      .1       0
  5100.1     .07       0  5633.5    .035       0  5798.8     .07       0
Bank Sta=4989.3,4996.2
XS Rating Curve= 0 ,0
Exp/Cntr=0.3,0.1

Type RM Length L Ch R = 1 ,39021   ,415,415,415
BEGIN DESCRIPTION:
B20274
END DESCRIPTION:
XS GIS Cut Line= 4
      2525866.12      13704894.3      2525417.26     13705253.38
      2525295.81     13705491.01      2525069.73     13705869.56
#Sta/Elev= 30
  4340.3  343.15  4349.9  343.12    4384  340.72  4520.3  335.67  4689.1  330.34
  4789.9  329.22  4832.2  326.84  4889.8   326.7  4953.8  324.32  4971.2  323.83
  4984.3  319.58  5003.3  317.54  5003.8  317.04  5010.3  317.54  5021.3  322.78
  5029.2  323.37  5082.3  323.12  5096.6  324.93  5141.5  324.84    5164  325.65
  5182.6   328.4  5187.2   328.4  5192.9  330.47  5214.3  330.15  5229.9   331.8
  5298.6  334.06  5383.6  337.23  5463.3  338.51    5596  344.34  5622.9  346.02
#Mann= 10 ,-1 , 0
  4340.3     .12       0  4349.9     .05       0  4520.3     .07       0
  4689.1      .1       0  4953.8    .035       0  5003.3    .035       0
  5010.3    .035       0  5182.6     .07       0  5298.6     .05       0
    5596     .07       0
Bank Sta=5003.3,5010.3
XS Rating Curve= 0 ,0
Exp/Cntr=0.3,0.1

Type RM Length L Ch R = 1 ,38606   ,338,338,338
BEGIN DESCRIPTION:
B20273
END DESCRIPTION:
XS GIS Cut Line= 3
      2525549.25     13704762.32      2525105.71     13705116.09
      2524916.57     13705320.99
#Sta/Elev= 30
  4618.1  337.05    4651   336.1  4665.7  334.76  4694.2  334.71  4737.5  330.84
  4794.5  329.05  4837.3  328.12  4857.6  327.97    4872  326.69  4892.8  323.53
  4915.2  322.42  4921.6  322.87  4943.3  321.39  4985.7  321.59  4990.1  315.13
  4990.6  314.63  4997.2  315.13  5007.3  319.71  5062.3  322.43  5071.2  322.48
  5099.4  325.93  5121.8  325.76  5171.4  327.55  5177.8  328.53    5249  329.06
  5294.9  330.53  5312.5  331.67  5333.7  331.27  5432.7  334.88  5464.3  335.11
#Mann= 8 ,-1 , 0
  4618.1      .1       0  4665.7    .035       0  4794.5     .07       0
  4837.3      .1       0  4990.1     .05       0  4997.2      .1       0
  5062.3     .07       0  5294.9     .05       0
Bank Sta=4990.1,4997.2
XS Rating Curve= 0 ,0
Exp/Cntr=0.3,0.1

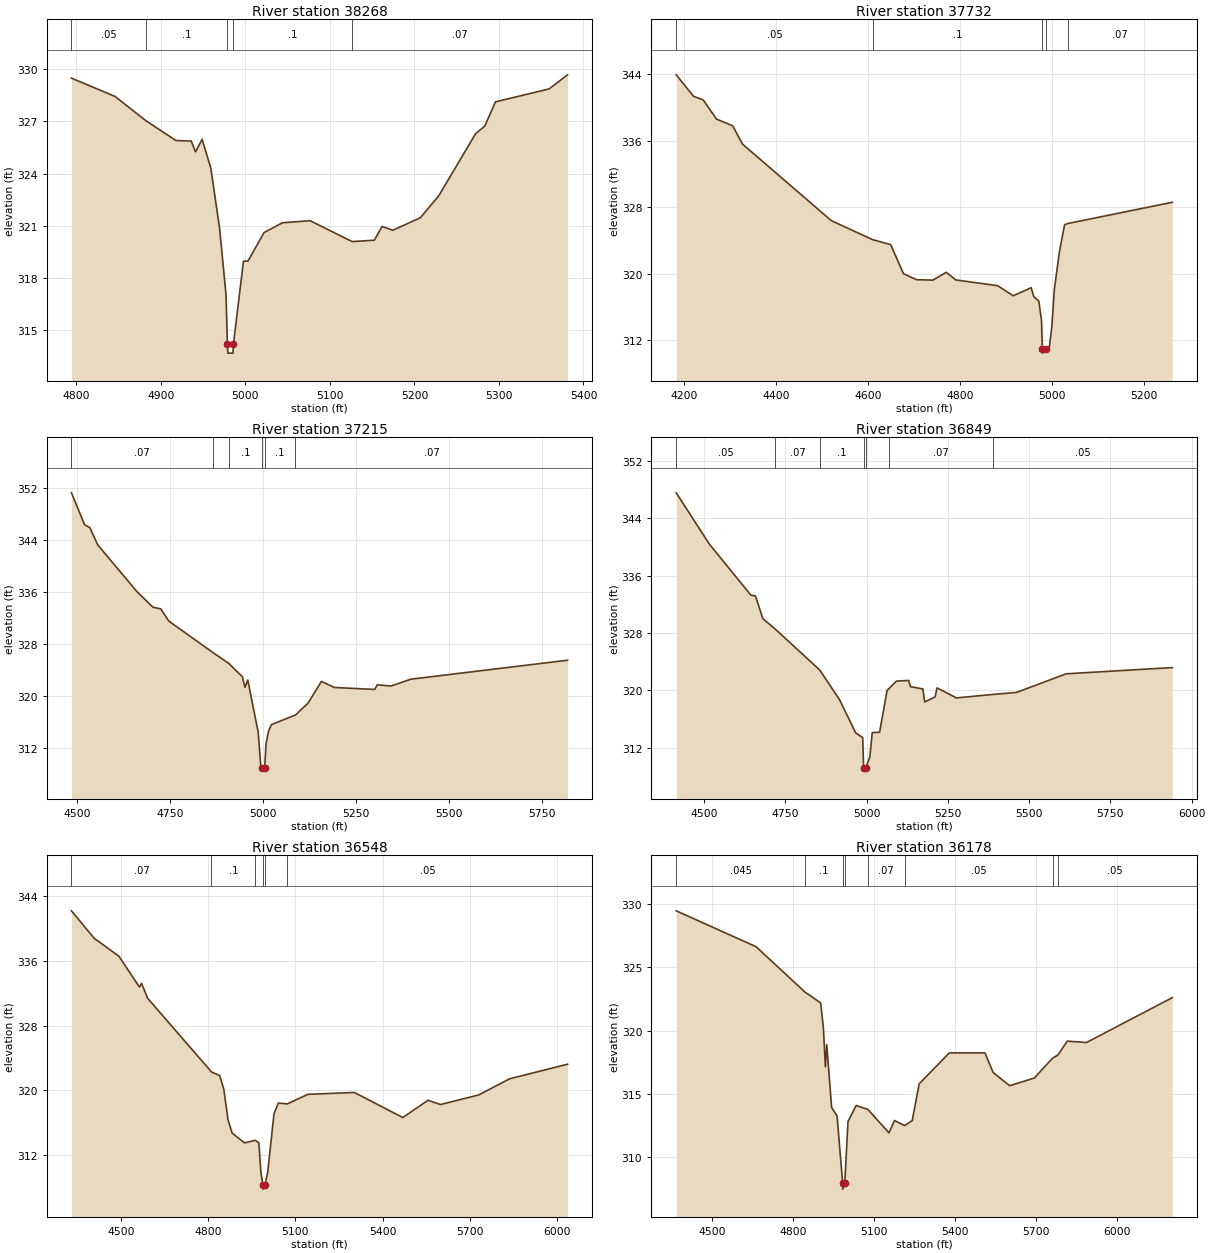
Type RM Length L Ch R = 1 ,38268   ,536,536,536
BEGIN DESCRIPTION:
ROCKY CREEK 3 52.0
END DESCRIPTION:
XS GIS Cut Line= 3
      2525274.96     13704675.01        2525075.       13704725.
        2524925.       13705075.
#Sta/Elev= 30
  4794.2  329.48  4845.7  328.43  4881.9  327.05  4917.8   325.9  4935.9  325.87
    4941  325.25  4948.8  325.97  4959.1  324.31  4969.4  320.88  4977.1  317.04
  4978.7   314.2  4979.2   313.7  4985.3   313.7  4985.8   314.2  4997.7  318.98
    5003  318.98  5022.1  320.62  5043.8  321.18  5076.5   321.3  5126.3   320.1
  5152.6  320.18  5161.7  320.97  5174.4  320.75    5207  321.47  5228.8  322.73
  5272.3  326.29  5283.2  326.73  5295.9  328.12  5359.3  328.86  5381.1  329.67
#Mann= 5 ,-1 , 0
  4794.2     .05       0  4881.9      .1       0  4978.7     .05       0
  4985.8      .1       0  5126.3     .07       0
Bank Sta=4978.7,4985.8
XS Rating Curve= 0 ,0
Exp/Cntr=0.3,0.1

Type RM Length L Ch R = 1 ,37732   ,517,517,517
BEGIN DESCRIPTION:
B20272
END DESCRIPTION:
XS GIS Cut Line= 3
      2525163.82     13704181.42       2524783.6     13704683.09
      2524582.92     13705084.44
#Sta/Elev= 30
  4182.8   343.9  4220.4  341.32  4241.3  340.89  4270.4  338.58  4305.7  337.77
  4326.6  335.59    4520  326.38  4609.7   324.1    4649   323.5  4676.6  320.02
  4705.2  319.29  4740.6  319.24  4769.7  320.18  4790.5  319.26  4881.5  318.57
  4915.2  317.36  4954.3  318.33  4959.9  317.27  4970.9  316.71  4976.7  314.46
  4978.7  310.97  4979.2  310.47  4985.9  310.97  4993.3     311    4999  313.51
  5004.6  318.11  5015.7  322.64    5027   325.9  5034.1  326.04    5261  328.59
#Mann= 5 ,-1 , 0
  4182.8     .05       0  4609.7      .1       0  4978.7     .05       0
  4985.9      .1       0  5034.1     .07       0
Bank Sta=4978.7,4985.9
XS Rating Curve= 0 ,0
Exp/Cntr=0.3,0.1

Type RM Length L Ch R = 1 ,37215   ,366,366,366
BEGIN DESCRIPTION:
B20271
END DESCRIPTION:
XS GIS Cut Line= 3
      2524936.74     13704007.18      2524440.37      13704572.2
      2524160.49     13705084.44
#Sta/Elev= 30
  4483.8  351.28  4519.2  346.37  4533.5  345.92  4554.4  343.28  4660.6  336.06
  4703.3  333.69  4724.2  333.44    4746  331.56  4864.6  326.73  4907.3  325.06
  4944.3  322.99    4951  321.36  4958.6  322.49  4986.7  314.46  4993.7  309.21
  4996.7  308.99  4997.2  308.49    5004  308.99  5007.9  312.74  5014.6  314.66
  5022.2  315.64    5087  317.12  5120.9  318.93  5156.9  322.29    5192  321.35
  5300.5  321.05  5307.4  321.77  5344.1  321.57  5398.2  322.63  5819.6  325.54
#Mann= 6 ,-1 , 0
  4483.8     .07       0  4864.6     .05       0  4907.3      .1       0
  4996.7     .05       0    5004      .1       0    5087     .07       0
Bank Sta=4996.7,5004
XS Rating Curve= 0 ,0
Exp/Cntr=0.3,0.1

Type RM Length L Ch R = 1 ,36849   ,301,301,301
BEGIN DESCRIPTION:
ROCKY CREEK 3 49.0
END DESCRIPTION:
XS GIS Cut Line= 3
      2524630.44     13703806.57      2524313.64     13704197.29
      2523822.57     13705094.93
#Sta/Elev= 30
  4414.2  347.54  4515.9   340.4  4643.9  333.27  4658.1  333.15  4680.5  330.01
  4718.6  328.55  4855.8  322.83  4917.2  318.65  4966.2  314.07    4988   313.4
  4990.7  309.23  4991.2  308.73    4998  309.23  5009.8  310.71  5017.2   314.1
    5040  314.15  5062.8  319.96  5069.1  320.25  5091.4  321.28  5129.3  321.38
    5135  320.51    5173  320.19  5178.7  318.37  5210.9   319.1  5216.6  320.34
  5276.3  318.94  5387.9  319.42  5461.3  319.71    5614   322.3  5940.4  323.17
#Mann= 7 ,-1 , 0
  4414.2     .05       0  4718.6     .07       0  4855.8      .1       0
  4990.7     .05       0    4998      .1       0  5069.1     .07       0
  5387.9     .05       0
Bank Sta=4990.7,4998
XS Rating Curve= 0 ,0
Exp/Cntr=0.3,0.1

Type RM Length L Ch R = 1 ,36548   ,370,370,370
BEGIN DESCRIPTION:
B20270
END DESCRIPTION:
XS GIS Cut Line= 3
      2524472.06      13703621.7      2524028.49      13704112.8
      2523632.45     13705079.13
#Sta/Elev= 30
    4330  342.19  4408.1   338.8  4493.3  336.58  4563.6  332.78    4571  333.23
  4591.9  331.39  4811.6  322.29    4840  321.83  4854.2  320.12  4868.4  316.38
  4882.6  314.74  4925.2  313.52  4961.6  313.84  4974.6  313.54  4981.3  309.98
  4988.1  308.31  4988.6  307.81  4995.4  308.31  5004.9  309.88  5026.6  317.12
  5041.6  318.44  5072.4  318.34    5143  319.52  5303.2  319.75  5469.7  316.65
  5556.1  318.79  5599.5  318.26  5730.3  319.44  5837.1  321.44  6036.1  323.24
#Mann= 6 ,-1 , 0
    4330     .07       0  4811.6      .1       0  4961.6     .07       0
  4988.1     .05       0  4995.4     .07       0  5072.4     .05       0
Bank Sta=4988.1,4995.4
XS Rating Curve= 0 ,0
Exp/Cntr=0.3,0.1

Type RM Length L Ch R = 1 ,36178   ,994,994,994
BEGIN DESCRIPTION:
B20269
END DESCRIPTION:
XS GIS Cut Line= 3
      2523875.36      13703246.8      2523748.62     13704059.99
      2523574.37     13705057.98
#Sta/Elev= 30
  4367.8  329.47  4663.4  326.63  4843.4  323.06  4902.4  322.18  4912.5   320.2
  4919.8  317.13  4924.9  318.88  4942.9  313.92  4963.1  313.24  4983.7  307.95
  4984.2  307.45  4991.7  307.95  5003.6   312.8  5033.9  314.07  5077.4  313.75
  5155.4   311.9  5175.6  312.88    5213  312.48  5241.3  312.87    5267  315.78
  5378.6  318.23  5510.6  318.23    5541  316.67  5601.9  315.63  5693.3  316.24
  5760.6  317.81  5780.6  318.06  5815.1  319.16  5886.2  319.05  6203.9   322.6
#Mann= 8 ,-1 , 0
  4367.8    .045       0  4843.4      .1       0  4983.7     .05       0
  4991.7      .1       0  5077.4     .07       0    5213     .05       0
  5760.6     .07       0  5780.6     .05       0
Bank Sta=4983.7,4991.7
XS Rating Curve= 0 ,0
Exp/Cntr=0.3,0.1

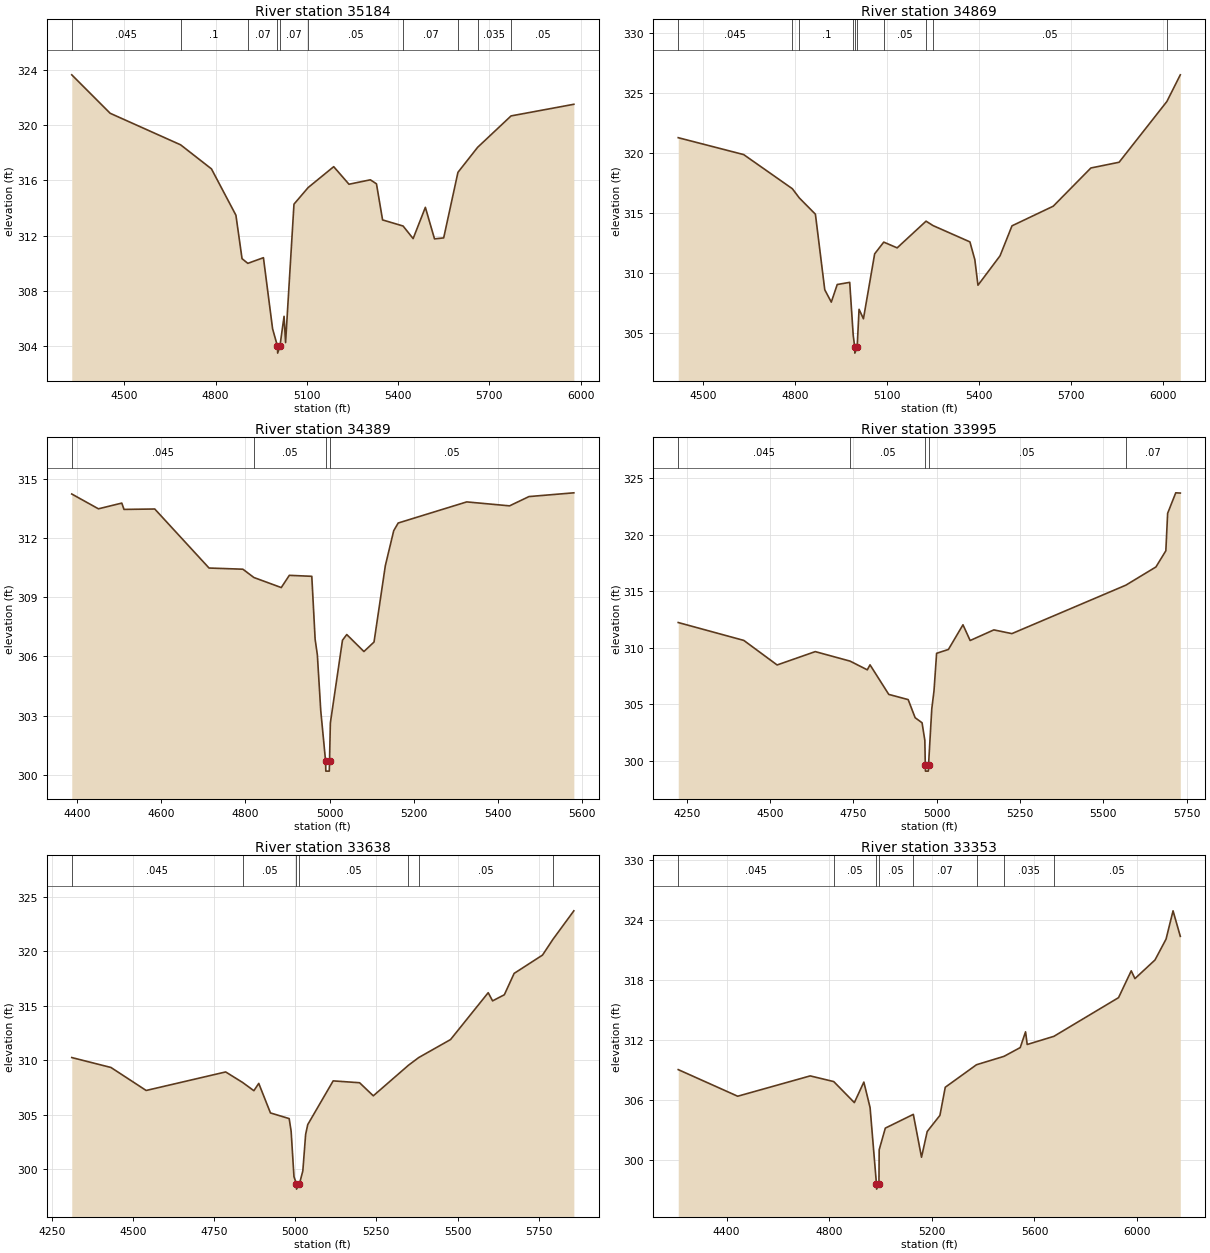
Type RM Length L Ch R = 1 ,35184   ,315,315,315
BEGIN DESCRIPTION:
B20268
END DESCRIPTION:
XS GIS Cut Line= 3
      2523463.48     13703399.91      2523400.11     13703875.18
      2523505.62     13705041.04
#Sta/Elev= 30
  4327.6  323.63  4453.8  320.85  4685.3  318.57  4786.7  316.83  4867.1  313.48
  4887.2  310.34  4906.2     310  4957.5  310.41  4987.6  305.27  5003.7  304.01
  5004.2  303.51  5011.7  304.01  5025.3  306.17  5030.3  304.27  5057.9  314.28
  5104.5  315.48  5188.5  316.99  5238.7  315.72  5308.9  316.04    5329  315.75
  5349.1  313.14  5416.5   312.7  5449.5  311.79  5489.7  314.05  5519.8  311.77
  5549.9  311.84  5596.8  316.58  5661.5  318.39  5771.4  320.66  5977.7   321.5
#Mann= 10 ,-1 , 0
  4327.6    .045       0  4685.3      .1       0  4906.2     .07       0
  5003.7     .05       0  5011.7     .07       0  5104.5     .05       0
  5416.5     .07       0  5596.8     .05       0  5661.5    .035       0
  5771.4     .05       0
Bank Sta=5003.7,5011.7
XS Rating Curve= 0 ,0
Exp/Cntr=0.3,0.1

Type RM Length L Ch R = 1 ,34869   ,480,480,480
BEGIN DESCRIPTION:
B20267
END DESCRIPTION:
XS GIS Cut Line= 3
       2523241.7     13703405.18       2523104.4     13704133.92
      2522914.37     13705010.19
#Sta/Elev= 30
  4419.8  321.27  4633.3  319.86  4792.1  317.01  4815.2  316.23  4867.4  314.88
  4897.9  308.57  4919.2  307.54  4938.6  309.01  4979.3  309.19  4990.7  304.79
  4995.6  303.78  4996.1  303.28  5003.6  303.78  5009.8  306.94  5024.1  306.15
  5060.7  311.57  5090.4  312.55  5134.1  312.07  5228.4   314.3  5251.2  313.93
  5371.5  312.57  5387.6  311.08  5397.8  308.95  5469.9  311.41  5508.8  313.91
  5643.4  315.55  5766.2  318.74  5858.3  319.22  6014.1  324.29    6058  326.52
#Mann= 10 ,-1 , 0
  4419.8    .045       0  4792.1     .05       0  4815.2      .1       0
  4990.7     .07       0  4995.6     .05       0  5003.6     .07       0
  5090.4     .05       0  5228.4     .07       0  5251.2     .05       0
  6014.1     .07       0
Bank Sta=4995.6,5003.6
XS Rating Curve= 0 ,0
Exp/Cntr=0.3,0.1

Type RM Length L Ch R = 1 ,34389   ,394,394,394
BEGIN DESCRIPTION:
B20266
END DESCRIPTION:
XS GIS Cut Line= 3
      2522961.82     13703399.95      2522750.61     13703970.22
      2522639.87     13704545.02
#Sta/Elev= 30
  4387.3  314.23  4450.7  313.48  4506.2  313.77  4511.5  313.45  4584.6  313.47
  4713.6  310.48  4794.1  310.42  4820.2     310  4885.3  309.49  4904.5  310.11
  4957.9  310.06  4965.8  306.87  4971.1  306.08  4979.2  303.25  4990.7  300.69
  4991.2  300.19  4999.5  300.19    5000  300.69    5002  302.63  5030.8  306.82
    5041  307.11  5081.8  306.25  5105.8  306.73  5132.7   310.6  5152.6  312.37
  5163.2  312.76  5326.2  313.83    5428  313.63  5474.1   314.1  5580.8  314.29
#Mann= 4 ,-1 , 0
  4387.3    .045       0  4820.2     .05       0  4990.7     .05       0
    5000     .05       0
Bank Sta=4990.7,5000
XS Rating Curve= 0 ,0
Exp/Cntr=0.3,0.1

Type RM Length L Ch R = 1 ,33995   ,357,357,357
BEGIN DESCRIPTION:
B20265
END DESCRIPTION:
XS GIS Cut Line= 3
      2522909.04     13703373.51      2522396.82     13704049.43
      2522154.29     13704661.02
#Sta/Elev= 30
  4224.6  312.23  4421.3  310.65  4521.2  308.48  4635.6  309.66  4740.1  308.82
  4791.7  308.05  4799.9  308.49  4856.1  305.88  4914.3  305.42  4935.2  303.82
    4956  303.37  4964.3  301.82  4965.7   299.6  4966.2   299.1  4974.8   299.1
  4975.3   299.6  4985.1  304.59  4991.8   306.2  4999.6  309.51    5035  309.85
  5078.7  312.03  5100.2  310.64  5171.3  311.58  5225.4  311.25  5567.2  315.53
  5657.5  317.14  5687.2  318.57  5692.6  321.88  5716.9  323.69  5730.6  323.67
#Mann= 5 ,-1 , 0
  4224.6    .045       0  4740.1     .05       0  4965.7     .05       0
  4975.3     .05       0  5567.2     .07       0
Bank Sta=4965.7,4975.3
XS Rating Curve= 0 ,0
Exp/Cntr=0.3,0.1

Type RM Length L Ch R = 1 ,33638   ,285,285,285
BEGIN DESCRIPTION:
B20264
END DESCRIPTION:
XS GIS Cut Line= 3
      2522835.12     13703336.55      2522285.93      13703706.2
      2521800.13     13704445.46
#Sta/Elev= 30
  4311.7  310.26  4432.4  309.35  4540.9  307.24  4785.8  308.94  4837.7  307.98
  4872.7  307.22  4887.7  307.89  4923.7  305.18  4981.4  304.66  4987.4  303.51
  4996.2  299.33  5003.6  298.69  5004.1  298.19  5013.2  298.69  5023.5  299.87
  5032.1  303.21  5038.6  304.11  5116.9  308.12  5198.3  307.95  5240.5  306.75
  5348.7  309.55  5380.5  310.26  5478.5  311.91  5594.5  316.21    5608  315.46
  5644.2  316.02  5674.4  317.98  5761.8  319.66  5793.8   321.1  5858.3  323.72
#Mann= 7 ,-1 , 0
  4311.7    .045       0  4837.7     .05       0  5003.6     .05       0
  5013.2     .05       0  5348.7     .07       0  5380.5     .05       0
  5793.8     .07       0
Bank Sta=5003.6,5013.2
XS Rating Curve= 0 ,0
Exp/Cntr=0.3,0.1

Type RM Length L Ch R = 1 ,33353   ,298,298,298
BEGIN DESCRIPTION:
B20263
END DESCRIPTION:
XS GIS Cut Line= 3
      2522803.37     13703283.78      2521990.22     13703605.87
      2521152.04     13704291.17
#Sta/Elev= 30
  4211.3  309.02  4443.1  306.35  4725.8  308.39  4817.5  307.82  4897.9  305.71
  4934.9  307.77  4959.2  305.21  4984.1  297.53  4984.6  297.03  4993.7  297.53
  4994.7  300.98  5018.6  303.15  5127.8  304.53  5159.7  300.23  5181.9  302.81
  5231.5  304.43  5252.3  307.25  5374.1  309.51  5481.2  310.35  5544.5  311.23
  5565.3  312.81  5571.7  311.54  5675.9  312.36  5927.8  316.24  5977.3  318.93
  5991.7  318.15  6069.9  320.02    6113  322.11  6140.3  324.95  6168.6  322.39
#Mann= 8 ,-1 , 0
  4211.3    .045       0  4817.5     .05       0  4984.1     .05       0
  4993.7     .05       0  5127.8     .07       0  5374.1     .05       0
  5481.2    .035       0  5675.9     .05       0
Bank Sta=4984.1,4993.7
XS Rating Curve= 0 ,0
Exp/Cntr=0.3,0.1

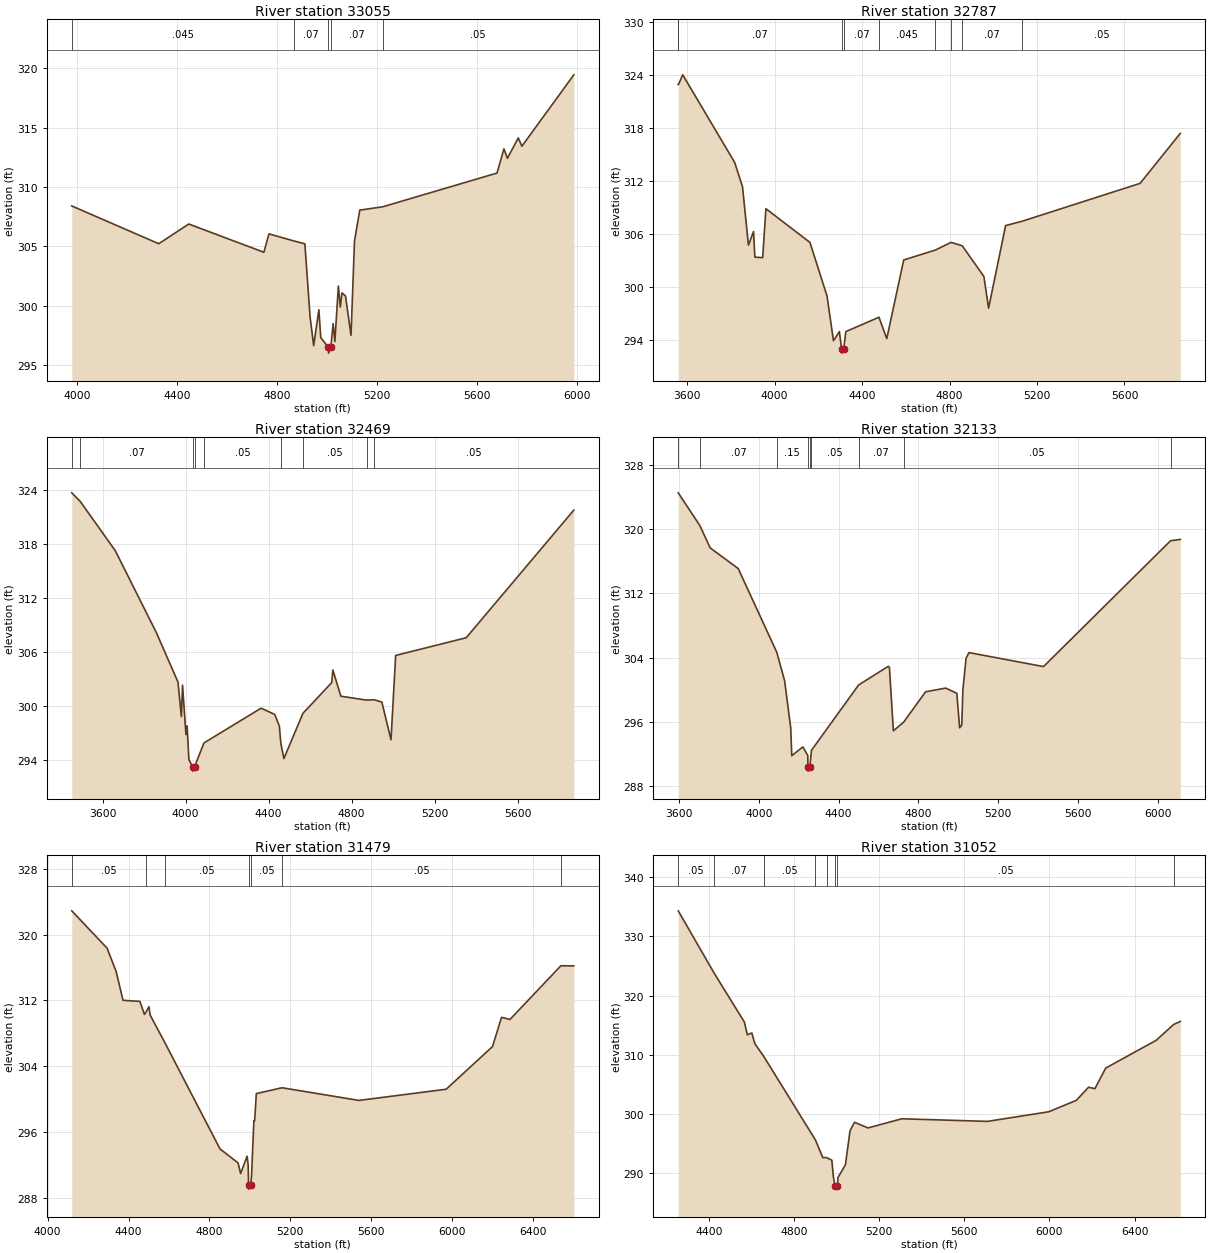
Type RM Length L Ch R = 1 ,33055   ,268,268,268
BEGIN DESCRIPTION:
B20262
END DESCRIPTION:
XS GIS Cut Line= 4
      2522782.29     13703230.96      2521921.57     13703378.81
      2521678.67     13703584.75      2521034.43     13704086.41
#Sta/Elev= 30
    3978  308.41    4326  305.23    4446  306.89  4746.4  304.51  4766.7  306.06
  4867.2  305.46  4910.4  305.22  4931.3  299.06  4945.6  296.65  4966.4  299.67
  4974.1  297.32  5004.5  296.52    5005  296.02  5014.1  296.52  5023.5   298.5
  5030.4  296.99  5044.4  301.67  5052.1   299.9  5058.7  301.09    5073  300.83
    5095  297.52    5109  305.47  5130.1  308.06  5221.8  308.34    5679  311.18
  5706.7  313.22  5720.6  312.42    5764  314.14  5778.5  313.44  5986.3  319.45
#Mann= 5 ,-1 , 0
    3978    .045       0  4867.2     .07       0  5004.5     .05       0
  5014.1     .07       0  5221.8     .05       0
Bank Sta=5004.5,5014.1
XS Rating Curve= 0 ,0
Exp/Cntr=0.3,0.1

Type RM Length L Ch R = 1 ,32787   ,318,318,318
BEGIN DESCRIPTION:
B20261
END DESCRIPTION:
XS GIS Cut Line= 3
      2522776.98     13702518.11      2521625.86     13703331.28
      2521009.12     13703969.11
#Sta/Elev= 30
  3558.9  322.87  3559.5  322.86  3579.6  323.97  3817.2  314.05  3852.9  311.31
    3880   304.7  3903.4  306.24  3909.5  303.34  3945.2  303.28    3960  308.82
  4161.3  305.01  4239.5  298.95    4269  293.88  4296.1  294.92    4306  292.98
  4306.5  292.48  4315.7  292.98  4325.7  294.92    4477  296.54  4512.8  294.12
  4590.3  303.02  4734.9  304.14  4806.9  305.01  4857.9  304.63  4957.1  301.15
  4978.5  297.57  5056.5  306.91  5132.8  307.41  5671.6  311.69  5855.5  317.35
#Mann= 9 ,-1 , 0
  3558.9     .05       0  3559.5     .07       0    4306     .05       0
  4315.7     .07       0    4477    .045       0  4734.9     .07       0
  4806.9     .05       0  4857.9     .07       0  5132.8     .05       0
Bank Sta=4306,4315.7
XS Rating Curve= 0 ,0
Exp/Cntr=0.3,0.1

Type RM Length L Ch R = 1 ,32469   ,336,336,336
BEGIN DESCRIPTION:
B20260
END DESCRIPTION:
XS GIS Cut Line= 3
      2522713.61     13702470.58      2521282.63     13703230.95
      2520639.22      13703705.6
#Sta/Elev= 30
  3451.2  323.71  3492.5  322.74  3661.1  317.27  3858.9  308.17  3963.2  302.67
  3979.5  298.84  3985.1  302.33  4001.5  296.83  4007.1   297.8  4015.8  294.03
  4033.6  293.27  4034.1  292.77  4043.4  293.27  4088.2   295.9  4363.8  299.77
  4429.7  299.07  4451.7  297.78  4459.1  295.83  4473.7  294.17  4565.6   299.2
  4704.1  302.61  4709.8  304.01  4748.1   301.1  4873.5  300.66    4907  300.71
  4945.9  300.45  4989.9  296.25  5012.4  305.63  5352.4   307.6  5871.2  321.79
#Mann= 9 ,-1 , 0
  3451.2     .05       0  3492.5     .07       0  4033.6     .05       0
  4043.4     .07       0  4088.2     .05       0  4459.1     .07       0
  4565.6     .05       0  4873.5     .07       0    4907     .05       0
Bank Sta=4033.6,4043.4
XS Rating Curve= 0 ,0
Exp/Cntr=0.3,0.1

Type RM Length L Ch R = 1 ,32133   ,654,654,654
BEGIN DESCRIPTION:
B20259
END DESCRIPTION:
XS GIS Cut Line= 3
      2522676.68     13702423.04      2521256.23     13702951.09
      2520559.64     13703668.79
#Sta/Elev= 30
  3596.8  324.49    3705  320.43  3756.8  317.65  3897.3  315.08  4090.7  304.67
    4130  301.12  4160.4  295.28  4165.7  291.83  4221.1  292.92  4246.1  291.84
  4246.5  290.41    4247  289.91  4256.3  290.41  4264.2  292.49  4500.8  300.62
  4649.7  302.94    4655  302.78  4674.7  294.92    4726  295.99  4836.2  299.77
  4937.2  300.23  4992.6  299.58  5006.9  295.29  5017.5  295.65  5022.9  299.99
  5038.9  303.93  5053.3  304.64    5427   302.9  6063.7  318.54  6112.4   318.7
#Mann= 9 ,-1 , 0
  3596.8     .05       0    3705     .07       0  4090.7     .15       0
  4246.5     .05       0  4256.3     .15       0  4264.2     .05       0
  4500.8     .07       0    4726     .05       0  6063.7     .07       0
Bank Sta=4246.5,4256.3
XS Rating Curve= 0 ,0
Exp/Cntr=0.3,0.1

Type RM Length L Ch R = 1 ,31479   ,427,427,427
BEGIN DESCRIPTION:
B20258
END DESCRIPTION:
XS GIS Cut Line= 4
      2522380.98     13702148.45      2521573.06     13702555.05
      2521213.99      13702623.7      2520516.99     13703616.39
#Sta/Elev= 30
  4119.4  322.88    4294  318.34  4338.8   315.5  4372.8     312  4456.4  311.86
  4478.8  310.28  4487.8  310.62  4501.1  311.22  4506.7  310.22  4579.5  306.86
  4852.5  293.92  4941.8  292.22  4954.5  290.93  4986.5  293.03    4992   291.9
  4993.8  289.53  4994.3  289.03  5004.9  289.53  5008.8  290.86    5020  297.34
  5023.9  297.34  5032.1  300.65  5159.3  301.36  5539.7  299.82    5971  301.18
  6200.2  306.37  6244.7  309.92  6286.5  309.67  6538.4   316.2  6602.4  316.18
#Mann= 7 ,-1 , 0
  4119.4     .05       0  4487.8     .07       0  4579.5     .05       0
  4993.8     .05       0  5004.9     .05       0  5159.3     .05       0
  6538.4     .07       0
Bank Sta=4993.8,5004.9
XS Rating Curve= 0 ,0
Exp/Cntr=0.3,0.1

Type RM Length L Ch R = 1 ,31052   ,443,443,443
BEGIN DESCRIPTION:
B20257
END DESCRIPTION:
XS GIS Cut Line= 3
      2521921.56     13701673.22      2521287.91      13702407.2
      2520516.97     13703563.62
#Sta/Elev= 30
  4255.7  334.34  4423.7  323.85  4566.3  315.54  4580.6  313.37  4601.5  313.68
  4615.7  311.87  4657.6  309.71  4900.5  295.58  4934.9   292.6  4952.9  292.59
  4977.7  292.15  4984.7  289.36    4993  287.76  4993.5  287.26  5004.1  287.76
  5006.2  289.22  5041.3  291.37  5063.2  297.15  5084.1  298.57  5147.7  297.61
  5306.3  299.16  5708.9  298.72  5997.3  300.35  6126.5  302.28  6184.2   304.5
  6213.7  304.25  6264.8  307.74  6502.1  312.44  6583.8  315.11  6615.2  315.63
#Mann= 8 ,-1 , 0
  4255.7     .05       0  4423.7     .07       0  4657.6     .05       0
  4900.5     .07       0  4952.9     .05       0    4993     .05       0
  5004.1     .05       0  6583.8     .07       0
Bank Sta=4993,5004.1
XS Rating Curve= 0 ,0
Exp/Cntr=0.3,0.1