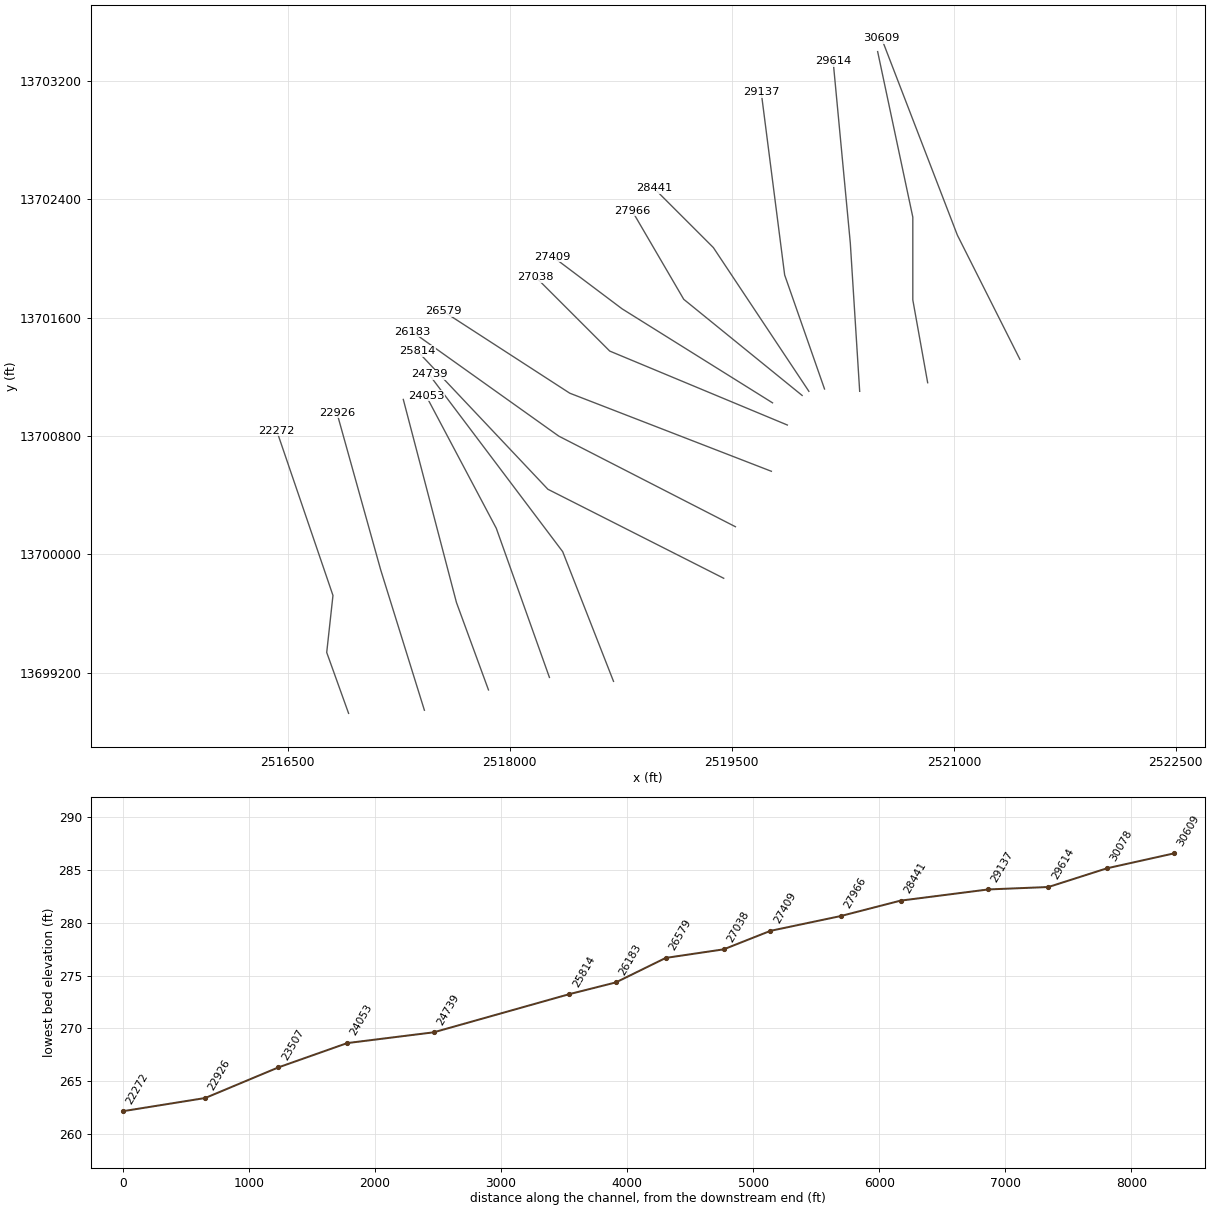
HEC-RAS study ROCKY CREEK 3.prj: ROCKY CREEK 3 Base Level Engineering

--- ROCKY CREEK 3.g01 (geometry) --- (continued)

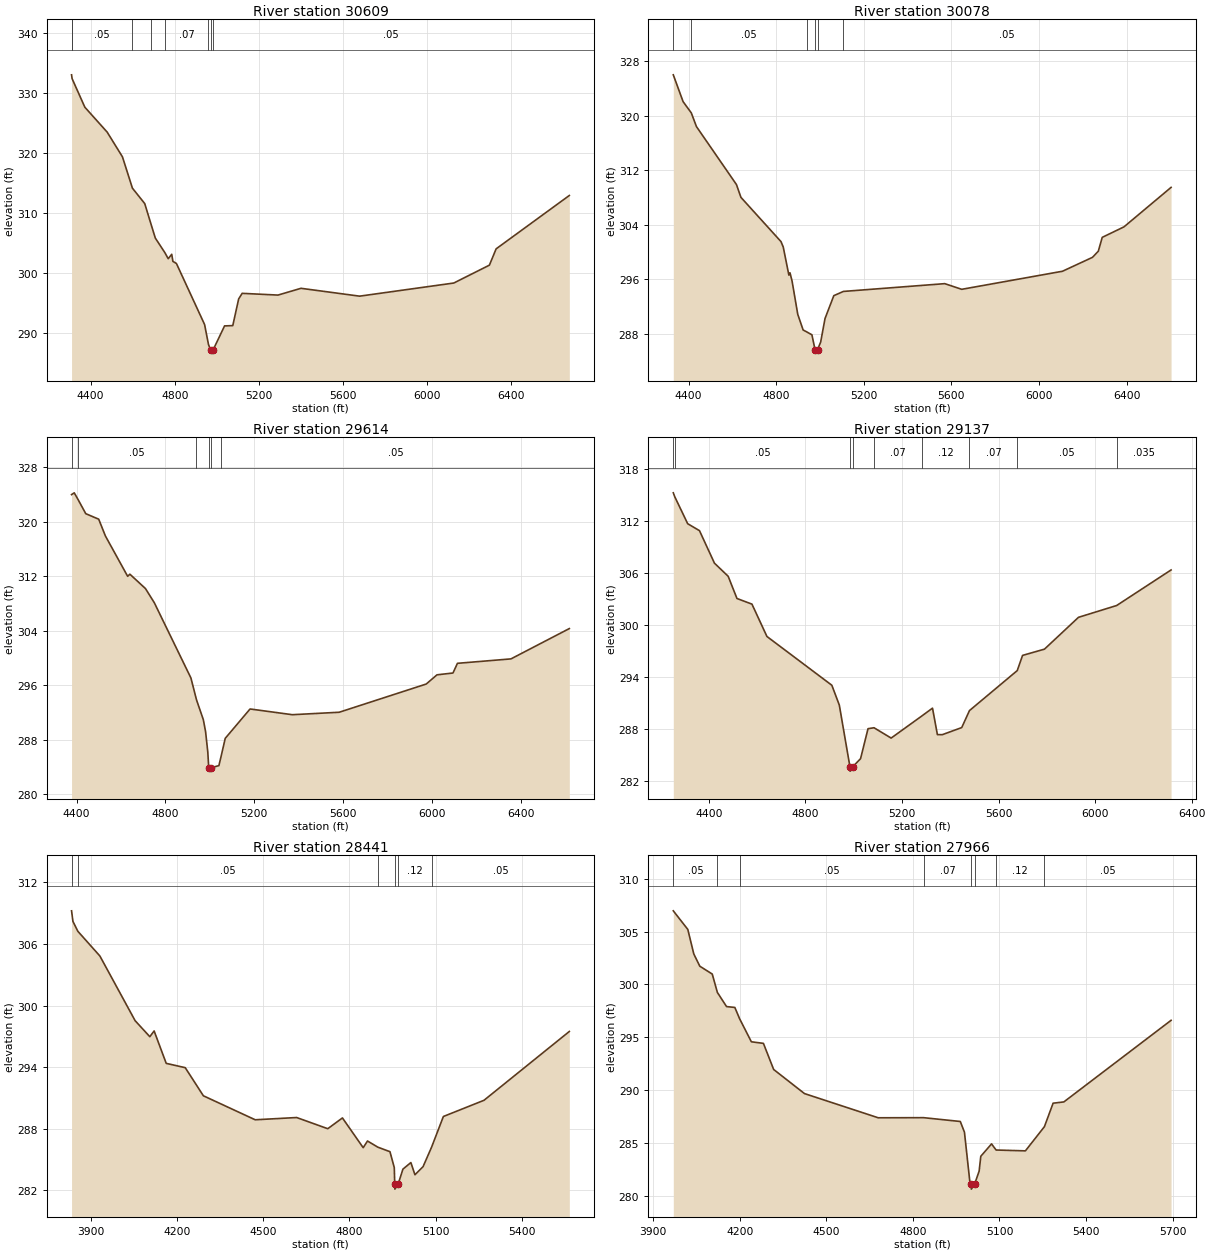
Type RM Length L Ch R = 1 ,30609   ,531,531,531
BEGIN DESCRIPTION:
B20256
END DESCRIPTION:
XS GIS Cut Line= 3
      2521446.35     13701319.38      2521023.89     13702159.01
      2520511.68     13703489.71
#Sta/Elev= 30
  4309.7  332.98  4312.3  332.34  4372.9  327.58  4478.9  323.43  4551.5  319.31
    4599  314.08  4657.5  311.51  4685.3  308.32  4707.8  305.76  4753.1  303.33
  4769.1  302.32  4785.8  303.05  4791.4  301.87  4808.1  301.52    4942  291.34
  4960.5  288.01  4970.9  287.07  4971.4  286.57    4982  287.07  5036.9  291.11
    5076  291.16  5103.9  295.61  5120.6  296.54  5290.9  296.25  5400.2  297.38
  5678.7  296.07  6126.4  298.26  6295.6  301.24  6327.6  303.96  6675.5  312.86
#Mann= 8 ,-1 , 0
  4309.7    .035       0  4312.3     .05       0    4599     .07       0
  4685.3     .05       0  4753.1     .07       0  4960.5     .05       0
  4970.9     .05       0    4982     .05       0
Bank Sta=4970.9,4982
XS Rating Curve= 0 ,0
Exp/Cntr=0.3,0.1

Type RM Length L Ch R = 1 ,30078   ,464,464,464
BEGIN DESCRIPTION:
B20255
END DESCRIPTION:
XS GIS Cut Line= 4
      2520823.23       13701161.       2520722.9     13701720.73
       2520722.9     13702280.47      2520485.28     13703399.94
#Sta/Elev= 30
  4330.5  325.98  4375.2  322.05  4412.8  320.39  4436.2  318.39    4619  309.88
  4639.3  308.01  4822.2  301.52  4832.4  300.74  4858.3   296.6  4863.4  296.94
    4873   295.7  4898.8  290.85  4923.4  288.55  4940.6  288.26  4963.4  287.85
  4977.8  285.66  4978.3  285.16    4989  285.66  5003.4  286.78  5023.4  290.25
  5063.4  293.59  5107.3  294.21    5570  295.35  5647.5  294.52  6107.6  297.17
  6244.5  299.21  6271.1  300.11    6289  302.14  6388.3  303.68  6603.3  309.47
#Mann= 6 ,-1 , 0
  4330.5    .035       0  4412.8     .05       0  4940.6     .07       0
  4977.8     .05       0    4989     .07       0  5107.3     .05       0
Bank Sta=4977.8,4989
XS Rating Curve= 0 ,0
Exp/Cntr=0.3,0.1

Type RM Length L Ch R = 1 ,29614   ,477,477,477
BEGIN DESCRIPTION:
B20254
END DESCRIPTION:
XS GIS Cut Line= 3
      2520363.83     13701102.89      2520300.46     13702106.21
      2520184.29     13703336.52
#Sta/Elev= 30
  4377.5  323.97  4389.6  324.23  4405.7  323.31  4441.5  321.17  4499.8  320.36
  4529.9   317.9  4630.1  311.98  4640.1  312.29  4710.3  310.18  4750.3  308.09
  4914.9  297.06    4940  293.86  4970.8  290.94  4980.8  289.21  4990.8  286.23
  4995.2  283.89  4995.7  283.39  5006.4  283.89  5040.9   284.2  5051.7  285.69
  5069.4   288.2  5181.2  292.51  5371.6  291.67  5582.5  292.03  5974.2  296.17
  6022.7  297.52  6094.8  297.79  6114.8  299.21  6355.9  299.86  6618.6  304.31
#Mann= 6 ,-1 , 0
  4377.5    .035       0  4405.7     .05       0    4940     .07       0
  4995.2     .05       0  5006.4     .07       0  5051.7     .05       0
Bank Sta=4995.2,5006.4
XS Rating Curve= 0 ,0
Exp/Cntr=0.3,0.1

Type RM Length L Ch R = 1 ,29137   ,696,696,696
BEGIN DESCRIPTION:
B20253
END DESCRIPTION:
XS GIS Cut Line= 3
      2520126.21     13701118.73       2519856.9     13701889.71
      2519698.48     13703125.34
#Sta/Elev= 30
  4252.3  315.24  4258.2   314.8  4311.9  311.68  4360.8  310.88  4422.9  307.13
  4479.7  305.62  4516.1  303.06  4578.2  302.41  4640.3  298.68  4909.2  293.06
  4940.2  290.77  4984.2  283.66  4984.7  283.16  4995.4  283.66  5028.1  284.59
  5059.1  288.05  5083.9  288.16  5154.9  286.97  5281.7  289.51  5326.3  290.42
  5346.5  287.37  5366.7  287.36  5447.3  288.18  5479.5  290.14  5677.4  294.75
  5699.4   296.5  5790.1  297.22  5931.2  300.89  6089.2  302.25  6314.7  306.35
#Mann= 9 ,-1 , 0
  4252.3    .035       0  4258.2     .05       0  4984.2     .05       0
  4995.4     .05       0  5083.9     .07       0  5281.7     .12       0
  5479.5     .07       0  5677.4     .05       0  6089.2    .035       0
Bank Sta=4984.2,4995.4
XS Rating Curve= 0 ,0
Exp/Cntr=0.3,0.1

Type RM Length L Ch R = 1 ,28441   ,475,475,475
BEGIN DESCRIPTION:
ROCKY CREEK 3 40.0
END DESCRIPTION:
XS GIS Cut Line= 3
      2520020.59     13701102.92        2519375.       13702075.
      2518975.01     13702474.99
#Sta/Elev= 30
  3832.9  309.23  3837.7   308.2  3854.7  307.24  3931.4  304.83  4054.2  298.52
  4105.3  296.96  4120.3  297.52  4162.4  294.36  4228.6  293.94  4291.7   291.2
  4472.1  288.86  4616.4  289.08  4724.7  287.99  4775.8  289.04    4848  286.14
    4863  286.79    4899  286.19  4941.2  285.75  4956.2   284.2  4957.8   282.6
  4958.3   282.1  4969.8   282.6  4986.3  284.05    5014  284.69  5028.1   283.5
  5056.4  284.29  5086.2   286.2  5127.1  289.18  5268.5  290.76  5565.5  297.47
#Mann= 6 ,-1 , 0
  3832.9    .035       0  3854.7     .05       0    4899     .12       0
  4957.8     .05       0  4969.8     .12       0  5086.2     .05       0
Bank Sta=4957.8,4969.8
XS Rating Curve= 0 ,0
Exp/Cntr=0.3,0.1

Type RM Length L Ch R = 1 ,27966   ,557,557,557
BEGIN DESCRIPTION:
ROCKY CREEK 3 39.0
END DESCRIPTION:
XS GIS Cut Line= 3
      2519974.99     13701075.01        2519175.       13701725.
      2518824.99     13702325.01
#Sta/Elev= 30
  3969.5  306.97  4019.8  305.21  4040.6  302.89  4061.4  301.73  4104.5  300.99
  4122.3  299.25  4154.1  297.91  4182.8  297.83  4199.4  296.76  4240.1  294.58
  4281.9  294.43  4317.4  291.96  4424.2  289.68  4679.9  287.39  4837.2   287.4
  4964.3  287.04  4978.7  286.03    4997  281.44  5002.1  281.14  5002.6  280.64
  5014.2  281.14  5029.6  282.34  5035.4  283.75  5072.6  284.92  5088.4  284.34
    5190  284.26  5255.9  286.55    5286  288.77  5323.2  288.89  5694.9  296.61
#Mann= 8 ,-1 , 0
  3969.5     .05       0  4122.3     .07       0  4199.4     .05       0
  4837.2     .07       0  5002.1     .05       0  5014.2     .07       0
  5088.4     .12       0  5255.9     .05       0
Bank Sta=5002.1,5014.2
XS Rating Curve= 0 ,0
Exp/Cntr=0.3,0.1

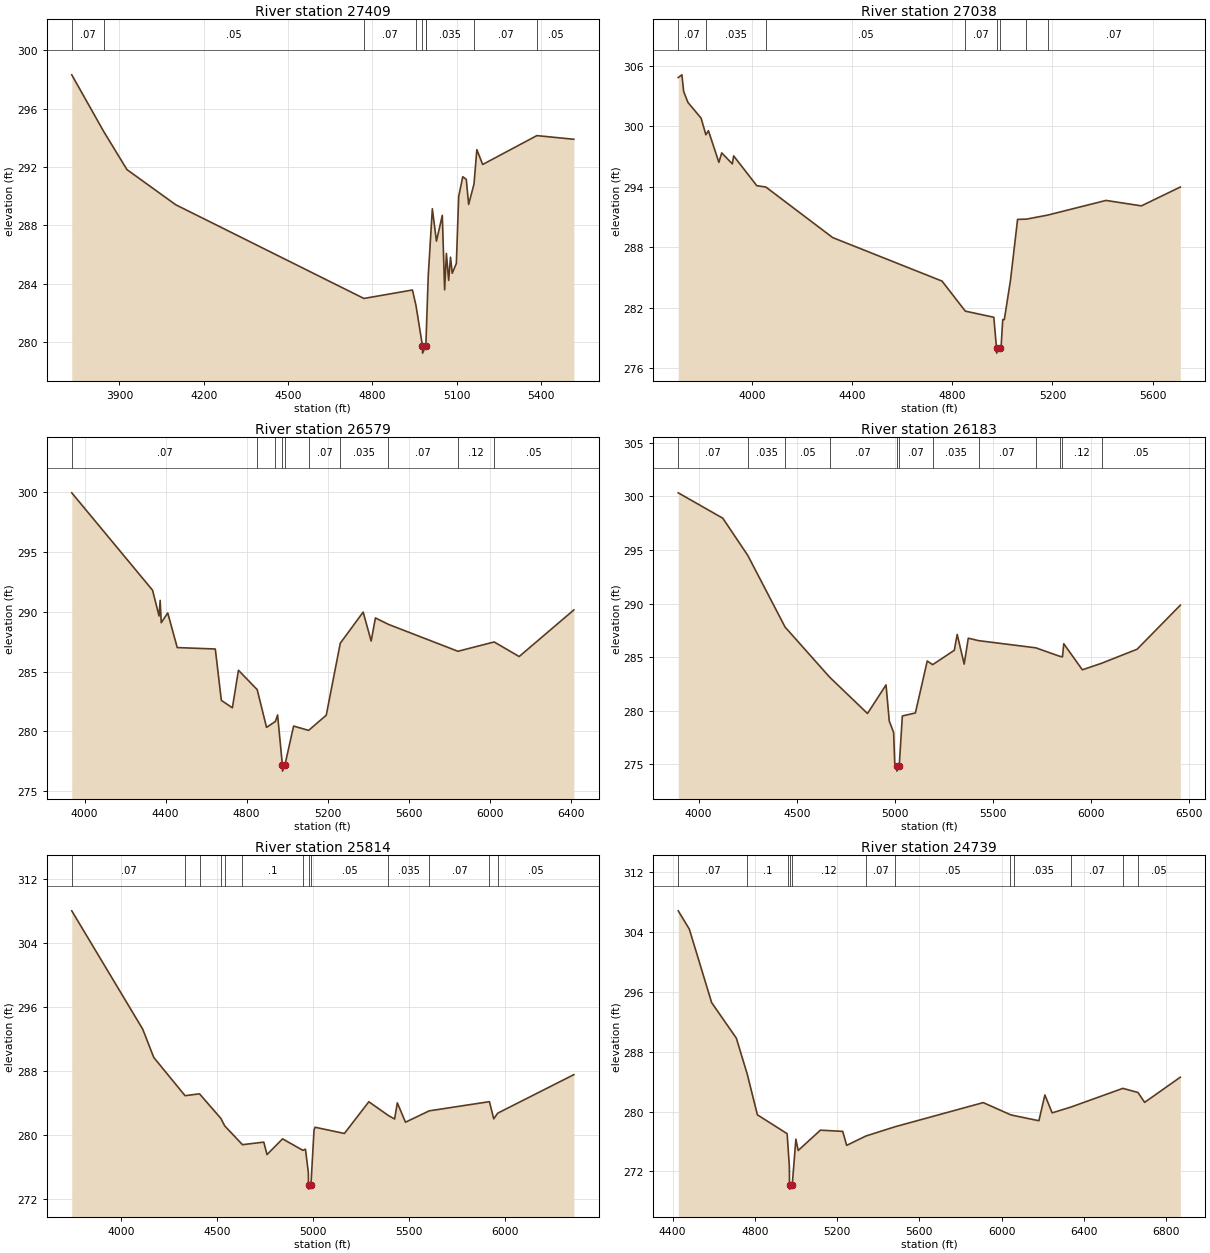
Type RM Length L Ch R = 1 ,27409   ,371,371,371
BEGIN DESCRIPTION:
ROCKY CREEK 3 38.0
END DESCRIPTION:
XS GIS Cut Line= 3
      2519775.02     13701024.99      2518758.55     13701660.54
      2518289.27     13702013.82
#Sta/Elev= 30
  3730.2  298.33  3843.9  294.44  3926.5  291.83  4099.9  289.42  4769.5  282.99
  4942.2  283.57  4954.8  282.51  4977.8  279.74  4978.3  279.24  4989.9  279.74
  4991.2   280.5  4998.5  284.58    5013  289.14  5027.6  286.92  5048.4  288.69
  5056.7  283.58    5063  286.08  5071.1  284.23  5077.6  285.82  5083.8  284.72
  5098.4  285.39  5106.7  289.98  5121.2  291.34  5133.8  291.16  5142.1  289.44
  5161.2  290.84  5171.3   293.2  5192.1  292.18  5384.7  294.16  5516.4  293.91
#Mann= 9 ,-1 , 0
  3730.2     .07       0  3843.9     .05       0  4769.5     .07       0
  4954.8     .12       0  4977.8    .035       0  4989.9     .12       0
  4991.2    .035       0  5161.2     .07       0  5384.7     .05       0
Bank Sta=4977.8,4989.9
XS Rating Curve= 0 ,0
Exp/Cntr=0.3,0.1

Type RM Length L Ch R = 1 ,27038   ,459,459,459
BEGIN DESCRIPTION:
ROCKY CREEK 3 37.0
END DESCRIPTION:
XS GIS Cut Line= 3
      2519875.04     13700874.99        2518675.       13701375.
      2518175.03     13701874.97
#Sta/Elev= 30
    3704  304.85  3718.7  305.12  3725.7  303.47  3742.5  302.39  3795.6  300.81
  3814.5  299.17  3824.8  299.57  3866.5  296.43  3877.9  297.37  3920.2  296.28
  3925.6  297.07  4018.2  294.11  4054.3  293.98  4321.5  288.96  4758.7  284.64
  4851.6  281.66  4965.6  281.05  4976.3  277.99  4976.8  277.49  4988.4  277.99
  4994.8  278.18  5001.3  280.82  5007.6  280.82  5032.3  284.74  5060.6  290.77
  5095.4  290.79  5180.3  291.19  5414.2  292.65  5555.6  292.11  5711.1  293.98
#Mann= 8 ,-1 , 0
    3704     .07       0  3814.5    .035       0  4054.3     .05       0
  4851.6     .07       0  4976.3     .05       0  4988.4     .07       0
  5095.4    .035       0  5180.3     .07       0
Bank Sta=4976.3,4988.4
XS Rating Curve= 0 ,0
Exp/Cntr=0.3,0.1

Type RM Length L Ch R = 1 ,26579   ,396,396,396
BEGIN DESCRIPTION:
B20252
END DESCRIPTION:
XS GIS Cut Line= 3
       2519767.1      13700562.2      2518404.76     13701090.24
      2517549.66     13701644.48
#Sta/Elev= 30
  3936.2  299.97  4335.3  291.82  4367.4  289.66  4372.8  290.97  4378.2   289.1
  4410.3  289.92  4457.2  287.02  4645.2   286.9  4675.1   282.6  4729.6  281.98
  4759.6  285.12  4852.2   283.5  4898.4  280.34  4942.3  280.84  4952.9  281.38
  4976.7  277.18  4977.2  276.68  4988.9  277.18    5032  280.45  5106.2  280.09
  5193.3  281.36  5262.5  287.38  5375.6  289.99  5415.1  287.57  5436.2   289.5
  5500.7  288.96  5843.8  286.71  6022.7  287.49  6146.2  286.27  6416.3  290.17
#Mann= 10 ,-1 , 0
  3936.2     .07       0  4852.2    .035       0  4942.3     .12       0
  4976.7     .05       0  4988.9     .12       0  5106.2     .07       0
  5262.5    .035       0  5500.7     .07       0  5843.8     .12       0
  6022.7     .05       0
Bank Sta=4976.7,4988.9
XS Rating Curve= 0 ,0
Exp/Cntr=0.3,0.1

Type RM Length L Ch R = 1 ,26183   ,369,369,369
BEGIN DESCRIPTION:
B20251
END DESCRIPTION:
XS GIS Cut Line= 3
      2519524.21     13700187.29      2518330.83     13700799.81
      2517339.07     13701506.71
#Sta/Elev= 30
  3895.9  300.34  4123.1  297.97  4250.7  294.49  4440.5  287.81  4667.3  283.14
  4860.7  279.74  4955.1  282.41  4971.7  279.03  4993.9  277.97  4999.5  275.09
  5009.7  274.86  5010.2  274.36  5022.4  274.86  5038.3  279.51  5104.8  279.79
  5165.2  284.64  5192.8   284.3  5303.1  285.64  5317.9  287.12  5353.5  284.35
  5374.4  286.77  5427.4  286.54  5718.7  285.87  5842.1  285.07  5854.6  285.03
  5861.2  286.25  5955.9  283.82  6054.2  284.43    6235  285.74  6455.2  289.85
#Mann= 12 ,-1 , 0
  3895.9     .07       0  4250.7    .035       0  4440.5     .05       0
  4667.3     .07       0  5009.7     .05       0  5022.4     .07       0
  5192.8    .035       0  5427.4     .07       0  5718.7     .12       0
  5842.1     .07       0  5854.6     .12       0  6054.2     .05       0
Bank Sta=5009.7,5022.4
XS Rating Curve= 0 ,0
Exp/Cntr=0.3,0.1

Type RM Length L Ch R = 1 ,25814   ,1075,1075,1075
BEGIN DESCRIPTION:
B20250
END DESCRIPTION:
XS GIS Cut Line= 3
      2519445.04     13699838.76      2518256.91     13700440.74
      2517375.08     13701375.37
#Sta/Elev= 30
  3744.3  308.06  4114.3  293.25  4171.7  289.72  4334.8  284.94  4410.1  285.17
    4522  282.08  4541.2  281.17    4634  278.81  4745.2  279.13  4761.9  277.57
    4843  279.54    4949   278.1  4962.3  278.25  4977.5  275.33  4978.2  273.75
  4978.7  273.25  4990.9  273.75  5006.9  280.62  5012.5  280.99  5165.3  280.21
  5292.7  284.18  5393.7  282.47  5427.1  282.02  5441.2  284.04  5483.7  281.62
  5607.3  283.04  5921.2  284.19  5943.7  282.04  5964.4  282.75  6361.2  287.57
#Mann= 13 ,-1 , 0
  3744.3     .07       0  4334.8     .05       0  4410.1     .07       0
    4522     .05       0  4541.2     .07       0    4634      .1       0
    4949     .05       0  4978.2     .05       0  4990.9     .05       0
  5393.7    .035       0  5607.3     .07       0  5921.2     .12       0
  5964.4     .05       0
Bank Sta=4978.2,4990.9
XS Rating Curve= 0 ,0
Exp/Cntr=0.3,0.1

Type RM Length L Ch R = 1 ,24739   ,686,686,686
BEGIN DESCRIPTION:
B20249
END DESCRIPTION:
XS GIS Cut Line= 3
      2518700.45     13699141.78      2518357.24      13700018.3
       2517454.3     13701216.94
#Sta/Elev= 30
  4427.7  306.79  4481.6  304.35  4590.2  294.54  4710.4  289.79  4763.6  284.97
  4812.7  279.56  4957.4  277.04  4963.2  274.68  4968.1  272.68    4969  270.14
  4969.5  269.64    4982  270.14  4999.9  276.31  5011.1   274.8  5119.2  277.51
  5227.8  277.35  5246.9  275.48  5340.4  276.73  5482.7  277.97  5911.2  281.19
  6043.7  279.57  6060.3  279.46  6181.9  278.77    6211  282.21  6246.4  279.82
  6338.2   280.6  6590.2  283.09  6663.9  282.54  6696.1  281.22  6869.7  284.58
#Mann= 12 ,-1 , 0
  4427.7     .07       0  4763.6      .1       0  4963.2     .12       0
    4969     .05       0    4982     .12       0  5340.4     .07       0
  5482.7     .05       0  6043.7     .07       0  6060.3    .035       0
  6338.2     .07       0  6590.2     .12       0  6663.9     .05       0
Bank Sta=4969,4982
XS Rating Curve= 0 ,0
Exp/Cntr=0.3,0.1

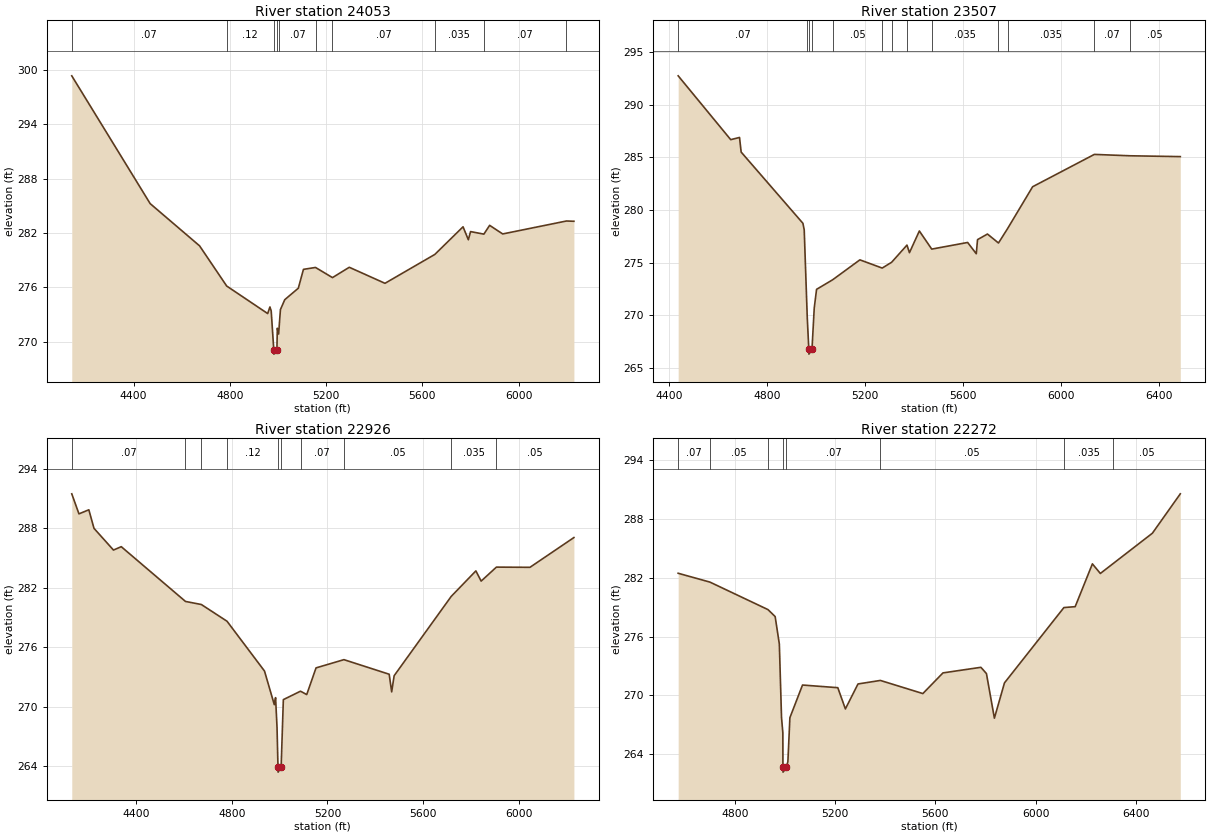
Type RM Length L Ch R = 1 ,24053   ,546,546,546
BEGIN DESCRIPTION:
B20248
END DESCRIPTION:
XS GIS Cut Line= 3
      2518267.45     13699168.19       2517908.4     13700176.72
      2517433.13     13701074.43
#Sta/Elev= 30
  4143.5  299.35  4469.2  285.24  4674.4  280.58  4787.2  276.14  4957.5   273.1
  4966.8  273.83  4972.1  273.39  4982.8  269.12  4983.3  268.62  4995.8  269.12
  4997.6  271.48  5002.9  270.84  5005.9  271.91  5010.5  273.54  5028.4  274.63
  5084.8   275.9  5106.1  277.98  5156.2  278.19  5226.7  277.07  5296.5  278.21
  5444.9  276.44    5652  279.63  5769.2  282.68  5791.2  281.25  5800.5  282.15
  5855.7  281.87  5879.7  282.84  5933.9  281.89    6199  283.32  6229.8  283.29
#Mann= 10 ,-1 , 0
  4143.5     .07       0  4787.2     .12       0  4982.8     .05       0
  4995.8     .12       0  5005.9     .07       0  5156.2     .05       0
  5226.7     .07       0    5652    .035       0  5855.7     .07       0
    6199     .05       0
Bank Sta=4982.8,4995.8
XS Rating Curve= 0 ,0
Exp/Cntr=0.3,0.1

Type RM Length L Ch R = 1 ,23507   ,581,581,581
BEGIN DESCRIPTION:
B20247
END DESCRIPTION:
XS GIS Cut Line= 3
      2517855.59     13699083.66      2517639.09     13699675.07
      2517280.02       13701048.
#Sta/Elev= 30
    4438  292.74  4652.4  286.68  4688.3  286.89    4695   285.5    4947  278.74
  4952.3  278.12  4964.7   269.8    4971  266.82  4971.5  266.32  4984.1  266.82
  4993.2   270.7  5002.7  272.47  5068.4  273.38  5179.5  275.27  5270.5  274.49
    5309  275.04  5371.6  276.67  5381.7  275.95  5422.1  278.01  5472.6  276.29
  5619.1  276.92  5654.4  275.85  5659.5  277.19    5700  277.72    5745  276.87
  5782.7  278.26  5884.3  282.21  6136.1  285.28  6280.9  285.15  6486.9  285.07
#Mann= 13 ,-1 , 0
    4438     .07       0  4964.7     .12       0    4971     .05       0
  4984.1     .12       0  5068.4     .05       0  5270.5    .035       0
    5309     .05       0  5371.6     .07       0  5472.6    .035       0
    5745     .05       0  5782.7    .035       0  6136.1     .07       0
  6280.9     .05       0
Bank Sta=4971,4984.1
XS Rating Curve= 0 ,0
Exp/Cntr=0.3,0.1

Type RM Length L Ch R = 1 ,22926   ,654,654,654
BEGIN DESCRIPTION:
B20246
END DESCRIPTION:
XS GIS Cut Line= 3
      2517422.59     13698946.37      2517126.88     13699896.85
      2516831.18     13700958.22
#Sta/Elev= 30
    4132  291.48    4162  289.46  4203.3  289.87  4224.8     288  4306.2  285.81
  4338.7  286.15  4606.9  280.63  4673.2  280.32  4780.6  278.63    4937  273.61
  4977.9  270.22  4983.2  270.93  4989.3  267.91  4993.3  263.92  4993.8  263.42
  5006.4  263.92  5015.7  270.73  5087.3  271.58  5113.3  271.24  5152.2  273.93
  5268.7  274.76  5457.7  273.29  5468.1  271.51  5478.4  273.14  5716.9  281.14
  5819.8  283.71  5841.8  282.68  5905.5  284.09  6045.7  284.07  6229.2  287.07
#Mann= 10 ,-1 , 0
    4132     .07       0  4606.9     .12       0  4673.2     .07       0
  4780.6     .12       0  4993.3     .05       0  5006.4     .12       0
  5087.3     .07       0  5268.7     .05       0  5716.9    .035       0
  5905.5     .05       0
Bank Sta=4993.3,5006.4
XS Rating Curve= 0 ,0
Exp/Cntr=0.3,0.1

Type RM Length L Ch R = 1 ,22272   ,1358,1358,1358
BEGIN DESCRIPTION:
B20245
END DESCRIPTION:
XS GIS Cut Line= 4
      2516910.39     13698925.21      2516762.53     13699337.12
      2516804.77     13699722.59      2516424.57     13700836.78
#Sta/Elev= 30
  4574.1  282.47  4700.6  281.57  4932.4  278.76  4960.9  278.05  4977.6  275.24
  4986.3  267.74  4991.6  266.18  4991.9  262.67  4992.4  262.17  5005.9  262.67
  5011.7  263.25  5019.7  267.73    5070  271.06  5210.8  270.79    5241  268.62
  5291.3  271.17  5380.5  271.53    5550  270.19  5630.2   272.3  5781.5  272.87
  5803.6  272.23  5835.3  267.68  5875.5  271.28  6112.6  278.97  6157.5  279.06
  6226.2  283.43  6257.9  282.45  6309.4  283.47  6465.5  286.56  6576.8  290.58
#Mann= 8 ,-1 , 0
  4574.1     .07       0  4700.6     .05       0  4932.4     .07       0
  4991.9     .05       0  5005.9     .07       0  5380.5     .05       0
  6112.6    .035       0  6309.4     .05       0
Bank Sta=4991.9,5005.9
XS Rating Curve= 0 ,0
Exp/Cntr=0.3,0.1