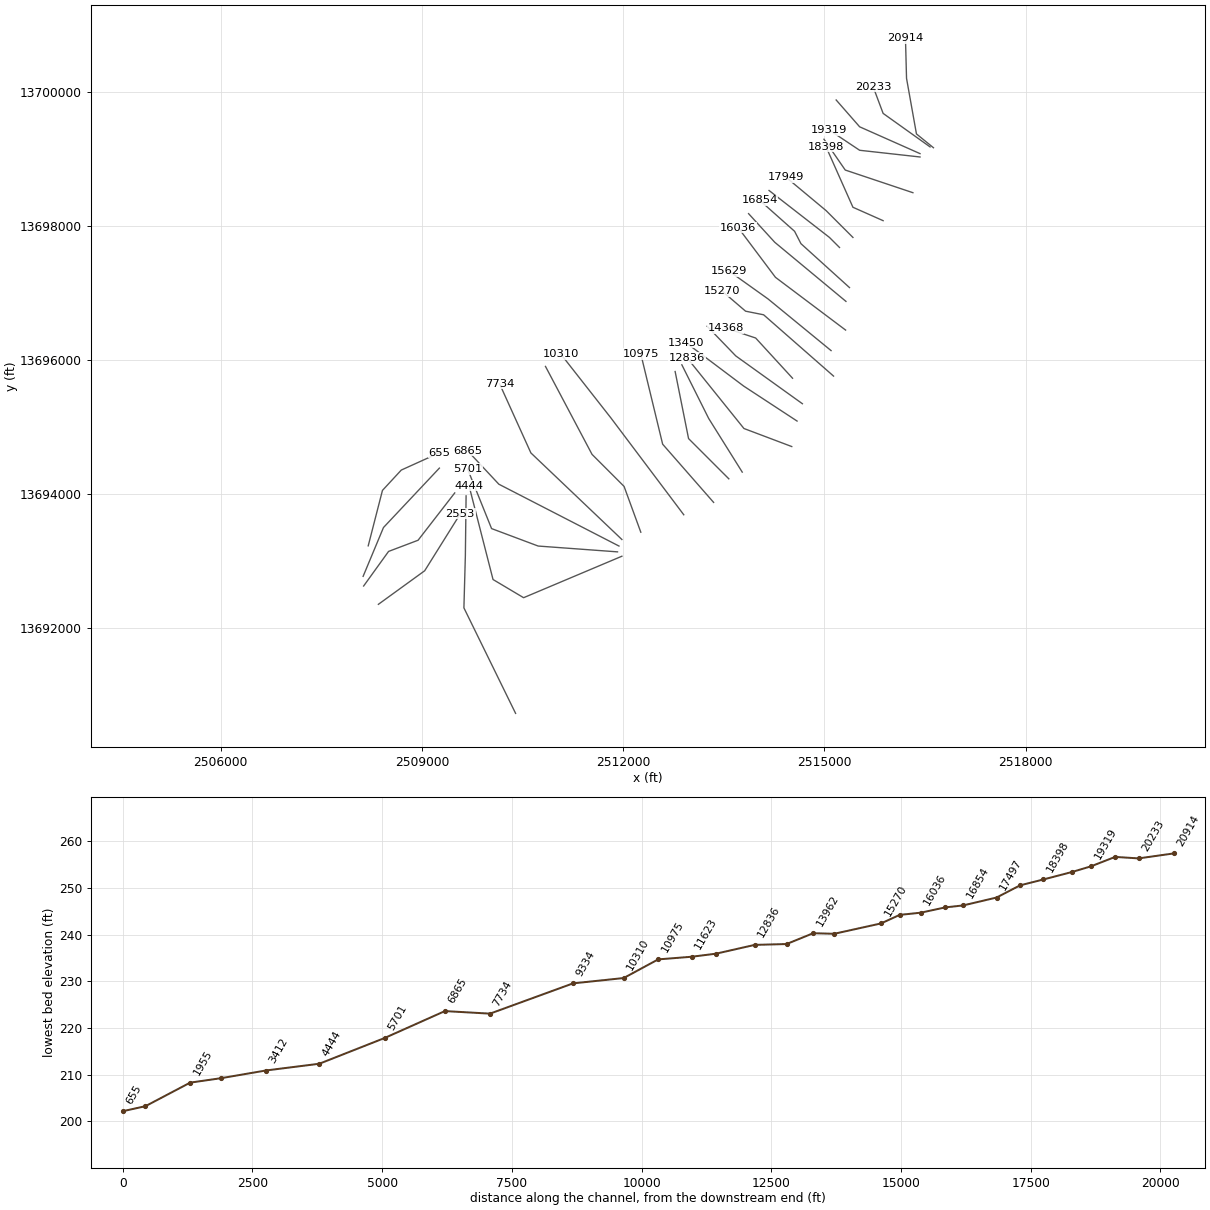
HEC-RAS study ROCKY CREEK 3.prj: ROCKY CREEK 3 Base Level Engineering

--- ROCKY CREEK 3.g01 (geometry) --- (continued)

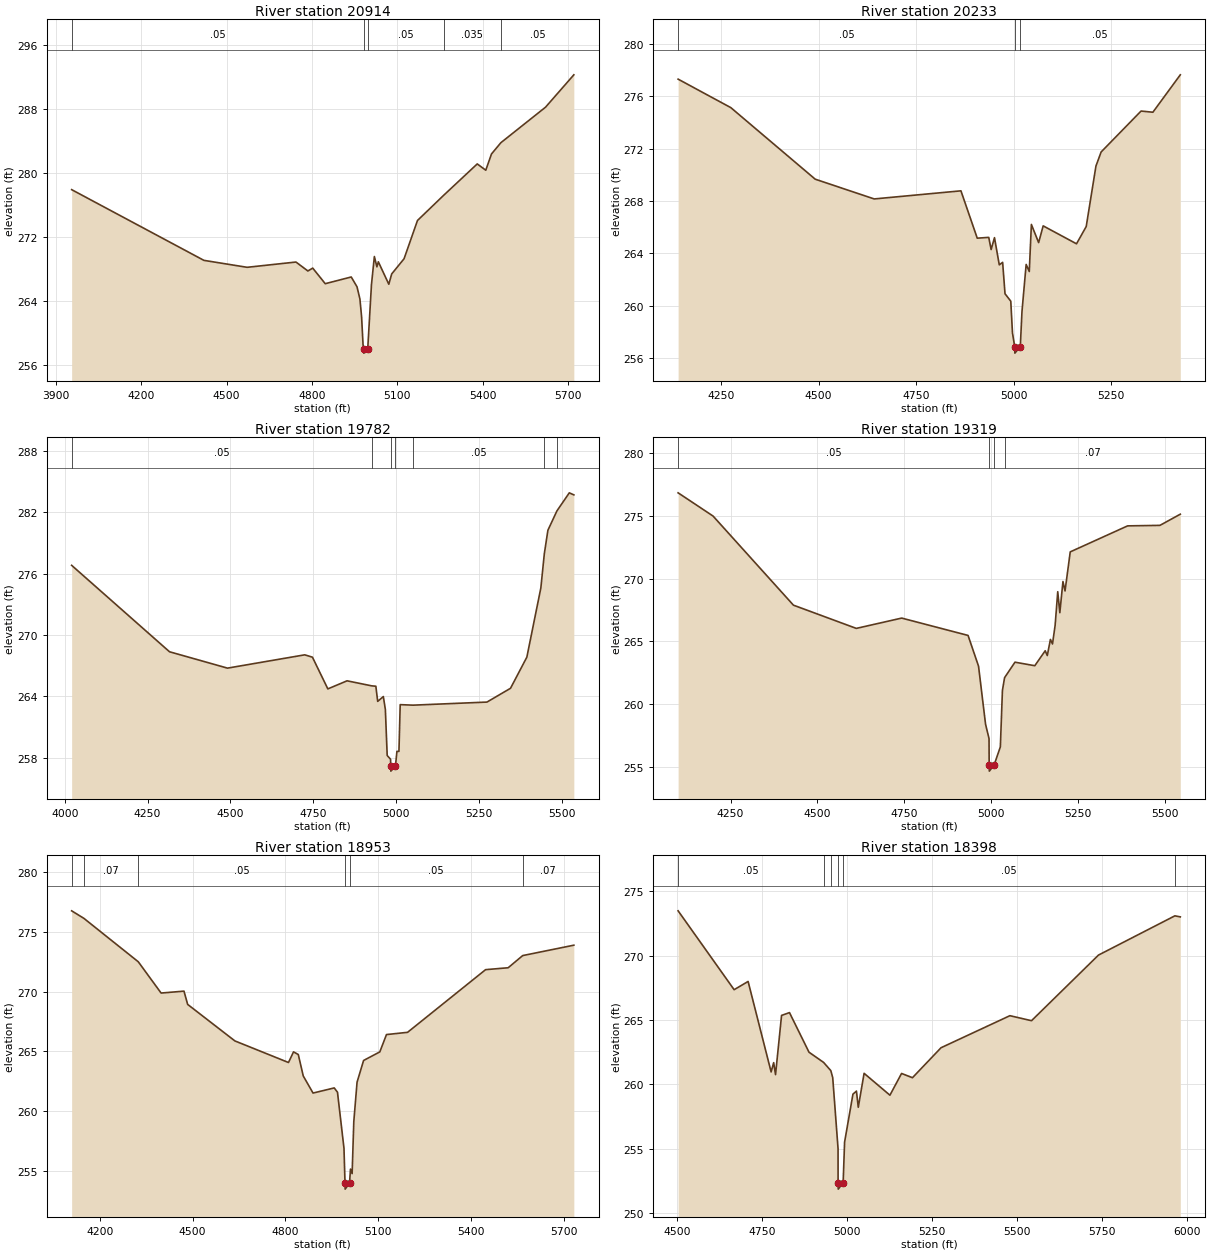
Type RM Length L Ch R = 1 ,20914   ,681,681,681
BEGIN DESCRIPTION:
B20244
END DESCRIPTION:
XS GIS Cut Line= 4
      2516625.26     13699162.84      2516371.77      13699368.8
      2516223.92     13700197.84      2516208.08     13700794.49
#Sta/Elev= 30
  3955.5   277.9  4420.5  269.05  4572.4  268.18  4744.1  268.84  4786.1  267.72
  4803.1  268.08  4847.1  266.13  4938.5  266.97  4958.8  265.74    4969  264.21
  4974.9  261.99  4979.9  258.54  4982.2  257.94  4982.7  257.44  4996.4  257.94
  5009.6  266.01  5019.8  269.53  5028.7  268.24  5033.8  268.87  5070.6  266.06
  5080.7  267.35  5124.2  269.25  5171.4  274.04  5263.4  277.19  5381.5  281.12
  5411.5  280.33  5431.5  282.36  5464.7  283.78  5621.6  288.22  5721.1  292.27
#Mann= 5 ,-1 , 0
  3955.5     .05       0  4982.2     .05       0  4996.4     .05       0
  5263.4    .035       0  5464.7     .05       0
Bank Sta=4982.2,4996.4
XS Rating Curve= 0 ,0
Exp/Cntr=0.3,0.1

Type RM Length L Ch R = 1 ,20233   ,451,451,451
BEGIN DESCRIPTION:
ROCKY CREEK 3 33.0
END DESCRIPTION:
XS GIS Cut Line= 3
      2516575.02     13699174.98        2515875.       13699675.
      2515724.99     13700075.04
#Sta/Elev= 30
  4139.7  277.32  4274.9  275.14  4491.2  269.67  4642.4  268.16  4864.8  268.78
  4906.6  265.16  4936.1  265.22  4942.2  264.29  4950.8   265.2  4963.1  263.12
  4971.7  263.31  4977.8  260.91  4992.6  260.34  4996.9  257.92  5002.6  256.87
  5003.1  256.37    5017  256.87  5021.3  259.56    5032  263.15    5040  262.61
  5045.4  266.21    5064  264.82  5075.6   266.1  5161.1  264.73    5186  266.05
  5210.9  270.67  5224.2  271.75  5326.6  274.88  5356.9  274.79  5427.2  277.65
#Mann= 3 ,-1 , 0
  4139.7     .05       0  5002.6     .05       0    5017     .05       0
Bank Sta=5002.6,5017
XS Rating Curve= 0 ,0
Exp/Cntr=0.3,0.1

Type RM Length L Ch R = 1 ,19782   ,463,463,463
BEGIN DESCRIPTION:
ROCKY CREEK 3 32.0
END DESCRIPTION:
XS GIS Cut Line= 3
      2516425.04     13699074.98        2515525.       13699475.
      2515175.03     13699874.97
#Sta/Elev= 30
  4020.7  276.81  4316.2  268.36  4491.3  266.76  4724.5  268.06  4747.8  267.83
  4794.3  264.73  4852.4  265.52  4926.3  265.03  4939.3  264.99  4944.8  263.51
  4961.9  263.98    4968  262.71  4973.5  258.22  4983.7  257.85  4984.1  257.19
  4984.6  256.69  4998.5  257.19  5002.9  258.62    5009  258.62  5012.8  263.19
    5052  263.14  5274.7  263.44  5345.9  264.79  5395.2  267.83  5437.5   274.6
    5448  277.95  5458.8  280.24    5486  282.13  5523.4   283.9  5537.1   283.7
#Mann= 7 ,-1 , 0
  4020.7     .05       0  4926.3     .07       0  4984.1     .05       0
  4998.5     .07       0    5052     .05       0    5448     .07       0
    5486     .05       0
Bank Sta=4984.1,4998.5
XS Rating Curve= 0 ,0
Exp/Cntr=0.3,0.1

Type RM Length L Ch R = 1 ,19319   ,366,366,366
BEGIN DESCRIPTION:
ROCKY CREEK 3 31.0
END DESCRIPTION:
XS GIS Cut Line= 3
      2516425.04       13699025.        2515525.       13699125.
      2515075.01     13699424.99
#Sta/Elev= 30
  4098.8  276.83  4199.5  274.98  4430.9  267.89    4612  266.04  4742.8  266.86
  4933.9  265.48  4964.1  263.03  4984.3  258.41  4994.3  257.27  4994.7  255.18
  4995.2  254.68  5009.1  255.18  5026.9  256.61  5032.9  261.11  5039.1  262.12
    5069  263.35  5126.1  263.07  5156.1  264.26  5162.1  263.88  5171.1  265.16
  5177.1   264.8  5184.7  266.29  5192.2  268.96  5198.2  267.29  5207.2  269.77
  5213.2  269.02  5228.2  272.13  5393.5   274.2  5486.6  274.24  5545.2  275.13
#Mann= 4 ,-1 , 0
  4098.8     .05       0  4994.7     .05       0  5009.1     .05       0
  5039.1     .07       0
Bank Sta=4994.7,5009.1
XS Rating Curve= 0 ,0
Exp/Cntr=0.3,0.1

Type RM Length L Ch R = 1 ,18953   ,555,555,555
BEGIN DESCRIPTION:
B20243
END DESCRIPTION:
XS GIS Cut Line= 3
      2516318.97     13698492.24      2515310.39     13698830.19
      2514993.54     13699289.63
#Sta/Elev= 30
  4109.5  276.78    4149  276.15  4324.7  272.51  4398.4  269.89  4472.3  270.05
  4484.1  268.94  4636.6  265.88  4809.8  264.07    4826  264.96  4841.4  264.74
  4857.5  262.94  4889.1  261.51  4957.5  261.94    4968  261.58    4989  256.88
  4992.3  253.96  4992.8  253.46  5006.9  253.96    5010  255.14  5015.3  254.76
  5020.7  259.12  5031.2  262.42  5052.3  264.24  5104.7  264.96  5126.2  266.41
  5194.4   266.6  5446.3  271.85  5519.2  272.01  5566.2  273.03  5731.3   273.9
#Mann= 6 ,-1 , 0
  4109.5     .05       0    4149     .07       0  4324.7     .05       0
  4992.3     .05       0  5006.9     .05       0  5566.2     .07       0
Bank Sta=4992.3,5006.9
XS Rating Curve= 0 ,0
Exp/Cntr=0.3,0.1

Type RM Length L Ch R = 1 ,18398   ,449,449,449
BEGIN DESCRIPTION:
ROCKY CREEK 3 30.0
END DESCRIPTION:
XS GIS Cut Line= 3
      2515874.99     13698075.01        2515425.       13698275.
      2515025.01     13699174.99
#Sta/Elev= 30
  4503.3  273.48  4668.1  267.35  4709.2  267.99  4776.9  260.96  4784.4  261.68
  4789.9  260.75  4807.6  265.35  4830.9  265.57  4888.4  262.49  4931.2   261.7
  4952.5  261.06  4958.1  260.52  4973.8  254.99  4973.9  252.35  4974.4  251.85
  4988.8  252.35    4993   255.5  5017.6  259.23  5027.9  259.47  5033.3  258.21
  5050.4  260.85  5126.4  259.15  5160.6  260.84  5192.7  260.51  5276.8  262.84
  5479.3  265.33  5542.9  264.94  5739.9  270.04  5964.6  273.09  5980.6  273.01
#Mann= 6 ,-1 , 0
  4503.3     .05       0  4931.2     .12       0  4952.5     .05       0
  4973.9     .05       0  4988.8     .05       0  5964.6     .07       0
Bank Sta=4973.9,4988.8
XS Rating Curve= 0 ,0
Exp/Cntr=0.3,0.1

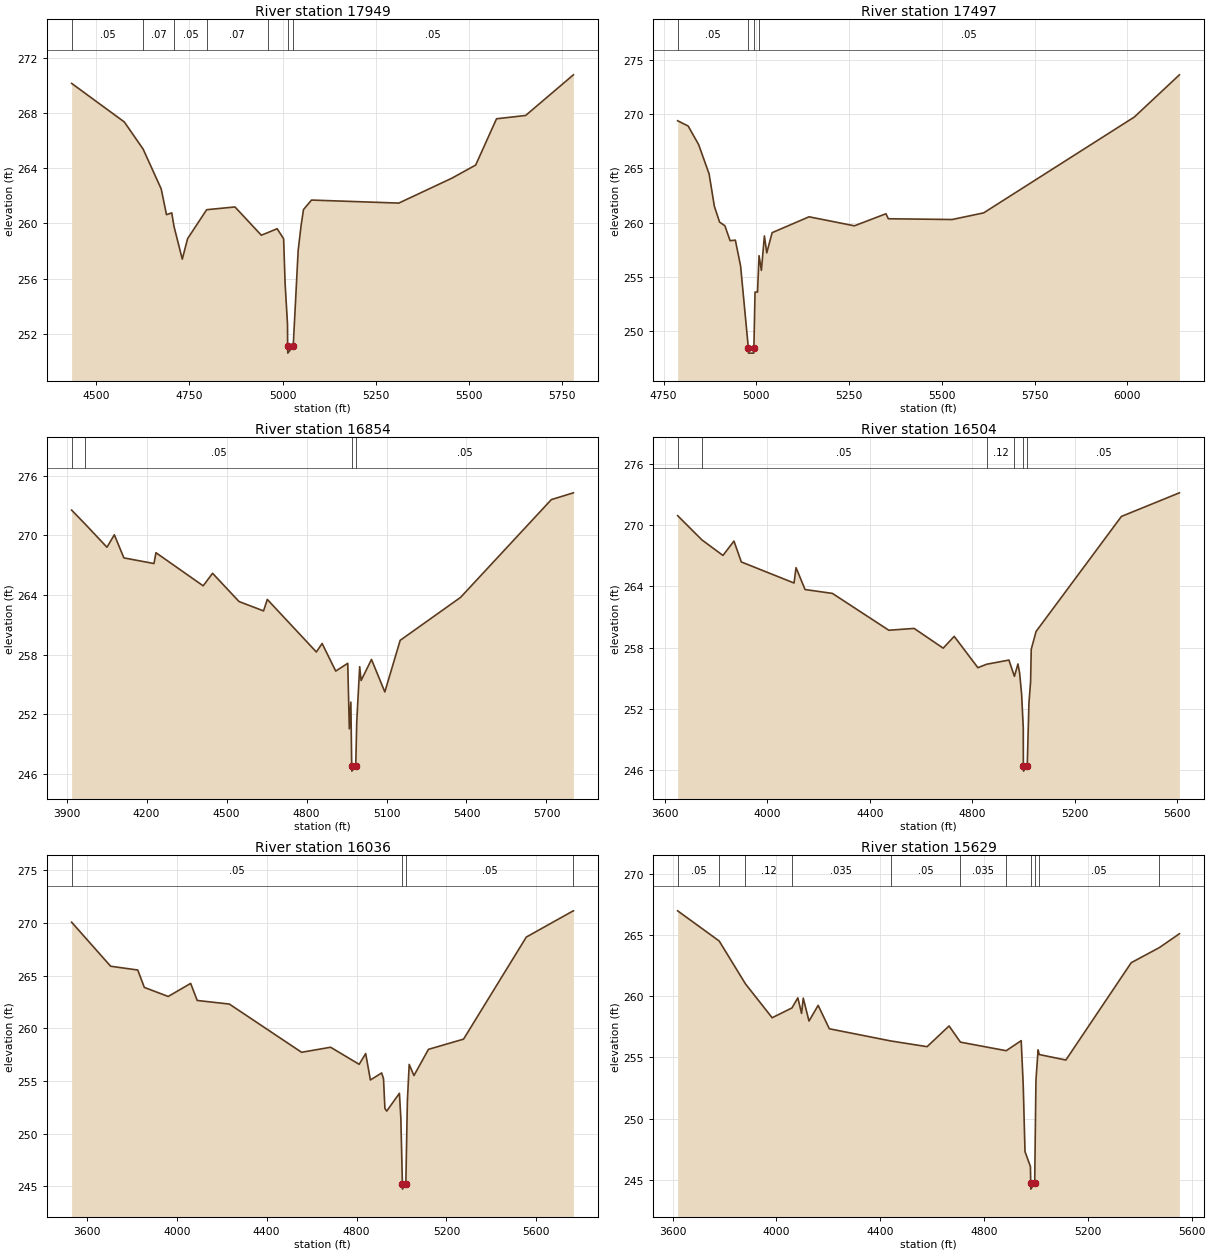
Type RM Length L Ch R = 1 ,17949   ,452,452,452
BEGIN DESCRIPTION:
ROCKY CREEK 3 29.0
END DESCRIPTION:
XS GIS Cut Line= 3
      2515425.01     13697824.99        2515025.       13698225.
      2514425.02     13698724.98
#Sta/Elev= 30
  4433.7  270.17  4575.1  267.37  4625.6   265.4  4674.1  262.51  4688.3  260.64
  4702.4  260.77  4708.6  259.77  4730.7  257.41  4744.8  258.89  4796.1     261
  4872.1   261.2  4942.8  259.15  4959.5  259.33  4985.3  259.62  5002.7  258.89
  5006.6  255.67  5013.1  252.68  5013.4  251.09  5013.9  250.59  5028.4  251.09
  5041.7  258.04  5049.5  259.84    5056  261.01  5077.5   261.7  5311.8  261.48
  5454.4  263.29  5518.1  264.24  5574.1   267.6  5652.2  267.84  5780.4  270.79
#Mann= 7 ,-1 , 0
  4433.7     .05       0  4625.6     .07       0  4708.6     .05       0
  4796.1     .07       0  4959.5     .05       0  5013.4     .05       0
  5028.4     .05       0
Bank Sta=5013.4,5028.4
XS Rating Curve= 0 ,0
Exp/Cntr=0.3,0.1

Type RM Length L Ch R = 1 ,17497   ,643,643,643
BEGIN DESCRIPTION:
ROCKY CREEK 3 28.0
END DESCRIPTION:
XS GIS Cut Line= 3
      2515224.99     13697675.01        2515075.       13697825.
        2514175.       13698525.
#Sta/Elev= 30
    4788  269.37  4816.3  268.89  4844.6  267.18  4872.8  264.48    4887   261.5
  4901.1  260.04  4915.3  259.71  4929.4  258.33  4943.6  258.38  4957.7  255.99
  4978.5  248.48    4979  247.98    4993  247.98  4993.5  248.48  4996.6   253.6
  5003.3   253.6    5006  255.81  5007.4  256.95  5013.7   255.6  5021.8  258.77
  5028.2  257.21  5042.7  259.07  5142.2  260.53  5264.4   259.7  5349.4  260.81
  5355.8  260.35  5527.7  260.28  5612.7  260.89    6019  269.72  6140.3   273.6
#Mann= 4 ,-1 , 0
    4788     .05       0  4978.5     .05       0  4993.5     .05       0
    5006     .05       0
Bank Sta=4978.5,4993.5
XS Rating Curve= 0 ,0
Exp/Cntr=0.3,0.1

Type RM Length L Ch R = 1 ,16854   ,350,350,350
BEGIN DESCRIPTION:
B20242
END DESCRIPTION:
XS GIS Cut Line= 4
      2515373.79     13697077.04      2514650.33     13697731.85
      2514555.28     13697916.66       2514033.3     13698380.65
#Sta/Elev= 30
    3919  272.53  3970.5  271.11  4051.5   268.8  4079.2  270.05    4115  267.73
  4227.9  267.16  4235.3  268.25  4412.4  264.92  4447.6  266.18  4546.9  263.34
  4638.8   262.4    4653  263.55  4836.9  258.27  4858.5  259.12  4909.6  256.35
  4954.6  257.13  4960.6  250.54  4966.3  253.23  4969.5  246.79    4970  246.29
  4984.6  246.79  4988.4  251.25  4999.4  256.79  5004.8   255.4  5043.7  257.52
  5093.7  254.25  5151.3  259.44  5377.9  263.76  5718.3  273.59    5801  274.27
#Mann= 4 ,-1 , 0
    3919     .07       0  3970.5     .05       0  4969.5     .05       0
  4984.6     .05       0
Bank Sta=4969.5,4984.6
XS Rating Curve= 0 ,0
Exp/Cntr=0.3,0.1

Type RM Length L Ch R = 1 ,16504   ,468,468,468
BEGIN DESCRIPTION:
ROCKY CREEK 3 27.0
END DESCRIPTION:
XS GIS Cut Line= 3
      2515320.97     13696871.11      2514259.57     13697752.97
      2513869.75     13698179.67
#Sta/Elev= 30
  3650.3  270.96  3745.3  268.57  3827.1  267.05  3870.1  268.46  3898.8  266.41
  4104.5  264.34  4112.3  265.85  4147.5   263.7  4254.2  263.32  4474.3   259.7
  4573.2  259.88  4686.5  257.94  4729.5   259.1  4821.9  256.02  4855.8  256.36
    4943  256.77  4964.4  255.17  4978.2  256.39  4984.7  255.51  4992.5  253.42
    4999  250.09  4999.3  246.36  4999.8  245.86  5014.4  246.36  5021.1  252.54
  5027.6  254.66    5030  257.82  5048.9  259.58  5381.9  270.88  5608.2   273.2
#Mann= 6 ,-1 , 0
  3650.3     .07       0  3745.3     .05       0  4855.8     .12       0
  4964.4     .05       0  4999.3     .05       0  5014.4     .05       0
Bank Sta=4999.3,5014.4
XS Rating Curve= 0 ,0
Exp/Cntr=0.3,0.1

Type RM Length L Ch R = 1 ,16036   ,407,407,407
BEGIN DESCRIPTION:
ROCKY CREEK 3 26.0
END DESCRIPTION:
XS GIS Cut Line= 3
      2515315.69     13696443.39      2514270.13      13697230.2
      2513715.69     13697969.45
#Sta/Elev= 30
  3532.3  270.07  3705.9  265.89  3826.6  265.53  3855.8  263.88    3962  263.02
    4062  264.26  4091.1  262.64    4234   262.3  4555.5  257.72  4684.6   258.2
  4811.6  256.58  4840.7   257.6  4861.7  255.09  4911.7  255.76    4920  255.21
  4926.2  252.39  4934.3  252.14  4990.8  253.83  4997.1  251.48  5004.1  245.23
  5004.6  244.73  5019.3  245.23  5026.2  253.12  5034.3  256.57  5055.4  255.51
    5120     258  5276.2  258.97  5555.4  268.66  5764.2  271.15  5764.9  271.15
#Mann= 4 ,-1 , 0
  3532.3     .05       0  5004.1     .05       0  5019.3     .05       0
  5764.2    .035       0
Bank Sta=5004.1,5019.3
XS Rating Curve= 0 ,0
Exp/Cntr=0.3,0.1

Type RM Length L Ch R = 1 ,15629   ,359,359,359
BEGIN DESCRIPTION:
ROCKY CREEK 3 25.0
END DESCRIPTION:
XS GIS Cut Line= 3
      2515099.19     13696137.12      2514159.24     13696908.09
      2513575.03     13697324.98
#Sta/Elev= 30
  3619.5  266.96  3779.6   264.5  3880.9     261  3983.7  258.24    4060  259.04
  4082.7  259.86    4097  258.59  4103.5  259.84  4125.7  257.97  4160.9  259.25
    4204  257.34  4439.7  256.35  4580.7  255.88  4665.4  257.57  4709.1  256.25
  4885.5  255.55  4943.3  256.37    4951  252.82    4958  247.32  4978.9   246.1
  4979.9  244.76  4980.4  244.26  4995.3  244.76  5000.1  253.13  5008.4  255.62
  5012.7  255.24  5115.4  254.79  5367.3  262.73  5475.6  263.96  5552.9  265.09
#Mann= 11 ,-1 , 0
  3619.5     .05       0  3779.6    .035       0  3880.9     .12       0
    4060    .035       0  4439.7     .05       0  4709.1    .035       0
  4885.5      .1       0  4979.9     .05       0  4995.3      .1       0
  5012.7     .05       0  5475.6     .07       0
Bank Sta=4979.9,4995.3
XS Rating Curve= 0 ,0
Exp/Cntr=0.3,0.1

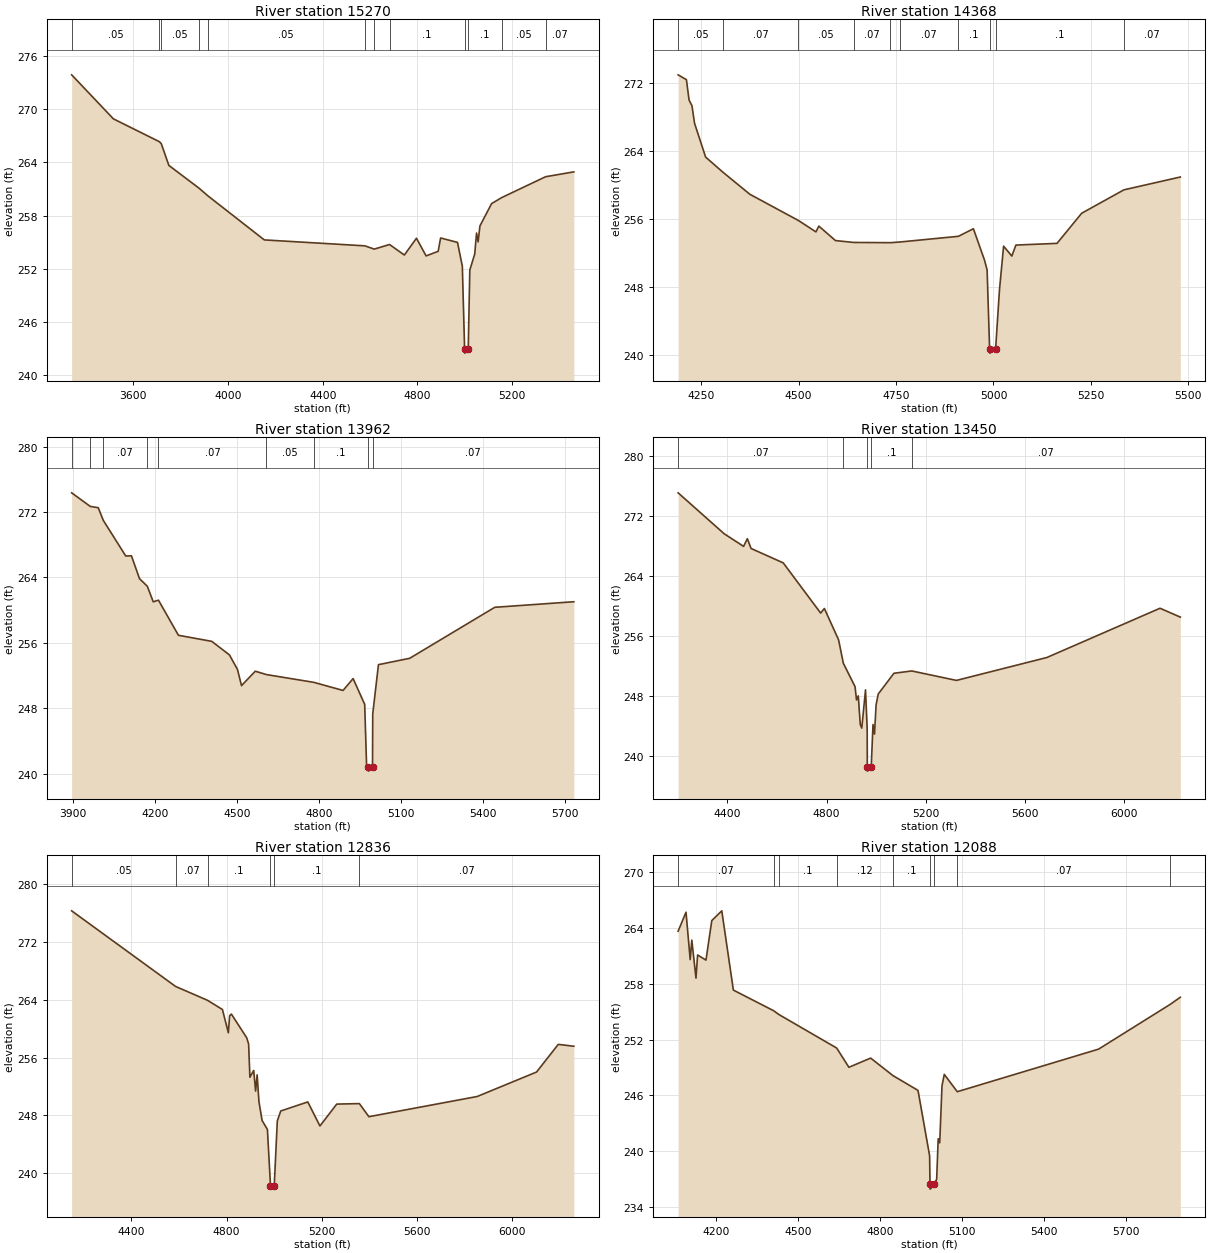
Type RM Length L Ch R = 1 ,15270   ,902,902,902
BEGIN DESCRIPTION:
ROCKY CREEK 3 24.0
END DESCRIPTION:
XS GIS Cut Line= 4
      2515136.14     13695756.94      2514093.92     13696671.22
        2513825.       13696725.      2513475.02     13697024.98
#Sta/Elev= 30
  3339.3  273.92  3515.6  268.94  3710.2  266.35  3718.1  266.12    3750  263.67
  3876.7  261.11  3913.8  260.25  4153.3  255.24    4578  254.57  4617.6   254.2
  4682.2  254.72    4745  253.53    4796  255.43  4836.8  253.43  4887.8  253.95
    4898  255.46  4969.4  254.96  4989.8  252.27  4999.4  242.93  4999.9  242.43
  5014.8  242.93  5021.4  251.83  5042.2  253.65  5049.9  256.02  5056.5  255.02
  5064.2  256.82  5113.5  259.35    5157  260.04  5341.7  262.39  5460.9  262.94
#Mann= 12 ,-1 , 0
  3339.3     .05       0  3710.2     .12       0  3718.1     .05       0
  3876.7     .12       0  3913.8     .05       0    4578     .07       0
  4617.6     .05       0  4682.2      .1       0  4999.4     .05       0
  5014.8      .1       0    5157     .05       0  5341.7     .07       0
Bank Sta=4999.4,5014.8
XS Rating Curve= 0 ,0
Exp/Cntr=0.3,0.1

Type RM Length L Ch R = 1 ,14368   ,406,406,406
BEGIN DESCRIPTION:
ROCKY CREEK 3 23.0
END DESCRIPTION:
XS GIS Cut Line= 3
        2514525.       13695725.        2513975.       13696325.
      2513524.98     13696475.01
#Sta/Elev= 30
    4191  272.92  4212.3  272.35  4219.1  269.95  4226.5  269.29  4233.2  267.22
  4261.6  263.25  4305.8  261.48  4375.1  258.88  4499.6   255.8  4544.6  254.46
    4552  255.14  4594.6  253.44  4641.1  253.22  4735.8  253.19  4759.8  253.27
  4910.1  253.94  4948.5  254.83  4976.9  251.16  4983.7  249.99  4990.1  240.71
  4990.6  240.21  5005.5  240.71  5015.5   247.7    5026  252.78  5047.1  251.62
  5057.6  252.91    5163  253.11  5226.3  256.65  5334.6   259.4  5479.3  260.91
#Mann= 10 ,-1 , 0
    4191     .05       0  4305.8     .07       0  4499.6     .05       0
  4641.1     .07       0  4735.8     .05       0  4759.8     .07       0
  4910.1      .1       0  4990.1     .05       0  5005.5      .1       0
  5334.6     .07       0
Bank Sta=4990.1,5005.5
XS Rating Curve= 0 ,0
Exp/Cntr=0.3,0.1

Type RM Length L Ch R = 1 ,13962   ,512,512,512
BEGIN DESCRIPTION:
B20241
END DESCRIPTION:
XS GIS Cut Line= 3
      2514671.48     13695345.04      2513678.72     13696057.93
      2513251.69     13696500.78
#Sta/Elev= 30
  3895.7  274.34  3963.9  272.68    3993  272.52  4011.4  270.98  4093.6  266.62
  4114.5  266.64    4144  263.85  4172.6  262.92  4194.3  261.02  4213.4  261.22
  4286.4  256.93  4408.4  256.19  4473.1  254.53  4502.5  252.75  4517.2  250.78
  4567.6  252.54  4608.2  252.13  4781.7  251.18  4888.6  250.19  4925.5  251.64
  4967.9  248.49  4974.7  241.11  4981.1  240.83  4981.6  240.33  4996.5  240.83
  4997.3  247.32  5018.2  253.34  5132.6  254.12  5443.8  260.35  5733.1  261.03
#Mann= 9 ,-1 , 0
  3895.7     .07       0  3963.9     .05       0  4011.4     .07       0
  4172.6     .05       0  4213.4     .07       0  4608.2     .05       0
  4781.7      .1       0  4981.1     .05       0  4996.5     .07       0
Bank Sta=4981.1,4996.5
XS Rating Curve= 0 ,0
Exp/Cntr=0.3,0.1

Type RM Length L Ch R = 1 ,13450   ,614,614,614
BEGIN DESCRIPTION:
B20240
END DESCRIPTION:
XS GIS Cut Line= 3
      2514592.27      13695086.3      2513794.89     13695609.09
      2512939.74     13696253.09
#Sta/Elev= 30
  4201.7  275.07  4387.3  269.62  4465.6  267.94  4480.7  268.96  4495.8  267.66
  4625.4  265.74  4776.1  259.06  4791.2  259.67  4848.5  255.49  4867.7  252.37
  4914.8  249.26  4920.8  247.49  4927.8  248.03  4935.9  244.22  4941.9  243.74
    4957  248.83  4963.7  243.62  4964.2  238.51  4964.7  238.01  4979.9  238.51
  4987.2  244.22  4993.2  242.94  4999.6  246.83  5008.3  248.28  5071.5  251.04
  5143.3  251.35  5323.5  250.09  5687.9  253.14    6144   259.7  6225.7  258.52
#Mann= 5 ,-1 , 0
  4201.7     .07       0  4867.7      .1       0  4964.2     .05       0
  4979.9      .1       0  5143.3     .07       0
Bank Sta=4964.2,4979.9
XS Rating Curve= 0 ,0
Exp/Cntr=0.3,0.1

Type RM Length L Ch R = 1 ,12836   ,748,748,748
BEGIN DESCRIPTION:
ROCKY CREEK 3 22.0
END DESCRIPTION:
XS GIS Cut Line= 3
      2514513.01     13694706.13      2513800.17     13694975.43
      2512955.27     13696026.28
#Sta/Elev= 30
  4148.9  276.26  4585.6  265.82  4720.1   263.9  4782.6  262.63  4807.4  259.42
  4812.8  261.77  4820.2     262  4884.4  258.74  4892.6  257.88    4898  253.28
    4914  254.21    4922  251.37  4928.4  253.61    4936  249.91  4949.2  247.31
  4971.6  246.07  4984.5  238.33    4985  237.83  5000.3  238.33  5013.2  247.25
  5027.6  248.62  5141.3  249.87  5192.3  246.55  5262.8  249.57  5358.1  249.64
    5398  247.83  5853.1  250.62  6102.7     254  6193.9  257.82  6259.3  257.56
#Mann= 6 ,-1 , 0
  4148.9     .05       0  4585.6     .07       0  4720.1      .1       0
  4984.5     .05       0  5000.3      .1       0  5358.1     .07       0
Bank Sta=4984.5,5000.3
XS Rating Curve= 0 ,0
Exp/Cntr=0.3,0.1

Type RM Length L Ch R = 1 ,12088   ,465,465,465
BEGIN DESCRIPTION:
ROCKY CREEK 3 21.0
END DESCRIPTION:
XS GIS Cut Line= 3
      2513774.98     13694325.03        2513275.       13695125.
        2512875.     13695925.01
#Sta/Elev= 30
  4060.9  263.63  4089.8  265.67  4105.1  260.59    4111  262.67  4126.3   258.6
  4132.2  261.08  4162.9  260.53  4184.1  264.77  4220.7  265.82  4263.1  257.31
  4410.8  255.09  4429.5  254.69  4641.1  251.09  4685.9  249.02  4765.5  250.01
  4847.1  248.13  4938.8  246.54  4981.3  239.52  4982.7  236.44  4983.2  235.94
  4998.7  236.44  5007.1  237.01  5012.7  241.35  5018.2  240.91  5026.6  247.04
    5035  248.26  5082.5   246.4  5599.6  250.97  5861.4  255.77  5898.7  256.54
#Mann= 9 ,-1 , 0
  4060.9     .07       0  4410.8     .12       0  4429.5      .1       0
  4641.1     .12       0  4847.1      .1       0  4982.7     .05       0
  4998.7      .1       0  5082.5     .07       0  5861.4    .035       0
Bank Sta=4982.7,4998.7
XS Rating Curve= 0 ,0
Exp/Cntr=0.3,0.1

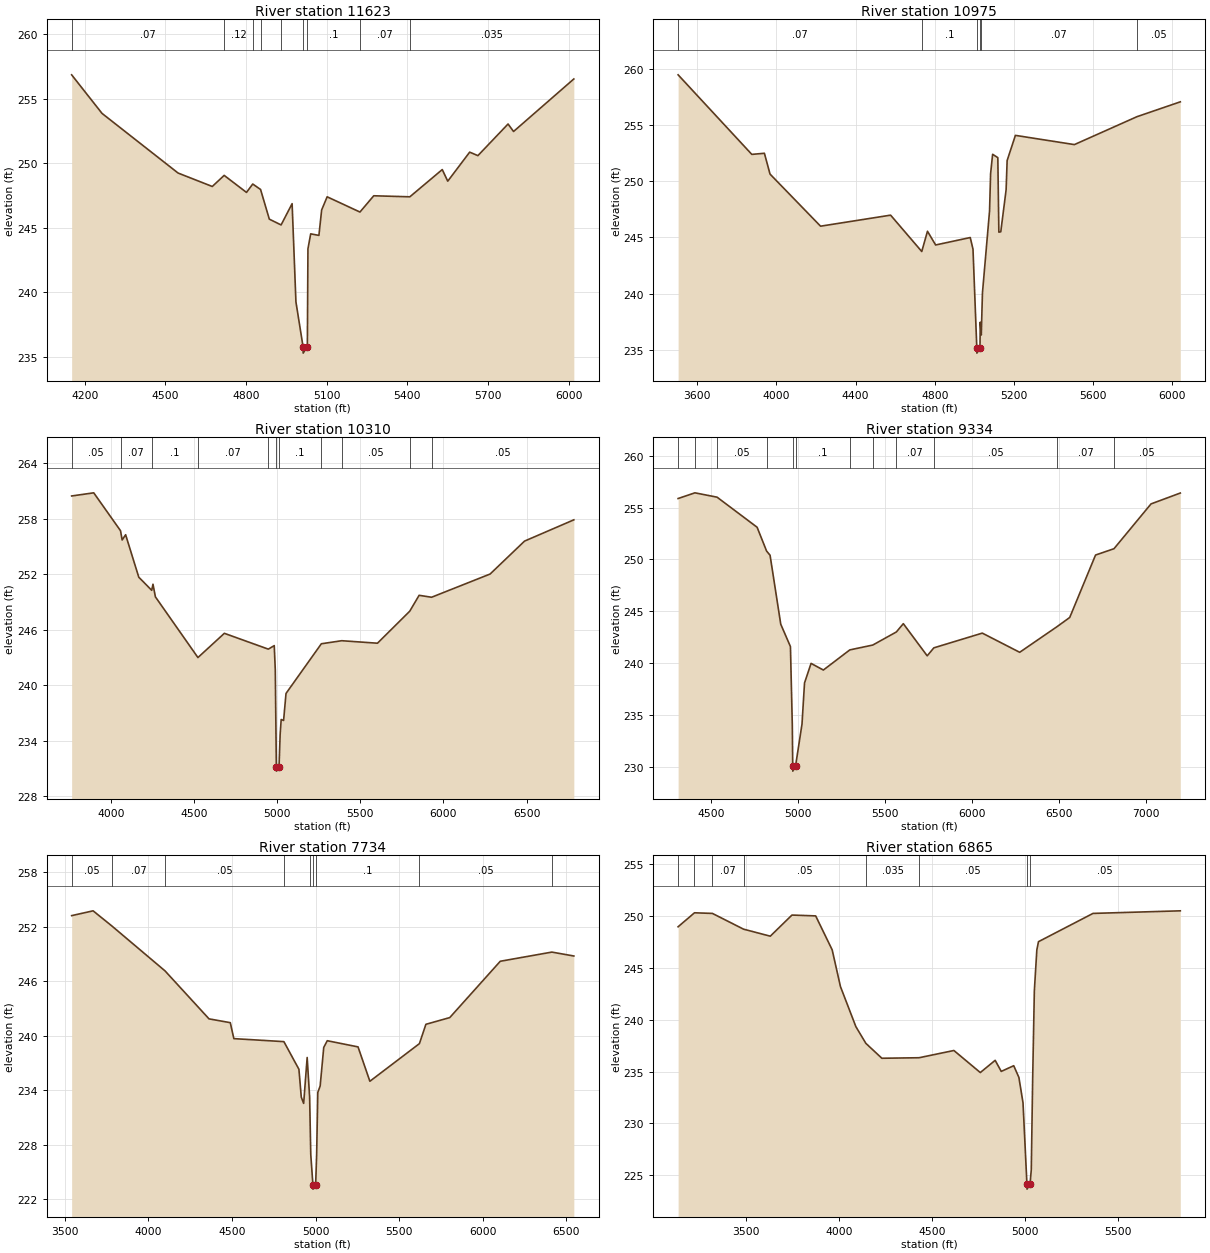
Type RM Length L Ch R = 1 ,11623   ,648,648,648
BEGIN DESCRIPTION:
ROCKY CREEK 3 20.0
END DESCRIPTION:
XS GIS Cut Line= 3
      2513574.98     13694225.02        2512975.       13694825.
        2512775.     13695824.99
#Sta/Elev= 30
  4151.5  256.85  4264.6  253.86  4547.5  249.24  4674.7   248.2  4718.9  249.06
    4802  247.74  4825.2  248.39  4854.3  247.97  4886.9  245.67  4930.7  245.22
  4971.7  246.87  4985.9  239.26  5012.4  235.79  5012.9  235.29  5028.4  235.79
  5030.6  243.37  5040.8  244.53  5071.4  244.41  5081.6  246.38    5102   247.4
  5224.1  246.22  5275.4  247.48  5409.7   247.4  5530.3  249.51  5550.7  248.61
  5632.3  250.86  5662.9  250.59  5775.1  253.04  5795.5  252.46  6019.8  256.53
#Mann= 9 ,-1 , 0
  4151.5     .07       0  4718.9     .12       0  4825.2      .1       0
  4854.3     .12       0  4930.7      .1       0  5012.4     .05       0
  5028.4      .1       0  5224.1     .07       0  5409.7    .035       0
Bank Sta=5012.4,5028.4
XS Rating Curve= 0 ,0
Exp/Cntr=0.3,0.1

Type RM Length L Ch R = 1 ,10975   ,665,665,665
BEGIN DESCRIPTION:
B20239
END DESCRIPTION:
XS GIS Cut Line= 3
      2513348.35     13693873.27      2512588.82     13694741.31
       2512263.3     13696086.77
#Sta/Elev= 30
  3503.3  259.45  3875.7  252.38  3939.3  252.48  3967.8  250.63  4223.1     246
  4577.1  246.98  4734.5  243.75  4763.4  245.55  4804.6  244.33  4979.5  244.99
  4993.4  243.96  5012.6  235.22  5013.1  234.72  5028.7  235.22  5030.1  237.47
    5033  236.82  5035.2  236.33  5041.2  240.07  5077.1  247.36  5082.4  250.67
  5092.6  252.39  5118.9  252.09  5124.1  245.47  5133.8   245.5  5160.8  249.24
  5165.9  251.83  5207.7  254.07  5505.8  253.25    5822  255.73    6041  257.05
#Mann= 6 ,-1 , 0
  3503.3     .07       0  4734.5      .1       0  5012.6     .05       0
  5028.7      .1       0    5033     .07       0    5822     .05       0
Bank Sta=5012.6,5028.7
XS Rating Curve= 0 ,0
Exp/Cntr=0.3,0.1

Type RM Length L Ch R = 1 ,10310   ,976,976,976
BEGIN DESCRIPTION:
B20238
END DESCRIPTION:
XS GIS Cut Line= 3
      2512903.48     13693688.81      2511818.42     13695131.93
      2511069.86     13696086.62
#Sta/Elev= 30
  3764.9  260.47  3897.7  260.81  4058.8  256.71  4068.4  255.71  4089.3  256.28
  4168.4  251.69  4246.2  250.27  4253.8  250.93  4268.4  249.56    4524     243
  4682.8  245.62    4947  243.91  4982.7  244.29    4989  241.66  4995.4  231.22
  4995.9  230.72  5011.6  231.22  5018.1  234.66  5024.4   236.3  5038.9   236.2
  5053.5  239.12  5265.9  244.49  5388.5  244.82  5603.2  244.55  5797.2  248.01
  5853.6  249.73  5928.6  249.52  6280.3  252.03  6487.3  255.59  6783.6  257.89
#Mann= 11 ,-1 , 0
  3764.9     .05       0  4058.8     .07       0  4246.2      .1       0
    4524     .07       0    4947      .1       0  4995.4     .05       0
  5011.6      .1       0  5265.9     .07       0  5388.5     .05       0
  5797.2     .07       0  5928.6     .05       0
Bank Sta=4995.4,5011.6
XS Rating Curve= 0 ,0
Exp/Cntr=0.3,0.1

Type RM Length L Ch R = 1 ,9334    ,1600,1600,1600
BEGIN DESCRIPTION:
B20237
END DESCRIPTION:
XS GIS Cut Line= 4
      2512263.28     13693428.41      2512013.73     13694111.97
       2511536.3      13694589.4      2510842.48     13695901.14
#Sta/Elev= 30
  4310.6  255.87  4407.2  256.42  4534.6     256  4764.7   253.1  4819.3   250.8
  4839.2   250.4  4900.6  243.75  4956.3  241.59    4967  234.03  4969.4  230.08
  4969.9  229.58  4985.8  230.08  5022.8  234.12  5037.2  238.08  5074.9  239.97
  5145.6  239.33  5297.4  241.27  5429.7  241.74  5565.1     243  5605.2   243.8
  5742.4   240.7  5780.7  241.47  6059.2  242.89  6274.1  241.04  6488.6  243.51
  6561.8   244.4  6710.2  250.42  6816.2  251.03    7029  255.35  7197.4   256.4
#Mann= 12 ,-1 , 0
  4310.6     .05       0  4407.2    .035       0  4534.6     .05       0
  4819.3      .1       0  4969.4     .05       0  4985.8      .1       0
  5297.4     .07       0  5429.7      .1       0  5565.1     .07       0
  5780.7     .05       0  6488.6     .07       0  6816.2     .05       0
Bank Sta=4969.4,4985.8
XS Rating Curve= 0 ,0
Exp/Cntr=0.3,0.1

Type RM Length L Ch R = 1 ,7734    ,869,869,869
BEGIN DESCRIPTION:
B20236
END DESCRIPTION:
XS GIS Cut Line= 3
      2511981.17     13693319.88      2510624.84      13694611.1
       2510158.7     13695640.95
#Sta/Elev= 30
  3541.3  253.24  3669.6  253.77  3780.5  252.12  4099.6  247.15  4362.8  241.86
  4489.9  241.44  4511.3  239.68  4810.5  239.35  4900.4   236.3  4914.5  233.23
  4928.7  232.54  4949.7   237.6  4964.4  233.24  4971.2  226.92    4984  223.59
  4984.5  223.09  5000.4  223.59  5006.4  226.91  5013.3  233.75  5027.4  234.46
  5048.8  238.71  5069.9  239.45  5253.9  238.77  5324.7  234.98    5621  239.13
  5659.7  241.26  5802.4     242  6104.5  248.21    6413  249.22  6544.4  248.79
#Mann= 9 ,-1 , 0
  3541.3     .05       0  3780.5     .07       0  4099.6     .05       0
  4810.5     .12       0  4964.4      .1       0    4984     .05       0
  5000.4      .1       0    5621     .05       0    6413     .07       0
Bank Sta=4984,5000.4
XS Rating Curve= 0 ,0
Exp/Cntr=0.3,0.1

Type RM Length L Ch R = 1 ,6865    ,1164,1164,1164
BEGIN DESCRIPTION:
B20235
END DESCRIPTION:
XS GIS Cut Line= 3
       2511937.8      13693222.2      2510147.41     13694144.52
      2509680.86     13694643.62
#Sta/Elev= 30
  3135.4  248.98  3223.3  250.33  3319.6  250.27  3486.7  248.75  3630.4  248.07
  3746.8  250.11  3874.2  250.03  3962.9  246.75  4007.2  243.21  4090.2  239.33
  4143.8  237.72  4229.7  236.28  4429.3  236.33  4616.6  237.03  4758.4   234.9
  4838.3  236.08  4870.9  235.01  4937.9  235.56  4965.7  234.43  4987.8  231.98
  5008.8  224.14  5009.3  223.64  5025.5  224.14  5032.2   225.5  5039.6  234.24
  5048.7   242.8  5062.1  246.75  5070.9  247.54  5363.7  250.27  5832.6  250.52
#Mann= 8 ,-1 , 0
  3135.4     .07       0  3223.3     .05       0  3319.6     .07       0
  3486.7     .05       0  4143.8    .035       0  4429.3     .05       0
  5008.8     .05       0  5025.5     .05       0
Bank Sta=5008.8,5025.5
XS Rating Curve= 0 ,0
Exp/Cntr=0.3,0.1

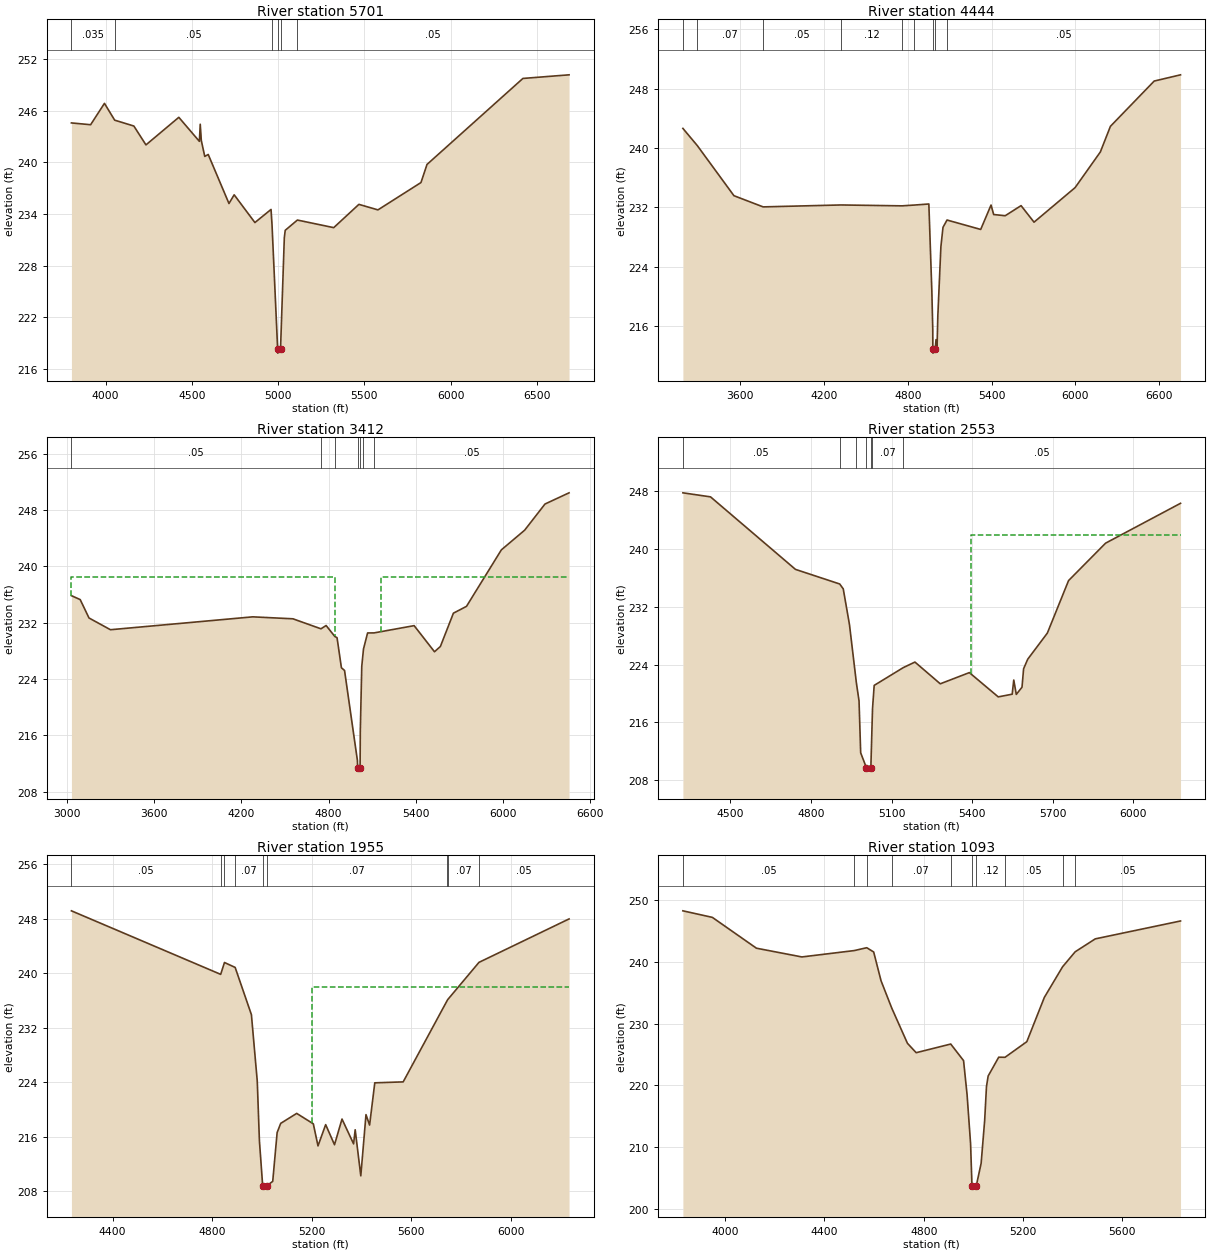
Type RM Length L Ch R = 1 ,5701    ,1257,1257,1257
BEGIN DESCRIPTION:
B20234
END DESCRIPTION:
XS GIS Cut Line= 4
      2511916.05     13693135.41      2510733.35     13693222.21
       2510038.9     13693482.63       2509681.3     13694371.22
#Sta/Elev= 30
    3802  244.57  3913.3  244.36  3993.6  246.84  4052.8  244.89    4164  244.21
  4234.2  242.02  4424.7  245.22  4543.9  242.43  4548.9  244.42  4555.1  242.53
  4575.1  240.68  4595.2  240.91  4715.5  235.22  4745.6  236.23  4865.9  233.01
  4959.4  234.53    4965   232.8  4997.7  218.36  4998.2  217.86  5014.5  218.36
  5036.4  231.24  5041.7  232.11  5112.2   233.3  5322.9  232.42  5468.9  235.12
  5579.3  234.48  5828.7  237.65  5863.7  239.75  6419.8  249.73  6687.4  250.15
#Mann= 6 ,-1 , 0
    3802    .035       0  4052.8     .05       0    4965     .12       0
  4997.7     .05       0  5014.5     .12       0  5112.2     .05       0
Bank Sta=4997.7,5014.5
XS Rating Curve= 0 ,0
Exp/Cntr=0.3,0.1

Type RM Length L Ch R = 1 ,4444    ,1032,1032,1032
BEGIN DESCRIPTION:
B20232
END DESCRIPTION:
XS GIS Cut Line= 4
      2511981.15     13693070.29      2510516.33     13692451.81
       2510060.6     13692723.08       2509702.9     13694121.37
#Sta/Elev= 30
  3189.5  242.64  3292.7  240.32    3555  233.57    3764  232.06  4321.8  232.32
  4759.1   232.2  4841.3   232.3  4950.9  232.45  4972.3  220.69  4978.9  215.52
  4979.5  212.85    4980  212.35  4996.3  212.85  5002.2  214.17  5009.3  212.88
  5015.1  217.35  5037.1  226.69  5052.1   229.3  5080.9  230.29  5322.2  229.02
  5396.3  232.31  5415.1  231.03  5497.7  230.87  5611.2  232.23  5704.1     230
  5998.3  234.66  6178.9  239.46  6251.2  242.92  6564.6  249.02  6753.2  249.86
#Mann= 9 ,-1 , 0
  3189.5    .035       0  3292.7     .07       0    3764     .05       0
  4321.8     .12       0  4759.1     .07       0  4841.3     .12       0
  4979.5     .05       0  4996.3     .12       0  5080.9     .05       0
Bank Sta=4979.5,4996.3
XS Rating Curve= 0 ,0
Exp/Cntr=0.3,0.1

Type RM Length L Ch R = 1 ,3412    ,859,859,859
BEGIN DESCRIPTION:
B20233
END DESCRIPTION:
XS GIS Cut Line= 4
      2510396.98     13690726.54      2509626.58      13692299.9
      2509648.28     13693081.15      2509659.12     13693970.48
#Sta/Elev= 30
  3031.8  235.83  3092.2  235.27  3152.6  232.66  3300.3  230.99  4279.2  232.82
  4555.5  232.54  4748.2  231.12  4783.7  231.59  4843.5  230.03  4858.8  229.86
  4888.8  225.59  4910.4   225.2  4998.8  212.43  5000.4   211.4  5000.9   210.9
  5017.3   211.4  5018.8  216.61  5028.8  225.78  5040.7  228.25  5068.9  230.53
  5114.1  230.54    5389  231.57    5529  227.86  5569.6  228.61  5659.1  233.34
  5749.1  234.31  5989.1  242.34  6149.1  245.13  6289.1  248.85  6454.6  250.44
#Mann= 7 ,-1 , 0
  3031.8     .05       0  4748.2     .12       0  4843.5      .1       0
  5000.4     .05       0  5017.3      .1       0  5040.7     .12       0
  5114.1     .05       0
#XS Ineff= 2 , 0
       0  4841.7  238.49  5158.3       0  238.49
Permanent Ineff=
       F       F
Bank Sta=5000.4,5017.3
XS Rating Curve= 0 ,0
Exp/Cntr=0.3,0.1

Type RM Length L Ch R = 1 ,2553    ,598,598,598
BEGIN DESCRIPTION:
B20231
END DESCRIPTION:
XS GIS Cut Line= 3
       2508351.9     13692353.12      2509042.11     13692853.71
      2509572.04      13693701.6
#Sta/Elev= 30
  4323.1  247.79    4426  247.23  4742.2  237.19  4906.8  235.17    4920   234.5
  4943.2  229.55    4969  221.46  4978.8  218.98  4984.9   211.8  5005.9  209.76
  5006.4  209.26  5022.8  209.76    5026  213.96    5029   217.9  5035.2  221.13
  5143.5  223.59  5186.9  224.36  5281.2  221.35  5389.5   222.9    5497  219.54
  5548.9  219.91  5554.8  221.87  5564.2  219.88  5585.5  220.88  5591.4  223.43
  5606.7  224.75  5679.8  228.37  5758.8  235.64  5896.6  240.82  6175.6  246.34
#Mann= 7 ,-1 , 0
  4323.1     .05       0  4906.8     .07       0    4969      .1       0
  5005.9     .05       0  5022.8      .1       0    5026     .07       0
  5143.5     .05       0
#XS Ineff= 2 , 0
       0                  5394.9       0  242.01
Permanent Ineff=
       F       F
Bank Sta=5005.9,5022.8
XS Rating Curve= 0 ,0
Exp/Cntr=0.3,0.1

Type RM Length L Ch R = 1 ,1955    ,862,862,862
BEGIN DESCRIPTION:
B20230
END DESCRIPTION:
XS GIS Cut Line= 4
       2508131.9     13692626.14      2508503.58     13693141.94
      2508943.51     13693308.81      2509489.64     13694014.23
#Sta/Elev= 30
  4234.9  249.17  4834.3  239.84  4849.5  241.58  4892.4  240.86  4957.7  233.92
  4981.2  224.15  4989.8  215.43  5002.9   208.8  5003.4   208.3  5019.8   208.8
  5043.3  209.44    5061  216.61  5075.4  217.96  5139.6  219.42  5206.3  217.89
  5225.1  214.65  5255.9  217.77  5291.4  214.82  5321.5  218.59    5368  214.95
  5374.4  217.02    5397  210.25  5417.8  219.24  5432.3  217.71  5453.1  223.91
  5567.2  224.05  5744.2  236.02  5746.7  236.16  5871.5   241.6  6233.3  247.98
#Mann= 9 ,-1 , 0
  4234.9     .05       0  4834.3     .07       0  4849.5     .05       0
  4892.4     .07       0  5002.9     .05       0  5019.8     .07       0
  5744.2    .035       0  5746.7     .07       0  5871.5     .05       0
#XS Ineff= 2 , 0
       0                    5200       0     238
Permanent Ineff=
       F       F
Bank Sta=5002.9,5019.8
XS Rating Curve= 0 ,0
Exp/Cntr=0.3,0.1

Type RM Length L Ch R = 1 ,1093    ,438,438,438
BEGIN DESCRIPTION:
B20229
END DESCRIPTION:
XS GIS Cut Line= 3
      2508124.35     13692770.32      2508427.73     13693498.43
      2509261.01     13694384.74
#Sta/Elev= 30
  3829.5  248.21  3948.3  247.15  4125.9  242.17    4309  240.76  4520.3  241.79
  4570.4  242.25  4598.3  241.56  4627.9  236.92  4670.9  232.52  4734.3  226.81
  4769.5  225.29  4908.8  226.69  4960.5  224.01  4974.6  218.54  4988.8  210.57
  4994.4  203.75  4994.9  203.25  5011.5  203.75  5031.3  207.42  5045.5  214.32
  5052.8  219.81  5059.6  221.52  5102.1  224.56  5127.7  224.55  5215.4  227.07
  5286.1  234.23  5359.5  239.17  5410.2  241.59  5491.3  243.68  5834.8  246.57
#Mann= 10 ,-1 , 0
  3829.5     .05       0  4520.3     .07       0  4570.4     .12       0
  4670.9     .07       0  4908.8     .12       0  4994.4     .05       0
  5011.5     .12       0  5127.7     .05       0  5359.5    .035       0
  5410.2     .05       0
Bank Sta=4994.4,5011.5
XS Rating Curve= 0 ,0
Exp/Cntr=0.3,0.1

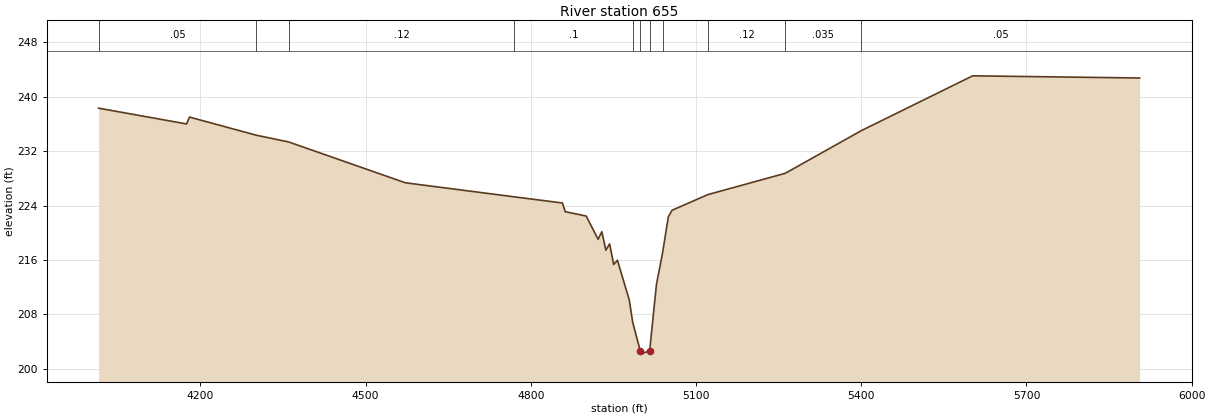
Type RM Length L Ch R = 1 ,655     ,0,0,0
BEGIN DESCRIPTION:
B20228
END DESCRIPTION:
XS GIS Cut Line= 4
      2508200.19     13693225.38      2508412.56     13694052.13
      2508693.21     13694355.53        2509261.     13694612.93
#Sta/Elev= 30
  4015.2   238.3    4175  235.98  4180.2  236.99  4301.9  234.32  4360.2  233.34
  4572.2  227.34  4770.3  225.27  4857.4  224.37  4862.5   223.1  4900.6  222.45
  4922.2  219.04    4929  220.15  4936.3  217.44  4943.1  218.36  4950.5  215.34
  4957.3  215.96  4978.9   210.1    4985  206.86  4998.7  202.67  4999.2  202.17
  5015.8  202.67  5028.2  212.42  5039.2  217.01  5049.7  222.33  5056.5   223.3
  5121.4   225.6    5262  228.73  5400.2     235  5602.4  243.05  5905.5  242.73
#Mann= 11 ,-1 , 0
  4015.2     .05       0  4301.9     .07       0  4360.2     .12       0
  4770.3      .1       0    4985     .12       0  4998.7     .05       0
  5015.8     .12       0  5039.2      .1       0  5121.4     .12       0
    5262    .035       0  5400.2     .05       0
Bank Sta=4998.7,5015.8
XS Rating Curve= 0 ,0
Exp/Cntr=0.3,0.1

Chan Stop Cuts=-1
Use User Specified Reach Order=0
Composite Channel Slope=5