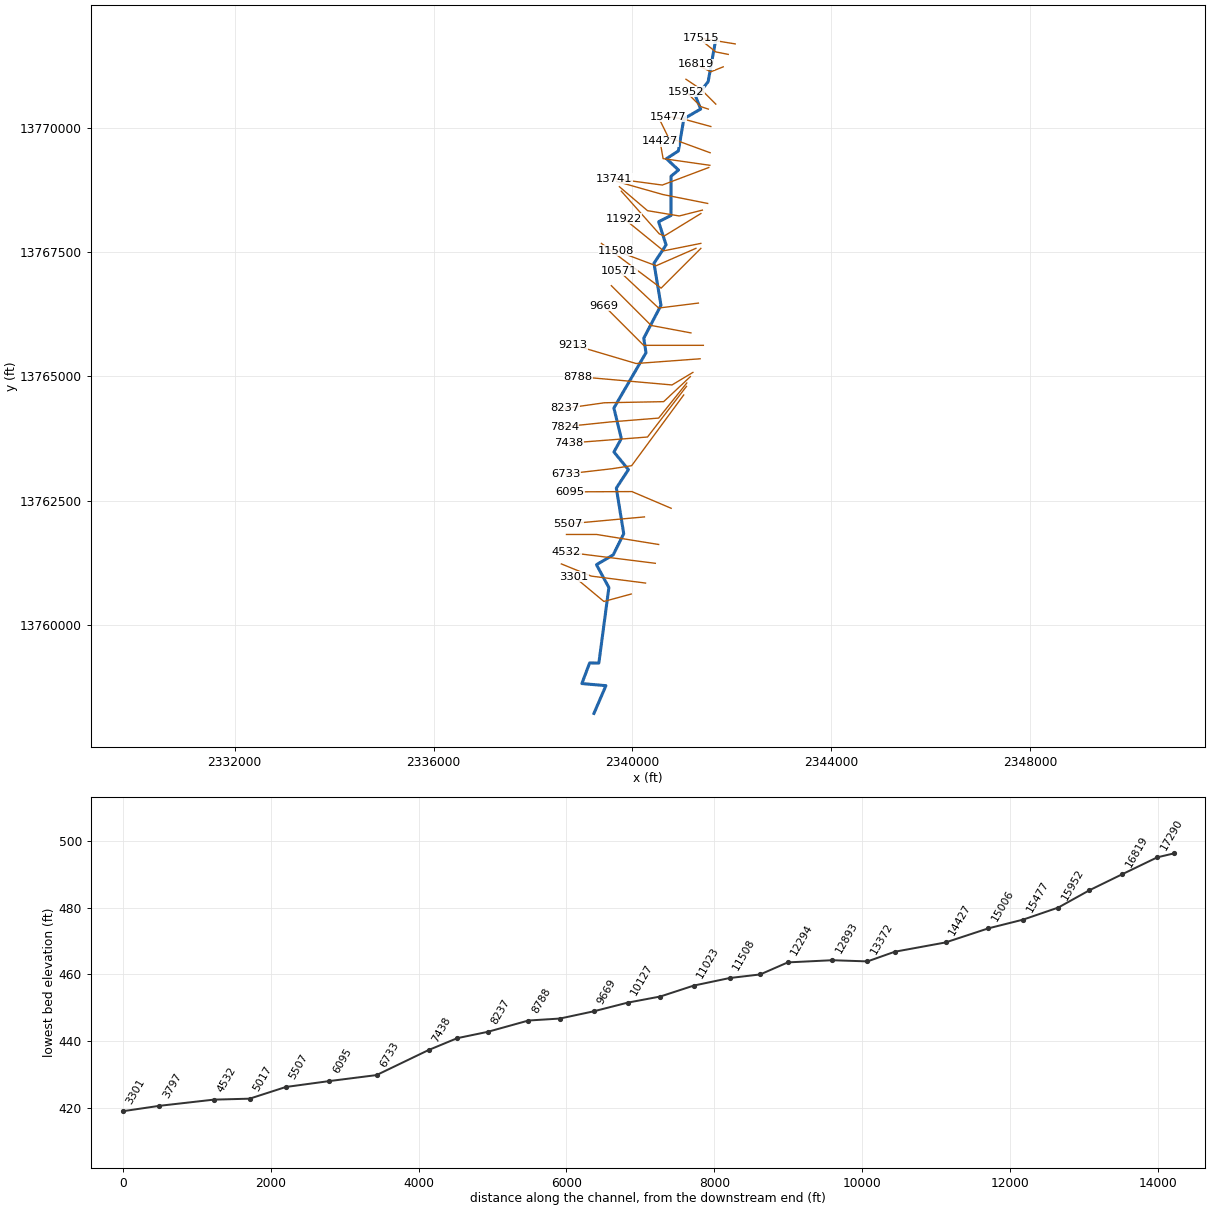
--- RUDOLPH CREEK.prj (project) ---

Proj Title=RUDOLPH CREEK Base Level Engineering
Current Plan=p01
Default Exp/Contr=0.3,0.1
English Units
Geom File=g01
Flow File=f01
Plan File=p01
Y Axis Title=Elevation
X Axis Title(PF)=Main Channel Distance
X Axis Title(XS)=Station
BEGIN DESCRIPTION:
RUDOLPH CREEK
END DESCRIPTION:
DSS Export Rating Curves= 0
DSS Export Rating Curve Sorted= 0
DSS Export Volume Flow Curves= 0
DXF OffsetX= 0
DXF OffsetY= 0
DXF ScaleX= 1
DXF ScaleY= 10

--- RUDOLPH CREEK.p01 (plan) ---

Plan Title=Multiple Run
Short Identifier=Multiple
Geom File=g01
Flow File=f01
Subcritical Flow
K Sum by GR= 0
Std Step Tol= 0.01
Critical Tol= 0.01
Num of Std Step Trials= 20
Max Error Tol= 0.3
Flow Tol Ratio= 0.001
Split Flow NTrial= 30
Split Flow Tol= 0.02
Split Flow Ratio= 0.02
Log Output Level= 0
Friction Slope Method= 1
Unsteady Friction Slope Method= 2
Unsteady Bridges Friction Slope Method= 1
Parabolic Critical Depth
Global Vel Dist=  1 , 1 , 1
Global Log Level= 0
CheckData=True
Encroach Param= -1, 0, 0, 0
BEGIN DESCRIPTION:
Multiple Run
END DESCRIPTION:

--- RUDOLPH CREEK.f01 (steady flow) ---

Flow Title=Multiple
Number of Profiles=7
Profile Names=10-year,25-year,50-year,1pct_min,100-year,1pct_plu,500-year
River Rch & RM= RUDOLPH CREEK,Reach-1,17515
     684    1120    1519     999    1994    3979    3402
River Rch & RM= RUDOLPH CREEK,Reach-1,13741
    1361    2300    3186    2133    4256    8493    7533
River Rch & RM= RUDOLPH CREEK,Reach-1,8237
    1402    2366    3274    2188    4366    8711    7701
River Rch & RM= RUDOLPH CREEK,Reach-1,6095
    2228    3839    5388    3647    7278   14521   13173
Boundary for River Rch & Prof#=RUDOLPH CREEK,Reach-1,1
Up Type=0
Dn Type=3
Dn Slope=0.005
Boundary for River Rch & Prof#=RUDOLPH CREEK,Reach-1,2
Up Type=0
Dn Type=3
Dn Slope=0.005
Boundary for River Rch & Prof#=RUDOLPH CREEK,Reach-1,3
Up Type=0
Dn Type=3
Dn Slope=0.005
Boundary for River Rch & Prof#=RUDOLPH CREEK,Reach-1,4
Up Type=0
Dn Type=3
Dn Slope=0.005
Boundary for River Rch & Prof#=RUDOLPH CREEK,Reach-1,5
Up Type=0
Dn Type=3
Dn Slope=0.005
Boundary for River Rch & Prof#=RUDOLPH CREEK,Reach-1,6
Up Type=0
Dn Type=3
Dn Slope=0.005
Boundary for River Rch & Prof#=RUDOLPH CREEK,Reach-1,7
Up Type=0
Dn Type=3
Dn Slope=0.005

--- RUDOLPH CREEK.g01 (geometry) ---

Geom Title=Existing Conditions
Program Version=4.10

River Reach=RUDOLPH CREEK   ,Reach-1
Reach XY= 30
        2341675.       13771775.      2341521.19     13770926.56
       2341275.7      13770614.3      2341371.64     13770376.25
      2341033.14     13770181.06      2340922.16     13769533.01
      2340682.51     13769378.15      2340925.55     13769149.89
        2340775.       13769025.      2340774.01     13768236.69
      2340524.95     13768109.67       2340675.6     13767645.05
      2340432.23     13767275.31      2340572.95     13766430.86
      2340227.05     13765769.14      2340271.54     13765476.49
       2339626.2      13764364.5       2339775.5     13763749.96
      2339626.96     13763480.89      2339917.93       13763125.
      2339675.07     13762754.97      2339823.81     13761837.02
      2339611.88     13761411.76      2339275.48     13761214.53
      2339525.36     13760754.85       2339323.4     13759236.17
      2339138.23     13759238.81      2338982.21     13758824.65
      2339466.03     13758782.06        2339225.       13758225.

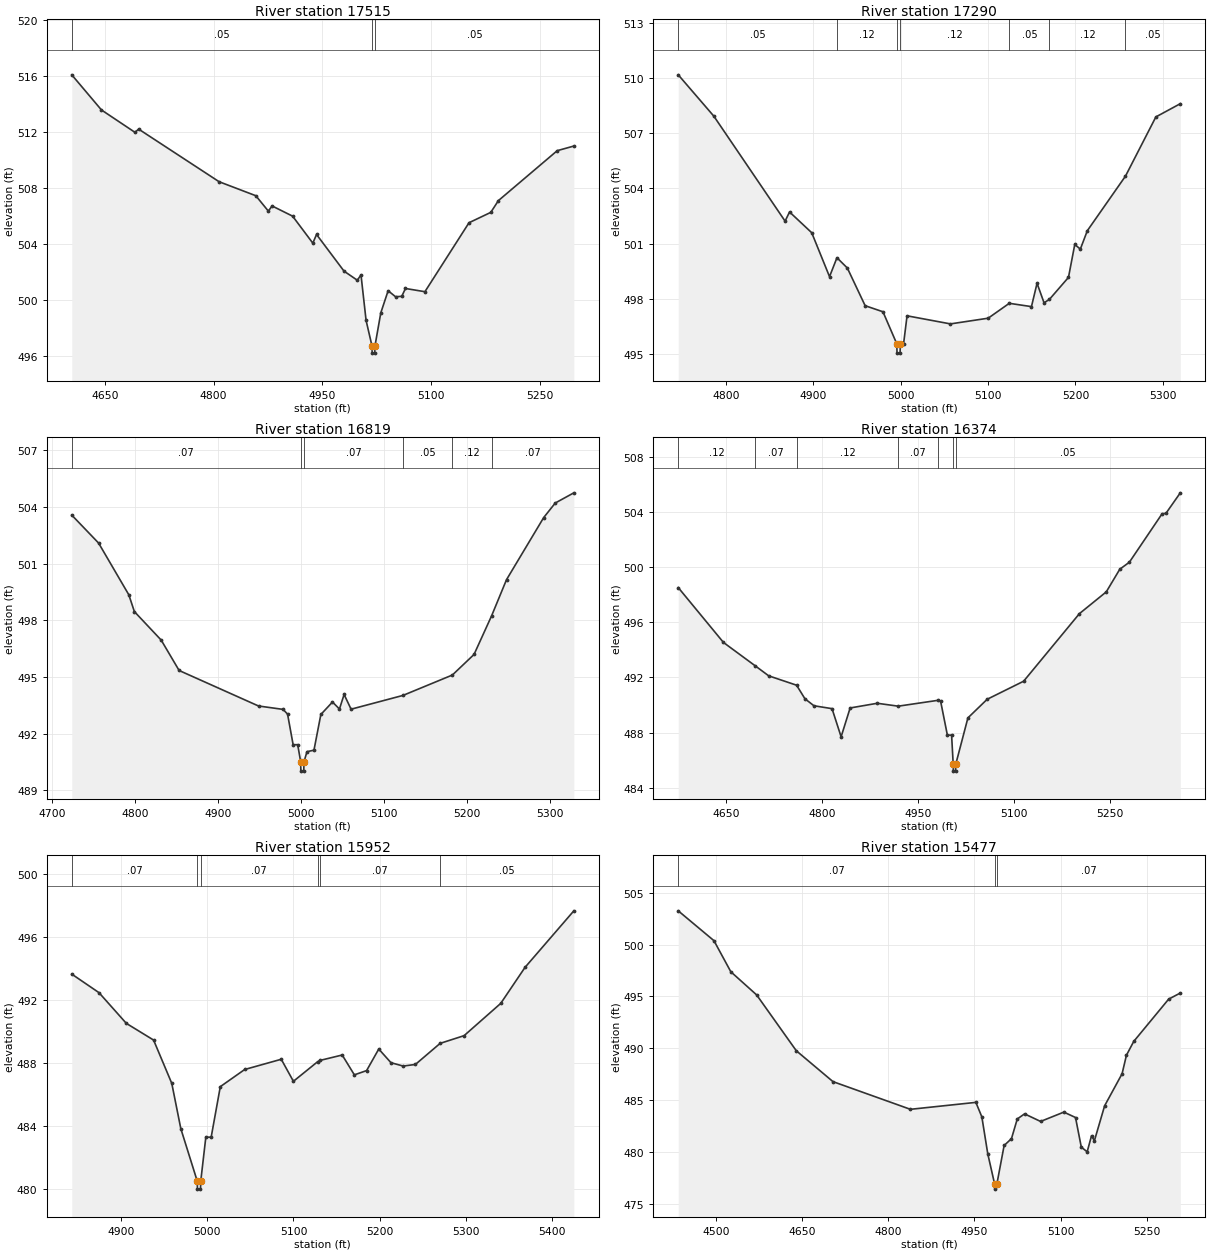
Type RM Length L Ch R = 1 ,17515   ,225,225,225
BEGIN DESCRIPTION:
B20322
END DESCRIPTION:
XS GIS Cut Line= 2
      2342065.39     13771685.82      2341382.41     13771797.78
#Sta/Elev= 30
  4604.4  516.11  4645.3   513.6  4691.5     512  4696.6  512.23  4807.5  508.47
  4858.1  507.47  4875.4  506.37  4880.5  506.74  4908.8  506.01  4936.7  504.08
  4941.8   504.7  4979.7  502.08    4998  501.43  5003.1  501.81  5010.1  498.56
  5018.3  496.72  5018.5  496.22    5022  496.22  5022.3  496.72  5030.4   499.1
  5040.5  500.68  5050.7  500.25  5059.3  500.28  5064.4  500.84  5091.2  500.61
    5152  505.54    5182  506.28  5192.5  507.12  5273.6  510.69  5296.5  511.02
#Mann= 3 ,-1 , 0
  4604.4     .05       0  5018.3     .05       0  5022.3     .05       0
Bank Sta=5018.3,5022.3
XS Rating Curve= 0 ,0
Exp/Cntr=0.3,0.1

Type RM Length L Ch R = 1 ,17290   ,471,471,471
BEGIN DESCRIPTION:
RUDOLPH CREEK 25.0
END DESCRIPTION:
XS GIS Cut Line= 3
      2341924.98       13771475.        2341675.       13771525.
      2341424.99     13771725.01
#Sta/Elev= 30
  4745.1  510.18  4785.9  507.93  4867.5  502.22  4872.6  502.72    4898  501.59
  4918.4   499.2  4926.9  500.23  4938.8  499.67  4959.2  497.62  4979.6  497.29
  4995.5  495.54  4995.7  495.04  4999.2  495.04  4999.5  495.54  5003.2  495.54
  5007.2  497.07  5056.9  496.63  5100.1  496.94  5124.3  497.75  5149.7  497.57
  5156.1  498.84  5164.1  497.78  5170.2  497.96  5192.1  499.16  5199.3  500.95
  5205.7   500.7  5213.7   501.7  5257.4  504.67  5292.2  507.89  5320.2  508.61
#Mann= 7 ,-1 , 0
  4745.1     .05       0  4926.9     .12       0  4995.5     .05       0
  4999.5     .12       0  5124.3     .05       0  5170.2     .12       0
  5257.4     .05       0
Bank Sta=4995.5,4999.5
XS Rating Curve= 0 ,0
Exp/Cntr=0.3,0.1

Type RM Length L Ch R = 1 ,16819   ,445,445,445
BEGIN DESCRIPTION:
RUDOLPH CREEK 24.0
END DESCRIPTION:
XS GIS Cut Line= 3
      2341825.03     13771225.01        2341575.       13771125.
        2341275.       13771275.
#Sta/Elev= 30
  4724.1  503.57  4756.4  502.09  4792.8  499.35  4799.5  498.46  4831.8  496.95
  4853.4  495.34    4949  493.46  4978.6  493.28    4984  493.03  4990.7  491.41
  4996.2  491.41  4999.8  490.51    5000  490.01  5003.5  490.01  5003.8  490.51
  5007.4  491.04  5015.8  491.12  5024.1  493.01  5038.1  493.67  5046.5   493.3
  5052.1  494.07  5060.5  493.29    5123  494.02  5182.5   495.1  5208.6  496.19
  5229.7  498.23  5247.7  500.15  5292.5  503.44  5306.4  504.21  5328.8  504.75
#Mann= 6 ,-1 , 0
  4724.1     .07       0  4999.8     .05       0  5003.8     .07       0
    5123     .05       0  5182.5     .12       0  5229.7     .07       0
Bank Sta=4999.8,5003.8
XS Rating Curve= 0 ,0
Exp/Cntr=0.3,0.1

Type RM Length L Ch R = 1 ,16374   ,422,422,422
BEGIN DESCRIPTION:
RUDOLPH CREEK 23.0
END DESCRIPTION:
XS GIS Cut Line= 3
        2341675.       13770475.        2341375.       13770775.
      2341075.02     13770974.99
#Sta/Elev= 30
  4575.3  498.51    4646  494.53  4695.8  492.83  4716.7  492.11  4760.3  491.43
  4773.3  490.45  4787.4  489.94  4815.7  489.73  4829.9  487.69    4844  489.78
  4886.4  490.12  4919.2  489.91  4980.7  490.33  4985.4  490.28    4996  487.81
  5002.6  487.81  5005.1   485.7  5005.3   485.2  5008.8   485.2  5009.1   485.7
  5028.1  489.06  5058.2  490.41  5115.2  491.72  5202.4  496.62  5244.4   498.2
  5265.5  499.84  5280.5  500.35  5331.6  503.86  5337.6  503.89  5360.1  505.38
#Mann= 7 ,-1 , 0
  4575.3     .12       0  4695.8     .07       0  4760.3     .12       0
  4919.2     .07       0  4980.7     .05       0  5005.1     .05       0
  5009.1     .05       0
Bank Sta=5005.1,5009.1
XS Rating Curve= 0 ,0
Exp/Cntr=0.3,0.1

Type RM Length L Ch R = 1 ,15952   ,475,475,475
BEGIN DESCRIPTION:
RUDOLPH CREEK 22.0
END DESCRIPTION:
XS GIS Cut Line= 3
      2341525.02     13770374.99        2341375.       13770425.
        2341075.       13770725.
#Sta/Elev= 30
  4842.8  493.67  4874.4  492.49  4906.1  490.54  4937.7  489.48  4958.8  486.73
  4969.3  483.85  4988.4  480.51  4988.6  480.01  4992.1  480.01  4992.4  480.51
  4998.3  483.31  5004.5  483.31  5015.1  486.52  5043.4  487.61  5085.8  488.26
  5099.9  486.86  5127.9   488.1    5131  488.19  5156.5  488.53  5170.6  487.27
  5184.8  487.54  5198.9  488.91  5213.1  488.04  5227.2  487.83  5241.4  487.93
  5270.1  489.27  5297.9  489.76  5340.4  491.81  5368.6   494.1  5425.2  497.69
#Mann= 6 ,-1 , 0
  4842.8     .07       0  4988.4     .05       0  4992.4     .07       0
  5127.9     .12       0    5131     .07       0  5270.1     .05       0
Bank Sta=4988.4,4992.4
XS Rating Curve= 0 ,0
Exp/Cntr=0.3,0.1

Type RM Length L Ch R = 1 ,15477   ,471,471,471
BEGIN DESCRIPTION:
RUDOLPH CREEK 21.0
END DESCRIPTION:
XS GIS Cut Line= 3
      2341575.05     13770024.99        2341025.       13770175.
      2340724.97       13770225.
#Sta/Elev= 30
  4434.2  503.25  4496.4  500.37  4525.8  497.37  4570.7  495.14  4639.8  489.75
  4703.7  486.77  4838.5   484.1  4952.5  484.77  4962.9  483.37  4973.2  479.81
  4985.1   476.9  4985.3   476.4  4989.1   476.9  5001.7  480.61  5014.5  481.27
  5024.6  483.17  5037.3  483.66  5065.2  482.93  5105.7  483.83    5126  483.31
  5136.1  480.45  5146.3     480  5153.9  481.55  5158.9  481.07  5176.7  484.44
  5207.1  487.53  5214.7  489.32  5227.4  490.65  5288.2  494.73  5308.5  495.32
#Mann= 3 ,-1 , 0
  4434.2     .07       0  4985.1     .05       0  4989.1     .07       0
Bank Sta=4985.1,4989.1
XS Rating Curve= 0 ,0
Exp/Cntr=0.3,0.1

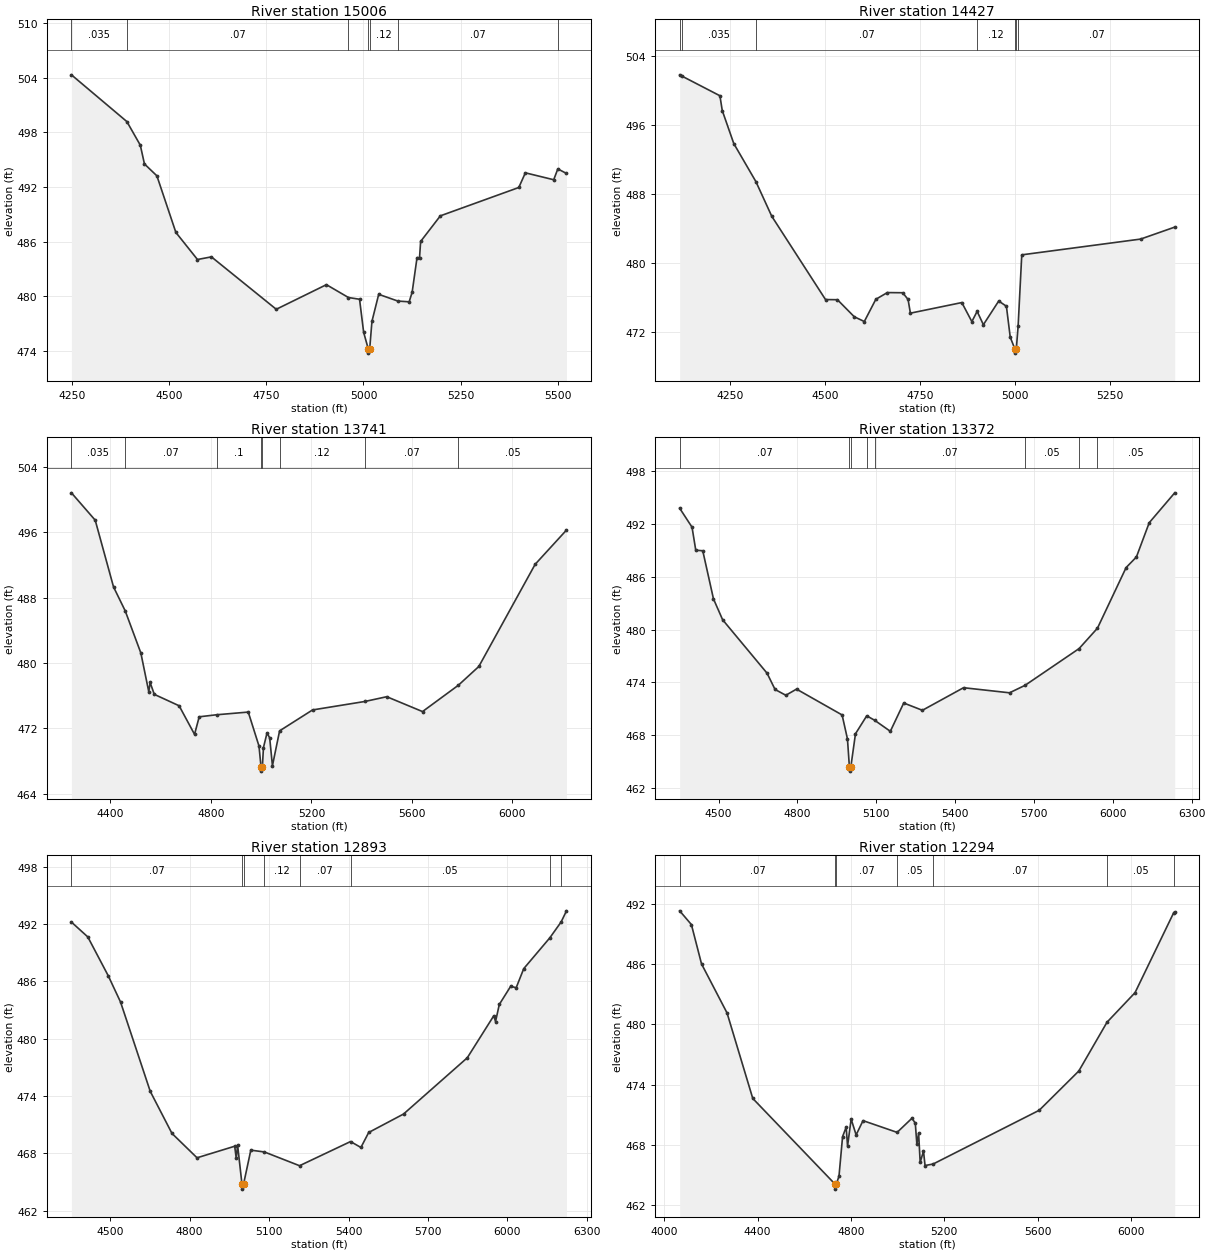
Type RM Length L Ch R = 1 ,15006   ,579,579,579
BEGIN DESCRIPTION:
B20321
END DESCRIPTION:
XS GIS Cut Line= 3
       2341561.6     13769497.07      2340721.91     13769804.96
      2340553.97     13770146.44
#Sta/Elev= 30
  4247.9  504.31  4390.7  499.18  4425.3  496.59    4436  494.53    4468  493.23
  4516.9  487.02  4572.5  484.05  4608.4  484.34  4775.4  478.59  4904.6  481.29
  4961.3  479.88  4989.9  479.69  5000.5  476.05  5012.1  474.28  5012.3  473.78
  5016.1  474.28  5021.8  477.26  5039.2  480.23  5088.7  479.49  5117.7  479.41
  5125.4  480.47  5137.9  484.25  5144.4  484.25  5147.2  486.03    5198  488.84
    5400  491.95  5416.9  493.56  5489.9   492.8  5500.5  493.99  5522.8  493.49
#Mann= 7 ,-1 , 0
  4247.9    .035       0  4390.7     .07       0  4961.3     .12       0
  5012.1     .05       0  5016.1     .12       0  5088.7     .07       0
  5500.5     .05       0
Bank Sta=5012.1,5016.1
XS Rating Curve= 0 ,0
Exp/Cntr=0.3,0.1

Type RM Length L Ch R = 1 ,14427   ,686,686,686
BEGIN DESCRIPTION:
B20320
END DESCRIPTION:
XS GIS Cut Line= 3
      2341555.94     13769245.18      2340615.55     13769379.52
      2340553.98     13769726.56
#Sta/Elev= 30
  4118.3  501.87  4125.7  501.69  4224.2  499.44  4230.4  497.72  4260.7  493.89
  4318.9  489.47  4360.6  485.45    4502  475.78  4533.4  475.76  4577.7  473.78
  4604.1  473.23  4634.4  475.81  4664.7  476.59  4705.1  476.57  4719.2  475.79
  4725.3   474.2  4860.6  475.43    4887  473.22  4900.9  474.41  4917.3  472.86
  4957.7  475.61  4977.9     475    4988  471.41    5000  470.06  5000.3  469.56
    5004  470.06  5008.7  472.68  5018.3  480.97  5330.9   482.8  5420.7  484.19
#Mann= 7 ,-1 , 0
  4118.3     .07       0  4125.7    .035       0  4318.9     .07       0
  4900.9     .12       0    5000     .05       0    5004     .12       0
  5008.7     .07       0
Bank Sta=5000,5004
XS Rating Curve= 0 ,0
Exp/Cntr=0.3,0.1

Type RM Length L Ch R = 1 ,13741   ,369,369,369
BEGIN DESCRIPTION:
B20319
END DESCRIPTION:
XS GIS Cut Line= 3
      2341533.59     13769200.39      2340598.75     13768847.73
      2339635.96     13768976.48
#Sta/Elev= 30
  4244.9  500.85  4339.6   497.5  4412.5  489.33    4459   486.4  4521.3  481.24
  4552.8   476.5  4558.2  477.63  4574.7  476.18  4673.6  474.78    4735  471.28
  4753.5  473.43  4822.7  473.68  4948.8  474.01  4991.5  469.85  4999.6  467.28
    5000  466.78  5004.9  467.28  5009.3  469.67  5023.6  471.47  5034.1  470.84
    5045  467.44  5073.5  471.71  5204.6  474.27  5413.4  475.31  5500.1  475.89
  5642.4  474.07  5784.9  477.29  5866.5  479.59  6090.7   492.1  6215.4  496.29
#Mann= 8 ,-1 , 0
  4244.9    .035       0    4459     .07       0  4822.7      .1       0
  4999.6     .05       0  5004.9      .1       0  5073.5     .12       0
  5413.4     .07       0  5784.9     .05       0
Bank Sta=4999.6,5004.9
XS Rating Curve= 0 ,0
Exp/Cntr=0.3,0.1

Type RM Length L Ch R = 1 ,13372   ,479,479,479
BEGIN DESCRIPTION:
B20318
END DESCRIPTION:
XS GIS Cut Line= 3
       2341511.2     13768478.28      2340609.95     13768657.41
      2339681.62     13768920.25
#Sta/Elev= 30
  4351.9   493.8    4399  491.64  4413.2  489.02  4439.8  488.96  4480.6  483.48
  4515.4  481.11  4684.5  475.03  4714.9  473.18  4755.9  472.52  4796.6  473.22
    4970  470.28  4990.4  467.55  4997.7  464.39  4998.2  463.89  5003.3  464.39
  5020.9  468.14  5063.7  470.18  5093.6  469.68  5153.5  468.42  5204.5  471.64
  5275.5  470.81  5432.1  473.38    5607   472.8  5666.1  473.65  5871.7  477.83
  5941.6  480.15  6050.7  487.05  6089.8  488.25  6138.6  492.15  6235.6  495.55
#Mann= 8 ,-1 , 0
  4351.9     .07       0  4997.7     .05       0  5003.3     .07       0
  5063.7     .12       0  5093.6     .07       0  5666.1     .05       0
  5871.7     .07       0  5941.6     .05       0
Bank Sta=4997.7,5003.3
XS Rating Curve= 0 ,0
Exp/Cntr=0.3,0.1

Type RM Length L Ch R = 1 ,12893   ,599,599,599
BEGIN DESCRIPTION:
B20317
END DESCRIPTION:
XS GIS Cut Line= 4
      2341404.84     13768343.93      2340940.22     13768226.38
      2340302.07     13768332.74      2339736.68     13768814.16
#Sta/Elev= 30
  4353.9  492.19  4415.7  490.64  4492.6  486.59  4539.4  483.82  4651.5  474.47
  4733.5  470.07  4828.1  467.52  4970.2  468.73  4976.1  467.46  4981.2  468.85
  4997.8  464.74  4998.3  464.24  5003.5  464.74  5031.1  468.32  5082.4  468.13
  5215.1  466.69  5407.6  469.22  5446.7   468.6  5476.1  470.17  5607.6   472.1
  5848.3  477.99  5948.3  482.39  5954.9  481.78  5969.1  483.57    6012  485.47
  6032.8  485.32  6061.4  487.32    6160  490.55  6202.6  492.21  6222.7  493.37
#Mann= 8 ,-1 , 0
  4353.9     .07       0  4997.8     .05       0  5003.5     .07       0
  5082.4     .12       0  5215.1     .07       0  5407.6     .05       0
    6160    .045       0  6202.6     .05       0
Bank Sta=4997.8,5003.5
XS Rating Curve= 0 ,0
Exp/Cntr=0.3,0.1

Type RM Length L Ch R = 1 ,12294   ,372,372,372
BEGIN DESCRIPTION:
RUDOLPH CREEK 16.0
END DESCRIPTION:
XS GIS Cut Line= 4
        2341375.       13768275.      2340637.94     13767823.34
      2340537.18     13767868.12      2339775.01     13768724.99
#Sta/Elev= 30
  4066.4   491.3  4116.7  489.93  4160.2  486.01  4269.5  481.13  4379.7  472.62
  4732.1  464.09  4732.5  463.59  4737.8  464.09  4749.2  464.88  4764.6  468.82
    4780  469.76  4785.9  467.88  4801.3  470.56  4822.6  468.99  4852.2  470.41
  4998.3  469.24    5062  470.65  5076.2  470.15  5082.9  468.06  5090.4  469.15
  5097.1  466.26  5111.3  467.37    5118  465.94  5152.6  466.09  5607.2  471.44
  5776.9  475.35  5897.8  480.21  6017.8  483.15  6183.9  491.13  6187.9  491.16
#Mann= 7 ,-1 , 0
  4066.4     .07       0  4732.1     .05       0  4737.8     .07       0
  4998.3     .05       0  5152.6     .07       0  5897.8     .05       0
  6183.9    .045       0
Bank Sta=4732.1,4737.8
XS Rating Curve= 0 ,0
Exp/Cntr=0.3,0.1

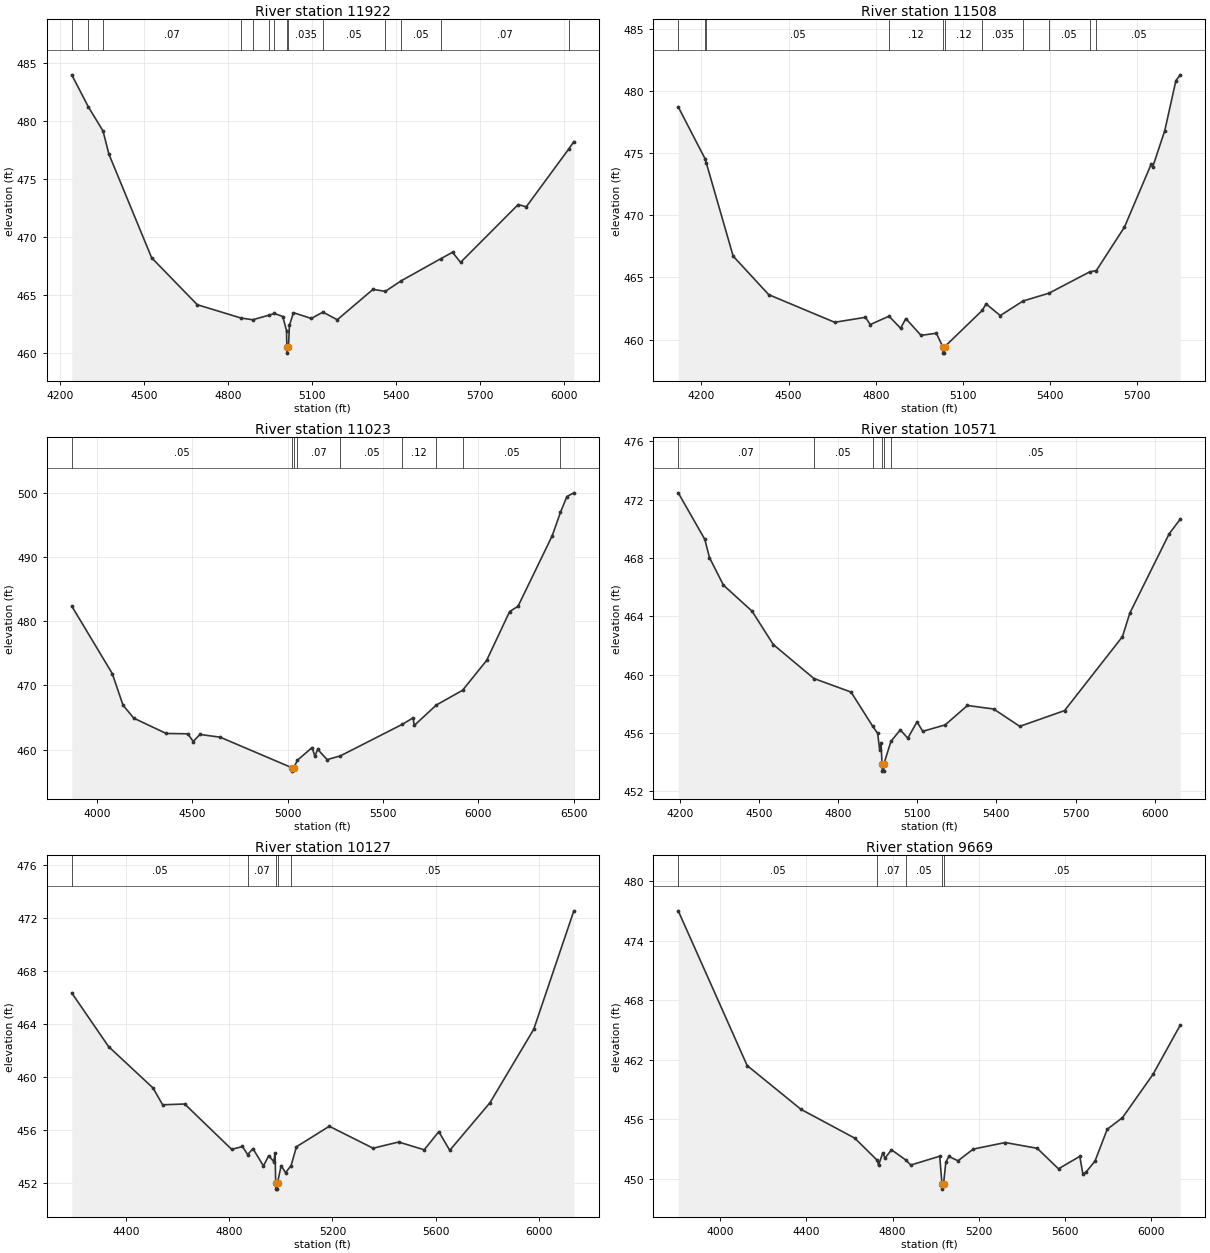
Type RM Length L Ch R = 1 ,11922   ,414,414,414
BEGIN DESCRIPTION:
RUDOLPH CREEK 15.0
END DESCRIPTION:
XS GIS Cut Line= 3
      2341375.03     13767675.01        2340625.       13767525.
      2339824.97     13768175.03
#Sta/Elev= 30
  4240.4     484  4299.3  481.25  4352.3  479.15    4373  477.17    4526  468.22
  4689.1  464.17  4845.3  463.02  4887.3  462.87  4945.2  463.26  4965.2  463.41
  4995.1  463.15  5008.5  461.93  5009.6  460.49  5010.1  459.99  5015.4  460.49
  5018.9  462.39  5033.3  463.48  5097.2  462.98  5138.8  463.53  5189.9  462.87
  5317.7  465.49  5361.9  465.32  5419.4  466.24  5560.4  468.14  5602.2  468.69
  5630.9  467.82  5837.1  472.81  5865.8  472.61  6018.7  477.63  6036.1  478.24
#Mann= 14 ,-1 , 0
  4240.4    .035       0  4299.3     .05       0  4352.3     .07       0
  4845.3    .035       0  4887.3     .07       0  4945.2     .12       0
  4965.2    .035       0  5009.6    .035       0  5015.4    .035       0
  5138.8     .05       0  5361.9     .07       0  5419.4     .05       0
  5560.4     .07       0  6018.7     .05       0
Bank Sta=5009.6,5015.4
XS Rating Curve= 0 ,0
Exp/Cntr=0.3,0.1

Type RM Length L Ch R = 1 ,11508   ,485,485,485
BEGIN DESCRIPTION:
RUDOLPH CREEK 14.0
END DESCRIPTION:
XS GIS Cut Line= 3
      2341274.98     13767574.99        2340475.       13767225.
      2339674.99       13767525.
#Sta/Elev= 30
  4120.4  478.71  4212.3  474.56  4216.8  474.22  4309.4  466.71  4431.8  463.61
  4658.7  461.39  4764.4  461.79  4781.1  461.21  4845.7  461.88  4885.6  460.91
  4903.5  461.69  4955.8  460.34  5008.7  460.51  5030.7  459.41  5031.2  458.91
  5036.1  458.91  5036.6  459.41  5166.6  462.35  5179.6  462.87  5228.5  461.93
  5306.7   463.1  5396.1  463.73  5535.9  465.44  5559.1  465.55  5655.7  469.04
  5747.4  474.09  5752.8  473.87  5794.6  476.81  5832.9  480.83    5848  481.29
#Mann= 11 ,-1 , 0
  4120.4     .05       0  4212.3     .07       0  4216.8     .05       0
  4845.7     .12       0  5030.7     .05       0  5036.6     .12       0
  5166.6    .035       0  5306.7     .07       0  5396.1     .05       0
  5535.9     .07       0  5559.1     .05       0
Bank Sta=5030.7,5036.6
XS Rating Curve= 0 ,0
Exp/Cntr=0.3,0.1

Type RM Length L Ch R = 1 ,11023   ,452,452,452
BEGIN DESCRIPTION:
RUDOLPH CREEK 13.0
END DESCRIPTION:
XS GIS Cut Line= 3
      2341374.98     13767574.98        2340575.       13766775.
      2339375.04     13767674.97
#Sta/Elev= 30
  3869.2  482.33  4081.3  471.84  4137.9  466.91  4194.4  464.89  4364.1  462.51
  4477.3  462.46  4505.6  461.26  4540.9  462.36    4647  461.93  5025.2  457.15
  5025.7  456.65  5032.2  457.15  5051.8  458.35  5128.7  460.32  5143.3  458.97
  5157.8  460.05  5207.8  458.44  5277.3  459.03  5601.4  463.93  5657.8  464.94
  5664.1  463.76    5780  466.94  5917.2  469.23  6043.3  473.87  6164.1  481.49
  6207.8   482.3    6387  493.27  6430.2  496.92  6464.1  499.38  6500.5  499.96
#Mann= 9 ,-1 , 0
  3869.2     .05       0  5025.2     .05       0  5032.2     .05       0
  5051.8     .07       0  5277.3     .05       0  5601.4     .12       0
    5780    .035       0  5917.2     .05       0  6430.2     .07       0
Bank Sta=5025.2,5032.2
XS Rating Curve= 0 ,0
Exp/Cntr=0.3,0.1

Type RM Length L Ch R = 1 ,10571   ,444,444,444
BEGIN DESCRIPTION:
RUDOLPH CREEK 12.0
END DESCRIPTION:
XS GIS Cut Line= 3
      2341324.97       13766475.        2340525.       13766375.
      2339724.98     13767125.02
#Sta/Elev= 30
  4194.2  472.46  4294.9  469.27  4312.6  468.02  4365.5  466.13  4473.8  464.35
  4554.4  462.06  4708.5  459.73  4849.2   458.8  4930.7  456.47    4950  455.97
  4957.6  454.84  4962.6  455.32  4966.7  453.88  4967.2  453.38  4973.2  453.38
  4973.7  453.88  5000.3  455.42  5035.8  456.21  5064.1  455.64  5099.3  456.76
  5120.8  456.11  5205.8  456.55  5290.3  457.88  5389.5  457.64  5488.6  456.45
  5658.3  457.53  5877.7   462.6  5905.8  464.22  6054.7  469.65    6097  470.66
#Mann= 6 ,-1 , 0
  4194.2     .07       0  4708.5     .05       0  4930.7     .07       0
  4966.7     .05       0  4973.7     .07       0  5000.3     .05       0
Bank Sta=4966.7,4973.7
XS Rating Curve= 0 ,0
Exp/Cntr=0.3,0.1

Type RM Length L Ch R = 1 ,10127   ,458,458,458
BEGIN DESCRIPTION:
RUDOLPH CREEK 11.0
END DESCRIPTION:
XS GIS Cut Line= 3
      2341175.02       13765875.        2340375.       13766025.
      2339575.02     13766824.98
#Sta/Elev= 30
  4190.1  466.35  4332.6   462.3  4505.5  459.16    4542   457.9  4627.6  457.96
  4809.9  454.53  4851.5  454.75  4871.6  454.14  4892.1  454.59  4932.8  453.28
  4953.2  454.06  4972.7  453.61  4977.8  454.25  4980.2  452.03  4980.7  451.53
  4986.8  451.53  4987.3  452.03  5001.5  453.31  5018.2  452.77  5039.9  453.31
  5060.6  454.73  5187.9  456.28  5357.6  454.62  5456.6  455.09  5555.6   454.5
  5612.2  455.87  5654.6  454.46  5810.2  458.05  5979.9   463.6  6135.4  472.55
#Mann= 5 ,-1 , 0
  4190.1     .05       0  4871.6     .07       0  4980.2     .05       0
  4987.3     .07       0  5039.9     .05       0
Bank Sta=4980.2,4987.3
XS Rating Curve= 0 ,0
Exp/Cntr=0.3,0.1

Type RM Length L Ch R = 1 ,9669    ,456,456,456
BEGIN DESCRIPTION:
RUDOLPH CREEK 10.0
END DESCRIPTION:
XS GIS Cut Line= 3
      2341424.97       13765625.        2340225.       13765625.
      2339425.03     13766424.97
#Sta/Elev= 30
  3804.6  477.02  4124.6  461.41  4374.6  456.99  4624.6  454.08  4729.1  451.84
  4734.6  451.34  4754.6  452.62  4764.6  452.06  4794.6  452.91  4860.5  451.89
  4884.6  451.37  5018.7  452.26  5029.3  449.44  5029.8  448.94  5036.4  449.44
    5047  451.64  5061.1  452.24  5103.6   451.8  5174.3  452.98  5322.8  453.64
  5471.3  453.06  5570.3  450.99  5669.2  452.25  5683.4  450.48  5697.5  450.64
    5740  451.78  5796.5  454.98  5867.2  456.15  6008.7  460.51  6135.9   465.5
#Mann= 5 ,-1 , 0
  3804.6     .05       0  4729.1     .07       0  4860.5     .05       0
  5029.3     .05       0  5036.4     .05       0
Bank Sta=5029.3,5036.4
XS Rating Curve= 0 ,0
Exp/Cntr=0.3,0.1

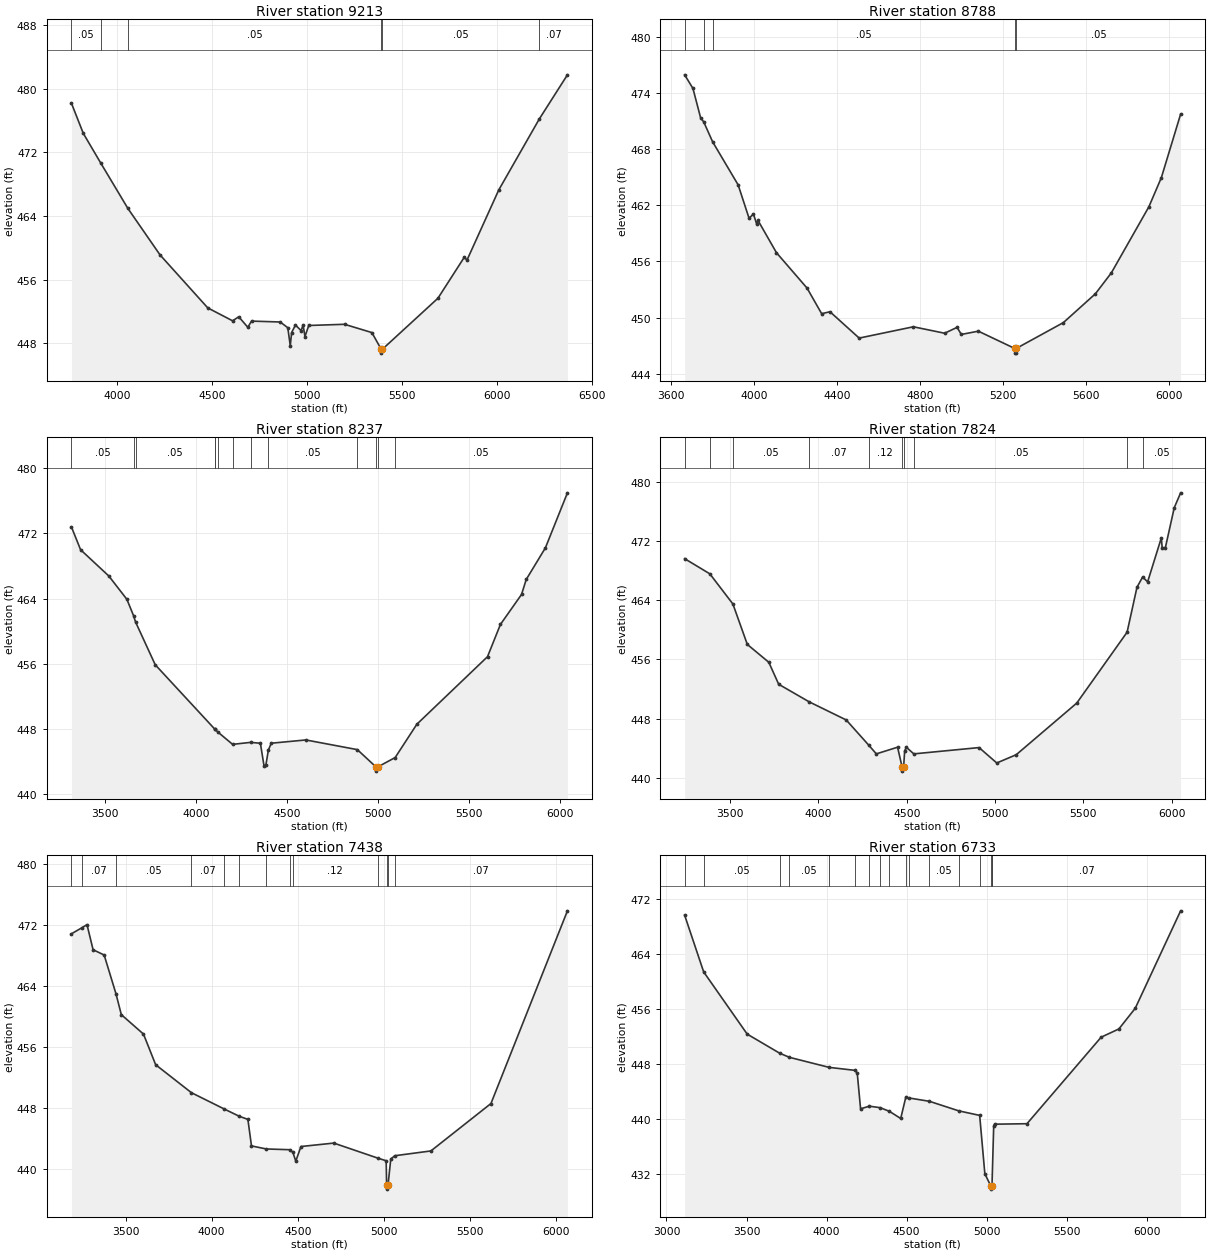
Type RM Length L Ch R = 1 ,9213    ,425,425,425
BEGIN DESCRIPTION:
B20316
END DESCRIPTION:
XS GIS Cut Line= 3
      2341360.05      13765354.7      2340072.56     13765259.54
      2338808.73     13765634.22
#Sta/Elev= 30
    3762  478.15    3824  474.38  3915.9  470.65  4058.7  464.95    4228  459.11
    4479  452.46  4609.4  450.84  4642.1  451.34  4689.6  450.03  4709.6   450.8
    4860  450.69  4900.1  449.97  4913.1  447.71  4920.2  449.36  4940.3  450.31
  4970.3   449.6  4980.4  450.33  4990.4  448.86  5010.4  450.25  5198.5   450.4
  5342.5  449.36  5391.1  447.28  5391.6  446.78  5398.2  447.28  5689.9  453.67
  5828.1   458.8  5843.2  458.48    6010  467.27    6223  476.17  6371.2  481.72
#Mann= 6 ,-1 , 0
    3762     .05       0  3915.9     .07       0  4058.7     .05       0
  5391.1     .05       0  5398.2     .05       0    6223     .07       0
Bank Sta=5391.1,5398.2
XS Rating Curve= 0 ,0
Exp/Cntr=0.3,0.1

Type RM Length L Ch R = 1 ,8788    ,551,551,551
BEGIN DESCRIPTION:
B20315
END DESCRIPTION:
XS GIS Cut Line= 3
      2341214.53     13765080.42      2340794.68     13764828.51
      2338902.65     13764996.44
#Sta/Elev= 30
  3665.2  475.98  3705.2  474.52  3742.1  471.38  3757.1  470.94  3800.2   468.8
  3922.9   464.2  3975.4  460.63  3996.7  461.08  4012.3  459.99  4018.1  460.41
  4107.5  456.94  4254.9  453.15  4325.2  450.41  4365.3  450.62  4505.9   447.8
  4766.9  449.01  4917.5  448.32  4977.7  448.95  4997.8  448.19  5079.9  448.54
  5255.3  446.69  5255.8  446.19  5261.9  446.19  5262.4  446.69  5489.7  449.46
  5643.7  452.54  5720.6  454.78  5901.3  461.85  5961.6  464.98  6054.3  471.77
#Mann= 5 ,-1 , 0
  3665.2     .05       0  3757.1     .07       0  3800.2     .05       0
  5255.3     .05       0  5262.4     .05       0
Bank Sta=5255.3,5262.4
XS Rating Curve= 0 ,0
Exp/Cntr=0.3,0.1

Type RM Length L Ch R = 1 ,8237    ,413,413,413
BEGIN DESCRIPTION:
B20314
END DESCRIPTION:
XS GIS Cut Line= 4
      2341164.17     13764996.48      2340626.74     13764492.64
      2339434.41     13764470.25      2338645.12     13764358.29
#Sta/Elev= 30
  3316.4  472.79  3366.5     470  3521.8  466.77    3621  463.91  3658.2  461.87
  3668.6  461.13  3776.8  455.87    4103  447.99  4103.6  447.98  4121.3   447.6
  4202.1  446.09  4300.6  446.33  4354.9  446.23  4374.9  443.45  4384.9  443.52
    4399   445.4  4414.9  446.23  4604.9  446.63  4887.9  445.44  4991.1   443.3
  4991.6   442.8  4998.9   443.3  5095.9  444.47    5215  448.56  5603.5  456.86
  5674.4  460.82  5790.4   464.5  5816.4  466.35  5921.7  470.23  6042.8  476.99
#Mann= 13 ,-1 , 0
  3316.4     .05       0  3658.2     .07       0  3668.6     .05       0
    4103     .07       0  4103.6     .05       0  4121.3     .07       0
  4202.1     .12       0  4300.6     .07       0    4399     .05       0
  4887.9     .07       0  4991.1     .05       0  4998.9     .07       0
  5095.9     .05       0
Bank Sta=4991.1,4998.9
XS Rating Curve= 0 ,0
Exp/Cntr=0.3,0.1

Type RM Length L Ch R = 1 ,7824    ,386,386,386
BEGIN DESCRIPTION:
B20313
END DESCRIPTION:
XS GIS Cut Line= 4
      2341091.38     13764867.72      2340525.98     13764162.37
      2339546.37       13764084.      2338629.21     13763988.93
#Sta/Elev= 30
  3242.4  469.59  3385.1  467.54  3515.6  463.47  3597.3  458.01    3719   455.6
    3775  452.63  3948.9  450.24  4157.4  447.81  4283.7  444.44  4327.9  443.23
  4448.3  444.13  4474.5   441.4    4475   440.9  4482.3   441.4  4488.5  443.66
  4498.5  444.11  4540.3  443.23  4909.8  444.08  5010.1     442  5120.5  443.12
  5463.1  450.09  5748.1  459.66  5804.1  465.73  5836.1  467.11  5864.4  466.46
  5941.8  472.38  5946.9  471.07    5965  471.09  6015.2  476.47  6051.2  478.48
#Mann= 10 ,-1 , 0
  3242.4     .05       0  3385.1     .07       0  3515.6     .05       0
  3948.9     .07       0  4283.7     .12       0  4474.5     .05       0
  4482.3     .12       0  4540.3     .05       0  5748.1     .07       0
  5836.1     .05       0
Bank Sta=4474.5,4482.3
XS Rating Curve= 0 ,0
Exp/Cntr=0.3,0.1

Type RM Length L Ch R = 1 ,7438    ,705,705,705
BEGIN DESCRIPTION:
B20312
END DESCRIPTION:
XS GIS Cut Line= 3
      2341085.76     13764800.51      2340302.07     13763781.72
      2338712.27     13763658.57
#Sta/Elev= 30
  3186.1  470.86    3246  471.64  3276.3  472.06  3311.6  468.77    3376  468.07
  3444.4     463  3475.6  460.25  3604.3   457.7    3675  453.68  3882.7  450.01
  4073.4  447.87  4161.2  446.91  4210.5  446.51  4231.4  443.03  4316.8  442.63
  4454.5  442.53    4472  442.17  4488.6  441.03  4518.7  442.95  4709.2   443.4
  4964.7  441.43  5013.4  441.08  5016.2  437.86  5016.7  437.36  5024.1  437.86
  5040.2   441.3  5063.3  441.74  5273.2  442.37  5621.9  448.59    6066  473.87
#Mann= 13 ,-1 , 0
  3186.1     .05       0    3246     .07       0  3444.4     .05       0
  3882.7     .07       0  4073.4     .05       0  4161.2     .07       0
  4316.8     .12       0  4454.5      .1       0    4472     .12       0
  4964.7      .1       0  5016.2     .05       0  5024.1      .1       0
  5063.3     .07       0
Bank Sta=5016.2,5024.1
XS Rating Curve= 0 ,0
Exp/Cntr=0.3,0.1

Type RM Length L Ch R = 1 ,6733    ,638,638,638
BEGIN DESCRIPTION:
B20311
END DESCRIPTION:
XS GIS Cut Line= 4
      2341029.76     13764626.96        2339983.     13763205.15
      2339585.55     13763143.57      2338661.92     13763037.21
#Sta/Elev= 30
  3113.6  469.71  3232.4  461.46  3504.2  452.41    3707  449.63  3767.9  449.03
  4015.6  447.57  4175.4  447.14  4191.4  446.76  4212.3  441.54  4267.6  441.92
  4335.1   441.7  4392.5  441.17    4463  440.13  4494.9  443.24  4513.8  443.12
  4642.4  442.63  4825.4  441.24  4956.1  440.58  4988.5  432.08  5024.8  430.35
  5025.3  429.85  5033.1  430.35  5033.3  430.55  5043.8  439.07  5049.2   439.3
  5251.6  439.37  5714.8  451.96  5825.5  453.16  5927.8  456.17  6211.1  470.35
#Mann= 17 ,-1 , 0
  3113.6     .07       0  3232.4     .05       0    3707     .07       0
  3767.9     .05       0  4015.6     .07       0  4175.4      .1       0
  4267.6     .12       0  4335.1      .1       0  4392.5     .12       0
  4494.9      .1       0  4513.8     .12       0  4642.4     .05       0
  4825.4     .07       0  4956.1     .12       0  5024.8     .05       0
  5033.1     .12       0  5033.3     .07       0
Bank Sta=5024.8,5033.1
XS Rating Curve= 0 ,0
Exp/Cntr=0.3,0.1

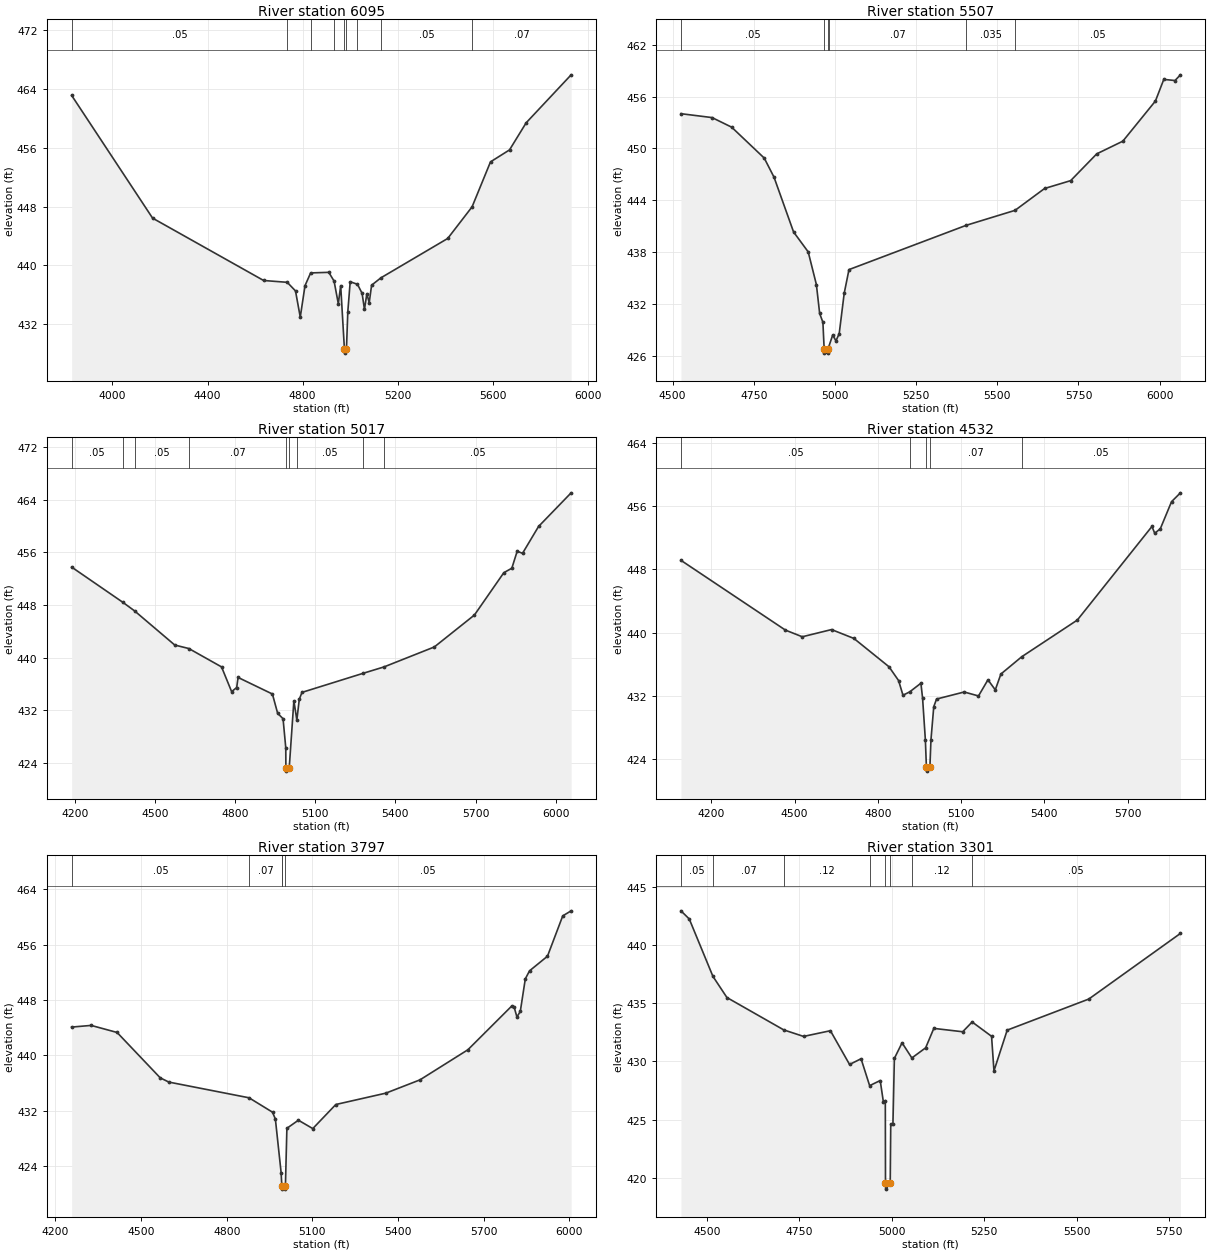
Type RM Length L Ch R = 1 ,6095    ,588,588,588
BEGIN DESCRIPTION:
RUDOLPH CREEK 9.0
END DESCRIPTION:
XS GIS Cut Line= 3
      2340777.88     13762348.68      2339988.59     13762684.55
      2338745.88     13762678.95
#Sta/Elev= 30
  3828.5  463.15  4168.9  446.44  4635.8  437.95  4735.1   437.7  4769.9  436.53
  4789.9  432.96  4809.9  437.25  4833.6  438.98  4909.9  439.06  4932.1  437.87
  4949.9  434.79  4959.9  437.25  4975.7  428.56  4976.2  428.06  4984.1  428.56
  4989.9  433.72  4999.9  437.78  5030.5  437.43  5049.9  436.21  5059.9  434.02
  5069.9  436.15  5079.9  434.93  5089.9  437.31    5129  438.31  5409.9  443.67
  5512.5  447.98  5589.9   454.1  5669.9  455.73  5739.9  459.42    5929  465.95
#Mann= 9 ,-1 , 0
  3828.5     .05       0  4735.1     .12       0  4833.6     .07       0
  4932.1     .05       0  4975.7     .05       0  4984.1     .05       0
  5030.5     .12       0    5129     .05       0  5512.5     .07       0
Bank Sta=4975.7,4984.1
XS Rating Curve= 0 ,0
Exp/Cntr=0.3,0.1

Type RM Length L Ch R = 1 ,5507    ,490,490,490
BEGIN DESCRIPTION:
B20310
END DESCRIPTION:
XS GIS Cut Line= 3
      2340240.53     13762175.15      2339619.14     13762119.17
       2338708.3     13762035.35
#Sta/Elev= 30
  4525.5  454.01  4621.4  453.56  4681.7  452.45  4782.1  448.87  4812.2  446.66
  4872.4  440.32  4917.5  438.01  4942.7  434.23  4952.8  430.88  4962.8  429.86
  4966.6  426.79  4967.1  426.29  4978.5  426.29    4979  426.79  4980.3  426.97
  4992.9  428.38    5003  427.71    5013  428.55  5028.4  433.22  5043.1  435.96
  5404.4  441.09  5554.6  442.82  5645.6  445.35    5726  446.26  5806.3  449.36
  5886.7  450.83  5987.1  455.48  6012.8  457.98  6047.3  457.85  6064.1  458.51
#Mann= 6 ,-1 , 0
  4525.5     .05       0  4966.6     .05       0    4979     .05       0
  4980.3     .07       0  5404.4    .035       0  5554.6     .05       0
Bank Sta=4966.6,4979
XS Rating Curve= 0 ,0
Exp/Cntr=0.3,0.1

Type RM Length L Ch R = 1 ,5017    ,485,485,485
BEGIN DESCRIPTION:
B20309
END DESCRIPTION:
XS GIS Cut Line= 3
      2340526.02     13761620.96      2339277.67     13761822.49
      2338673.08     13761822.49
#Sta/Elev= 30
  4188.6  453.78  4380.6  448.42    4424  447.13  4574.5  441.94  4627.2  441.41
  4749.5  438.62  4787.3  434.86  4806.2  435.49  4811.3  437.02  4939.9   434.5
  4959.5  431.57  4979.7  430.75  4989.9  426.32  4990.3  423.29  4990.8  422.79
  5002.8  423.29  5020.2  433.48  5031.3  430.54  5040.5  433.72  5050.6  434.75
  5279.5  437.65  5357.6  438.62  5545.8  441.65  5695.8   446.5  5805.8  452.93
  5835.8  453.61  5855.8  456.19  5875.8  455.87  5935.8  459.95  6057.7  465.06
#Mann= 9 ,-1 , 0
  4188.6     .05       0  4380.6     .07       0    4424     .05       0
  4627.2     .07       0  4990.3     .05       0  5002.8     .07       0
  5031.3     .05       0  5279.5    .035       0  5357.6     .05       0
Bank Sta=4990.3,5002.8
XS Rating Curve= 0 ,0
Exp/Cntr=0.3,0.1

Type RM Length L Ch R = 1 ,4532    ,735,735,735
BEGIN DESCRIPTION:
B20308
END DESCRIPTION:
XS GIS Cut Line= 2
      2340458.82     13761242.56       2338673.1     13761466.47
#Sta/Elev= 30
  4090.5  449.14    4467  440.32  4527.7  439.48  4633.1  440.39  4713.6  439.27
  4840.1  435.69  4874.6  433.95  4890.5  432.09  4914.9  432.52  4955.1  433.61
  4961.1  431.74  4971.2  426.43  4974.9     423  4975.4   422.5  4987.5     423
  4991.3  426.45  5001.4  430.64  5011.5  431.61    5111   432.5  5162.6     432
  5196.6  434.04  5223.1  432.77  5243.3  434.77  5318.6  436.96  5518.6  441.59
  5787.5  453.42  5797.6  452.56  5817.7  453.13  5858.1  456.55  5890.2  457.67
#Mann= 5 ,-1 , 0
  4090.5     .05       0  4914.9     .07       0  4974.9     .05       0
  4987.5     .07       0  5318.6     .05       0
Bank Sta=4974.9,4987.5
XS Rating Curve= 0 ,0
Exp/Cntr=0.3,0.1

Type RM Length L Ch R = 1 ,3797    ,496,496,496
BEGIN DESCRIPTION:
B20307
END DESCRIPTION:
XS GIS Cut Line= 3
      2340262.86     13760845.12      2339171.31     13760985.06
      2338570.08     13761230.01
#Sta/Elev= 30
  4256.6  444.07    4325  444.31  4415.8  443.29    4567  436.73  4597.2  436.12
    4878  433.85  4960.2  431.77  4970.3  430.77  4990.4  423.03  4992.6  421.31
  4992.8  421.15  4993.3  420.65    5005  420.65  5005.5  421.15  5010.6  429.44
  5050.9  430.61  5101.3   429.4    5182  432.88  5357.1  434.52  5476.7  436.44
  5644.6  440.79  5797.7  447.09  5806.6  446.96  5816.4  445.53  5828.2  446.33
  5845.8  451.04  5860.6   452.2  5923.4  454.31  5976.9  460.14  6006.3  460.87
#Mann= 5 ,-1 , 0
  4256.6     .05       0    4878     .07       0  4992.6     .05       0
  4992.8     .05       0  5005.5     .05       0
Bank Sta=4992.8,5005.5
XS Rating Curve= 0 ,0
Exp/Cntr=0.3,0.1

Type RM Length L Ch R = 1 ,3301    ,466,466,466
BEGIN DESCRIPTION:
RUDOLPH CREEK 4.0
END DESCRIPTION:
XS GIS Cut Line= 3
      2339975.01       13760625.        2339425.       13760475.
      2338825.02     13760974.98
#Sta/Elev= 30
  4429.7  442.94  4452.2  442.24  4516.2  437.31  4554.1  435.49  4707.8  432.71
  4761.4  432.15    4834  432.64  4885.8  429.74  4916.9  430.23  4940.1  427.92
  4968.7  428.36  4977.3  426.52  4982.5  426.64    4983  419.53  4983.5  419.03
  4995.8  419.53  4997.2   424.6  5003.1   424.6    5007  430.26  5027.8   431.6
  5054.3   430.3  5091.6  431.17  5113.7  432.84  5191.8  432.55  5217.4  433.39
  5269.9  432.16  5276.4  429.19  5312.2  432.69  5532.9  435.36  5780.8     441
#Mann= 8 ,-1 , 0
  4429.7     .05       0  4516.2     .07       0  4707.8     .12       0
  4940.1      .1       0    4983     .05       0  4995.8      .1       0
  5054.3     .12       0  5217.4     .05       0
Bank Sta=4983,4995.8
XS Rating Curve= 0 ,0
Exp/Cntr=0.3,0.1