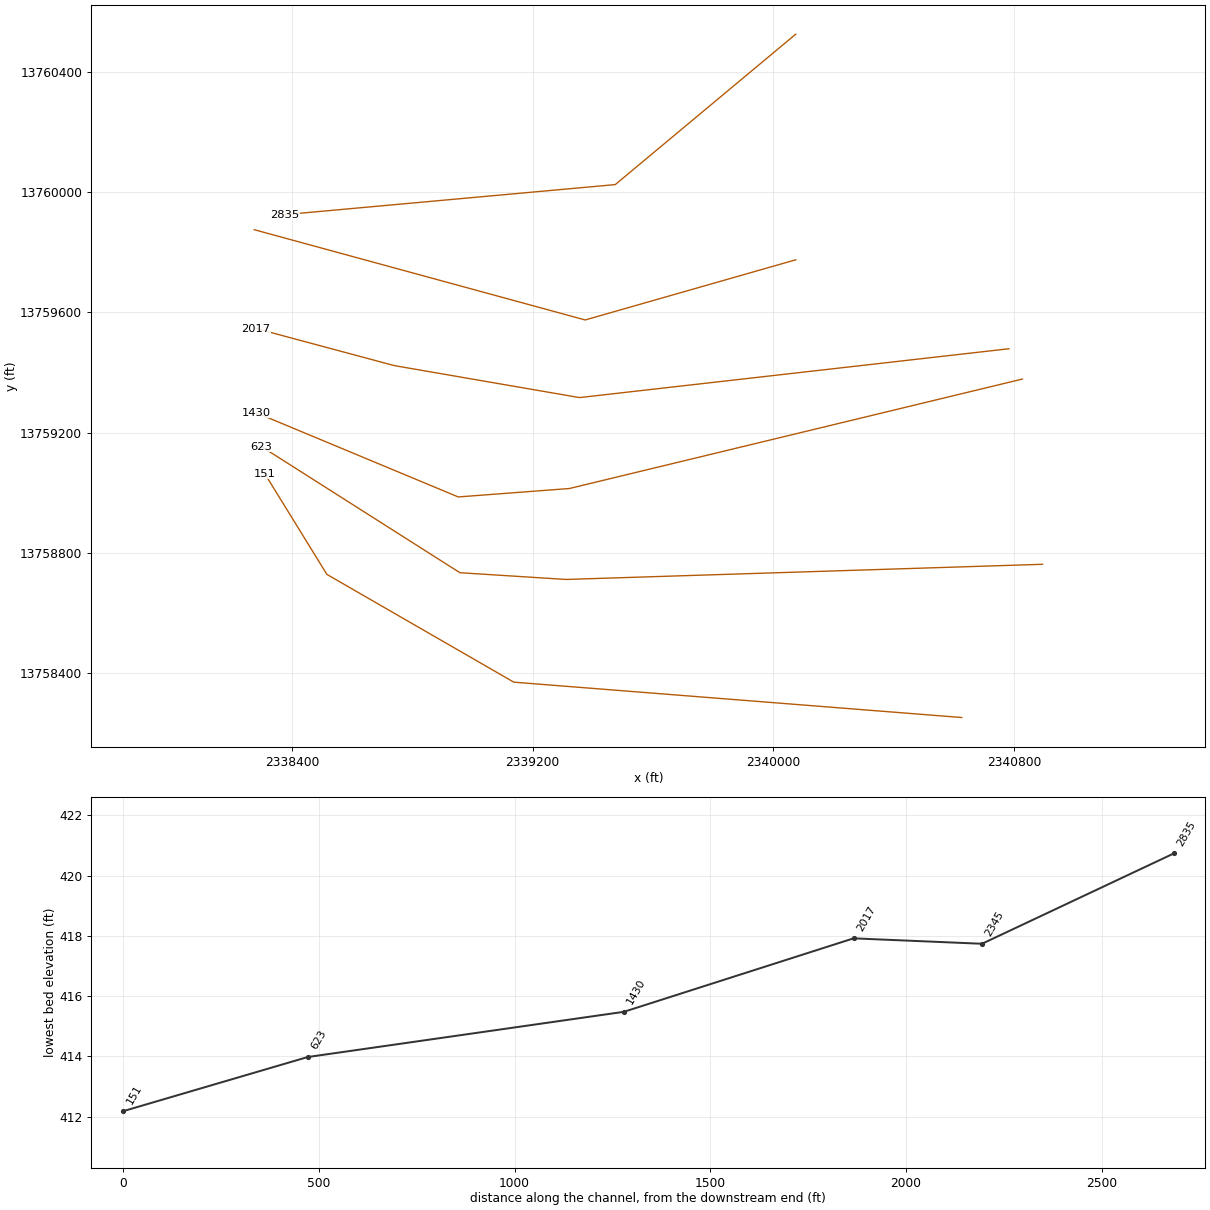
HEC-RAS study RUDOLPH CREEK.prj: RUDOLPH CREEK Base Level Engineering

--- RUDOLPH CREEK.g01 (geometry) --- (continued)

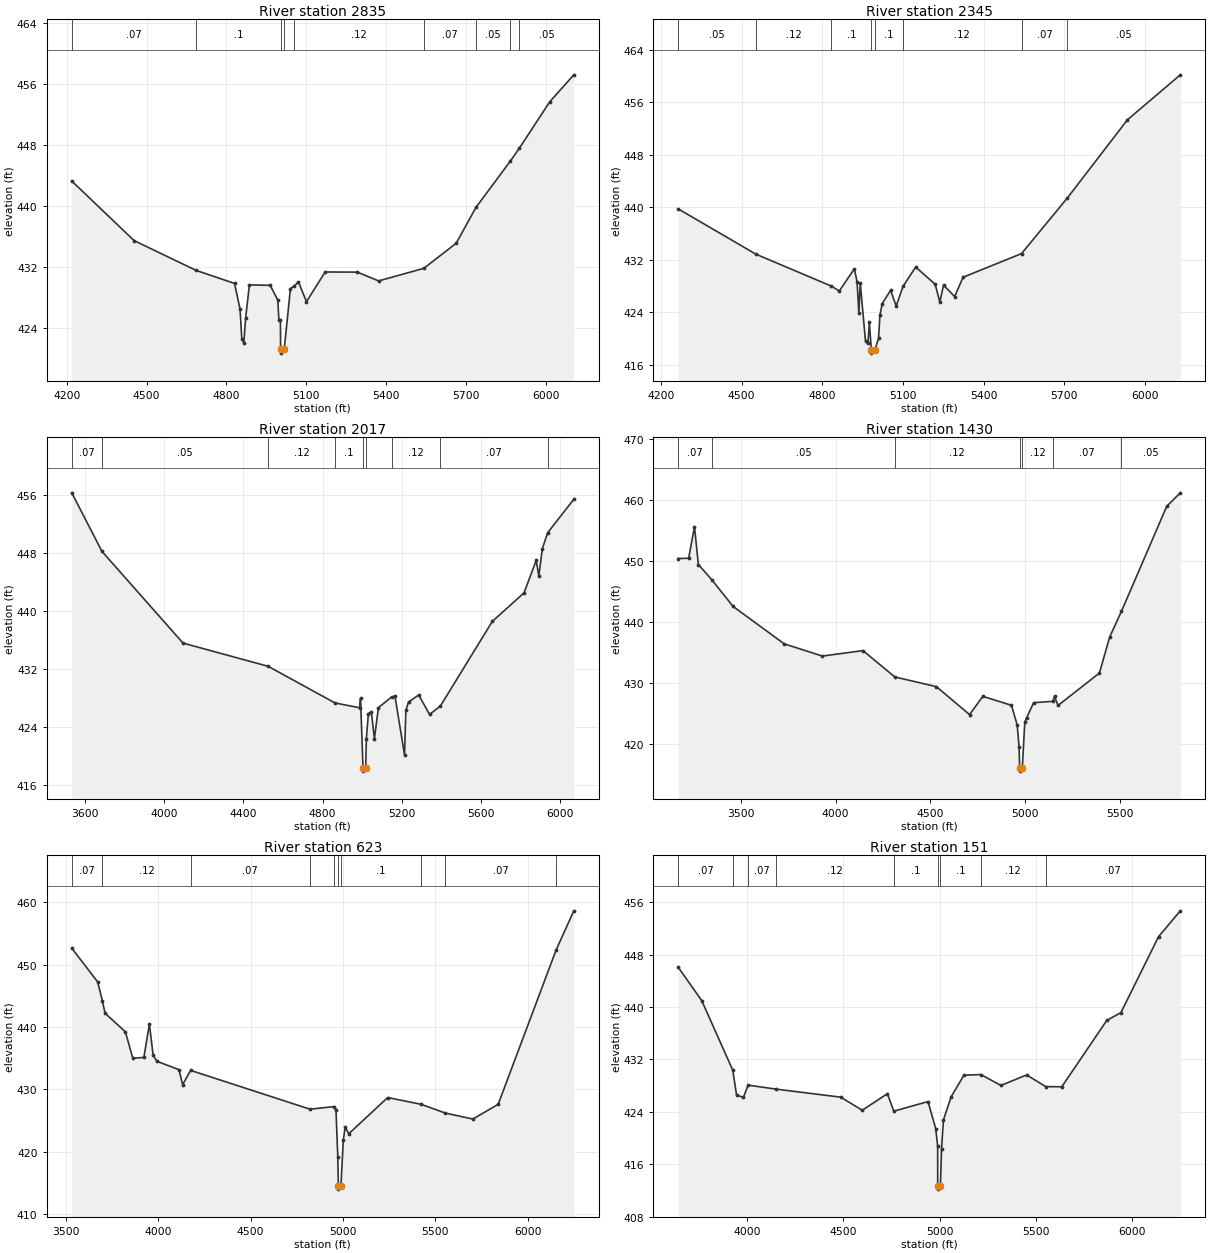
Type RM Length L Ch R = 1 ,2835    ,490,490,490
BEGIN DESCRIPTION:
RUDOLPH CREEK 3.0
END DESCRIPTION:
XS GIS Cut Line= 3
        2340075.       13760525.        2339475.       13760025.
      2338374.96       13759925.
#Sta/Elev= 30
    4219  443.26  4453.3  435.46  4685.9  431.57  4830.2  429.86    4851   426.5
  4857.5  422.64  4865.3  422.06  4871.8  425.28  4886.1  429.67  4964.2  429.61
  4992.9  427.67  4996.8  425.09  5002.5  425.09  5003.3  421.24  5003.8  420.74
  5016.9  421.24  5040.2  429.18    5055  429.53  5070.3  430.08  5100.4  427.47
  5170.7  431.36  5291.2  431.34  5371.5  430.19  5541.4  431.84  5662.7  435.12
  5736.8   439.8  5866.1  445.87  5900.3  447.57  6014.2  453.64  6104.6  457.16
#Mann= 9 ,-1 , 0
    4219     .07       0  4685.9      .1       0  5003.3     .05       0
  5016.9      .1       0    5055     .12       0  5541.4     .07       0
  5736.8     .05       0  5866.1     .07       0  5900.3     .05       0
Bank Sta=5003.3,5016.9
XS Rating Curve= 0 ,0
Exp/Cntr=0.3,0.1

Type RM Length L Ch R = 1 ,2345    ,328,328,328
BEGIN DESCRIPTION:
RUDOLPH CREEK 2.0
END DESCRIPTION:
XS GIS Cut Line= 3
      2340075.03     13759775.01        2339375.       13759575.
      2338275.02     13759874.99
#Sta/Elev= 30
    4264  439.75  4552.5  432.85  4833.6  427.97  4863.3  427.22  4919.2   430.6
  4929.6  428.62  4936.1  423.84  4941.3  428.43  4960.8  419.57  4969.9  419.23
  4975.1  422.44  4982.6  418.24  4983.1  417.74  4996.2  418.24  5009.3  420.01
  5014.5  423.55  5023.1  425.29  5054.2  427.33    5075  424.93  5100.5  427.93
  5147.5  430.88  5220.1  428.25  5237.4  425.54  5251.2  428.12  5292.6  426.37
  5323.7  429.32  5541.5  432.93    5711  441.37  5935.3  453.34  6132.2  460.21
#Mann= 8 ,-1 , 0
    4264     .05       0  4552.5     .12       0  4833.6      .1       0
  4982.6     .05       0  4996.2      .1       0  5100.5     .12       0
  5541.5     .07       0    5711     .05       0
Bank Sta=4982.6,4996.2
XS Rating Curve= 0 ,0
Exp/Cntr=0.3,0.1

Type RM Length L Ch R = 1 ,2017    ,587,587,587
BEGIN DESCRIPTION:
B20306
END DESCRIPTION:
XS GIS Cut Line= 4
      2340783.46     13759479.24      2339356.04     13759316.91
      2338740.28     13759423.27      2338281.31     13759546.41
#Sta/Elev= 30
  3532.4  456.31  3684.7  448.24  4094.5  435.58  4524.7  432.38  4862.1  427.33
  4986.2  426.66  4991.3  427.94  5003.8  418.42  5004.3  417.92  5017.5  418.42
  5020.8  422.35    5031  425.86    5046   426.1  5061.4   422.4  5081.7  426.68
  5149.4  428.17  5165.7  428.22  5213.6  420.15  5220.4   426.3  5233.9  427.46
  5285.3  428.42  5340.1  425.74  5394.8   426.9  5657.4  438.58  5817.4  442.51
  5878.9  446.98  5892.2  444.87    5910  448.61  5936.4  450.79  6069.1  455.43
#Mann= 9 ,-1 , 0
  3532.4     .07       0  3684.7     .05       0  4524.7     .12       0
  4862.1      .1       0  5003.8     .05       0  5017.5      .1       0
  5149.4     .12       0  5394.8     .07       0  5936.4     .05       0
Bank Sta=5003.8,5017.5
XS Rating Curve= 0 ,0
Exp/Cntr=0.3,0.1

Type RM Length L Ch R = 1 ,1430    ,807,807,807
BEGIN DESCRIPTION:
B20305
END DESCRIPTION:
XS GIS Cut Line= 4
      2340828.27     13759378.49      2339322.45     13759014.63
        2338953.     13758986.64      2338281.25     13759266.54
#Sta/Elev= 30
  3170.7  450.36  3225.5  450.41  3256.4  455.56  3276.9  449.38  3349.5  446.81
  3459.6  442.51  3729.6  436.36  3930.4  434.36  4144.9  435.25  4312.7  430.93
  4532.1  429.34  4706.9  424.75  4776.8  427.75  4927.9  426.28    4958  423.05
    4968   419.4  4971.1  415.98  4971.6  415.48  4984.9  415.98  4998.1  423.52
  5008.1  424.25  5044.6  426.71  5145.5  426.93  5154.9  427.77  5173.3  426.25
  5391.5  431.57  5445.7  437.48  5507.7   441.7  5746.4  458.92  5818.1  461.14
#Mann= 7 ,-1 , 0
  3170.7     .07       0  3349.5     .05       0  4312.7     .12       0
  4971.1     .05       0  4984.9     .12       0  5145.5     .07       0
  5507.7     .05       0
Bank Sta=4971.1,4984.9
XS Rating Curve= 0 ,0
Exp/Cntr=0.3,0.1

Type RM Length L Ch R = 1 ,623     ,472,472,472
BEGIN DESCRIPTION:
B20304
END DESCRIPTION:
XS GIS Cut Line= 4
      2340895.44     13758762.73      2339311.26     13758712.35
       2338958.6     13758734.74        2338299.     13759153.97
#Sta/Elev= 30
  3531.1  452.63  3671.6  447.21  3697.4  444.12  3711.6  442.19  3821.7  439.21
  3861.7  434.98  3921.7   435.1  3951.7  440.45  3971.8  435.48  3991.8  434.49
  4111.8  433.14  4131.8  430.73  4174.8  433.03  4821.7   426.8  4952.9  427.22
  4962.3  426.74  4972.3  419.12  4975.3  414.48  4975.8  413.98  4989.2  414.48
  5002.3  421.92  5012.3  423.88  5032.3  422.88  5242.6  428.67    5423  427.59
  5554.7  426.18  5703.9  425.22    5841  427.58  6155.5  452.38    6251  458.62
#Mann= 10 ,-1 , 0
  3531.1     .07       0  3697.4     .12       0  4174.8     .07       0
  4821.7     .12       0  4952.9      .1       0  4975.3     .05       0
  4989.2      .1       0    5423     .12       0  5554.7     .07       0
  6155.5     .05       0
Bank Sta=4975.3,4989.2
XS Rating Curve= 0 ,0
Exp/Cntr=0.3,0.1

Type RM Length L Ch R = 1 ,151     ,0,0,0
BEGIN DESCRIPTION:
B20303
END DESCRIPTION:
XS GIS Cut Line= 4
      2340626.75     13758253.33      2339137.73     13758370.88
      2338516.37     13758729.14      2338309.62     13759064.42
#Sta/Elev= 30
  3644.5  446.05  3766.6  440.95  3927.4  430.34  3947.2  426.53  3982.9  426.19
  4006.8  428.06  4151.7  427.45  4487.8  426.22  4599.2  424.22  4729.6  426.75
  4762.7  424.08  4940.3  425.55  4980.4  421.42  4990.4  418.77  4990.7  412.68
  4991.2  412.18  5004.6  412.68  5010.5  418.33  5020.5  422.75  5060.6  426.29
  5126.4  429.56  5214.6  429.68  5318.4  428.01    5452  429.61  5551.3  427.83
  5634.4  427.81  5867.8  437.94  5941.2  439.13  6136.3  450.72  6249.3  454.67
#Mann= 9 ,-1 , 0
  3644.5     .07       0  3927.4     .12       0  4006.8     .07       0
  4151.7     .12       0  4762.7      .1       0  4990.7     .05       0
  5004.6      .1       0  5214.6     .12       0  5551.3     .07       0
Bank Sta=4990.7,5004.6
XS Rating Curve= 0 ,0
Exp/Cntr=0.3,0.1

Chan Stop Cuts=-1
Use User Specified Reach Order=0
Composite Channel Slope=5