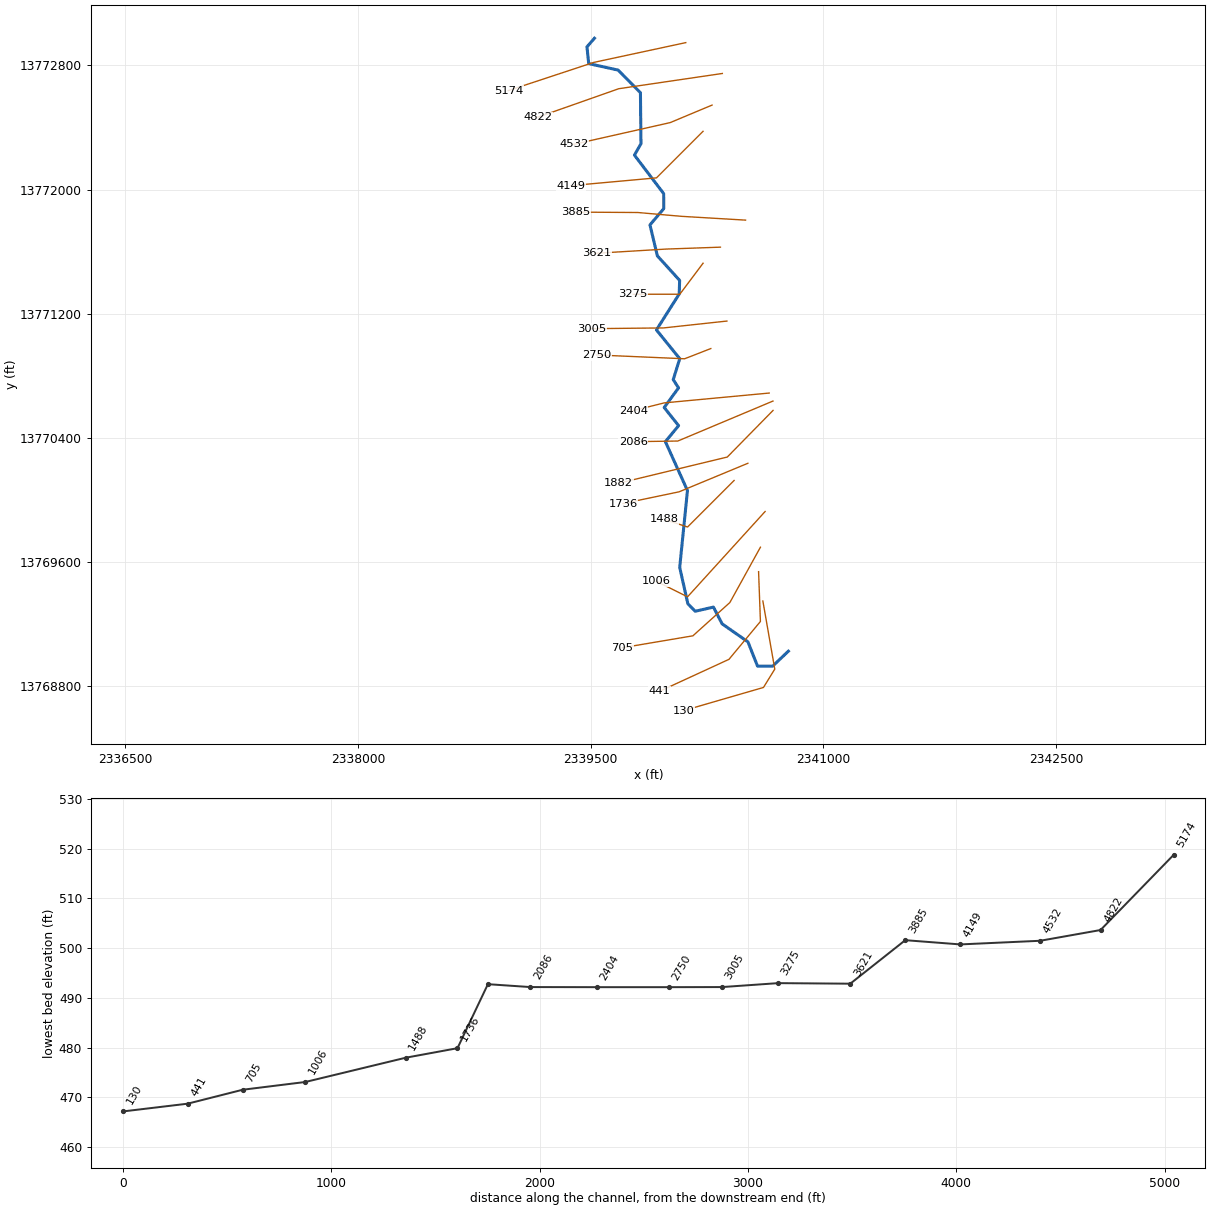
--- RUDOLPH TRIBUTARY 1.prj (project) ---

Proj Title=RUDOLPH TRIBUTARY 1 Base Level Engineering
Current Plan=p01
Default Exp/Contr=0.3,0.1
English Units
Geom File=g01
Flow File=f01
Plan File=p01
BEGIN DESCRIPTION:
RUDOLPH TRIBUTARY 1
END DESCRIPTION:

--- RUDOLPH TRIBUTARY 1.p01 (plan) ---

Plan Title=Multiple Run
Short Identifier=Multiple
Geom File=g01
Flow File=f01
Subcritical Flow
K Sum by GR= 0
Std Step Tol= 0.01
Critical Tol= 0.01
Num of Std Step Trials= 20
Max Error Tol= 0.3
Flow Tol Ratio= 0.001
Split Flow NTrial= 30
Split Flow Tol= 0.02
Split Flow Ratio= 0.02
Log Output Level= 0
Friction Slope Method= 1
Unsteady Friction Slope Method= 2
Unsteady Bridges Friction Slope Method= 1
Parabolic Critical Depth
Global Vel Dist=  1 , 1 , 1
Global Log Level= 0
CheckData=True
Encroach Param= -1, 0, 0, 0
BEGIN DESCRIPTION:
Multiple Run
END DESCRIPTION:

--- RUDOLPH TRIBUTARY 1.f01 (steady flow) ---

Flow Title=Multiple
Number of Profiles=7
Profile Names=10-year,25-year,50-year,1pct_min,100-year,1pct_plu,500-year
River Rch & RM= RUDOLPH TRIBUTAR,Reach-1,5174
     569     919    1235     805    1606    3205    2689
Boundary for River Rch & Prof#=RUDOLPH TRIBUTAR,Reach-1,1
Up Type=0
Dn Type=3
Dn Slope=0.005
Boundary for River Rch & Prof#=RUDOLPH TRIBUTAR,Reach-1,2
Up Type=0
Dn Type=3
Dn Slope=0.005
Boundary for River Rch & Prof#=RUDOLPH TRIBUTAR,Reach-1,3
Up Type=0
Dn Type=3
Dn Slope=0.005
Boundary for River Rch & Prof#=RUDOLPH TRIBUTAR,Reach-1,4
Up Type=0
Dn Type=3
Dn Slope=0.005
Boundary for River Rch & Prof#=RUDOLPH TRIBUTAR,Reach-1,5
Up Type=0
Dn Type=3
Dn Slope=0.005
Boundary for River Rch & Prof#=RUDOLPH TRIBUTAR,Reach-1,6
Up Type=0
Dn Type=3
Dn Slope=0.005
Boundary for River Rch & Prof#=RUDOLPH TRIBUTAR,Reach-1,7
Up Type=0
Dn Type=3
Dn Slope=0.005

--- RUDOLPH TRIBUTARY 1.g01 (geometry) ---

Geom Title=Existing Conditions

River Reach=RUDOLPH TRIBUTAR,Reach-1
Reach XY= 30
      2339525.00     13772975.00      2339476.76     13772919.16
      2339488.16     13772811.27      2339677.45     13772769.53
      2339821.46     13772623.54      2339824.81     13772294.98
      2339782.79     13772221.58      2339971.33     13771973.41
      2339971.52     13771876.50      2339882.88     13771771.78
      2339930.47     13771572.55      2340074.07     13771414.52
      2340071.33     13771326.59      2339924.53     13771095.16
      2340074.75     13770909.78      2340032.81     13770774.90
      2340066.99     13770721.67      2339974.54     13770595.16
      2340067.38     13770478.33      2339982.34     13770375.10
      2340124.49     13770059.79      2340074.50     13769564.83
      2340127.06     13769330.45      2340174.67     13769282.25
      2340292.05     13769308.92      2340347.86     13769201.17
      2340514.49     13769084.81      2340576.25     13768928.36
      2340673.52     13768928.40      2340775.00     13769025.00

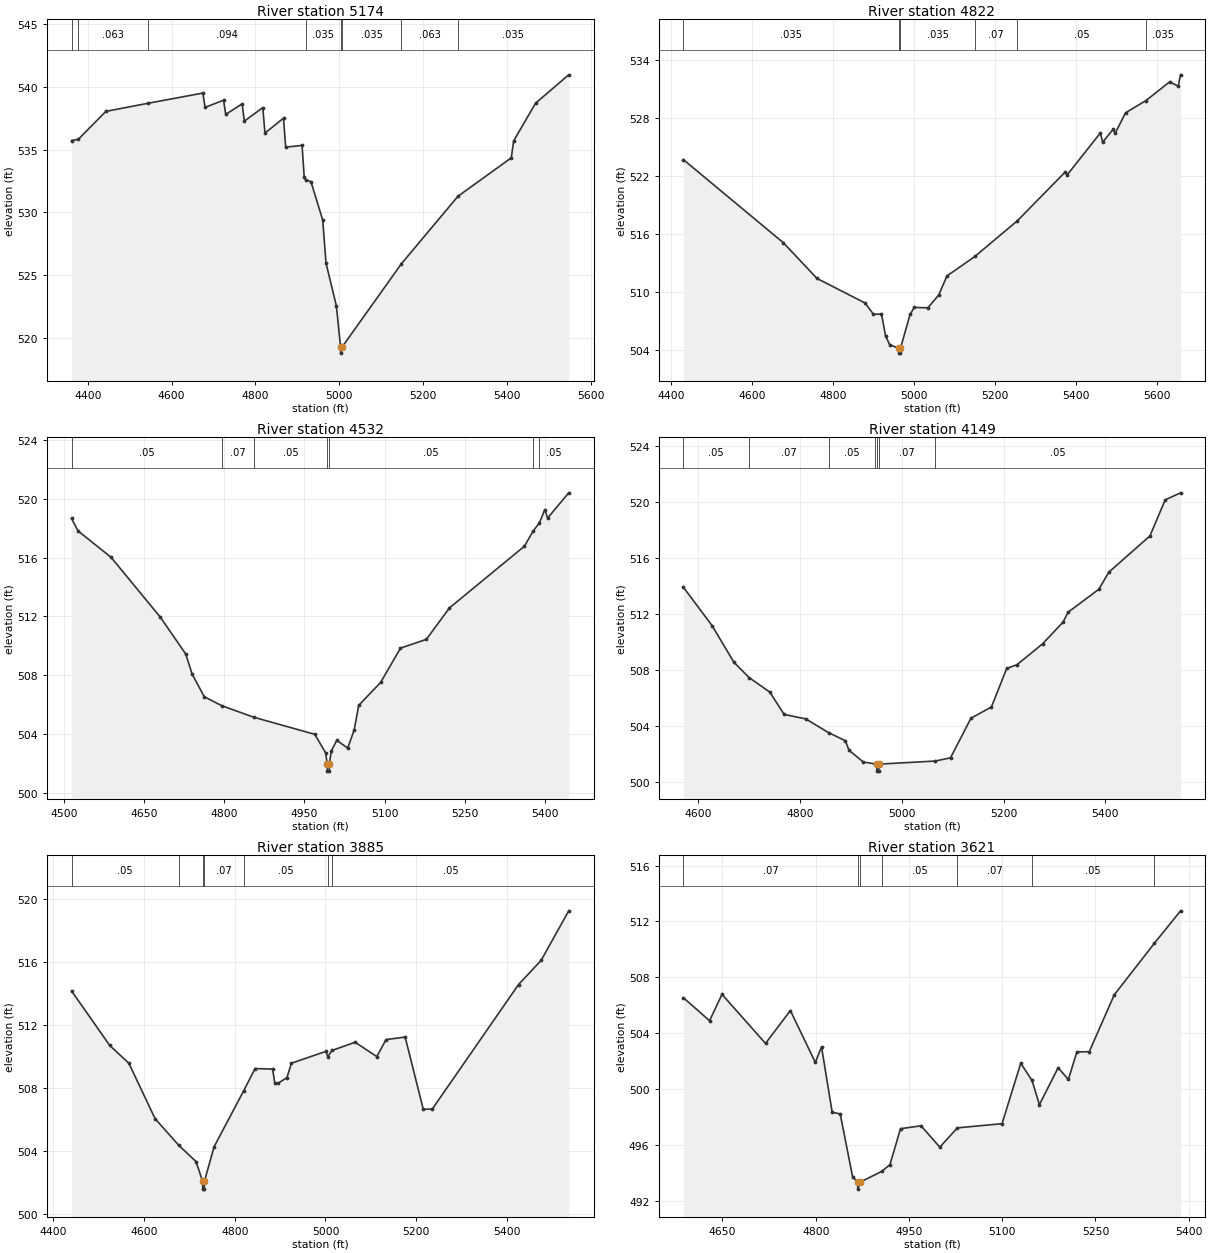
Type RM Length L Ch R = 1,5174,352,352,352
BEGIN DESCRIPTION:
RUDOLPH TRIBUTARY 1 10.0
END DESCRIPTION:
XS GIS Cut Line= 3
      2340113.64     13772946.49      2339519.69     13772818.86
      2338969.92     13772637.24
#Sta/Elev= 30
  4361.3  535.71  4377.6  535.82  4443.3  538.04  4543.2  538.68  4674.8  539.50
  4679.9  538.36  4724.2  538.93  4729.3  537.80  4768.5  538.64  4773.6  537.26
  4817.8  538.34  4822.9  536.31  4867.2  537.50  4872.3  535.19  4911.5  535.33
  4916.6  532.79  4920.0  532.59  4932.7  532.44  4960.8  529.38  4968.6  525.96
  4993.3  522.56  5003.3  519.29  5003.6  518.79  5007.3  519.29  5148.4  525.90
  5283.5  531.28  5410.8  534.34  5416.4  535.69  5468.7  538.69  5547.8  540.95
#Mann=8,-1,0
  4361.3   0.035       0  4377.6   0.063       0  4543.2   0.094       0
  4920.0   0.035       0  5003.3   0.035       0  5007.3   0.035       0
  5148.4   0.063       0  5283.5   0.035       0
Bank Sta=5003.3,5007.3
Exp/Cntr=0.3,0.1

Type RM Length L Ch R = 1,4822,290,290,290
BEGIN DESCRIPTION:
B20330
END DESCRIPTION:
XS GIS Cut Line= 3
      2340349.28     13772747.68      2339681.69     13772649.50
      2339159.49     13772465.63
#Sta/Elev= 30
  4430.4  523.65  4677.3  515.06  4760.7  511.36  4879.5  508.82  4900.1  507.65
  4919.9  507.69  4930.0  505.42  4940.1  504.51  4962.8  504.14  4963.1  503.64
  4966.6  503.64  4966.8  504.14  4990.6  507.65  5000.8  508.36  5034.6  508.33
  5061.4  509.66  5081.6  511.62  5150.8  513.64  5255.7  517.33  5373.3  522.35
  5378.6  522.07  5460.9  526.42  5466.2  525.45  5491.9  526.77  5497.2  526.37
  5522.8  528.49  5573.4  529.76  5631.8  531.69  5653.0  531.25  5658.8  532.42
#Mann=6,-1,0
  4430.4   0.035       0  4962.8   0.035       0  4966.8   0.035       0
  5150.8    0.07       0  5255.7    0.05       0  5573.4   0.035       0
Bank Sta=4962.8,4966.8
Exp/Cntr=0.3,0.1

Type RM Length L Ch R = 1,4532,383,383,383
BEGIN DESCRIPTION:
RUDOLPH TRIBUTARY 1 9.0
END DESCRIPTION:
XS GIS Cut Line= 3
      2340283.08     13772543.98      2340013.05     13772431.05
      2339392.11     13772291.16
#Sta/Elev= 30
  4514.6  518.66  4526.8  517.81  4588.4  516.02  4680.5  511.95  4728.1  509.44
  4740.1  508.07  4762.7  506.54  4795.3  505.93  4854.7  505.15  4969.3  503.98
  4989.4  502.73  4992.5  501.98  4992.8  501.48  4996.3  501.48  4996.5  501.98
  5000.1  502.85  5010.3  503.57  5030.8  503.05  5042.9  504.28  5051.3  505.95
  5092.3  507.51  5129.4  509.84  5177.8  510.44  5221.0  512.58  5361.0  516.77
  5377.5  517.81  5389.1  518.36  5399.1  519.26  5404.3  518.68  5443.8  520.40
#Mann=7,-1,0
  4514.6    0.05       0  4795.3    0.07       0  4854.7    0.05       0
  4992.5    0.05       0  4996.5    0.05       0  5377.5    0.07       0
  5389.1    0.05       0
Bank Sta=4992.5,4996.5
Exp/Cntr=0.3,0.1

Type RM Length L Ch R = 1,4149,264,264,264
BEGIN DESCRIPTION:
RUDOLPH TRIBUTARY 1 8.0
END DESCRIPTION:
XS GIS Cut Line= 3
      2340224.99     13772374.99      2339925.00     13772075.00
      2339375.02     13772025.00
#Sta/Elev= 30
  4571.2  513.89  4627.8  511.13  4670.2  508.54  4700.3  507.43  4740.9  506.40
  4769.2  504.80  4811.6  504.48  4856.4  503.50  4889.4  502.92  4896.5  502.24
  4924.7  501.40  4947.1  501.27  4951.0  501.25  4951.3  500.75  4954.8  500.75
  4955.0  501.25  5065.6  501.47  5095.9  501.70  5136.0  504.53  5176.2  505.33
  5206.3  508.09  5226.4  508.35  5276.6  509.84  5316.8  511.39  5326.8  512.10
  5387.1  513.74  5407.1  514.97  5487.5  517.55  5517.6  520.13  5547.7  520.63
#Mann=7,-1,0
  4571.2    0.05       0  4700.3    0.07       0  4856.4    0.05       0
  4947.1    0.07       0  4951.0    0.05       0  4955.0    0.07       0
  5065.6    0.05       0
Bank Sta=4951,4955
Exp/Cntr=0.3,0.1

Type RM Length L Ch R = 1,3885,264,264,264
BEGIN DESCRIPTION:
B20329
END DESCRIPTION:
XS GIS Cut Line= 4
      2340499.00     13771802.71      2340084.23     13771827.25
      2339804.42     13771851.79      2339404.31     13771854.25
#Sta/Elev= 30
  4440.0  514.18  4524.2  510.72  4566.4  509.59  4624.3  506.07  4676.5  504.38
  4714.5  503.35  4729.1  502.10  4729.4  501.60  4732.9  501.60  4733.1  502.10
  4754.6  504.30  4819.7  507.84  4844.7  509.25  4883.4  509.22  4888.4  508.32
  4894.9  508.31  4915.0  508.67  4925.0  509.59  5000.9  510.34  5005.2  510.01
  5014.4  510.40  5065.5  510.92  5113.3  510.01  5133.6  511.09  5175.8  511.25
  5215.8  506.66  5235.8  506.69  5425.8  514.58  5475.8  516.12  5536.5  519.26
#Mann=7,-1,0
  4440.0    0.05       0  4676.5    0.07       0  4729.1    0.05       0
  4733.1    0.07       0  4819.7    0.05       0  5005.2    0.07       0
  5014.4    0.05       0
Bank Sta=4729.1,4733.1
Exp/Cntr=0.3,0.1

Type RM Length L Ch R = 1,3621,346,346,346
BEGIN DESCRIPTION:
RUDOLPH TRIBUTARY 1 7.0
END DESCRIPTION:
XS GIS Cut Line= 3
      2340337.03     13771628.44      2339986.05     13771616.16
      2339538.46     13771589.26
#Sta/Elev= 30
  4587.2  506.55  4629.3  504.90  4649.3  506.79  4719.3  503.28  4759.3  505.63
  4799.4  501.92  4809.4  503.03  4826.5  498.36  4839.4  498.24  4859.4  493.73
  4867.4  493.36  4867.7  492.86  4871.4  493.36  4906.3  494.13  4919.4  494.61
  4936.4  497.18  4969.5  497.39  4999.6  495.86  5027.8  497.24  5099.7  497.54
  5129.8  501.86  5147.8  500.64  5159.8  498.90  5189.9  501.54  5206.4  500.70
  5220.0  502.67  5240.0  502.69  5280.1  506.75  5344.7  510.44  5386.8  512.76
#Mann=7,-1,0
  4587.2    0.07       0  4867.4    0.05       0  4871.4    0.07       0
  4906.3    0.05       0  5027.8    0.07       0  5147.8    0.05       0
  5344.7    0.07       0
Bank Sta=4867.4,4871.4
Exp/Cntr=0.3,0.1

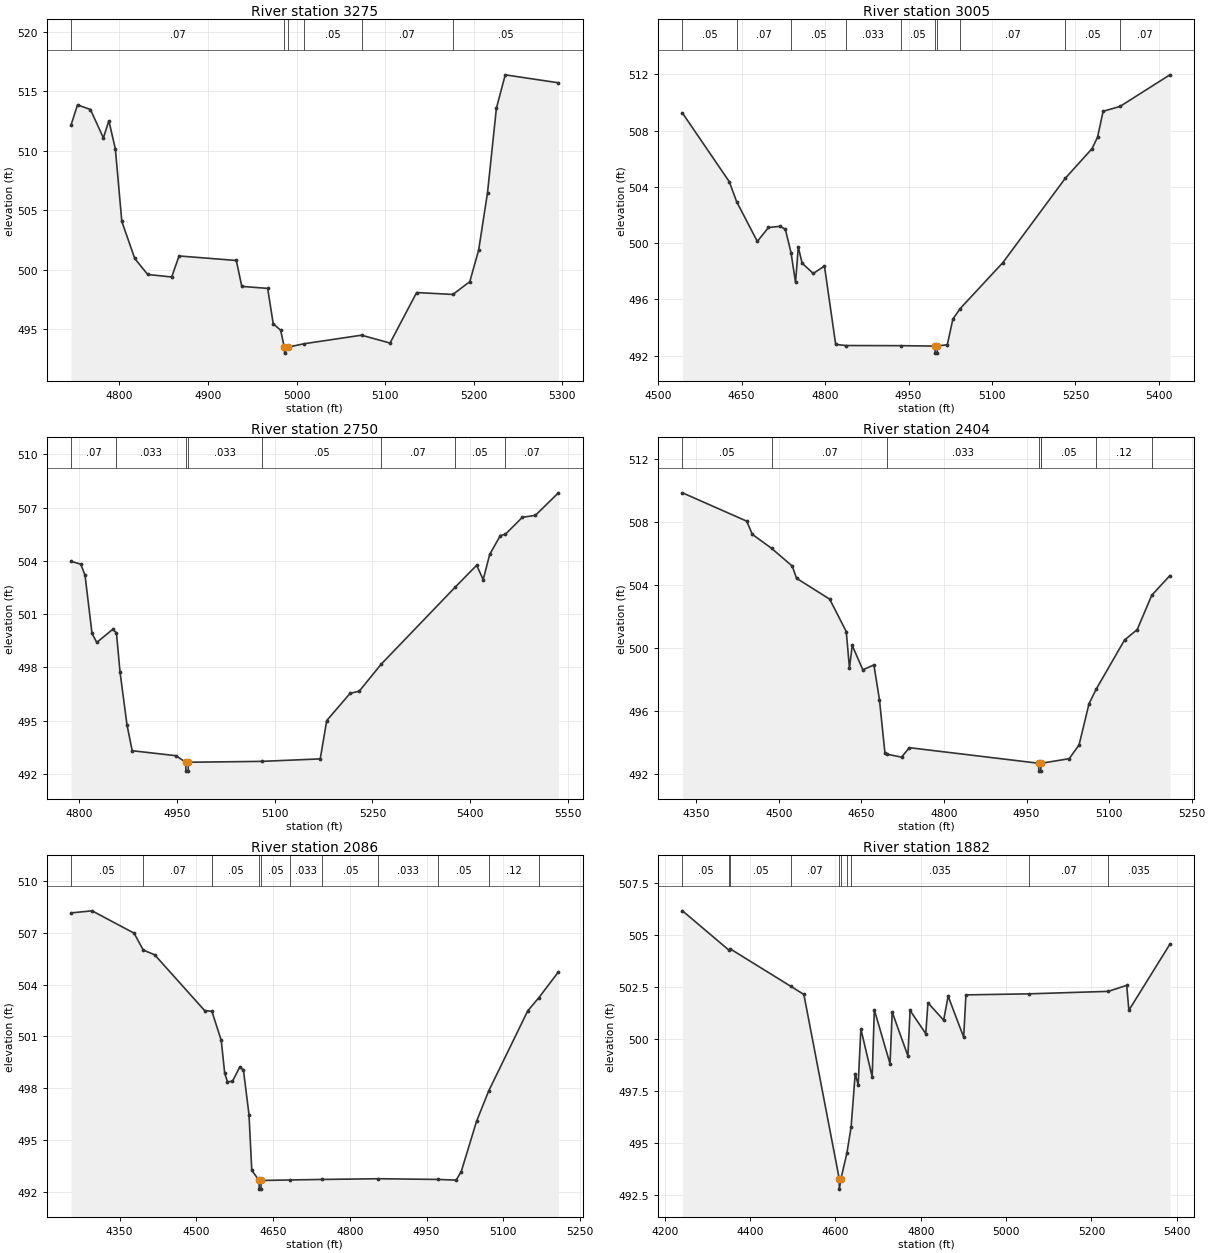
Type RM Length L Ch R = 1,3275,270,270,270
BEGIN DESCRIPTION:
RUDOLPH TRIBUTARY 1 6.0
END DESCRIPTION:
XS GIS Cut Line= 3
      2340225.02     13771525.02      2340075.00     13771325.00
      2339775.03     13771325.00
#Sta/Elev= 30
  4745.5  512.17  4752.8  513.87  4767.4  513.48  4782.0  511.09  4788.2  512.53
  4795.5  510.17  4802.8  504.06  4817.4  500.94  4832.0  499.59  4859.1  499.38
  4867.4  501.15  4932.0  500.77  4938.2  498.59  4967.4  498.42  4973.7  495.43
  4982.0  494.91  4986.2  493.47  4986.5  492.97  4990.2  493.47  5008.5  493.76
  5073.3  494.48  5105.5  493.82  5135.5  498.07  5176.4  497.91  5195.5  498.99
  5205.5  501.65  5215.5  506.48  5225.5  513.58  5235.5  516.40  5295.5  515.73
#Mann=6,-1,0
  4745.5    0.07       0  4986.2    0.05       0  4990.2    0.07       0
  5008.5    0.05       0  5073.3    0.07       0  5176.4    0.05       0
Bank Sta=4986.2,4990.2
Exp/Cntr=0.3,0.1

Type RM Length L Ch R = 1,3005,255,255,255
BEGIN DESCRIPTION:
B20328
END DESCRIPTION:
XS GIS Cut Line= 3
      2340378.75     13771152.26      2339971.32     13771108.08
      2339504.96     13771103.18
#Sta/Elev= 30
  4543.6  509.24  4627.8  504.36  4640.9  502.95  4678.1  500.12  4698.2  501.11
  4718.4  501.19  4728.4  501.00  4738.7  499.33  4746.8  497.21  4751.8  499.72
  4758.6  498.58  4778.7  497.84  4798.8  498.37  4819.0  492.80  4837.4  492.72
  4936.2  492.71  4997.7  492.68  4998.0  492.18  5001.5  492.18  5001.7  492.68
  5019.7  492.78  5029.7  494.60  5042.9  495.35  5119.7  498.62  5231.6  504.60
  5279.8  506.71  5289.8  507.53  5299.8  509.37  5330.0  509.71  5419.8  511.96
#Mann=10,-1,0
  4543.6    0.05       0  4640.9    0.07       0  4738.7    0.05       0
  4837.4   0.033       0  4936.2    0.05       0  4997.7    0.05       0
  5001.7    0.05       0  5042.9    0.07       0  5231.6    0.05       0
  5330.0    0.07       0
Bank Sta=4997.7,5001.7
Exp/Cntr=0.3,0.1

Type RM Length L Ch R = 1,2750,346,346,346
BEGIN DESCRIPTION:
RUDOLPH TRIBUTARY 1 5.0
END DESCRIPTION:
XS GIS Cut Line= 3
      2340275.04     13770975.02      2340106.32     13770909.27
      2339539.63     13770933.80
#Sta/Elev= 30
  4787.2  503.98  4802.2  503.82  4808.7  503.19  4819.4  499.92  4826.7  499.41
  4851.2  500.15  4856.9  499.95  4862.4  497.75  4873.1  494.77  4881.1  493.31
  4948.2  493.03  4963.3  492.66  4963.5  492.16  4967.0  492.16  4967.3  492.66
  5080.5  492.71  5169.8  492.85  5179.8  495.01  5215.6  496.54  5229.8  496.67
  5263.5  498.19  5376.6  502.51  5410.0  503.76  5420.0  502.95  5430.0  504.37
  5446.3  505.43  5454.2  505.51  5480.1  506.46  5500.1  506.57  5535.5  507.84
#Mann=8,-1,0
  4787.2    0.07       0  4856.9   0.033       0  4963.3   0.033       0
  4967.3   0.033       0  5080.5    0.05       0  5263.5    0.07       0
  5376.6    0.05       0  5454.2    0.07       0
Bank Sta=4963.3,4967.3
Exp/Cntr=0.3,0.1

Type RM Length L Ch R = 1,2404,318,318,318
BEGIN DESCRIPTION:
RUDOLPH TRIBUTARY 1 4.0
END DESCRIPTION:
XS GIS Cut Line= 3
      2340651.20     13770688.37      2339975.00     13770625.00
      2339775.01     13770575.00
#Sta/Elev= 30
  4325.0  509.85  4441.7  508.05  4451.8  507.21  4486.9  506.32  4524.5  505.19
  4532.1  504.42  4592.4  503.09  4622.5  501.03  4628.3  498.70  4633.3  500.15
  4652.6  498.60  4672.7  498.91  4682.8  496.69  4692.8  493.29  4697.2  493.23
  4722.9  493.05  4737.1  493.65  4972.0  492.66  4972.3  492.16  4975.8  492.16
  4976.0  492.66  4976.5  492.66  5027.4  492.95  5045.4  493.83  5063.4  496.44
  5076.6  497.38  5127.9  500.49  5151.0  501.16  5177.4  503.34  5210.3  504.59
#Mann=8,-1,0
  4325.0    0.05       0  4486.9    0.07       0  4697.2   0.033       0
  4972.0    0.05       0  4976.0   0.033       0  4976.5    0.05       0
  5076.6    0.12       0  5177.4    0.07       0
Bank Sta=4972,4976
Exp/Cntr=0.3,0.1

Type RM Length L Ch R = 1,2086,204,204,204
BEGIN DESCRIPTION:
RUDOLPH TRIBUTARY 1 3.0
END DESCRIPTION:
XS GIS Cut Line= 3
      2340675.73     13770636.81      2340062.14     13770379.10
      2339774.98     13770375.00
#Sta/Elev= 30
  4255.1  508.14  4296.2  508.26  4378.3  506.97  4396.4  505.99  4418.6  505.72
  4516.2  502.50  4530.5  502.45  4548.7  500.78  4555.5  498.87  4560.9  498.39
  4570.4  498.40  4584.6  499.22  4592.1  499.07  4603.0  496.48  4608.4  493.27
  4622.7  492.68  4622.9  492.18  4626.4  492.18  4626.7  492.68  4683.4  492.71
  4746.0  492.74  4856.1  492.78  4972.9  492.74  5007.8  492.70  5017.8  493.19
  5047.8  496.10  5071.3  497.84  5147.8  502.48  5169.8  503.25  5207.8  504.73
#Mann=11,-1,0
  4255.1    0.05       0  4396.4    0.07       0  4530.5    0.05       0
  4622.7    0.05       0  4626.7    0.05       0  4683.4   0.033       0
  4746.0    0.05       0  4856.1   0.033       0  4972.9    0.05       0
  5071.3    0.12       0  5169.8    0.07       0
Bank Sta=4622.7,4626.7
Exp/Cntr=0.3,0.1

Type RM Length L Ch R = 1,1882,146,146,146
BEGIN DESCRIPTION:
B20327
END DESCRIPTION:
XS GIS Cut Line= 3
      2340676.15     13770576.40      2340381.22     13770276.01
      2339679.62     13770106.75
#Sta/Elev= 30
  4241.3  506.17  4350.5  504.27  4353.8  504.33  4494.7  502.54  4525.9  502.14
  4608.8  493.26  4609.0  492.76  4612.8  493.26  4626.8  494.50  4636.7  495.76
  4646.2  498.32  4653.2  497.79  4659.5  500.48  4686.0  498.17  4691.1  501.40
  4727.9  498.80  4733.0  501.29  4769.8  499.18  4774.9  501.37  4811.7  500.25
  4816.8  501.74  4853.6  500.90  4864.1  502.06  4900.6  500.08  4905.8  502.12
  5053.9  502.17  5239.7  502.29  5282.8  502.58  5287.9  501.38  5384.0  504.56
#Mann=10,-1,0
  4241.3    0.05       0  4350.5    0.07       0  4353.8    0.05       0
  4494.7    0.07       0  4608.8   0.035       0  4612.8    0.07       0
  4626.8    0.05       0  4636.7   0.035       0  5053.9    0.07       0
  5239.7   0.035       0
Bank Sta=4608.8,4612.8
Exp/Cntr=0.3,0.1

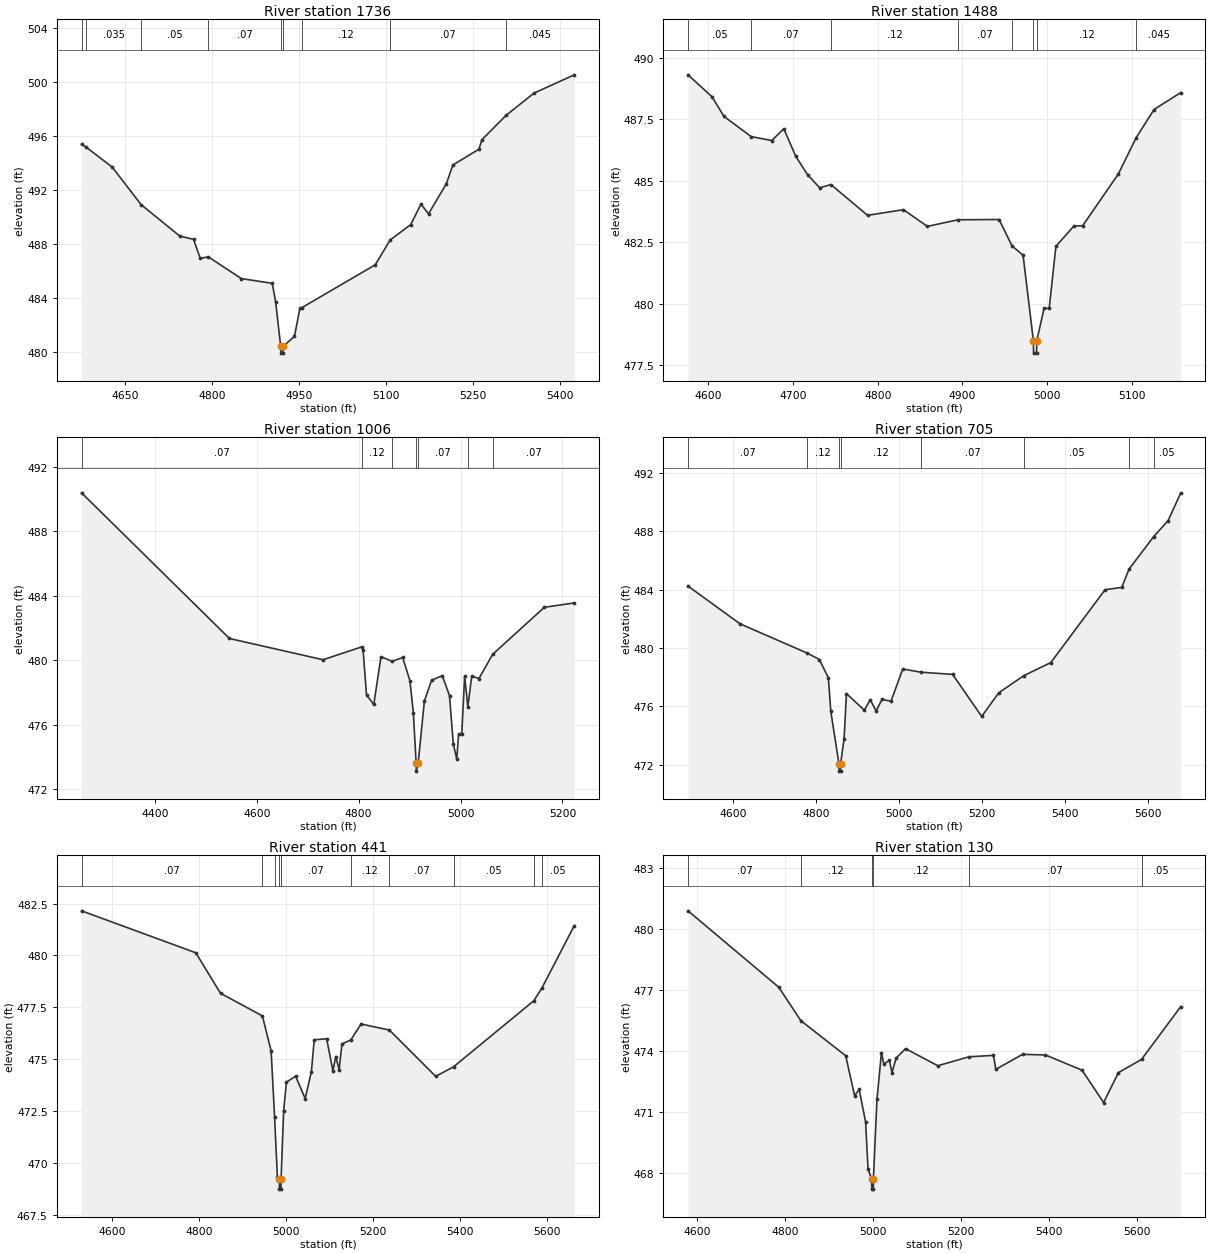
Type RM Length L Ch R = 1,1736,248,248,248
BEGIN DESCRIPTION:
B20326
END DESCRIPTION:
XS GIS Cut Line= 3
      2340513.91     13770235.72      2340070.50     13770051.87
      2339709.12     13769976.36
#Sta/Elev= 30
  4575.1  495.41  4583.1  495.18  4628.0  493.70  4677.7  490.92  4744.2  488.59
  4768.1  488.34  4779.6  486.94  4793.7  487.04  4850.5  485.43  4903.7  485.08
  4909.5  483.73  4918.3  480.40  4918.6  479.90  4922.1  479.90  4922.3  480.40
  4942.0  481.14  4951.5  483.25  4954.2  483.26  5081.2  486.45  5107.0  488.30
  5142.5  489.44  5159.9  490.95  5173.1  490.24  5203.8  492.47  5215.0  493.86
  5259.9  495.03  5265.1  495.74  5306.9  497.55  5354.7  499.19  5424.3  500.55
#Mann=9,-1,0
  4575.1    0.05       0  4583.1   0.035       0  4677.7    0.05       0
  4793.7    0.07       0  4918.3    0.05       0  4922.3    0.07       0
  4954.2    0.12       0  5107.0    0.07       0  5306.9   0.045       0
Bank Sta=4918.3,4922.3
Exp/Cntr=0.3,0.1

Type RM Length L Ch R = 1,1488,482,482,482
BEGIN DESCRIPTION:
RUDOLPH TRIBUTARY 1 2.0
END DESCRIPTION:
XS GIS Cut Line= 3
      2340425.03     13770125.03      2340125.00     13769825.00
      2339975.02     13769874.99
#Sta/Elev= 30
  4575.8  489.30  4604.1  488.41  4618.3  487.61  4650.4  486.79  4674.8  486.63
  4689.0  487.11  4703.1  485.99  4717.3  485.23  4731.4  484.71  4744.7  484.84
  4788.0  483.59  4830.4  483.82  4858.7  483.14  4894.9  483.41  4943.5  483.42
  4958.7  482.35  4971.8  481.97  4984.0  478.49  4984.2  477.99  4987.7  477.99
  4988.0  478.49  4996.6  479.81  5002.7  479.81  5010.6  482.33  5031.7  483.15
  5042.3  483.17  5084.4  485.27  5105.4  486.74  5126.6  487.89  5158.2  488.58
#Mann=8,-1,0
  4575.8    0.05       0  4650.4    0.07       0  4744.7    0.12       0
  4894.9    0.07       0  4958.7    0.12       0  4984.0    0.05       0
  4988.0    0.12       0  5105.4   0.045       0
Bank Sta=4984,4988
Exp/Cntr=0.3,0.1

Type RM Length L Ch R = 1,1006,301,301,301
BEGIN DESCRIPTION:
RUDOLPH TRIBUTARY 1 1.0
END DESCRIPTION:
XS GIS Cut Line= 3
      2340625.01     13769925.01      2340125.00     13769375.00
      2339925.02     13769474.99
#Sta/Elev= 30
  4256.3  490.40  4546.5  481.35  4730.3  480.03  4806.1  480.83  4808.7  480.63
  4815.5  477.84  4829.7  477.25  4843.9  480.22  4865.8  479.93  4886.4  480.17
  4900.6  478.73  4907.4  476.73  4912.8  473.61  4913.1  473.11  4916.8  473.61
  4929.0  477.46  4943.2  478.76  4964.1  479.04  4978.3  477.80  4985.8  474.79
  4992.5  473.86  4996.2  475.43  5002.4  475.43  5008.0  479.03  5014.3  477.11
  5022.0  479.02  5036.0  478.86  5063.1  480.37  5164.5  483.29  5223.2  483.56
#Mann=7,-1,0
  4256.3    0.07       0  4806.1    0.12       0  4865.8    0.07       0
  4912.8    0.05       0  4916.8    0.07       0  5014.3    0.12       0
  5063.1    0.07       0
Bank Sta=4912.8,4916.8
Exp/Cntr=0.3,0.1

Type RM Length L Ch R = 1,705,264,264,264
BEGIN DESCRIPTION:
B20325
END DESCRIPTION:
XS GIS Cut Line= 4
      2340594.72     13769694.86      2340397.85     13769338.52
      2340159.62     13769123.91      2339704.81     13769047.13
#Sta/Elev= 30
  4491.0  484.25  4616.5  481.66  4778.6  479.65  4808.0  479.21  4829.7  477.95
  4835.5  475.66  4855.2  472.05  4855.5  471.55  4859.0  471.55  4859.2  472.05
  4867.6  473.78  4873.3  476.87  4916.5  475.73  4930.7  476.45  4944.9  475.68
  4959.1  476.47  4980.8  476.35  5009.2  478.56  5052.9  478.34  5129.5  478.19
  5199.7  475.30  5240.5  476.92  5301.1  478.10  5366.4  479.00  5497.3  484.00
  5537.7  484.16  5554.9  485.40  5614.4  487.64  5649.4  488.74  5680.0  490.65
#Mann=8,-1,0
  4491.0    0.07       0  4778.6    0.12       0  4855.2    0.05       0
  4859.2    0.12       0  5052.9    0.07       0  5301.1    0.05       0
  5554.9    0.07       0  5614.4    0.05       0
Bank Sta=4855.2,4859.2
Exp/Cntr=0.3,0.1

Type RM Length L Ch R = 1,441,311,311,311
BEGIN DESCRIPTION:
B20324
END DESCRIPTION:
XS GIS Cut Line= 4
      2340582.92     13769537.39      2340594.73     13769216.45
      2340391.94     13768972.31      2339943.09     13768765.60
#Sta/Elev= 30
  4529.4  482.15  4792.0  480.13  4848.8  478.18  4945.1  477.09  4965.2  475.40
  4973.1  472.23  4979.6  469.32  4984.1  469.25  4984.3  468.75  4987.8  468.75
  4988.1  469.25  4993.9  472.51  5000.4  473.90  5021.4  474.19  5043.4  473.11
  5057.7  474.40  5064.2  475.94  5092.8  475.99  5107.2  474.45  5113.7  475.13
  5121.5  474.51  5128.0  475.74  5148.7  475.94  5171.8  476.70  5237.0  476.41
  5343.5  474.18  5384.6  474.64  5569.0  477.82  5587.8  478.44  5662.1  481.44
#Mann=10,-1,0
  4529.4    0.07       0  4945.1    0.12       0  4973.1    0.07       0
  4984.1    0.05       0  4988.1    0.07       0  5148.7    0.12       0
  5237.0    0.07       0  5384.6    0.05       0  5569.0    0.07       0
  5587.8    0.05       0
Bank Sta=4984.1,4988.1
Exp/Cntr=0.3,0.1

Type RM Length L Ch R = 1,130,0,0,0
BEGIN DESCRIPTION:
B20323
END DESCRIPTION:
XS GIS Cut Line= 4
      2340610.48     13769348.38      2340687.27     13768909.31
      2340614.42     13768791.18      2340099.28     13768641.75
#Sta/Elev= 30
  4579.3  480.88  4785.8  477.12  4835.8  475.48  4938.0  473.75  4958.3  471.78
  4968.5  472.10  4983.3  470.49  4988.8  468.17  4997.0  467.69  4997.2  467.19
  5000.7  467.19  5001.0  467.69  5009.1  471.60  5019.3  473.90  5024.7  473.34
  5037.4  473.52  5043.3  472.92  5052.8  473.64  5074.1  474.10  5147.5  473.26
  5218.5  473.70  5274.1  473.77  5279.4  473.08  5340.2  473.82  5392.3  473.79
  5475.6  473.04  5524.7  471.45  5558.3  472.92  5610.9  473.57  5700.2  476.17
#Mann=6,-1,0
  4579.3    0.07       0  4835.8    0.12       0  4997.0    0.05       0
  5001.0    0.12       0  5218.5    0.07       0  5610.9    0.05       0
Bank Sta=4997,5001
Exp/Cntr=0.3,0.1

Chan Stop Cuts=-1