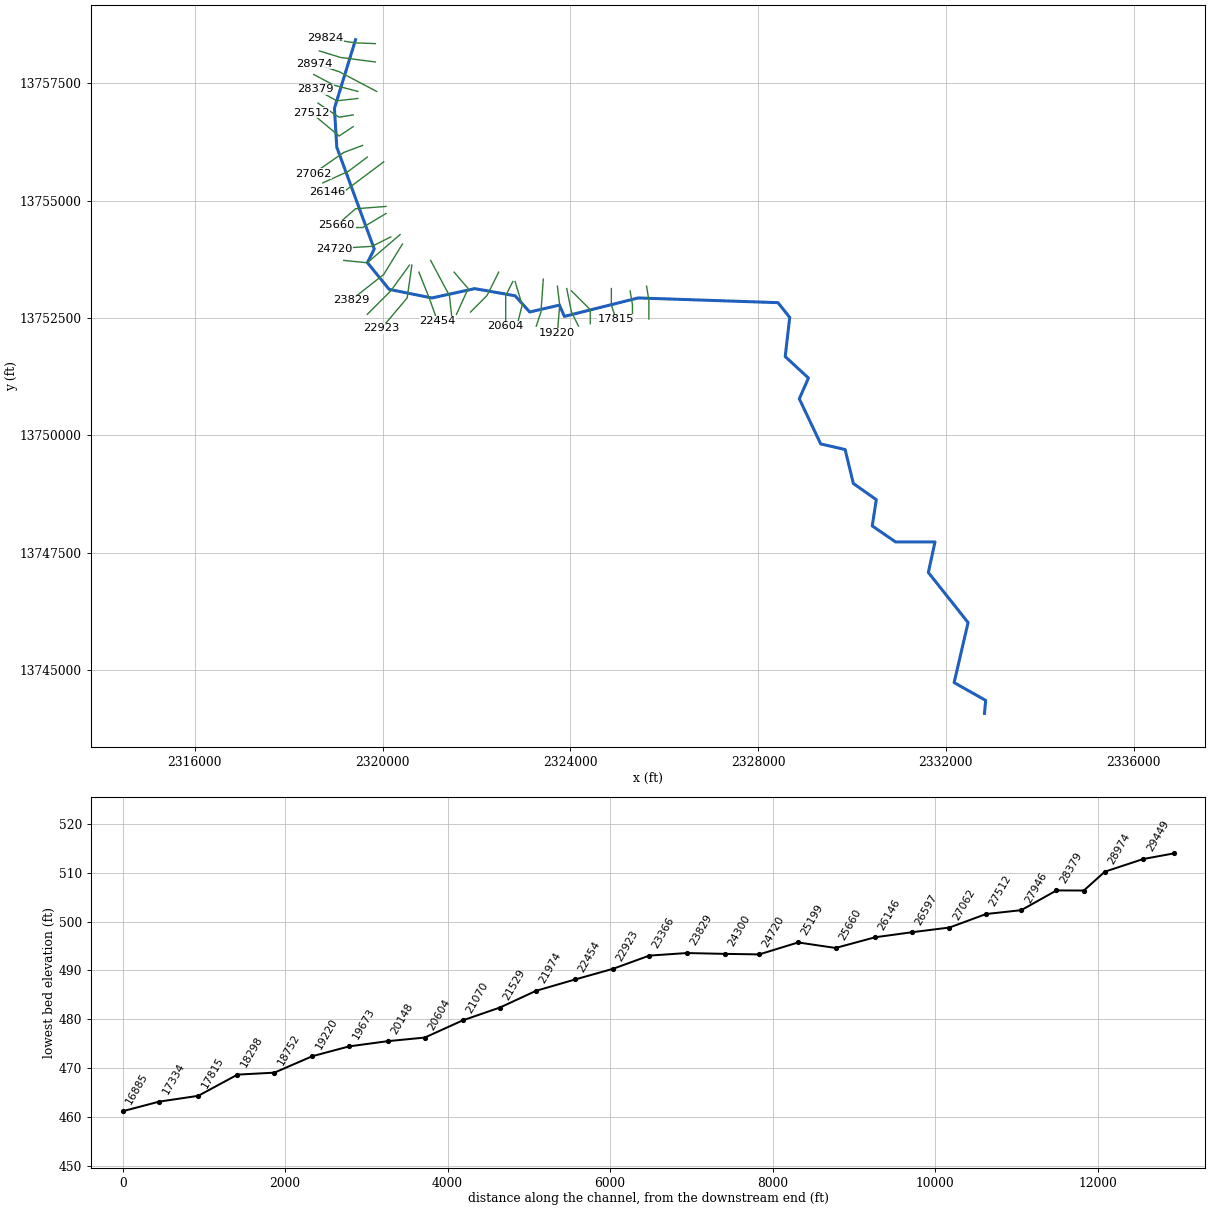
--- SAUL CREEK.prj (project) ---

Proj Title=SAUL CREEK Base Level Engineering
Current Plan=p01
Default Exp/Contr=0.3,0.1
English Units
Geom File=g01
Flow File=f01
Plan File=p01
Y Axis Title=Elevation
X Axis Title(PF)=Main Channel Distance
X Axis Title(XS)=Station
BEGIN DESCRIPTION:
SAUL CREEK
END DESCRIPTION:
DSS Export Rating Curves= 0
DSS Export Rating Curve Sorted= 0
DSS Export Volume Flow Curves= 0
DXF OffsetX= 0
DXF OffsetY= 0
DXF ScaleX= 1
DXF ScaleY= 10

--- SAUL CREEK.p01 (plan) ---

Plan Title=Multiple Run
Short Identifier=Multiple
Geom File=g01
Flow File=f01
Subcritical Flow
K Sum by GR= 0
Std Step Tol= 0.01
Critical Tol= 0.01
Num of Std Step Trials= 20
Max Error Tol= 0.3
Flow Tol Ratio= 0.001
Split Flow NTrial= 30
Split Flow Tol= 0.02
Split Flow Ratio= 0.02
Log Output Level= 0
Friction Slope Method= 1
Unsteady Friction Slope Method= 2
Unsteady Bridges Friction Slope Method= 1
Parabolic Critical Depth
Global Vel Dist=  1 , 1 , 1
Global Log Level= 0
CheckData=True
Encroach Param= -1, 0, 0, 0
BEGIN DESCRIPTION:
Multiple Run
END DESCRIPTION:

--- SAUL CREEK.f01 (steady flow) ---

Flow Title=Multiple
Number of Profiles=7
Profile Names=10-year,25-year,50-year,1pct_min,100-year,1pct_plu,500-year
River Rch & RM= SAUL CREEK,Reach-1,29824
     368     569     742     469     936    1868    1476
River Rch & RM= SAUL CREEK,Reach-1,27062
     852    1381    1859    1209    2413    4815    4031
River Rch & RM= SAUL CREEK,Reach-1,17815
    1150    1898    2586    1702    3395    6774    5803
River Rch & RM= SAUL CREEK,Reach-1,13642
    1858    3141    4351    2906    5798   11569   10215
River Rch & RM= SAUL CREEK,Reach-1,5964
    2222    3787    5273    3539    7060   14087   12558
Boundary for River Rch & Prof#=SAUL CREEK,Reach-1,1
Up Type=0
Dn Type=3
Dn Slope=0.005
Boundary for River Rch & Prof#=SAUL CREEK,Reach-1,2
Up Type=0
Dn Type=3
Dn Slope=0.005
Boundary for River Rch & Prof#=SAUL CREEK,Reach-1,3
Up Type=0
Dn Type=3
Dn Slope=0.005
Boundary for River Rch & Prof#=SAUL CREEK,Reach-1,4
Up Type=0
Dn Type=3
Dn Slope=0.005
Boundary for River Rch & Prof#=SAUL CREEK,Reach-1,5
Up Type=0
Dn Type=3
Dn Slope=0.005
Boundary for River Rch & Prof#=SAUL CREEK,Reach-1,6
Up Type=0
Dn Type=3
Dn Slope=0.005
Boundary for River Rch & Prof#=SAUL CREEK,Reach-1,7
Up Type=0
Dn Type=3
Dn Slope=0.005

--- SAUL CREEK.g01 (geometry) ---

Geom Title=Existing Conditions

River Reach=SAUL CREEK,Reach-1
Reach XY= 30
      2319425.00     13758425.00      2318975.61     13756964.38
      2319025.95     13756135.41      2319823.42     13753968.95
      2319678.34     13753676.72      2320141.40     13753108.25
      2321050.00     13752924.60      2321964.49     13753123.80
      2322823.75     13752971.55      2323135.29     13752626.00
      2323769.31     13752773.13      2323874.75     13752531.98
      2325444.89     13752925.11      2328425.00     13752825.00
      2328674.64     13752509.82      2328578.82     13751676.58
      2329073.51     13751219.15      2328878.75     13750776.55
      2329335.17     13749815.32      2329855.24     13749695.63
      2330030.40     13748972.57      2330519.59     13748627.71
      2330433.00     13748068.67      2330931.05     13747726.67
      2331769.66     13747727.74      2331628.09     13747076.65
      2332474.76     13746009.79      2332176.96     13744730.66
      2332848.86     13744351.93      2332825.00     13744075.00

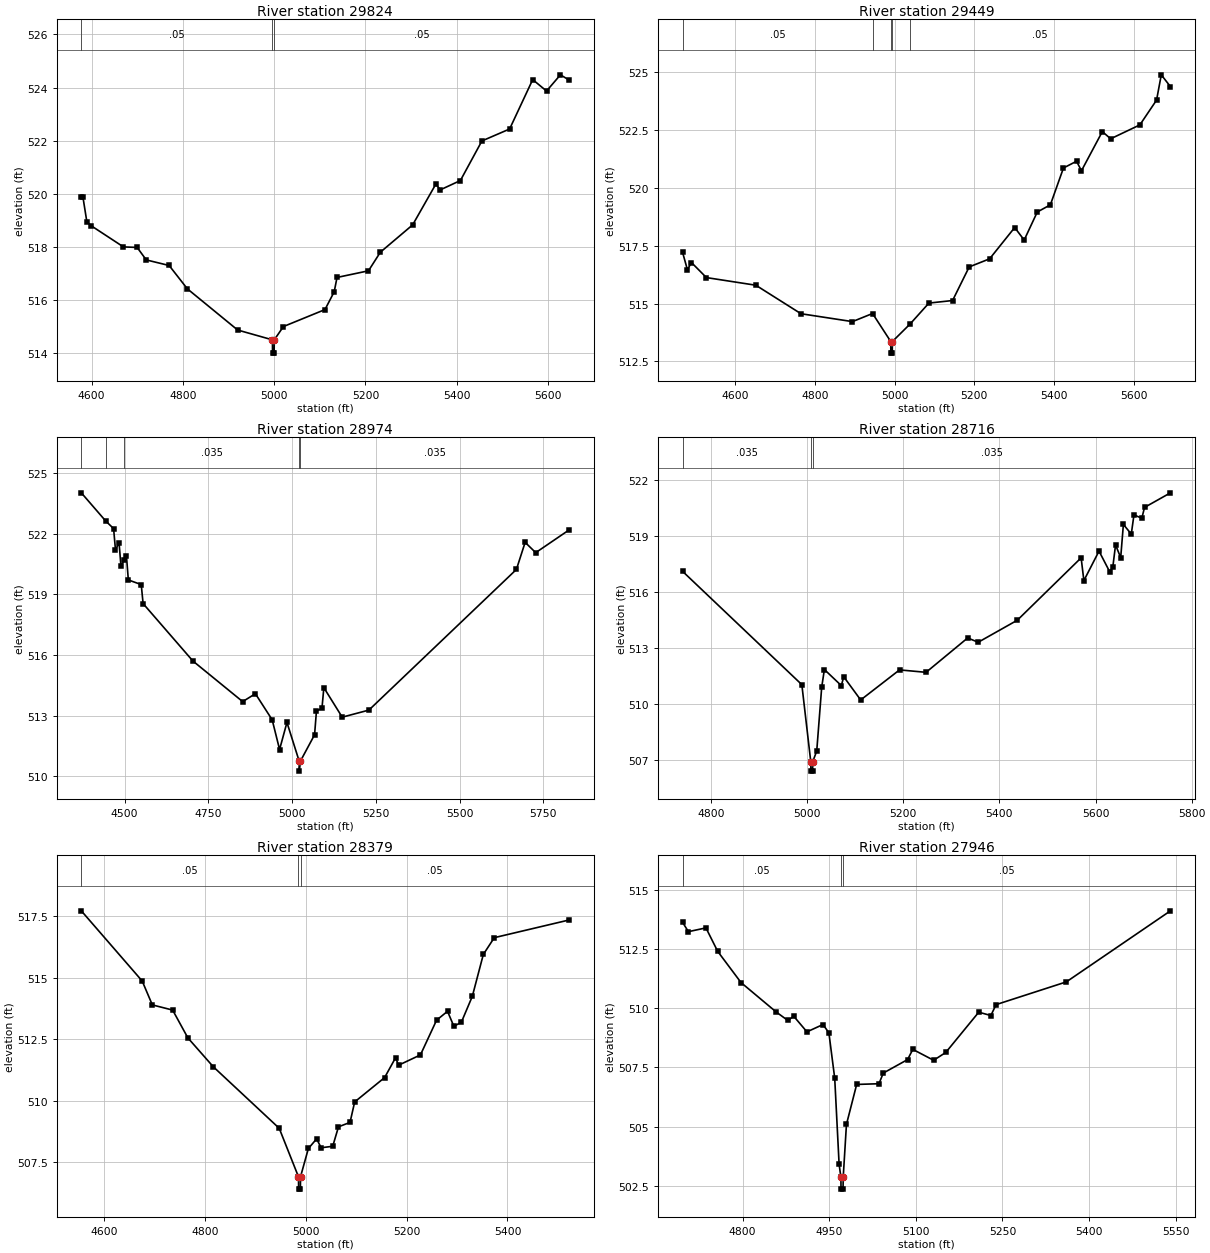
Type RM Length L Ch R = 1,29824,375,375,375
BEGIN DESCRIPTION:
SAUL CREEK 65.0
END DESCRIPTION:
XS GIS Cut Line= 3
      2319847.22     13758343.33      2319423.73     13758359.42
      2318785.78     13758455.91
#Sta/Elev= 30
  4577.5  519.87  4581.1  519.87  4589.7  518.94  4599.7  518.79  4669.8  518.00
  4699.8  517.98  4719.8  517.51  4769.9  517.30  4809.9  516.42  4920.0  514.87
  4996.2  514.50  4996.4  514.00  4999.9  514.00  5000.2  514.50  5020.2  515.00
  5111.3  515.64  5131.5  516.31  5137.7  516.85  5206.6  517.10  5232.6  517.80
  5303.4  518.83  5354.0  520.36  5364.1  520.15  5408.0  520.50  5455.1  521.99
  5515.8  522.44  5566.4  524.30  5596.7  523.87  5627.1  524.48  5646.5  524.28
#Mann=3,-1,0
  4577.5    0.05       0  4996.2    0.05       0  5000.2    0.05       0
Bank Sta=4996.2,5000.2
Exp/Cntr=0.3,0.1

Type RM Length L Ch R = 1,29449,475,475,475
BEGIN DESCRIPTION:
E20755
END DESCRIPTION:
XS GIS Cut Line= 3
      2319847.23     13757951.97      2319107.43     13758048.47
      2318651.74     13758187.86
#Sta/Elev= 30
  4468.8  517.22  4481.1  516.46  4491.2  516.77  4528.7  516.12  4652.6  515.79
  4765.7  514.56  4894.6  514.22  4945.0  514.57  4990.6  513.36  4990.8  512.86
  4994.3  512.86  4994.6  513.36  5039.2  514.12  5086.2  515.02  5145.5  515.13
  5187.1  516.58  5238.3  516.93  5301.1  518.28  5324.9  517.74  5357.7  518.95
  5390.5  519.26  5423.3  520.85  5456.1  521.14  5468.4  520.73  5520.7  522.42
  5541.6  522.11  5614.8  522.71  5656.6  523.78  5668.4  524.87  5691.4  524.36
#Mann=5,-1,0
  4468.8    0.05       0  4945.0    0.07       0  4990.6    0.07       0
  4994.6    0.07       0  5039.2    0.05       0
Bank Sta=4990.6,4994.6
Exp/Cntr=0.3,0.1

Type RM Length L Ch R = 1,28974,258,258,258
BEGIN DESCRIPTION:
SAUL CREEK 64.0
END DESCRIPTION:
XS GIS Cut Line= 3
      2319875.01     13757325.00      2319080.62     13757742.88
      2318549.92     13757919.78
#Sta/Elev= 30
  4370.6  524.02  4443.2  522.63  4467.0  522.25  4472.6  521.20  4483.3  521.55
  4489.0  520.39  4498.7  520.69  4505.4  520.89  4511.0  519.71  4549.5  519.48
  4555.1  518.54  4703.7  515.70  4852.4  513.69  4890.4  514.08  4940.5  512.79
  4962.6  511.32  4984.6  512.66  5021.0  510.75  5021.3  510.25  5025.0  510.75
  5067.1  512.05  5072.7  513.23  5089.1  513.35  5094.8  514.38  5149.6  512.92
  5229.3  513.27  5669.8  520.23  5695.8  521.57  5727.4  521.06  5827.6  522.19
#Mann=5,-1,0
  4370.6   0.035       0  4443.2   0.063       0  4498.7   0.035       0
  5021.0   0.035       0  5025.0   0.035       0
Bank Sta=5021,5025
Exp/Cntr=0.3,0.1

Type RM Length L Ch R = 1,28716,337,337,337
BEGIN DESCRIPTION:
SAUL CREEK 63.0
END DESCRIPTION:
XS GIS Cut Line= 3
      2319475.03     13757324.99      2318957.31     13757460.89
      2318533.80     13757686.05
#Sta/Elev= 30
  4741.0  517.09  4989.2  511.02  5007.8  506.89  5008.1  506.39  5011.6  506.39
  5011.8  506.89  5020.2  507.47  5030.5  510.88  5036.1  511.83  5071.3  510.97
  5076.4  511.44  5111.6  510.20  5192.4  511.81  5247.6  511.68  5334.1  513.52
  5356.0  513.29  5437.4  514.47  5570.1  517.81  5575.8  516.59  5607.3  518.17
  5630.0  517.04  5636.1  517.34  5641.7  518.50  5652.4  517.82  5658.0  519.60
  5674.4  519.08  5680.0  520.11  5696.3  519.93  5702.0  520.51  5755.9  521.29
#Mann=3,-1,0
  4741.0   0.035       0  5007.8   0.035       0  5011.8   0.035       0
Bank Sta=5007.8,5011.8
Exp/Cntr=0.3,0.1

Type RM Length L Ch R = 1,28379,433,433,433
BEGIN DESCRIPTION:
SAUL CREEK 62.0
END DESCRIPTION:
XS GIS Cut Line= 3
      2319474.96     13757175.00      2319025.00     13757125.00
      2318575.01     13757374.99
#Sta/Elev= 30
  4555.0  517.71  4675.7  514.86  4695.8  513.89  4736.1  513.68  4766.3  512.55
  4816.6  511.38  4947.4  508.88  4985.6  506.91  4985.9  506.41  4989.4  506.41
  4989.6  506.91  5005.2  508.06  5021.5  508.45  5030.6  508.09  5053.5  508.15
  5064.9  508.94  5087.8  509.12  5097.0  509.95  5156.4  510.94  5178.2  511.75
  5183.9  511.44  5227.4  511.86  5259.4  513.27  5281.1  513.63  5293.7  513.02
  5308.6  513.19  5330.3  514.24  5352.1  515.94  5373.8  516.62  5522.5  517.34
#Mann=3,-1,0
  4555.0    0.05       0  4985.6    0.05       0  4989.6    0.05       0
Bank Sta=4985.6,4989.6
Exp/Cntr=0.3,0.1

Type RM Length L Ch R = 1,27946,434,434,434
BEGIN DESCRIPTION:
SAUL CREEK 61.0
END DESCRIPTION:
XS GIS Cut Line= 3
      2319375.03     13756825.00      2319075.00     13756775.00
      2318625.00     13757075.00
#Sta/Elev= 30
  4695.9  513.63  4706.1  513.23  4736.5  513.39  4756.8  512.40  4797.3  511.08
  4858.1  509.84  4878.4  509.48  4888.5  509.66  4911.4  509.00  4939.2  509.31
  4949.4  508.96  4959.5  507.04  4967.1  503.41  4970.2  502.86  4970.4  502.36
  4973.9  502.36  4974.2  502.86  4979.8  505.09  4997.5  506.78  5036.1  506.81
  5043.6  507.26  5085.7  507.83  5094.7  508.26  5130.8  507.80  5151.8  508.13
  5208.9  509.83  5229.9  509.69  5238.9  510.15  5360.6  511.11  5540.9  514.11
#Mann=3,-1,0
  4695.9    0.05       0  4970.2    0.05       0  4974.2    0.05       0
Bank Sta=4970.2,4974.2
Exp/Cntr=0.3,0.1

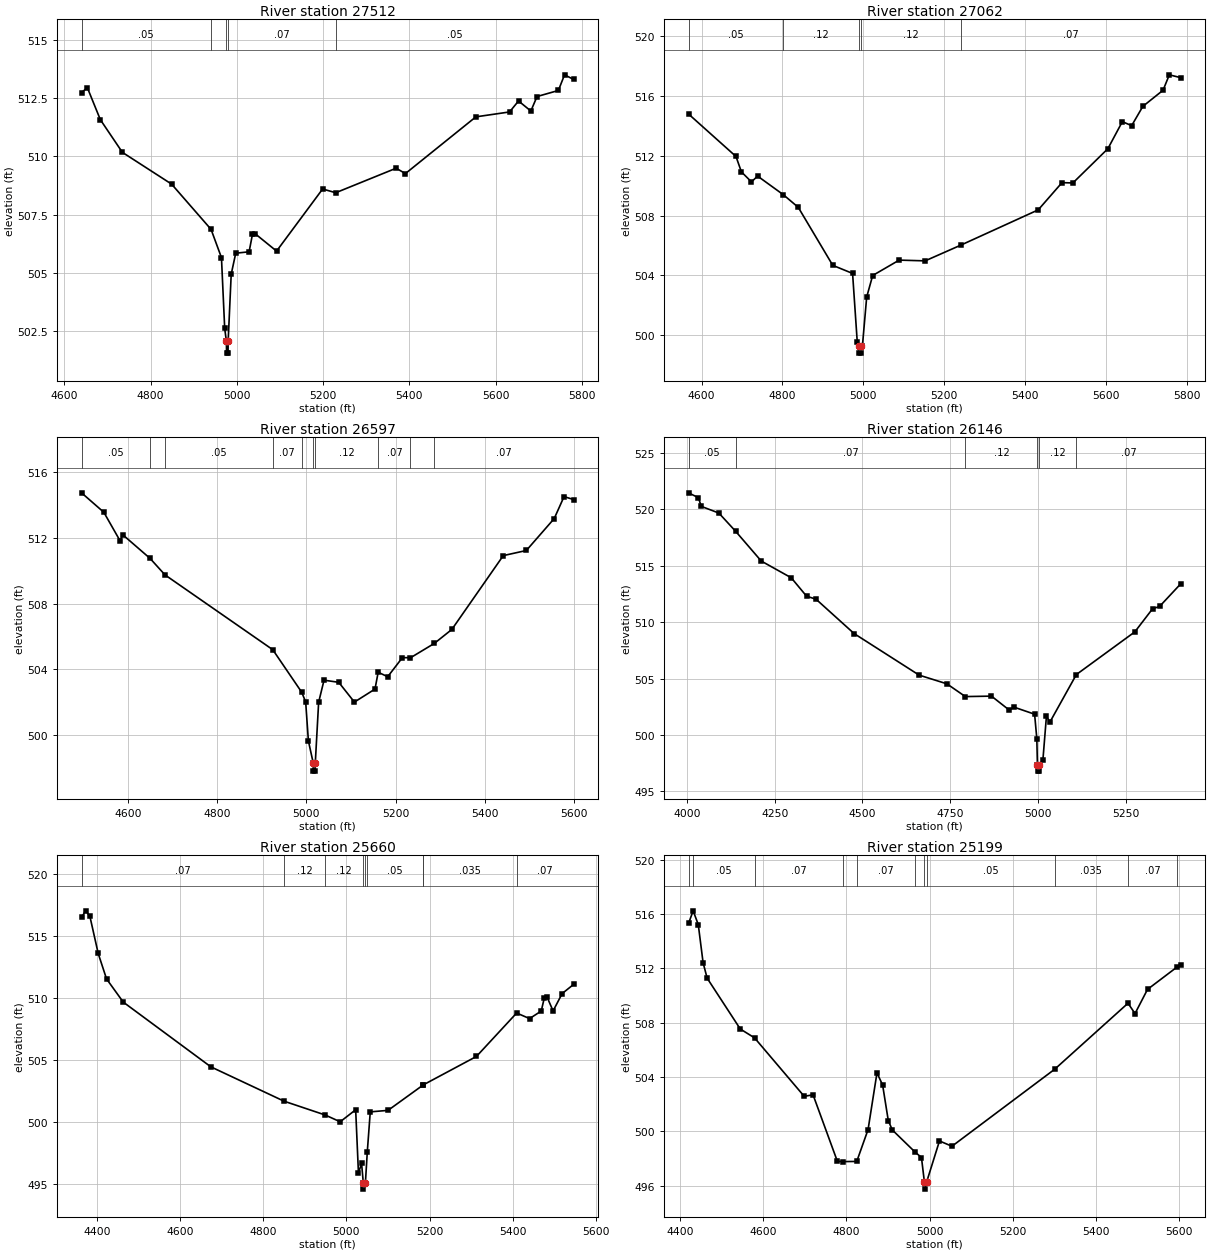
Type RM Length L Ch R = 1,27512,450,450,450
BEGIN DESCRIPTION:
SAUL CREEK 60.0
END DESCRIPTION:
XS GIS Cut Line= 3
      2319375.02     13756575.01      2319075.00     13756375.00
      2318475.00     13756875.00
#Sta/Elev= 30
  4639.9  512.73  4653.4  512.94  4683.5  511.57  4734.6  510.17  4848.7  508.81
  4940.3  506.87  4964.4  505.66  4971.9  502.63  4975.9  502.07  4976.2  501.57
  4979.7  501.57  4979.9  502.07  4987.0  504.95  4997.5  505.85  5028.5  505.91
  5036.3  506.66  5042.8  506.68  5092.2  505.94  5199.0  508.60  5229.4  508.44
  5369.5  509.49  5391.0  509.26  5554.4  511.69  5632.5  511.90  5653.3  512.37
  5681.9  511.94  5696.2  512.56  5745.7  512.82  5760.0  513.49  5781.5  513.29
#Mann=5,-1,0
  4639.9    0.05       0  4940.3    0.07       0  4975.9    0.07       0
  4979.9    0.07       0  5229.4    0.05       0
Bank Sta=4975.9,4979.9
Exp/Cntr=0.3,0.1

Type RM Length L Ch R = 1,27062,465,465,465
BEGIN DESCRIPTION:
SAUL CREEK 59.0
END DESCRIPTION:
XS GIS Cut Line= 3
      2319574.96     13756174.98      2319175.00     13756025.00
      2318525.02     13755575.01
#Sta/Elev= 30
  4567.9  514.79  4685.3  511.95  4698.7  510.92  4723.6  510.25  4738.7  510.64
  4802.1  509.40  4839.3  508.55  4924.7  504.67  4973.7  504.13  4985.3  499.53
  4990.0  499.30  4990.4  498.80  4994.4  498.80  4994.7  499.30  4998.1  499.30
  5008.6  502.55  5023.4  503.99  5089.0  505.02  5153.2  504.97  5241.3  506.02
  5432.9  508.38  5491.7  510.20  5518.7  510.18  5605.2  512.47  5641.0  514.28
  5664.0  514.01  5691.7  515.30  5741.7  516.38  5757.2  517.41  5785.6  517.22
#Mann=5,-1,0
  4567.9    0.05       0  4802.1    0.12       0  4990.0    0.07       0
  4994.7    0.12       0  5241.3    0.07       0
Bank Sta=4990,4994.7
Exp/Cntr=0.3,0.1

Type RM Length L Ch R = 1,26597,451,451,451
BEGIN DESCRIPTION:
SAUL CREEK 58.0
END DESCRIPTION:
XS GIS Cut Line= 3
      2319674.98     13755924.98      2319275.00     13755625.00
      2318725.02     13755375.01
#Sta/Elev= 30
  4495.8  514.72  4545.8  513.54  4582.2  511.81  4588.5  512.17  4649.5  510.74
  4683.0  509.74  4924.7  505.20  4989.6  502.62  4998.5  502.03  5004.6  499.67
  5015.4  498.33  5015.7  497.83  5019.8  497.83  5020.1  498.33  5027.6  502.01
  5039.7  503.35  5072.7  503.22  5107.8  502.02  5154.0  502.81  5161.1  503.83
  5182.5  503.56  5215.5  504.72  5233.6  504.71  5287.0  505.58  5326.4  506.43
  5441.7  510.91  5493.4  511.22  5556.0  513.16  5578.0  514.49  5599.9  514.31
#Mann=10,-1,0
  4495.8    0.05       0  4649.5    0.07       0  4683.0    0.05       0
  4924.7    0.07       0  4989.6    0.12       0  5015.4    0.07       0
  5020.1    0.12       0  5161.1    0.07       0  5233.6    0.12       0
  5287.0    0.07       0
Bank Sta=5015.4,5020.1
Exp/Cntr=0.3,0.1

Type RM Length L Ch R = 1,26146,486,486,486
BEGIN DESCRIPTION:
SAUL CREEK 57.0
END DESCRIPTION:
XS GIS Cut Line= 3
      2320024.98     13755824.99      2319225.00     13755225.00
      2318824.99     13755175.00
#Sta/Elev= 30
  4004.4  521.44  4032.5  521.01  4040.8  520.24  4090.8  519.65  4138.5  518.04
  4211.7  515.40  4297.1  513.92  4340.8  512.29  4367.9  512.02  4476.3  508.98
  4661.7  505.30  4740.8  504.53  4793.4  503.40  4867.9  503.44  4917.9  502.22
  4932.5  502.46  4990.8  501.84  4997.1  499.68  4998.9  497.30  4999.2  496.80
  5003.3  496.80  5003.7  497.30  5014.5  497.81  5024.5  501.65  5034.6  501.15
  5109.8  505.35  5276.5  509.13  5326.9  511.17  5347.0  511.38  5407.5  513.39
#Mann=6,-1,0
  4004.4    0.05       0  4138.5    0.07       0  4793.4    0.12       0
  4998.9    0.07       0  5003.7    0.12       0  5109.8    0.07       0
Bank Sta=4998.9,5003.7
Exp/Cntr=0.3,0.1

Type RM Length L Ch R = 1,25660,461,461,461
BEGIN DESCRIPTION:
SAUL CREEK 56.0
END DESCRIPTION:
XS GIS Cut Line= 3
      2320074.97     13754875.00      2319425.00     13754825.00
      2319025.00     13754475.00
#Sta/Elev= 30
  4363.3  516.53  4373.3  517.05  4383.3  516.62  4403.4  513.61  4423.4  511.56
  4463.6  509.69  4674.2  504.47  4850.2  501.70  4948.8  500.59  4985.1  500.04
  5022.3  501.01  5029.0  495.91  5036.5  496.68  5040.7  495.11  5041.1  494.61
  5045.7  495.11  5050.3  497.64  5057.4  500.84  5100.1  500.96  5184.3  503.00
  5185.1  503.02  5312.7  505.31  5409.3  508.81  5440.4  508.36  5468.4  508.97
  5476.0  510.06  5482.6  510.08  5496.9  508.98  5518.7  510.38  5546.7  511.13
#Mann=9,-1,0
  4363.3    0.07       0  4850.2    0.12       0  4948.8    0.12       0
  5040.7    0.07       0  5045.7    0.12       0  5050.3    0.05       0
  5184.3    0.12       0  5185.1   0.035       0  5409.3    0.07       0
Bank Sta=5040.7,5045.7
Exp/Cntr=0.3,0.1

Type RM Length L Ch R = 1,25199,479,479,479
BEGIN DESCRIPTION:
SAUL CREEK 55.0
END DESCRIPTION:
XS GIS Cut Line= 3
      2320075.02     13754725.01      2319575.00     13754425.00
      2318975.02     13754425.00
#Sta/Elev= 30
  4420.8  515.32  4431.9  516.25  4444.2  515.24  4455.8  512.43  4465.5  511.29
  4545.2  507.54  4579.4  506.89  4698.8  502.58  4720.1  502.69  4778.5  497.79
  4792.7  497.77  4825.1  497.78  4852.3  500.13  4873.7  504.31  4887.3  503.41
  4900.9  500.79  4910.6  500.10  4964.3  498.50  4980.6  498.07  4987.8  496.24
  4988.2  495.74  4992.8  496.24  5023.9  499.29  5053.9  498.90  5301.0  504.58
  5477.0  509.44  5493.9  508.68  5523.9  510.46  5595.8  512.13  5603.9  512.27
#Mann=11,-1,0
  4420.8    0.07       0  4431.9    0.05       0  4579.4    0.07       0
  4792.7    0.05       0  4825.1    0.07       0  4964.3    0.05       0
  4987.8    0.05       0  4992.8    0.05       0  5301.0   0.035       0
  5477.0    0.07       0  5595.8   0.035       0
Bank Sta=4987.8,4992.8
Exp/Cntr=0.3,0.1

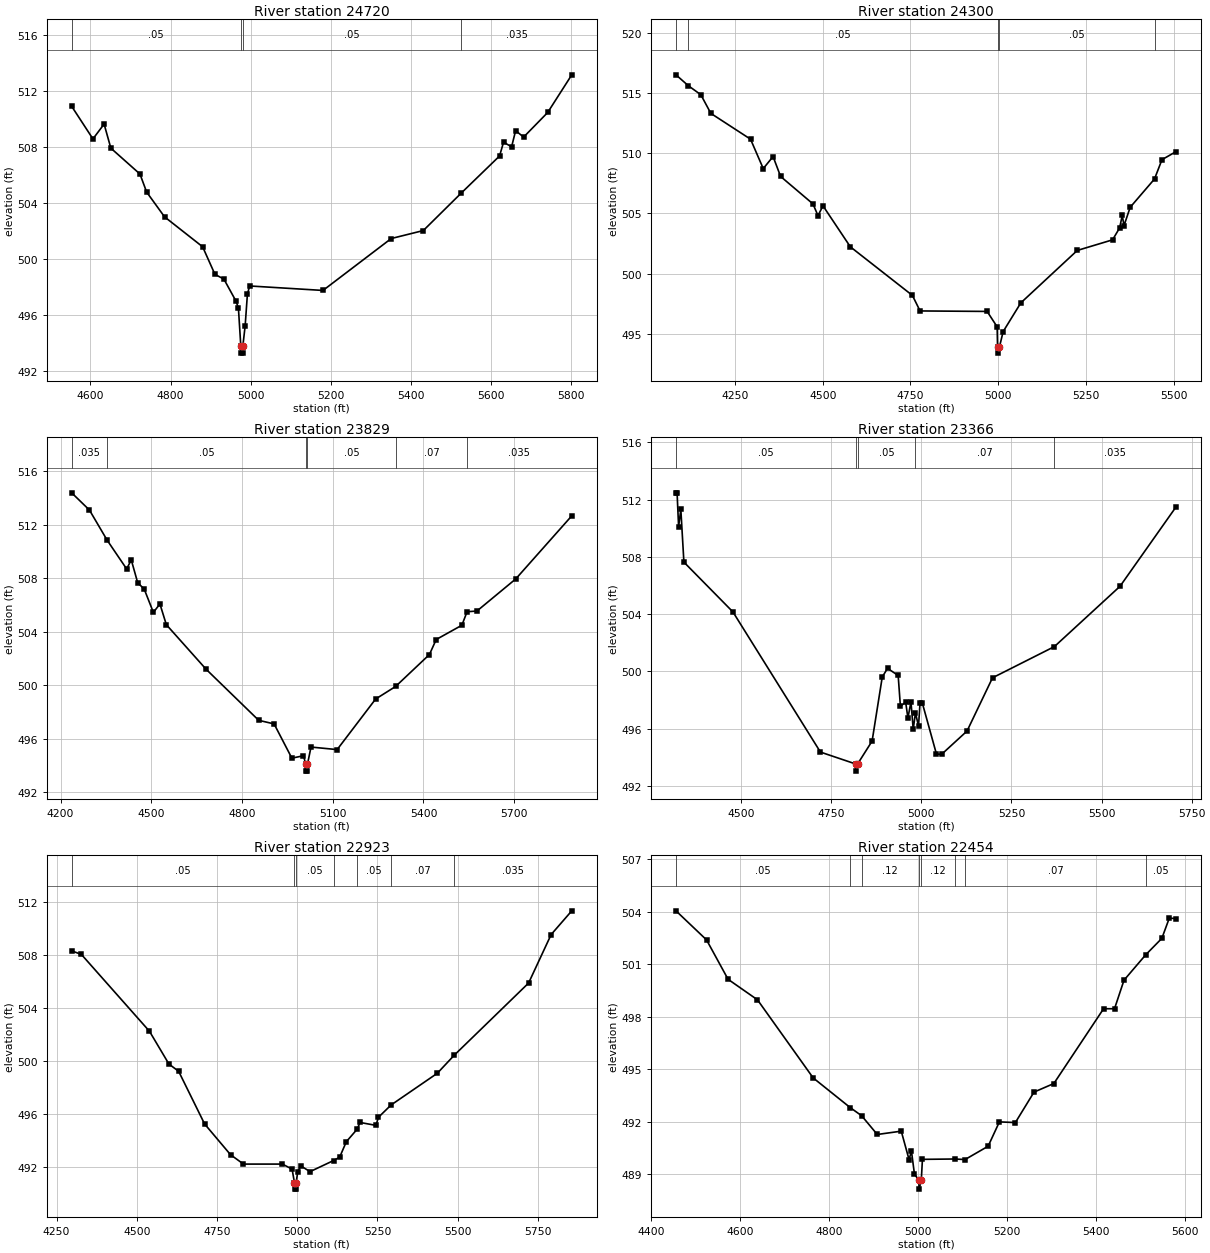
Type RM Length L Ch R = 1,24720,420,420,420
BEGIN DESCRIPTION:
SAUL CREEK 54.0
END DESCRIPTION:
XS GIS Cut Line= 3
      2320174.96     13754224.98      2319775.00     13754025.00
      2318975.03     13753975.00
#Sta/Elev= 30
  4553.1  510.93  4606.2  508.60  4634.1  509.66  4650.9  507.94  4723.6  506.09
  4740.3  504.80  4785.0  503.03  4880.1  500.89  4910.8  498.92  4933.2  498.58
  4963.9  496.98  4969.5  496.49  4975.4  493.79  4975.8  493.29  4980.1  493.29
  4980.5  493.79  4986.3  495.25  4991.9  497.51  4997.5  498.09  5180.6  497.77
  5351.0  501.48  5431.1  502.05  5525.5  504.72  5621.5  507.38  5631.5  508.37
  5651.5  508.03  5661.6  509.19  5681.6  508.73  5741.7  510.49  5801.8  513.18
#Mann=4,-1,0
  4553.1    0.05       0  4975.4    0.05       0  4980.5    0.05       0
  5525.5   0.035       0
Bank Sta=4975.4,4980.5
Exp/Cntr=0.3,0.1

Type RM Length L Ch R = 1,24300,471,471,471
BEGIN DESCRIPTION:
SAUL CREEK 53.0
END DESCRIPTION:
XS GIS Cut Line= 3
      2320375.03     13754275.02      2319675.00     13753675.00
      2319174.98     13753725.00
#Sta/Elev= 30
  4082.0  516.49  4117.5  515.58  4152.8  514.84  4181.4  513.29  4294.4  511.15
  4330.6  508.71  4358.6  509.71  4380.0  508.06  4472.2  505.78  4486.5  504.81
  4500.8  505.62  4578.7  502.22  4755.4  498.19  4777.3  496.90  4968.3  496.86
  4996.9  495.58  4998.0  493.90  4998.5  493.40  5003.3  493.90  5014.0  495.19
  5064.3  497.57  5225.1  501.92  5325.6  502.80  5345.7  503.79  5353.2  504.82
  5358.2  503.98  5375.8  505.50  5445.1  507.85  5466.3  509.45  5506.5  510.12
#Mann=5,-1,0
  4082.0   0.035       0  4117.5    0.05       0  4998.0    0.05       0
  5003.3    0.05       0  5445.1   0.035       0
Bank Sta=4998,5003.3
Exp/Cntr=0.3,0.1

Type RM Length L Ch R = 1,23829,463,463,463
BEGIN DESCRIPTION:
SAUL CREEK 52.0
END DESCRIPTION:
XS GIS Cut Line= 3
      2320425.02     13754075.04      2320025.00     13753425.00
      2319324.99     13752874.99
#Sta/Elev= 30
  4236.8  514.38  4295.6  513.09  4354.0  510.84  4418.5  508.69  4433.9  509.36
  4455.2  507.65  4476.5  507.19  4506.9  505.44  4528.6  506.07  4549.8  504.52
  4681.2  501.19  4855.1  497.37  4906.1  497.10  4964.8  494.54  5003.2  494.72
  5011.0  494.07  5011.4  493.57  5015.9  493.57  5016.3  494.07  5028.1  495.37
  5114.5  495.18  5241.7  498.96  5307.8  499.90  5419.7  502.29  5442.0  503.41
  5527.0  504.48  5544.1  505.49  5576.7  505.54  5705.0  507.94  5890.3  512.66
#Mann=6,-1,0
  4236.8   0.035       0  4354.0    0.05       0  5011.0    0.05       0
  5016.3    0.05       0  5307.8    0.07       0  5544.1   0.035       0
Bank Sta=5011,5016.3
Exp/Cntr=0.3,0.1

Type RM Length L Ch R = 1,23366,443,443,443
BEGIN DESCRIPTION:
SAUL CREEK 51.0
END DESCRIPTION:
XS GIS Cut Line= 3
      2320574.98     13753624.97      2320175.00     13753075.00
      2319675.03     13752575.03
#Sta/Elev= 30
  4319.7  512.48  4322.8  512.48  4327.0  510.12  4333.2  511.32  4341.7  507.64
  4477.7  504.16  4720.4  494.37  4818.1  493.54  4818.6  493.04  4823.5  493.54
  4863.7  495.14  4891.9  499.62  4906.6  500.22  4936.0  499.72  4942.2  497.57
  4956.8  497.86  4963.0  496.75  4971.5  497.88  4977.7  495.96  4984.0  497.11
  4992.4  496.19  4996.6  497.77  5003.3  497.77  5042.2  494.23  5056.3  494.21
  5127.0  495.84  5197.7  499.56  5369.4  501.74  5551.3  505.95  5706.8  511.50
#Mann=5,-1,0
  4319.7    0.05       0  4818.1    0.07       0  4823.5    0.05       0
  4984.0    0.07       0  5369.4   0.035       0
Bank Sta=4818.1,4823.5
Exp/Cntr=0.3,0.1

Type RM Length L Ch R = 1,22923,469,469,469
BEGIN DESCRIPTION:
SAUL CREEK 50.0
END DESCRIPTION:
XS GIS Cut Line= 3
      2320625.00     13753625.03      2320525.00     13752925.00
      2319975.00     13752275.00
#Sta/Elev= 30
  4296.9  508.33  4327.2  508.06  4539.4  502.26  4600.0  499.79  4630.3  499.24
  4711.1  495.27  4791.9  492.95  4832.3  492.24  4953.5  492.24  4983.8  491.86
  4991.2  490.85  4991.6  490.35  4996.2  490.35  4996.6  490.85  5001.5  491.67
  5011.2  492.10  5039.8  491.67  5113.4  492.51  5132.1  492.76  5152.9  493.93
  5186.2  494.86  5195.8  495.38  5245.2  495.16  5252.9  495.77  5292.4  496.70
  5436.3  499.09  5489.4  500.46  5720.9  505.90  5791.2  509.56  5855.5  511.35
#Mann=7,-1,0
  4296.9    0.05       0  4991.2    0.05       0  4996.6    0.05       0
  5113.4    0.07       0  5186.2    0.05       0  5292.4    0.07       0
  5489.4   0.035       0
Bank Sta=4991.2,4996.6
Exp/Cntr=0.3,0.1

Type RM Length L Ch R = 1,22454,480,480,480
BEGIN DESCRIPTION:
SAUL CREEK 49.0
END DESCRIPTION:
XS GIS Cut Line= 3
      2320775.00     13753474.99      2320975.00     13752975.00
      2321174.99     13752425.04
#Sta/Elev= 30
  4455.5  504.04  4524.2  502.38  4572.6  500.13  4638.6  498.96  4763.8  494.50
  4846.8  492.81  4872.7  492.34  4907.8  491.27  4961.7  491.46  4979.2  489.84
  4984.6  490.32  4991.3  489.02  5001.2  488.65  5001.7  488.15  5006.7  488.65
  5009.3  489.85  5081.4  489.87  5105.1  489.84  5156.9  490.60  5182.2  491.99
  5218.1  491.95  5260.0  493.69  5304.6  494.18  5416.3  498.45  5440.9  498.45
  5462.2  500.08  5511.0  501.53  5547.3  502.47  5563.9  503.62  5579.2  503.60
#Mann=8,-1,0
  4455.5    0.05       0  4846.8    0.07       0  4872.7    0.12       0
  5001.2    0.07       0  5006.7    0.12       0  5081.4    0.05       0
  5105.1    0.07       0  5511.0    0.05       0
Bank Sta=5001.2,5006.7
Exp/Cntr=0.3,0.1

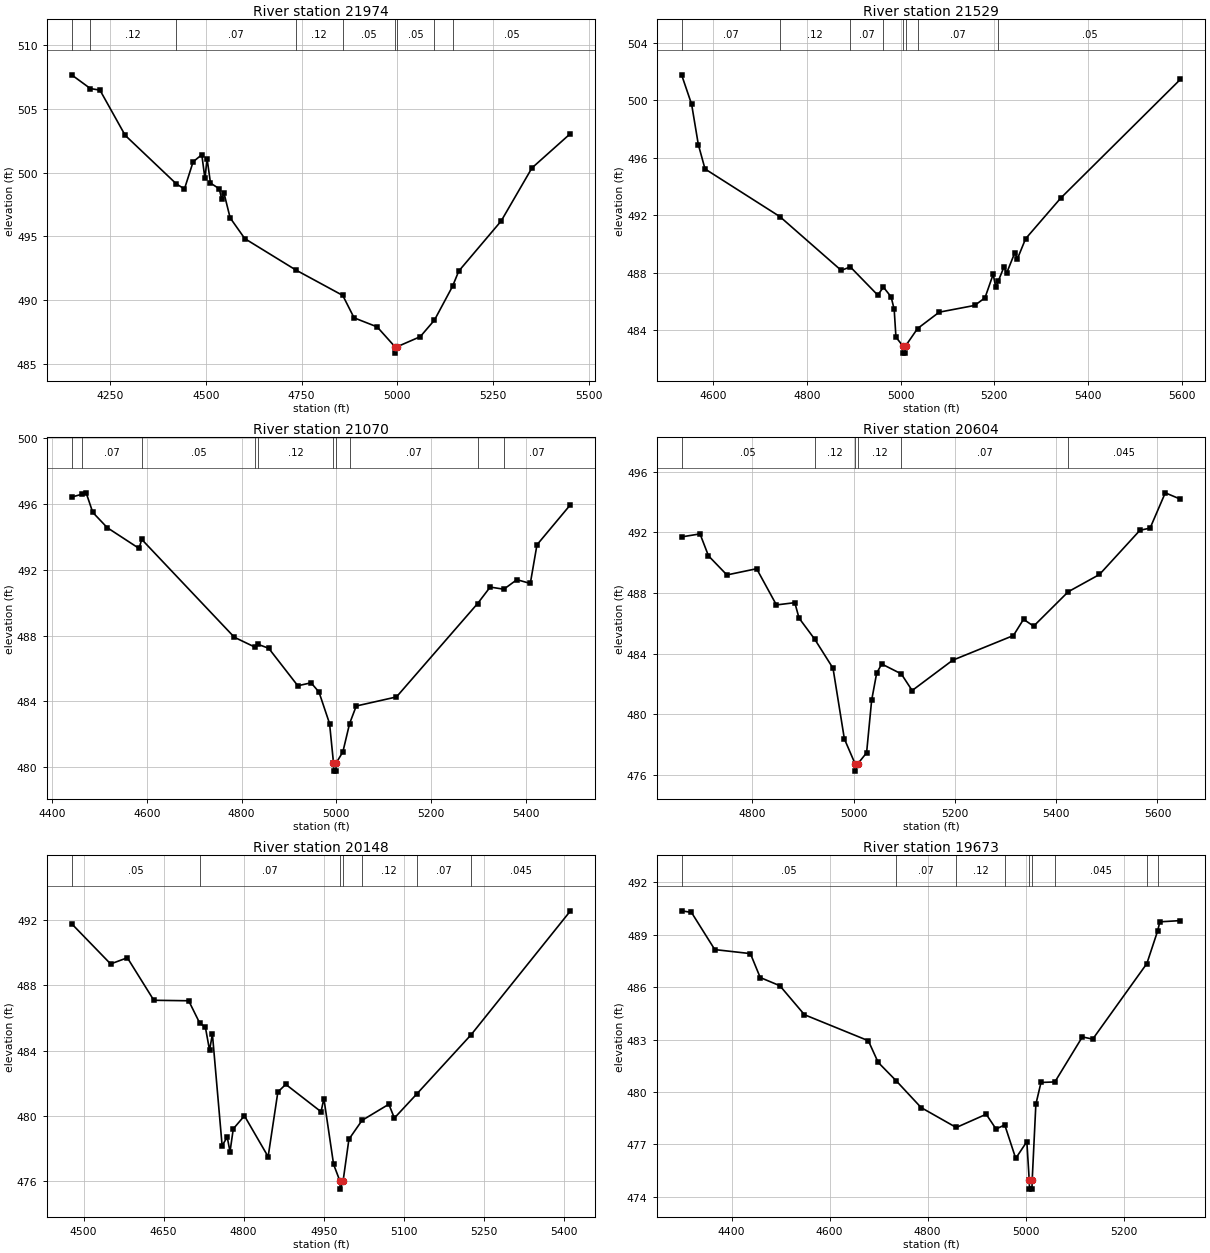
Type RM Length L Ch R = 1,21974,445,445,445
BEGIN DESCRIPTION:
SAUL CREEK 48.0
END DESCRIPTION:
XS GIS Cut Line= 3
      2321025.00     13753725.00      2321425.00     13752975.00
      2321475.00     13752524.97
#Sta/Elev= 30
  4149.6  507.68  4198.7  506.60  4223.6  506.48  4289.5  502.93  4423.0  499.12
  4444.3  498.72  4466.9  500.85  4489.6  501.41  4497.7  499.55  4503.4  501.09
  4512.3  499.18  4534.9  498.74  4541.7  497.92  4547.3  498.42  4563.6  496.45
  4601.9  494.82  4735.0  492.36  4857.7  490.36  4887.3  488.60  4947.5  487.89
  4994.0  486.33  4994.4  485.83  4999.5  486.33  5060.0  487.12  5097.1  488.42
  5144.3  491.07  5160.6  492.27  5271.3  496.20  5351.8  500.37  5452.4  503.07
#Mann=9,-1,0
  4149.6    0.07       0  4198.7    0.12       0  4423.0    0.07       0
  4735.0    0.12       0  4857.7    0.05       0  4994.0    0.05       0
  4999.5    0.05       0  5097.1    0.07       0  5144.3    0.05       0
Bank Sta=4994,4999.5
Exp/Cntr=0.3,0.1

Type RM Length L Ch R = 1,21529,459,459,459
BEGIN DESCRIPTION:
SAUL CREEK 47.0
END DESCRIPTION:
XS GIS Cut Line= 3
      2321524.97     13753475.04      2321825.00     13753125.00
      2321574.99     13752574.98
#Sta/Elev= 30
  4532.4  501.77  4553.8  499.72  4568.1  496.92  4582.4  495.22  4742.3  491.90
  4873.2  488.16  4892.7  488.40  4951.2  486.44  4963.4  486.99  4979.7  486.32
  4986.3  485.45  4990.1  483.51  5004.9  482.90  5005.4  482.40  5010.1  482.40
  5010.6  482.90  5036.2  484.11  5082.4  485.25  5158.2  485.72  5180.2  486.25
  5197.7  487.89  5203.2  486.98  5208.4  487.40  5220.8  488.40  5226.3  487.96
  5243.9  489.39  5249.4  488.96  5266.9  490.36  5341.6  493.18  5597.6  501.46
#Mann=8,-1,0
  4532.4    0.07       0  4742.3    0.12       0  4892.7    0.07       0
  4963.4    0.12       0  5004.9    0.07       0  5010.6    0.12       0
  5036.2    0.07       0  5208.4    0.05       0
Bank Sta=5004.9,5010.6
Exp/Cntr=0.3,0.1

Type RM Length L Ch R = 1,21070,466,466,466
BEGIN DESCRIPTION:
SAUL CREEK 46.0
END DESCRIPTION:
XS GIS Cut Line= 3
      2322474.99     13753474.97      2322225.00     13752975.00
      2321874.97     13752624.97
#Sta/Elev= 30
  4440.8  496.42  4461.9  496.59  4471.5  496.68  4485.5  495.49  4516.2  494.56
  4583.3  493.30  4588.9  493.85  4784.6  487.90  4828.8  487.29  4835.3  487.46
  4857.2  487.23  4918.7  484.95  4946.7  485.13  4963.4  484.57  4985.8  482.65
  4994.1  480.26  4994.5  479.76  4999.4  479.76  4999.9  480.26  5013.9  480.93
  5028.1  482.65  5042.2  483.72  5127.1  484.27  5298.6  489.95  5325.1  490.95
  5354.0  490.82  5381.6  491.40  5409.9  491.17  5424.0  493.52  5494.8  495.96
#Mann=10,-1,0
  4440.8    0.05       0  4461.9    0.07       0  4588.9    0.05       0
  4828.8    0.12       0  4835.3    0.12       0  4994.1    0.07       0
  4999.9    0.12       0  5028.1    0.07       0  5298.6   0.045       0
  5354.0    0.07       0
Bank Sta=4994.1,4999.9
Exp/Cntr=0.3,0.1

Type RM Length L Ch R = 1,20604,456,456,456
BEGIN DESCRIPTION:
SAUL CREEK 45.0
END DESCRIPTION:
XS GIS Cut Line= 3
      2322775.01     13753275.02      2322625.00     13752975.00
      2322625.00     13752325.03
#Sta/Elev= 30
  4660.0  491.70  4696.4  491.90  4713.1  490.45  4749.5  489.19  4808.2  489.60
  4847.3  487.21  4883.6  487.36  4892.0  486.34  4922.9  484.95  4959.1  483.03
  4981.5  478.37  5002.5  476.74  5003.0  476.24  5008.4  476.74  5025.4  477.45
  5035.4  480.92  5045.4  482.72  5055.4  483.31  5093.9  482.66  5115.4  481.56
  5195.4  483.56  5315.4  485.19  5335.4  486.26  5355.4  485.81  5423.7  488.08
  5485.4  489.22  5565.4  492.14  5585.4  492.28  5615.4  494.61  5645.4  494.19
#Mann=6,-1,0
  4660.0    0.05       0  4922.9    0.12       0  5002.5    0.07       0
  5008.4    0.12       0  5093.9    0.07       0  5423.7   0.045       0
Bank Sta=5002.5,5008.4
Exp/Cntr=0.3,0.1

Type RM Length L Ch R = 1,20148,475,475,475
BEGIN DESCRIPTION:
SAUL CREEK 44.0
END DESCRIPTION:
XS GIS Cut Line= 3
      2322824.99     13753275.04      2322975.00     13752775.00
      2322874.99     13752374.96
#Sta/Elev= 30
  4477.7  491.79  4550.8  489.32  4582.1  489.70  4631.7  487.09  4697.0  487.06
  4717.5  485.70  4728.3  485.43  4736.1  484.02  4741.4  485.02  4759.6  478.17
  4769.2  478.69  4774.4  477.79  4780.5  479.20  4801.4  480.00  4845.8  477.49
  4864.0  481.46  4878.8  481.93  4944.9  480.25  4950.2  481.06  4968.4  477.02
  4980.2  476.00  4980.7  475.50  4986.2  476.00  4997.1  478.56  5021.7  479.72
  5071.9  480.71  5082.2  479.86  5123.9  481.33  5226.1  484.98  5412.1  492.58
#Mann=7,-1,0
  4477.7    0.05       0  4717.5    0.07       0  4980.2    0.07       0
  4986.2    0.07       0  5021.7    0.12       0  5123.9    0.07       0
  5226.1   0.045       0
Bank Sta=4980.2,4986.2
Exp/Cntr=0.3,0.1

Type RM Length L Ch R = 1,19673,453,453,453
BEGIN DESCRIPTION:
SAUL CREEK 43.0
END DESCRIPTION:
XS GIS Cut Line= 3
      2323425.00     13753325.04      2323375.00     13752625.00
      2323275.02     13752325.05
#Sta/Elev= 30
  4298.1  490.37  4318.2  490.28  4365.8  488.15  4438.5  487.92  4458.5  486.55
  4498.6  486.08  4548.8  484.42  4679.1  482.93  4699.2  481.69  4735.5  480.65
  4786.9  479.10  4858.6  477.96  4919.7  478.72  4939.8  477.87  4957.5  478.11
  4979.9  476.19  5002.6  477.15  5007.5  474.93  5008.0  474.43  5013.0  474.43
  5013.5  474.93  5021.0  479.29  5031.5  480.54  5059.8  480.57  5115.9  483.15
  5137.0  483.02  5247.5  487.35  5269.4  489.21  5274.0  489.74  5316.1  489.81
#Mann=9,-1,0
  4298.1    0.05       0  4735.5    0.07       0  4858.6    0.12       0
  4957.5    0.12       0  5007.5    0.07       0  5013.5    0.12       0
  5059.8   0.045       0  5247.5    0.07       0  5269.4   0.045       0
Bank Sta=5007.5,5013.5
Exp/Cntr=0.3,0.1

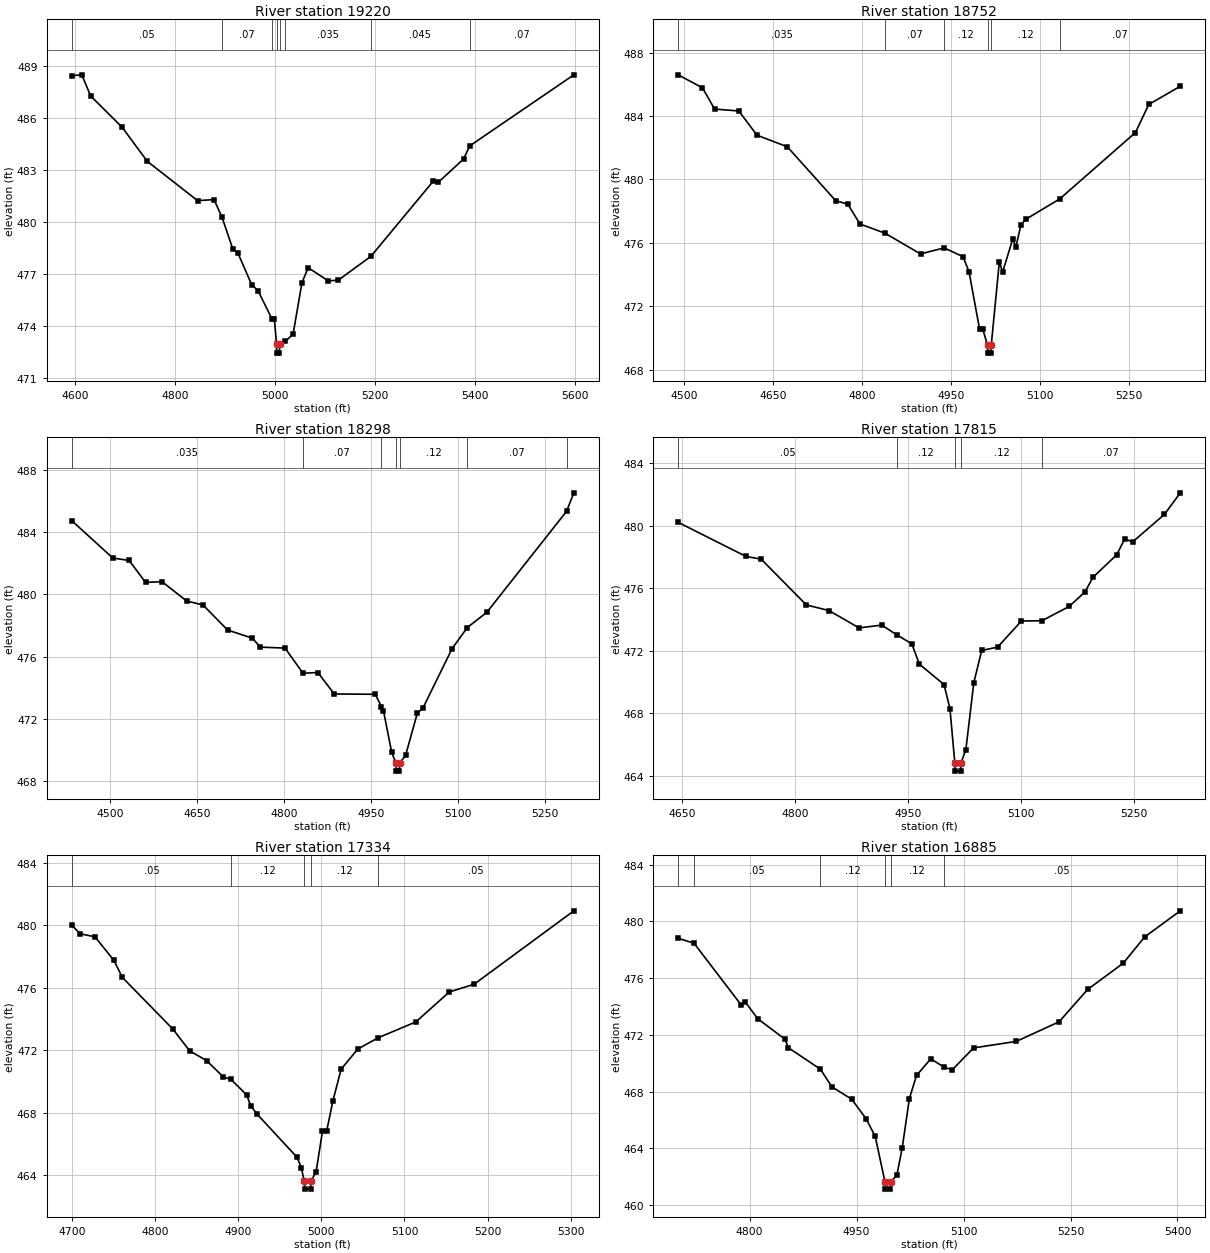
Type RM Length L Ch R = 1,19220,468,468,468
BEGIN DESCRIPTION:
SAUL CREEK 42.0
END DESCRIPTION:
XS GIS Cut Line= 3
      2323725.00     13753174.97      2323775.00     13752775.00
      2323725.00     13752174.96
#Sta/Elev= 30
  4593.1  488.43  4613.2  488.48  4630.9  487.26  4693.8  485.46  4744.2  483.49
  4845.0  481.22  4877.8  481.28  4893.6  480.29  4915.6  478.42  4925.6  478.20
  4953.3  476.37  4965.9  476.03  4993.8  474.40  4998.7  474.40  5003.1  472.92
  5003.6  472.42  5008.8  472.42  5009.3  472.92  5021.0  473.10  5036.3  473.53
  5053.9  476.48  5066.4  477.35  5106.6  476.59  5126.6  476.63  5191.8  478.00
  5317.3  482.36  5327.3  482.29  5377.5  483.62  5389.9  484.38  5598.3  488.48
#Mann=8,-1,0
  4593.1    0.05       0  4893.6    0.07       0  4993.8    0.12       0
  5003.1    0.07       0  5009.3    0.12       0  5021.0   0.035       0
  5191.8   0.045       0  5389.9    0.07       0
Bank Sta=5003.1,5009.3
Exp/Cntr=0.3,0.1

Type RM Length L Ch R = 1,18752,454,454,454
BEGIN DESCRIPTION:
SAUL CREEK 41.0
END DESCRIPTION:
XS GIS Cut Line= 3
      2323925.00     13753124.99      2324025.00     13752625.00
      2324175.00     13752325.00
#Sta/Elev= 30
  4490.6  486.60  4531.4  485.78  4551.8  484.44  4592.6  484.32  4623.2  482.79
  4674.2  482.06  4755.7  478.66  4776.1  478.44  4796.5  477.19  4838.5  476.61
  4898.5  475.30  4938.3  475.68  4969.9  475.13  4980.1  474.19  4997.9  470.56
  5003.3  470.56  5011.3  469.54  5011.8  469.04  5017.1  469.04  5017.6  469.54
  5031.2  474.79  5036.8  474.16  5053.6  476.22  5059.2  475.76  5067.6  477.14
  5076.0  477.49  5132.9  478.77  5260.4  482.96  5282.8  484.73  5335.9  485.88
#Mann=6,-1,0
  4490.6   0.035       0  4838.5    0.07       0  4938.3    0.12       0
  5011.3    0.07       0  5017.6    0.12       0  5132.9    0.07       0
Bank Sta=5011.3,5017.6
Exp/Cntr=0.3,0.1

Type RM Length L Ch R = 1,18298,483,483,483
BEGIN DESCRIPTION:
SAUL CREEK 40.0
END DESCRIPTION:
XS GIS Cut Line= 3
      2324024.98     13753075.02      2324425.00     13752675.00
      2324425.00     13752375.02
#Sta/Elev= 30
  4434.4  484.74  4505.1  482.34  4533.4  482.18  4561.7  480.77  4590.0  480.82
  4632.4  479.58  4660.7  479.32  4703.1  477.71  4745.6  477.19  4759.7  476.61
  4802.1  476.55  4833.2  474.93  4858.7  474.98  4887.0  473.60  4957.7  473.58
  4968.4  472.78  4971.8  472.53  4986.0  469.85  4993.4  469.14  4993.9  468.64
  4999.3  468.64  4999.8  469.14  5010.1  469.67  5030.1  472.35  5040.1  472.71
  5090.1  476.51  5116.4  477.87  5150.1  478.85  5287.5  485.34  5300.1  486.53
#Mann=7,-1,0
  4434.4   0.035       0  4833.2    0.07       0  4968.4    0.12       0
  4993.4    0.07       0  4999.8    0.12       0  5116.4    0.07       0
  5287.5    0.05       0
Bank Sta=4993.4,4999.8
Exp/Cntr=0.3,0.1

Type RM Length L Ch R = 1,17815,481,481,481
BEGIN DESCRIPTION:
SAUL CREEK 39.0
END DESCRIPTION:
XS GIS Cut Line= 3
      2324875.00     13753125.04      2324875.00     13752775.00
      2324975.01     13752474.96
#Sta/Elev= 30
  4645.4  480.20  4735.4  478.02  4755.4  477.85  4815.4  474.92  4845.4  474.56
  4885.4  473.45  4915.4  473.63  4936.1  472.99  4955.4  472.43  4965.4  471.13
  4998.1  469.83  5006.0  468.28  5012.5  464.79  5013.0  464.29  5020.0  464.29
  5020.5  464.79  5027.1  465.66  5037.6  469.93  5048.1  472.01  5069.2  472.22
  5100.8  473.89  5128.1  473.91  5164.1  474.82  5185.2  475.75  5195.7  476.68
  5227.3  478.13  5237.9  479.14  5248.4  478.95  5290.6  480.71  5311.7  482.09
#Mann=5,-1,0
  4645.4    0.05       0  4936.1    0.12       0  5012.5    0.07       0
  5020.5    0.12       0  5128.1    0.07       0
Bank Sta=5012.5,5020.5
Exp/Cntr=0.3,0.1

Type RM Length L Ch R = 1,17334,449,449,449
BEGIN DESCRIPTION:
SAUL CREEK 38.0
END DESCRIPTION:
XS GIS Cut Line= 3
      2325275.01     13753074.97      2325325.00     13752775.00
      2325325.00     13752475.00
#Sta/Elev= 30
  4699.7  480.00  4709.8  479.45  4727.5  479.26  4750.4  477.75  4760.5  476.66
  4821.3  473.35  4841.6  471.95  4861.9  471.33  4882.1  470.28  4891.2  470.13
  4910.0  469.14  4915.1  468.43  4922.7  467.90  4970.9  465.13  4975.9  464.46
  4979.5  463.60  4980.0  463.10  4987.0  463.10  4987.5  463.60  4993.7  464.21
  5001.3  466.79  5006.3  466.79  5013.8  468.73  5023.8  470.78  5043.8  472.07
  5068.3  472.79  5113.8  473.81  5153.8  475.72  5183.8  476.22  5303.8  480.92
#Mann=5,-1,0
  4699.7    0.05       0  4891.2    0.12       0  4979.5    0.07       0
  4987.5    0.12       0  5068.3    0.05       0
Bank Sta=4979.5,4987.5
Exp/Cntr=0.3,0.1

Type RM Length L Ch R = 1,16885,467,467,467
BEGIN DESCRIPTION:
SAUL CREEK 37.0
END DESCRIPTION:
XS GIS Cut Line= 3
      2325624.99     13753175.04      2325675.00     13752875.00
      2325675.00     13752474.98
#Sta/Elev= 30
  4699.8  478.80  4721.9  478.46  4788.5  474.08  4793.6  474.33  4811.4  473.13
  4849.4  471.70  4854.4  471.09  4899.2  469.58  4915.3  468.34  4943.2  467.46
  4963.4  466.08  4976.1  464.84  4989.8  461.63  4990.3  461.13  4997.4  461.13
  4997.9  461.63  5006.5  462.13  5014.0  464.05  5024.0  467.51  5034.0  469.14
  5054.0  470.31  5072.2  469.74  5084.0  469.53  5114.0  471.08  5174.0  471.54
  5234.0  472.92  5274.0  475.20  5324.0  477.05  5354.0  478.90  5404.0  480.74
#Mann=6,-1,0
  4699.8   0.045       0  4721.9    0.05       0  4899.2    0.12       0
  4989.8    0.07       0  4997.9    0.12       0  5072.2    0.05       0
Bank Sta=4989.8,4997.9
Exp/Cntr=0.3,0.1