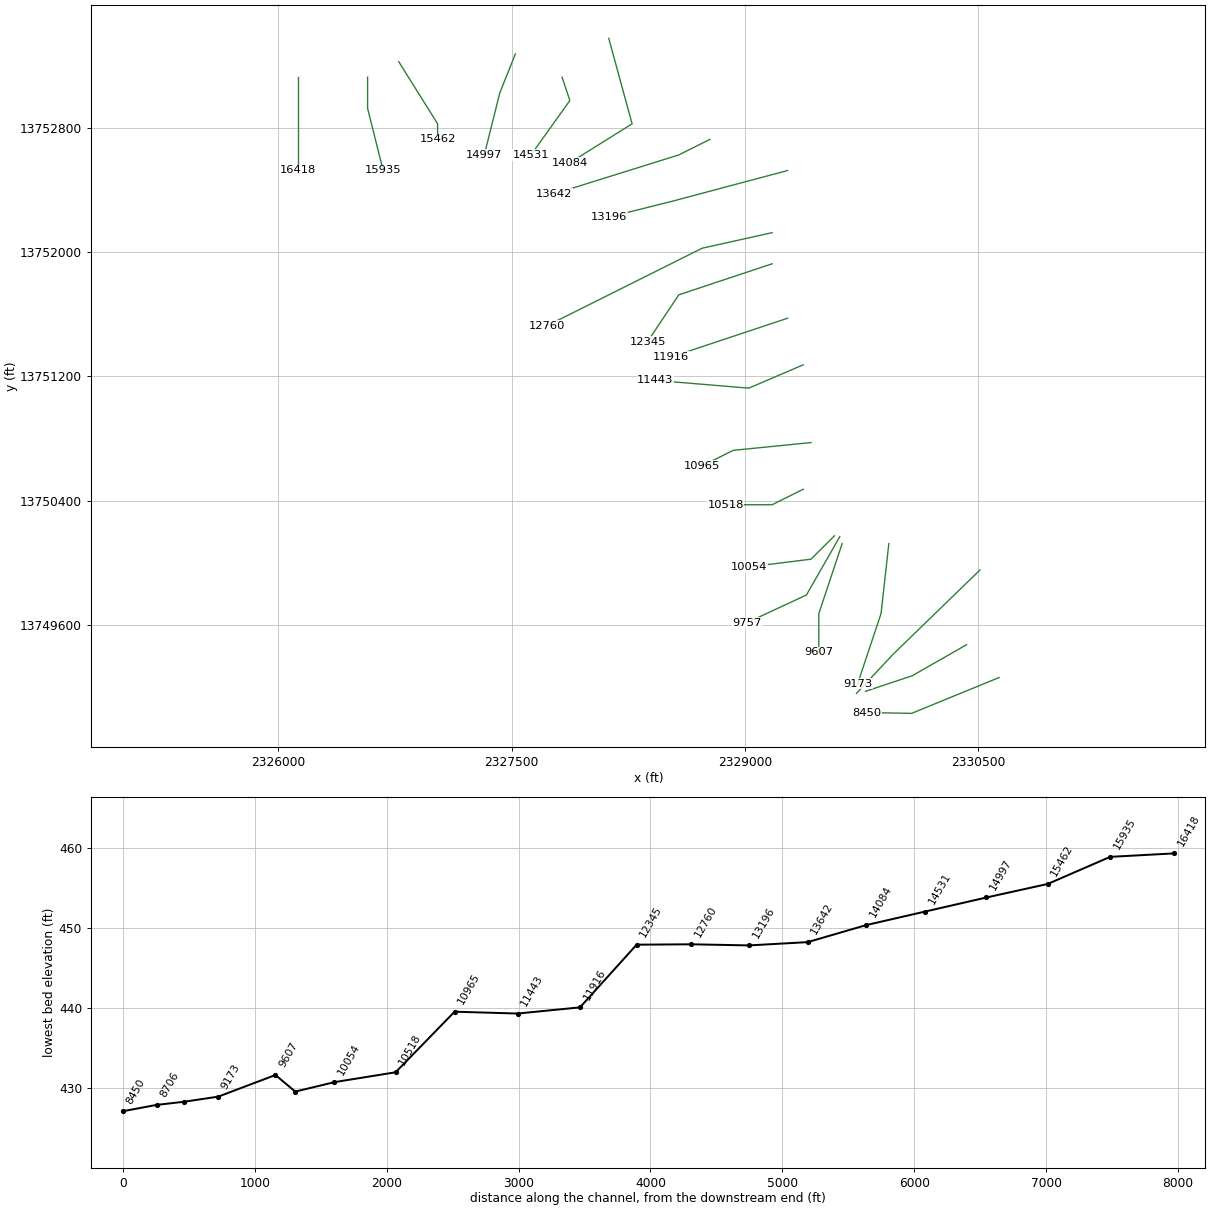
HEC-RAS study SAUL CREEK.prj: SAUL CREEK Base Level Engineering

--- SAUL CREEK.g01 (geometry) --- (continued)

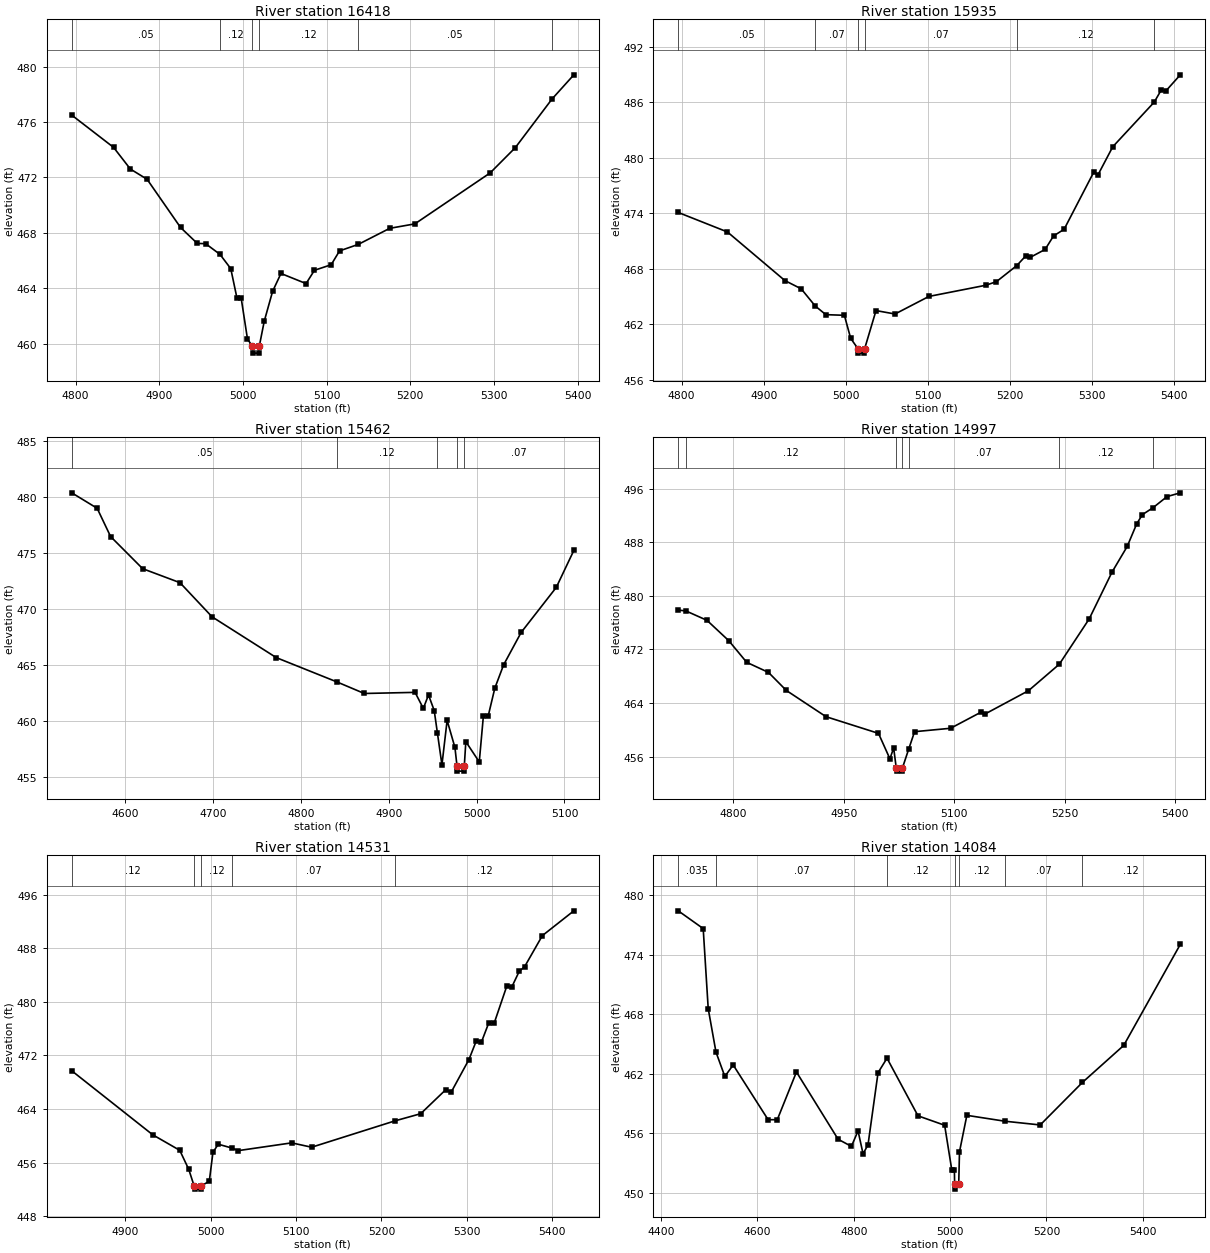
Type RM Length L Ch R = 1,16418,483,483,483
BEGIN DESCRIPTION:
SAUL CREEK 36.0
END DESCRIPTION:
XS GIS Cut Line= 3
      2326125.00     13753125.03      2326125.00     13752925.00
      2326125.00     13752525.03
#Sta/Elev= 30
  4795.4  476.50  4845.4  474.17  4865.4  472.61  4885.4  471.87  4925.4  468.39
  4945.4  467.24  4955.4  467.22  4972.5  466.45  4985.4  465.42  4992.9  463.27
  4997.9  463.27  5005.4  460.33  5011.3  459.82  5011.8  459.32  5019.0  459.32
  5019.5  459.82  5025.4  461.62  5035.4  463.78  5045.4  465.07  5075.4  464.34
  5085.4  465.30  5105.4  465.70  5115.4  466.70  5137.8  467.17  5175.4  468.33
  5205.4  468.65  5295.4  472.33  5325.4  474.15  5369.4  477.67  5395.4  479.41
#Mann=6,-1,0
  4795.4    0.05       0  4972.5    0.12       0  5011.3    0.07       0
  5019.5    0.12       0  5137.8    0.05       0  5369.4    0.07       0
Bank Sta=5011.3,5019.5
Exp/Cntr=0.3,0.1

Type RM Length L Ch R = 1,15935,473,473,473
BEGIN DESCRIPTION:
SAUL CREEK 35.0
END DESCRIPTION:
XS GIS Cut Line= 3
      2326575.00     13753125.02      2326575.00     13752925.00
      2326674.99     13752525.03
#Sta/Elev= 30
  4795.8  474.10  4855.8  471.99  4925.8  466.74  4945.8  465.84  4962.8  463.99
  4975.8  463.05  4998.4  462.98  5006.1  460.49  5014.8  459.39  5015.3  458.89
  5022.7  458.89  5023.2  459.39  5037.0  463.49  5060.2  463.12  5101.5  465.02
  5171.0  466.23  5183.9  466.62  5208.7  468.36  5220.0  469.44  5225.2  469.25
  5243.2  470.10  5253.5  471.56  5266.4  472.28  5302.5  478.45  5307.6  478.15
  5325.7  481.20  5376.3  486.03  5384.9  487.35  5390.1  487.20  5408.1  488.98
#Mann=6,-1,0
  4795.8    0.05       0  4962.8    0.07       0  5014.8    0.07       0
  5023.2    0.07       0  5208.7    0.12       0  5376.3    0.07       0
Bank Sta=5014.8,5023.2
Exp/Cntr=0.3,0.1

Type RM Length L Ch R = 1,15462,465,465,465
BEGIN DESCRIPTION:
SAUL CREEK 34.0
END DESCRIPTION:
XS GIS Cut Line= 3
      2326775.02     13753224.97      2327025.00     13752825.00
      2327025.00     13752724.97
#Sta/Elev= 30
  4539.0  480.35  4567.9  478.97  4583.2  476.45  4619.7  473.58  4662.2  472.33
  4698.8  469.28  4771.9  465.64  4841.3  463.46  4872.1  462.44  4929.9  462.54
  4939.3  461.11  4945.2  462.31  4951.7  460.92  4955.3  458.94  4960.5  456.07
  4966.4  460.04  4975.3  457.62  4977.6  456.01  4978.1  455.51  4985.5  455.51
  4986.0  456.01  4987.7  458.14  5003.0  456.33  5007.7  460.44  5013.2  460.44
  5020.7  462.91  5030.7  464.99  5050.7  467.89  5090.7  471.91  5110.7  475.21
#Mann=5,-1,0
  4539.0    0.05       0  4841.3    0.12       0  4955.3    0.07       0
  4977.6    0.07       0  4986.0    0.07       0
Bank Sta=4977.6,4986
Exp/Cntr=0.3,0.1

Type RM Length L Ch R = 1,14997,466,466,466
BEGIN DESCRIPTION:
SAUL CREEK 33.0
END DESCRIPTION:
XS GIS Cut Line= 3
      2327524.98     13753274.96      2327425.00     13753025.00
      2327325.01     13752625.02
#Sta/Elev= 30
  4725.4  477.87  4735.9  477.74  4764.4  476.34  4794.0  473.30  4818.3  470.07
  4847.9  468.56  4872.1  465.87  4926.0  461.95  4997.2  459.46  5012.7  455.66
  5017.8  457.28  5021.3  454.32  5021.8  453.82  5029.3  453.82  5029.8  454.32
  5038.2  457.10  5046.2  459.71  5095.1  460.22  5136.3  462.62  5141.5  462.33
  5200.8  465.83  5242.7  469.79  5283.2  476.55  5314.2  483.54  5334.8  487.37
  5347.7  490.75  5355.4  492.12  5370.0  493.17  5388.9  494.82  5406.9  495.38
#Mann=7,-1,0
  4725.4    0.07       0  4735.9    0.12       0  5021.3    0.07       0
  5029.8    0.12       0  5038.2    0.07       0  5242.7    0.12       0
  5370.0   0.035       0
Bank Sta=5021.3,5029.8
Exp/Cntr=0.3,0.1

Type RM Length L Ch R = 1,14531,447,447,447
BEGIN DESCRIPTION:
SAUL CREEK 32.0
END DESCRIPTION:
XS GIS Cut Line= 3
      2327825.01     13753124.96      2327875.00     13752975.00
      2327624.99     13752624.99
#Sta/Elev= 30
  4837.2  469.71  4932.0  460.17  4963.7  457.85  4974.2  455.02  4980.5  452.56
  4981.0  452.06  4988.5  452.06  4989.0  452.56  4998.3  453.23  5002.6  457.55
  5008.8  458.76  5025.3  458.17  5032.1  457.80  5094.8  458.96  5118.2  458.31
  5215.8  462.24  5246.0  463.31  5275.5  466.91  5281.6  466.50  5302.5  471.39
  5311.1  474.17  5317.2  474.02  5325.8  476.88  5332.0  476.79  5346.7  482.29
  5352.9  482.26  5361.5  484.57  5367.6  485.21  5388.5  489.87  5425.4  493.57
#Mann=5,-1,0
  4837.2    0.12       0  4980.5    0.07       0  4989.0    0.12       0
  5025.3    0.07       0  5215.8    0.12       0
Bank Sta=4980.5,4989
Exp/Cntr=0.3,0.1

Type RM Length L Ch R = 1,14084,442,442,442
BEGIN DESCRIPTION:
SAUL CREEK 31.0
END DESCRIPTION:
XS GIS Cut Line= 3
      2328125.01     13753374.97      2328275.00     13752825.00
      2327874.96     13752574.98
#Sta/Elev= 30
  4435.9  478.43  4487.7  476.64  4498.1  468.57  4514.2  464.19  4532.6  461.73
  4549.9  462.89  4622.4  457.37  4641.4  457.37  4681.2  462.18  4767.6  455.40
  4795.2  454.68  4809.0  456.24  4819.4  453.93  4829.7  454.84  4850.5  462.11
  4869.1  463.57  4933.4  457.76  4988.7  456.81  5003.4  452.34  5008.9  452.34
  5009.4  450.87  5009.9  450.37  5017.9  450.87  5019.5  454.14  5034.8  457.81
  5113.3  457.22  5187.0  456.84  5274.6  461.13  5360.3  464.86  5477.7  475.05
#Mann=7,-1,0
  4435.9   0.035       0  4514.2    0.07       0  4869.1    0.12       0
  5009.4    0.07       0  5017.9    0.12       0  5113.3    0.07       0
  5274.6    0.12       0
Bank Sta=5009.4,5017.9
Exp/Cntr=0.3,0.1

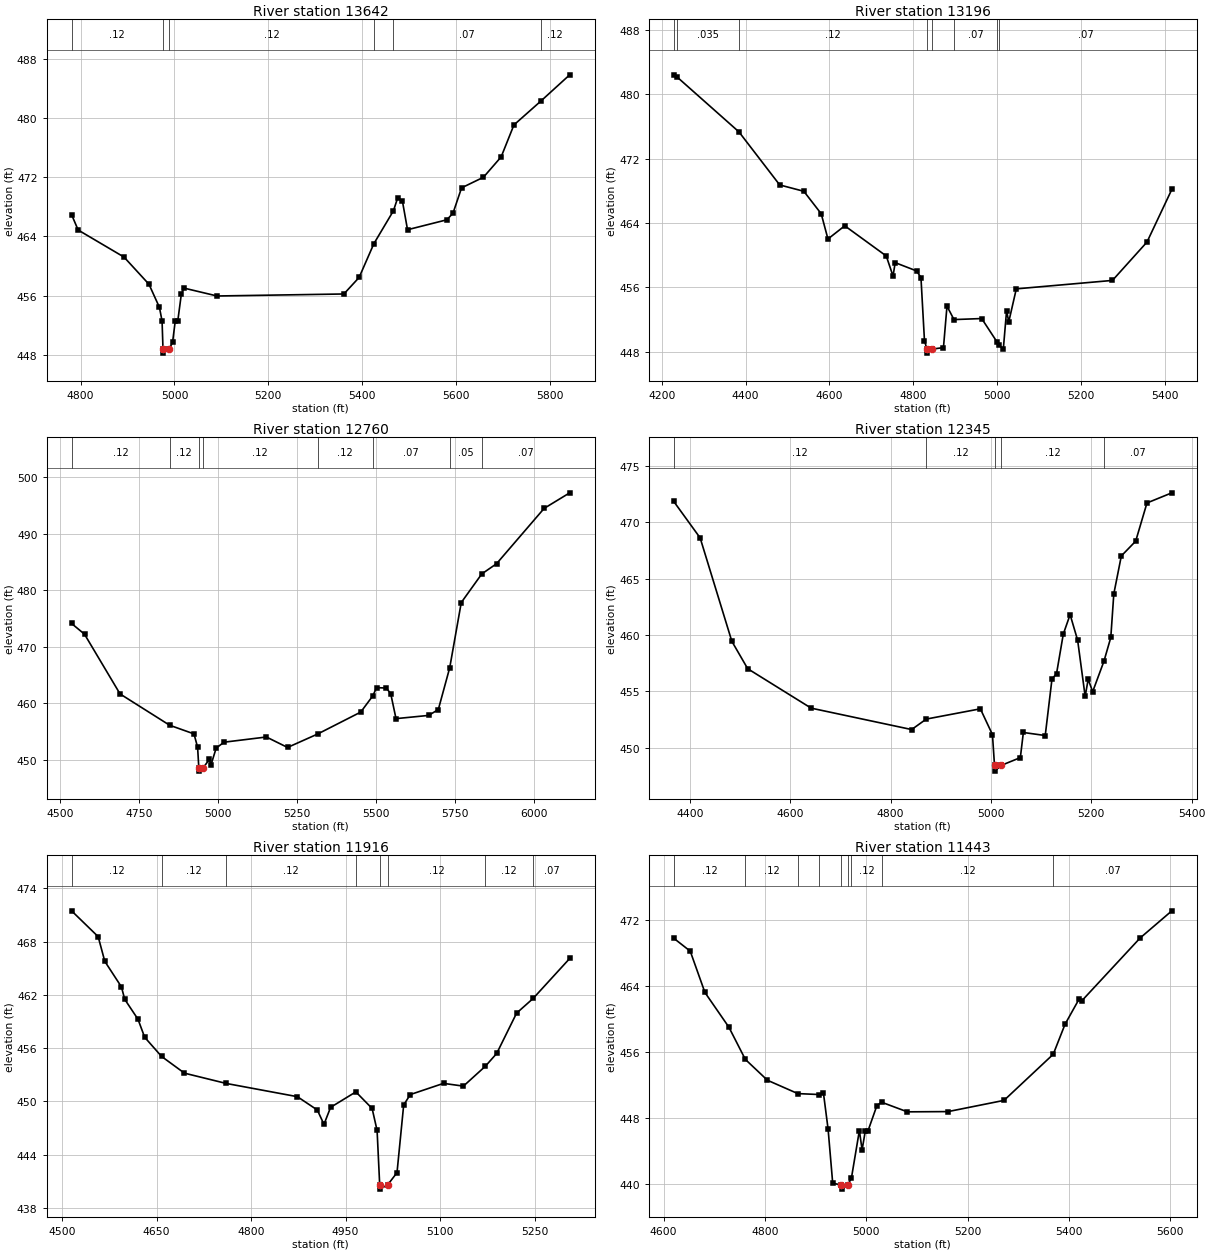
Type RM Length L Ch R = 1,13642,446,446,446
BEGIN DESCRIPTION:
SAUL CREEK 30.0
END DESCRIPTION:
XS GIS Cut Line= 3
      2328775.04     13752725.02      2328575.00     13752625.00
      2327775.00     13752375.00
#Sta/Elev= 30
  4780.7  466.94  4794.7  464.86  4892.5  461.21  4945.7  457.54  4968.0  454.42
  4973.6  452.58  4975.6  448.75  4976.1  448.25  4988.3  448.75  4996.0  449.71
  5001.6  452.55  5007.0  452.55  5014.8  456.28  5020.6  457.02  5090.8  455.96
  5361.1  456.23  5393.6  458.46  5425.0  463.01  5466.7  467.45  5475.8  469.19
  5485.8  468.80  5496.8  464.90  5580.6  466.24  5593.7  467.13  5612.0  470.55
  5658.6  471.98  5696.4  474.73  5723.6  479.04  5780.5  482.23  5842.5  485.80
#Mann=6,-1,0
  4780.7    0.12       0  4975.6    0.07       0  4988.3    0.12       0
  5425.0    0.12       0  5466.7    0.07       0  5780.5    0.12       0
Bank Sta=4975.6,4988.3
Exp/Cntr=0.3,0.1

Type RM Length L Ch R = 1,13196,436,436,436
BEGIN DESCRIPTION:
SAUL CREEK 29.0
END DESCRIPTION:
XS GIS Cut Line= 3
      2329274.98     13752524.99      2328525.00     13752325.00
      2328124.99     13752225.00
#Sta/Elev= 30
  4228.6  482.44  4235.3  482.23  4384.2  475.35  4481.5  468.75  4539.1  467.96
  4580.5  465.17  4596.6  462.03  4636.7  463.67  4735.7  459.92  4751.9  457.42
  4757.0  459.09  4808.1  458.06  4818.5  457.24  4826.9  449.38  4832.8  448.34
  4833.3  447.84  4845.5  448.34  4872.2  448.53  4880.6  453.68  4897.3  452.01
  4963.4  452.14  4999.6  449.26  5004.3  448.82  5015.1  448.39  5022.8  453.12
  5028.0  451.73  5046.0  455.83  5275.4  456.88  5357.8  461.65  5417.1  468.20
#Mann=8,-1,0
  4228.6    0.05       0  4235.3   0.035       0  4384.2    0.12       0
  4832.8    0.07       0  4845.5    0.12       0  4897.3    0.07       0
  4999.6    0.12       0  5004.3    0.07       0
Bank Sta=4832.8,4845.5
Exp/Cntr=0.3,0.1

Type RM Length L Ch R = 1,12760,415,415,415
BEGIN DESCRIPTION:
SAUL CREEK 28.0
END DESCRIPTION:
XS GIS Cut Line= 3
      2329175.00     13752125.00      2328725.00     13752025.00
      2327725.01     13751525.01
#Sta/Elev= 30
  4535.7  474.11  4576.7  472.21  4689.4  461.64  4846.6  456.10  4923.7  454.57
  4935.2  452.21  4939.1  448.48  4939.6  447.98  4951.9  448.48  4972.4  450.07
  4977.5  449.07  4994.1  452.06  5019.0  453.10  5153.2  454.02  5220.3  452.17
  5315.4  454.54  5452.3  458.43  5490.3  461.28  5502.6  462.76  5533.3  462.68
  5547.3  461.70  5564.1  457.27  5667.5  457.84  5698.2  458.88  5734.4  466.29
  5770.9  477.81  5836.0  482.88  5882.7  484.68  6033.7  494.48  6114.7  497.23
#Mann=8,-1,0
  4535.7    0.12       0  4846.6    0.12       0  4939.1    0.07       0
  4951.9    0.12       0  5315.4    0.12       0  5490.3    0.07       0
  5734.4    0.05       0  5836.0    0.07       0
Bank Sta=4939.1,4951.9
Exp/Cntr=0.3,0.1

Type RM Length L Ch R = 1,12345,429,429,429
BEGIN DESCRIPTION:
SAUL CREEK 27.0
END DESCRIPTION:
XS GIS Cut Line= 3
      2329174.97     13751924.99      2328575.00     13751725.00
      2328374.99     13751424.98
#Sta/Elev= 30
  4367.5  471.87  4420.2  468.63  4483.4  459.45  4515.0  457.02  4641.5  453.52
  4841.8  451.62  4871.0  452.55  4978.8  453.46  5002.9  451.17  5007.0  448.43
  5007.5  447.93  5019.9  448.43  5058.5  449.13  5064.5  451.36  5108.1  451.09
  5121.6  456.12  5130.6  456.57  5144.1  460.09  5157.7  461.82  5172.7  459.55
  5187.7  454.56  5193.7  456.08  5202.7  454.98  5225.1  457.68  5238.8  459.79
  5244.8  463.66  5259.8  467.03  5288.4  468.34  5310.9  471.73  5360.5  472.63
#Mann=5,-1,0
  4367.5    0.12       0  4871.0    0.12       0  5007.0    0.07       0
  5019.9    0.12       0  5225.1    0.07       0
Bank Sta=5007,5019.9
Exp/Cntr=0.3,0.1

Type RM Length L Ch R = 1,11916,473,473,473
BEGIN DESCRIPTION:
SAUL CREEK 26.0
END DESCRIPTION:
XS GIS Cut Line= 3
      2329275.03     13751575.01      2328825.00     13751425.00
      2328525.00     13751325.00
#Sta/Elev= 30
  4515.2  471.48  4557.4  468.57  4567.9  465.79  4594.3  462.91  4599.6  461.50
  4620.6  459.26  4631.2  457.23  4658.0  455.07  4694.4  453.18  4760.8  452.02
  4873.6  450.53  4905.2  449.03  4915.8  447.41  4926.3  449.33  4966.4  451.07
  4992.2  449.20  5000.1  446.72  5004.2  440.61  5004.7  440.11  5017.1  440.61
  5031.7  441.97  5042.3  449.60  5052.8  450.77  5105.5  452.03  5137.1  451.72
  5171.9  453.96  5189.9  455.40  5221.5  459.95  5247.7  461.60  5305.8  466.11
#Mann=8,-1,0
  4515.2    0.12       0  4658.0    0.12       0  4760.8    0.12       0
  4966.4    0.12       0  5004.2    0.07       0  5017.1    0.12       0
  5171.9    0.12       0  5247.7    0.07       0
Bank Sta=5004.2,5017.1
Exp/Cntr=0.3,0.1

Type RM Length L Ch R = 1,11443,478,478,478
BEGIN DESCRIPTION:
SAUL CREEK 25.0
END DESCRIPTION:
XS GIS Cut Line= 3
      2329374.98     13751274.99      2329025.00     13751125.00
      2328425.05     13751175.00
#Sta/Elev= 30
  4620.0  469.76  4652.6  468.19  4681.6  463.18  4728.8  458.98  4761.3  455.07
  4804.9  452.54  4864.9  450.92  4906.6  450.81  4915.5  450.95  4924.6  446.61
  4933.7  440.06  4950.7  439.84  4951.2  439.34  4963.7  439.84  4970.7  440.71
  4986.3  446.44  4991.7  444.10  4998.0  446.40  5003.3  446.40  5020.8  449.45
  5030.0  449.88  5081.0  448.71  5161.3  448.74  5271.7  450.10  5368.8  455.69
  5392.1  459.33  5419.7  462.37  5424.7  462.14  5540.1  469.78  5602.8  473.08
#Mann=9,-1,0
  4620.0    0.12       0  4761.3    0.12       0  4864.9    0.12       0
  4906.6    0.12       0  4950.7    0.07       0  4963.7    0.12       0
  4970.7    0.12       0  5030.0    0.12       0  5368.8    0.07       0
Bank Sta=4950.7,4963.7
Exp/Cntr=0.3,0.1

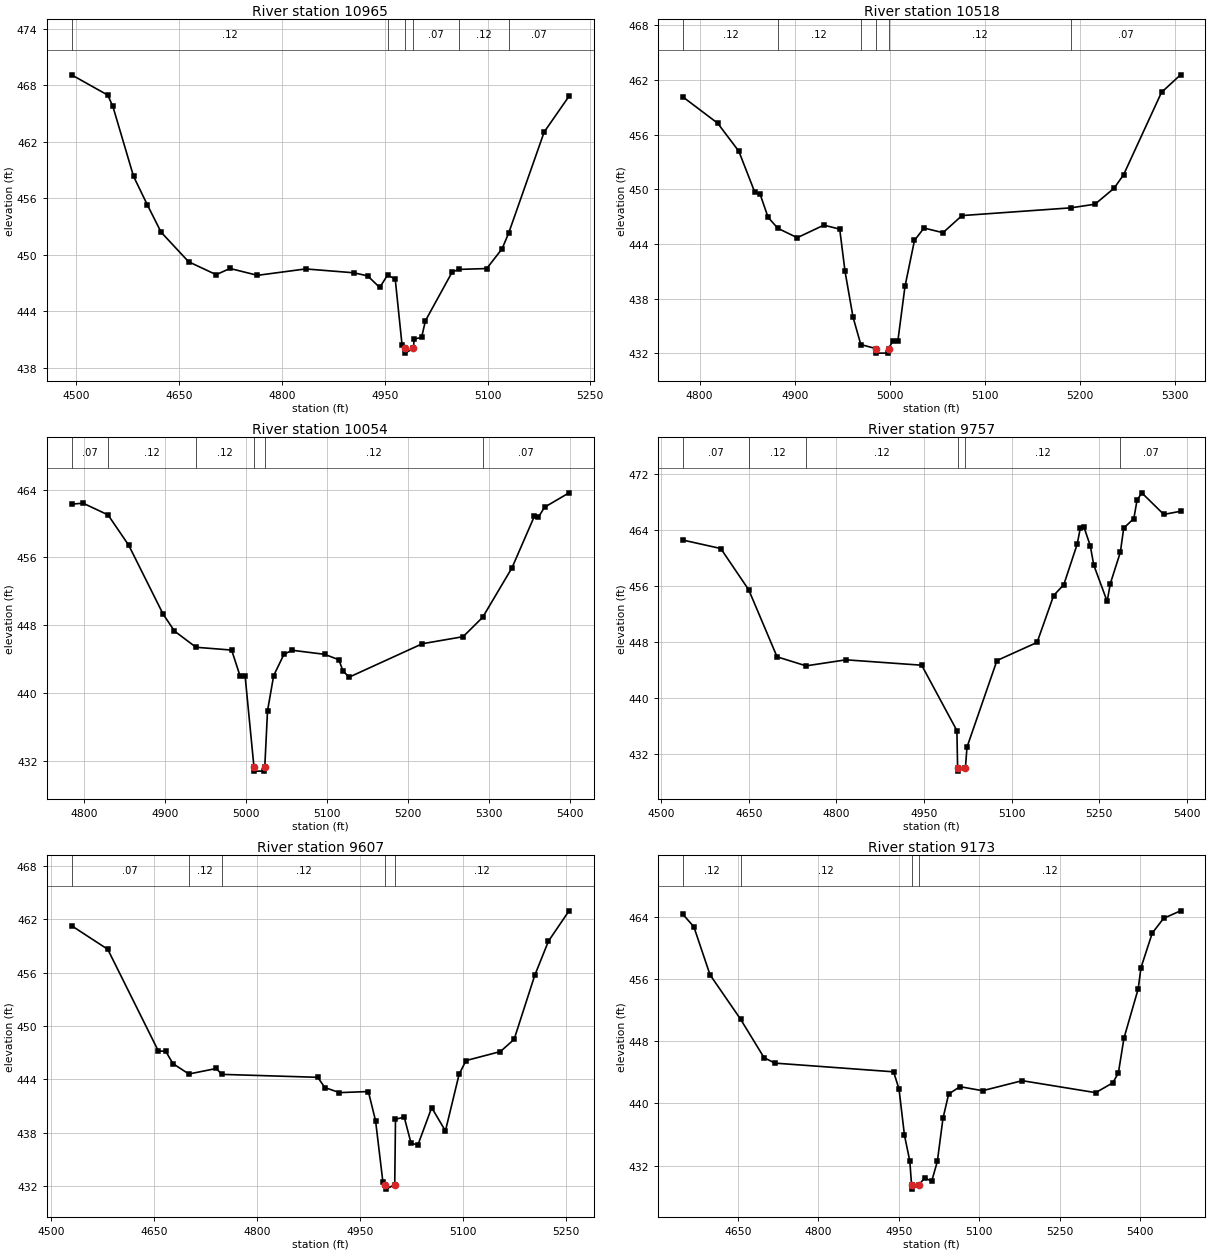
Type RM Length L Ch R = 1,10965,447,447,447
BEGIN DESCRIPTION:
SAUL CREEK 24.0
END DESCRIPTION:
XS GIS Cut Line= 3
      2329425.04     13750775.00      2328925.00     13750725.00
      2328725.03     13750625.02
#Sta/Elev= 30
  4492.9  469.12  4545.7  466.97  4553.2  465.77  4583.4  458.34  4603.5  455.32
  4623.6  452.41  4663.8  449.27  4704.0  447.90  4724.1  448.56  4764.3  447.83
  4834.6  448.51  4905.0  448.10  4925.1  447.77  4942.7  446.54  4954.1  447.86
  4965.3  447.44  4975.3  440.41  4978.9  440.07  4979.4  439.57  4991.9  440.07
  4992.9  441.06  5003.8  441.24  5009.4  443.01  5048.5  448.19  5058.5  448.46
  5098.8  448.55  5121.2  450.64  5130.8  452.30  5182.7  463.05  5219.0  466.85
#Mann=6,-1,0
  4492.9    0.12       0  4954.1    0.07       0  4978.9    0.07       0
  4991.9    0.07       0  5058.5    0.12       0  5130.8    0.07       0
Bank Sta=4978.9,4991.9
Exp/Cntr=0.3,0.1

Type RM Length L Ch R = 1,10518,464,464,464
BEGIN DESCRIPTION:
SAUL CREEK 23.0
END DESCRIPTION:
XS GIS Cut Line= 3
      2329375.03     13750475.01      2329175.00     13750375.00
      2328875.04     13750375.00
#Sta/Elev= 30
  4782.5  460.14  4818.9  457.27  4841.2  454.19  4858.0  449.69  4863.6  449.47
  4872.0  446.93  4882.3  445.72  4902.7  444.69  4930.7  446.07  4947.4  445.63
  4953.0  440.98  4961.4  435.97  4969.6  432.95  4985.5  432.51  4986.0  432.01
  4998.4  432.01  4998.9  432.51  5003.3  433.35  5008.6  433.35  5016.1  439.34
  5026.1  444.40  5036.1  445.75  5056.1  445.24  5076.1  447.12  5190.8  447.97
  5216.1  448.37  5236.1  450.12  5246.1  451.59  5286.1  460.66  5306.1  462.58
#Mann=6,-1,0
  4782.5    0.12       0  4882.3    0.12       0  4969.6    0.12       0
  4985.5    0.07       0  4998.9    0.12       0  5190.8    0.07       0
Bank Sta=4985.5,4998.9
Exp/Cntr=0.3,0.1

Type RM Length L Ch R = 1,10054,297,297,297
BEGIN DESCRIPTION:
SAUL CREEK 22.0
END DESCRIPTION:
XS GIS Cut Line= 3
      2329575.02     13750175.02      2329425.00     13750025.00
      2329024.98     13749975.00
#Sta/Elev= 30
  4784.1  462.27  4798.3  462.39  4829.2  461.01  4854.8  457.43  4897.3  449.31
  4911.4  447.30  4938.1  445.39  4982.1  445.06  4992.7  441.95  4998.8  441.95
  5009.7  431.28  5010.2  430.78  5022.6  430.78  5023.1  431.28  5026.5  437.91
  5034.1  442.05  5046.7  444.54  5056.7  445.04  5097.0  444.56  5114.7  443.92
  5119.7  442.62  5127.3  441.86  5218.0  445.81  5268.4  446.64  5292.6  448.93
  5328.8  454.76  5356.5  460.84  5361.6  460.75  5369.1  461.91  5399.4  463.61
#Mann=6,-1,0
  4784.1    0.07       0  4829.2    0.12       0  4938.1    0.12       0
  5009.7    0.07       0  5023.1    0.12       0  5292.6    0.07       0
Bank Sta=5009.7,5023.1
Exp/Cntr=0.3,0.1

Type RM Length L Ch R = 1,9757,150,150,150
BEGIN DESCRIPTION:
E20754
END DESCRIPTION:
XS GIS Cut Line= 3
      2329609.92     13750169.75      2329395.46     13749794.45
      2329014.83     13749617.53
#Sta/Elev= 30
  4537.3  462.54  4601.9  461.34  4649.8  455.45  4698.3  445.90  4748.0  444.61
  4816.4  445.47  4946.0  444.70  5006.3  435.38  5007.5  430.10  5008.0  429.60
  5020.9  430.10  5023.6  433.02  5074.9  445.37  5143.6  447.95  5172.0  454.64
  5189.4  456.19  5212.3  461.96  5217.8  464.31  5223.7  464.44  5234.7  461.74
  5240.7  458.98  5263.6  453.81  5269.1  456.35  5286.2  460.81  5292.0  464.25
  5309.3  465.61  5314.8  468.22  5322.9  469.28  5360.6  466.20  5389.3  466.65
#Mann=6,-1,0
  4537.3    0.07       0  4649.8    0.12       0  4748.0    0.12       0
  5007.5    0.07       0  5020.9    0.12       0  5286.2    0.07       0
Bank Sta=5007.5,5020.9
Exp/Cntr=0.3,0.1

Type RM Length L Ch R = 1,9607,434,434,434
BEGIN DESCRIPTION:
SAUL CREEK 21.0
END DESCRIPTION:
XS GIS Cut Line= 3
      2329625.00     13750125.01      2329475.00     13749675.00
      2329475.00     13749424.95
#Sta/Elev= 30
  4529.5  461.26  4582.2  458.61  4656.0  447.17  4666.5  447.17  4677.1  445.77
  4700.3  444.60  4740.3  445.22  4748.2  444.56  4887.9  444.23  4898.4  443.08
  4919.5  442.51  4961.7  442.63  4972.2  439.34  4982.8  432.50  4986.6  432.17
  4987.1  431.67  5000.1  432.17  5001.2  439.52  5013.9  439.76  5023.9  436.81
  5033.9  436.65  5053.9  440.82  5073.9  438.21  5093.9  444.59  5103.9  446.11
  5153.9  447.12  5173.9  448.49  5203.9  455.67  5223.9  459.52  5253.9  462.93
#Mann=5,-1,0
  4529.5    0.07       0  4700.3    0.12       0  4748.2    0.12       0
  4986.6    0.07       0  5000.1    0.12       0
Bank Sta=4986.6,5000.1
Exp/Cntr=0.3,0.1

Type RM Length L Ch R = 1,9173,260,260,260
BEGIN DESCRIPTION:
SAUL CREEK 20.0
END DESCRIPTION:
XS GIS Cut Line= 3
      2329925.00     13750125.04      2329875.00     13749675.00
      2329725.02     13749225.05
#Sta/Elev= 30
  4547.8  464.30  4568.0  462.71  4598.1  456.54  4654.9  450.84  4698.8  445.88
  4718.9  445.18  4940.2  444.06  4950.3  441.83  4960.4  435.91  4970.4  432.58
  4973.7  429.47  4974.2  428.97  4987.2  429.47  4998.1  430.45  5011.1  429.97
  5021.7  432.53  5032.2  438.08  5042.8  441.20  5063.9  442.15  5106.0  441.63
  5179.8  442.92  5316.8  441.38  5348.5  442.64  5359.0  443.89  5369.5  448.40
  5395.9  454.71  5401.2  457.46  5422.2  461.91  5443.3  463.80  5474.9  464.77
#Mann=4,-1,0
  4547.8    0.12       0  4654.9    0.12       0  4973.7    0.07       0
  4987.2    0.12       0
Bank Sta=4973.7,4987.2
Exp/Cntr=0.3,0.1

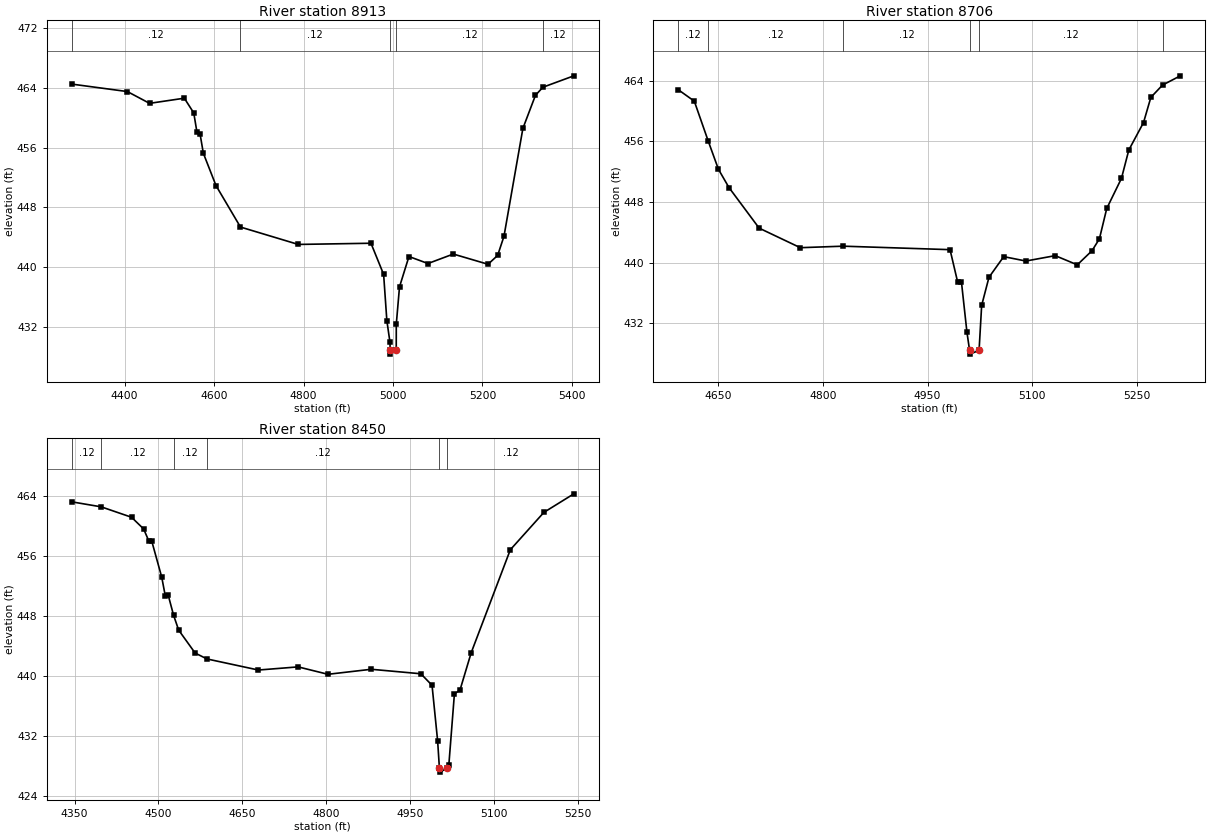
Type RM Length L Ch R = 1,8913,207,207,207
BEGIN DESCRIPTION:
E20752
END DESCRIPTION:
XS GIS Cut Line= 3
      2330510.55     13749955.25      2329953.02     13749413.81
      2329717.16     13749161.86
#Sta/Elev= 30
  4281.9  464.54  4406.2  463.54  4455.8  461.96  4533.5  462.65  4554.6  460.67
  4561.8  458.07  4568.8  457.81  4576.0  455.27  4604.3  450.93  4659.0  445.37
  4788.2  443.04  4950.7  443.20  4979.0  439.02  4986.2  432.83  4993.2  429.91
  4993.6  428.83  4994.1  428.33  5007.2  428.83  5007.3  432.35  5014.5  437.35
  5035.6  441.42  5078.1  440.48  5134.7  441.75  5212.4  440.38  5233.9  441.57
  5248.0  444.13  5290.3  458.60  5318.4  463.04  5335.0  464.12  5404.2  465.65
#Mann=5,-1,0
  4281.9    0.12       0  4659.0    0.12       0  4993.6    0.07       0
  5007.2    0.12       0  5335.0    0.12       0
Bank Sta=4993.6,5007.2
Exp/Cntr=0.3,0.1

Type RM Length L Ch R = 1,8706,256,256,256
BEGIN DESCRIPTION:
SAUL CREEK 19.0
END DESCRIPTION:
XS GIS Cut Line= 3
      2330424.98     13749474.99      2330075.00     13749275.00
      2329775.01     13749175.00
#Sta/Elev= 30
  4592.8  462.82  4615.8  461.31  4635.9  456.01  4650.4  452.32  4665.5  449.91
  4708.7  444.56  4767.7  441.98  4829.2  442.18  4982.2  441.72  4993.0  437.49
  4998.5  437.49  5006.4  430.84  5010.2  428.44  5010.7  427.94  5023.8  428.44
  5027.5  434.37  5038.0  438.08  5059.1  440.80  5090.8  440.22  5132.9  440.93
  5164.5  439.72  5185.6  441.58  5196.2  443.15  5206.7  447.15  5227.8  451.13
  5238.3  454.86  5259.4  458.49  5269.9  461.81  5286.6  463.43  5312.1  464.65
#Mann=6,-1,0
  4592.8    0.12       0  4635.9    0.12       0  4829.2    0.12       0
  5010.2    0.07       0  5023.8    0.12       0  5286.6    0.12       0
Bank Sta=5010.2,5023.8
Exp/Cntr=0.3,0.1

Type RM Length L Ch R = 1,8450,199,199,199
BEGIN DESCRIPTION:
E20753
END DESCRIPTION:
XS GIS Cut Line= 3
      2330633.92     13749263.71      2330070.97     13749033.17
      2329781.45     13749038.53
#Sta/Elev= 30
  4344.9  463.26  4397.6  462.59  4451.8  461.20  4473.4  459.64  4482.7  458.03
  4488.1  457.97  4505.8  453.19  4512.1  450.71  4517.5  450.76  4527.0  448.10
  4536.1  446.12  4565.5  443.06  4586.7  442.27  4678.7  440.79  4749.7  441.21
  4803.1  440.22  4880.5  440.89  4969.2  440.29  4989.2  438.75  4999.2  431.32
  5002.4  427.65  5002.9  427.15  5016.0  427.65  5019.2  428.07  5029.2  437.60
  5039.2  438.12  5059.2  443.10  5129.2  456.86  5189.2  461.85  5242.8  464.33
#Mann=6,-1,0
  4344.9    0.12       0  4397.6    0.12       0  4527.0    0.12       0
  4586.7    0.12       0  5002.4    0.07       0  5016.0    0.12       0
Bank Sta=5002.4,5016
Exp/Cntr=0.3,0.1