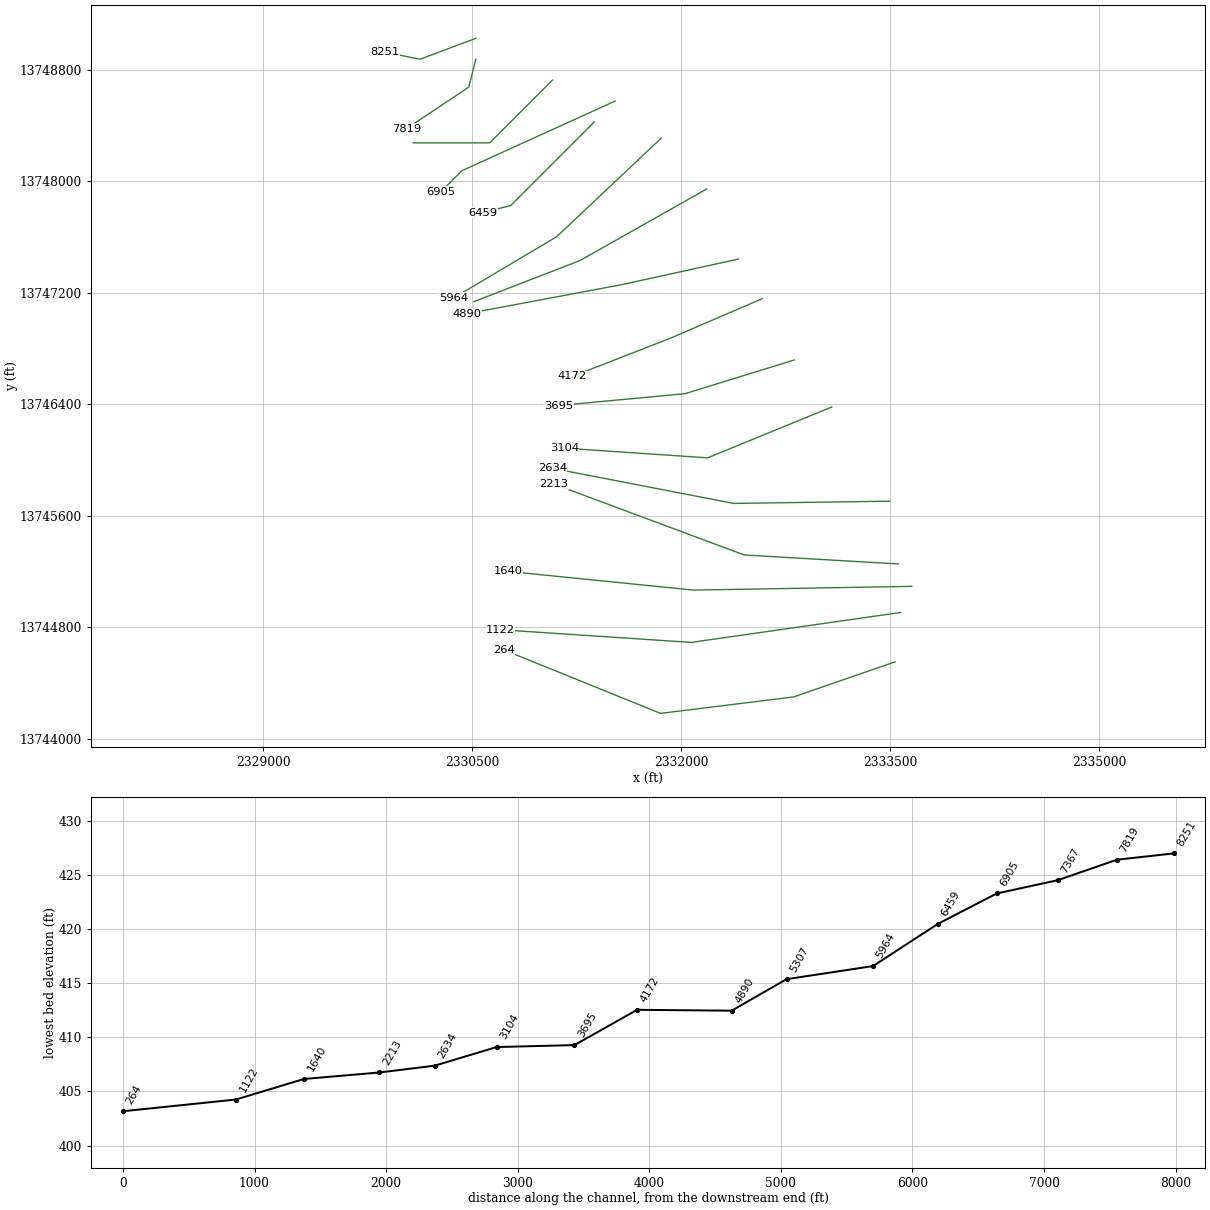
HEC-RAS study SAUL CREEK.prj: SAUL CREEK Base Level Engineering

--- SAUL CREEK.g01 (geometry) --- (continued)

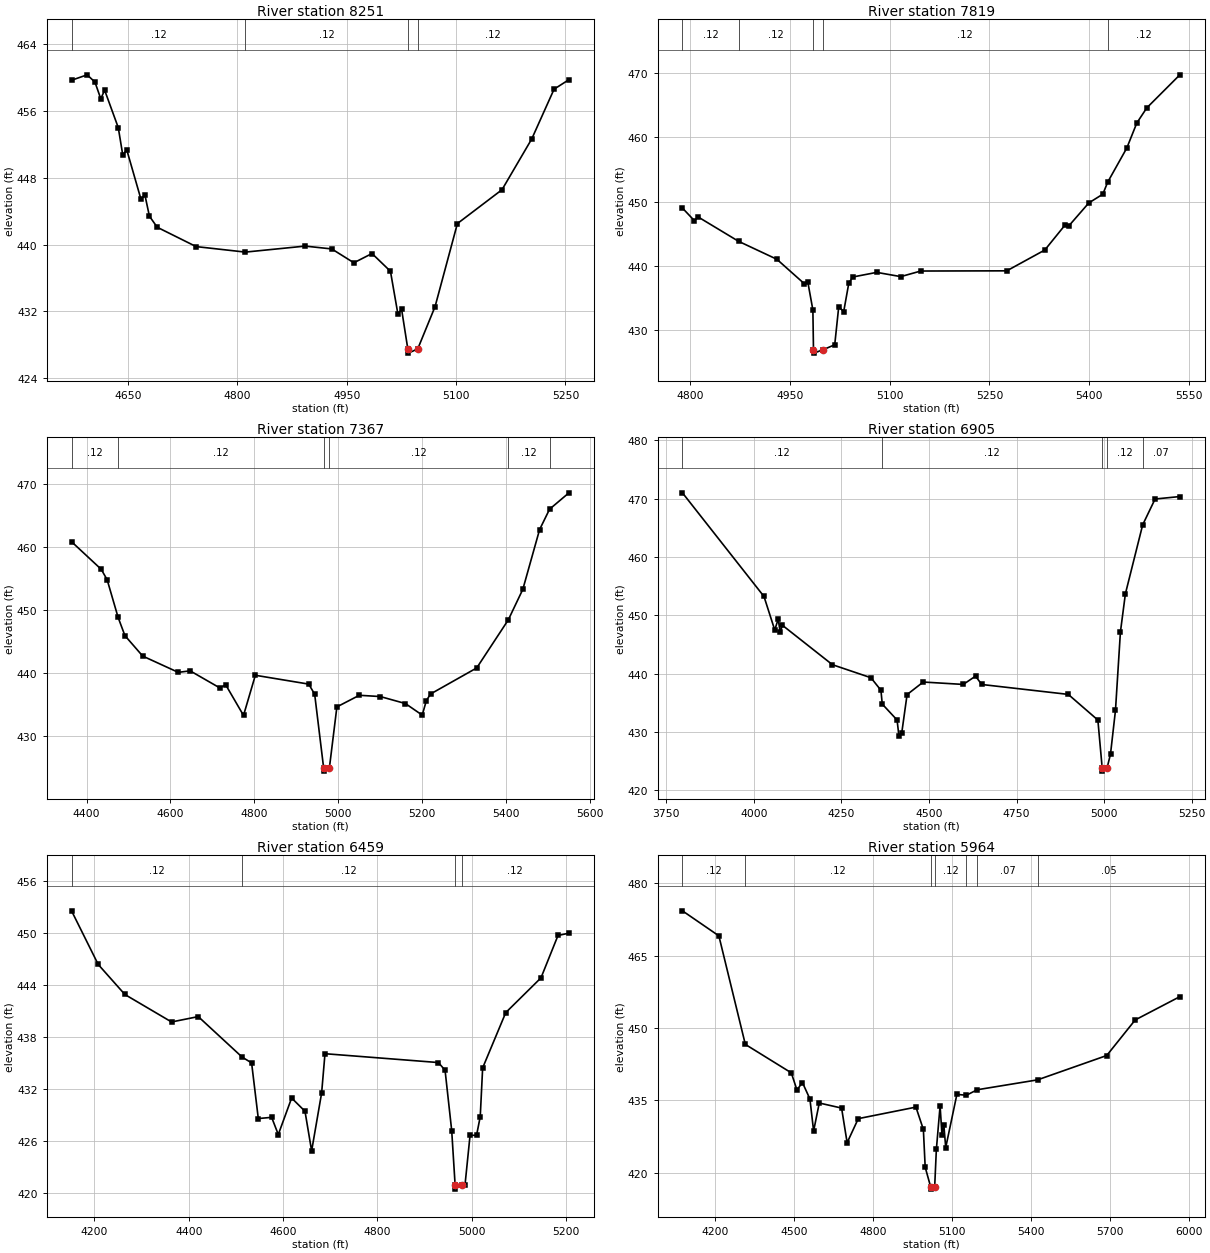
Type RM Length L Ch R = 1,8251,432,432,432
BEGIN DESCRIPTION:
SAUL CREEK 18.0
END DESCRIPTION:
XS GIS Cut Line= 3
      2330525.03     13749025.01      2330125.00     13748875.00
      2329874.99     13748925.00
#Sta/Elev= 30
  4572.7  459.70  4594.1  460.35  4604.8  459.48  4612.8  457.48  4618.1  458.51
  4636.8  454.02  4643.0  450.72  4648.4  451.37  4668.0  445.41  4673.3  445.96
  4679.5  443.41  4690.2  442.08  4743.6  439.76  4811.1  439.10  4893.1  439.82
  4929.6  439.48  4959.9  437.82  4984.8  438.93  5010.1  436.80  5020.3  431.68
  5025.4  432.23  5033.9  427.49  5034.4  426.99  5047.5  427.49  5071.3  432.57
  5101.9  442.52  5163.1  446.58  5203.9  452.67  5234.5  458.63  5254.9  459.77
#Mann=4,-1,0
  4572.7    0.12       0  4811.1    0.12       0  5033.9    0.07       0
  5047.5    0.12       0
Bank Sta=5033.9,5047.5
Exp/Cntr=0.3,0.1

Type RM Length L Ch R = 1,7819,452,452,452
BEGIN DESCRIPTION:
SAUL CREEK 17.0
END DESCRIPTION:
XS GIS Cut Line= 3
      2330525.01     13748875.03      2330475.00     13748675.00
      2330025.02     13748375.01
#Sta/Elev= 30
  4789.0  448.99  4807.1  447.01  4812.2  447.63  4873.2  443.82  4930.8  441.02
  4972.0  437.22  4977.2  437.53  4984.9  433.13  4985.8  426.91  4986.3  426.41
  4999.5  426.91  5017.7  427.71  5023.7  433.61  5031.2  432.88  5038.8  437.28
  5044.8  438.26  5080.8  438.98  5116.9  438.32  5146.9  439.19  5276.1  439.22
  5333.2  442.46  5363.3  446.31  5369.3  446.22  5399.3  449.79  5420.3  451.15
  5427.7  453.04  5456.4  458.35  5471.4  462.24  5486.4  464.59  5536.0  469.73
#Mann=5,-1,0
  4789.0    0.12       0  4873.2    0.12       0  4985.8    0.07       0
  4999.5    0.12       0  5427.7    0.12       0
Bank Sta=4985.8,4999.5
Exp/Cntr=0.3,0.1

Type RM Length L Ch R = 1,7367,462,462,462
BEGIN DESCRIPTION:
SAUL CREEK 16.0
END DESCRIPTION:
XS GIS Cut Line= 3
      2331075.03     13748725.03      2330625.00     13748275.00
      2330075.04     13748275.00
#Sta/Elev= 30
  4364.3  460.84  4435.1  456.47  4449.2  454.82  4475.3  448.87  4491.6  445.97
  4534.0  442.73  4618.9  440.15  4647.2  440.39  4717.9  437.69  4732.0  438.18
  4774.5  433.33  4802.7  439.69  4930.0  438.29  4944.2  436.69  4965.6  425.01
  4966.1  424.51  4979.3  425.01  4997.2  434.68  5050.7  436.52  5100.7  436.32
  5160.7  435.21  5200.7  433.38  5210.7  435.69  5220.7  436.73  5330.7  440.85
  5406.0  448.46  5440.7  453.30  5480.7  462.76  5504.5  465.99  5550.7  468.58
#Mann=6,-1,0
  4364.3    0.12       0  4475.3    0.12       0  4965.6    0.07       0
  4979.3    0.12       0  5406.0    0.12       0  5504.5    0.07       0
Bank Sta=4965.6,4979.3
Exp/Cntr=0.3,0.1

Type RM Length L Ch R = 1,6905,446,446,446
BEGIN DESCRIPTION:
SAUL CREEK 15.0
END DESCRIPTION:
XS GIS Cut Line= 3
      2331525.00     13748575.00      2330425.00     13748075.00
      2330275.03     13747925.03
#Sta/Elev= 30
  3795.8  471.02  4028.7  453.24  4059.4  447.49  4069.3  449.37  4074.8  447.17
  4081.4  448.30  4224.2  441.54  4334.0  439.31  4362.6  437.16  4366.4  434.79
  4408.7  432.06  4414.2  429.23  4421.9  429.77  4437.3  436.42  4483.4  438.57
  4597.7  438.16  4632.8  439.58  4650.4  438.15  4897.6  436.45  4982.1  432.05
  4994.5  423.79  4995.0  423.29  5008.2  423.79  5018.2  426.22  5032.4  433.73
  5046.5  447.16  5060.7  453.70  5110.0  465.52  5145.5  469.96  5216.2  470.38
#Mann=5,-1,0
  3795.8    0.12       0  4366.4    0.12       0  4994.5    0.07       0
  5008.2    0.12       0  5110.0    0.07       0
Bank Sta=4994.5,5008.2
Exp/Cntr=0.3,0.1

Type RM Length L Ch R = 1,6459,495,495,495
BEGIN DESCRIPTION:
SAUL CREEK 14.0
END DESCRIPTION:
XS GIS Cut Line= 3
      2331375.00     13748425.00      2330775.00     13747825.00
      2330574.98     13747775.00
#Sta/Elev= 30
  4151.4  452.59  4208.0  446.40  4264.5  442.94  4363.5  439.77  4420.1  440.39
  4513.1  435.72  4533.2  435.05  4547.4  428.63  4575.7  428.77  4589.8  426.79
  4618.1  431.00  4646.4  429.47  4660.5  424.90  4681.7  431.59  4688.8  436.11
  4929.2  435.09  4943.4  434.21  4957.5  427.24  4964.7  420.99  4965.2  420.49
  4978.5  420.99  4985.8  421.02  4996.4  426.70  5010.2  426.70  5018.0  428.85
  5023.1  434.47  5072.1  440.85  5146.8  444.86  5182.9  449.75  5206.1  450.01
#Mann=4,-1,0
  4151.4    0.12       0  4513.1    0.12       0  4964.7    0.07       0
  4978.5    0.12       0
Bank Sta=4964.7,4978.5
Exp/Cntr=0.3,0.1

Type RM Length L Ch R = 1,5964,657,657,657
BEGIN DESCRIPTION:
E20751
END DESCRIPTION:
XS GIS Cut Line= 3
      2331856.21     13748309.39      2331105.67     13747601.74
      2330365.86     13747162.14
#Sta/Elev= 30
  4074.7  474.30  4213.3  469.11  4313.9  446.60  4488.8  440.70  4510.2  437.16
  4531.2  438.68  4559.6  435.28  4573.7  428.64  4595.2  434.44  4680.1  433.39
  4701.2  426.21  4743.6  431.20  4962.9  433.59  4991.2  428.95  4998.1  421.13
  5018.7  417.08  5019.2  416.58  5034.2  417.08  5040.6  424.82  5054.8  433.84
  5062.1  427.74  5068.9  429.95  5076.2  425.21  5118.7  436.23  5154.8  436.05
  5196.0  437.19  5425.4  439.24  5688.6  444.29  5797.0  451.67  5966.8  456.50
#Mann=7,-1,0
  4074.7    0.12       0  4313.9    0.12       0  5018.7    0.07       0
  5034.2    0.12       0  5154.8    0.12       0  5196.0    0.07       0
  5425.4    0.05       0
Bank Sta=5018.7,5034.2
Exp/Cntr=0.3,0.1

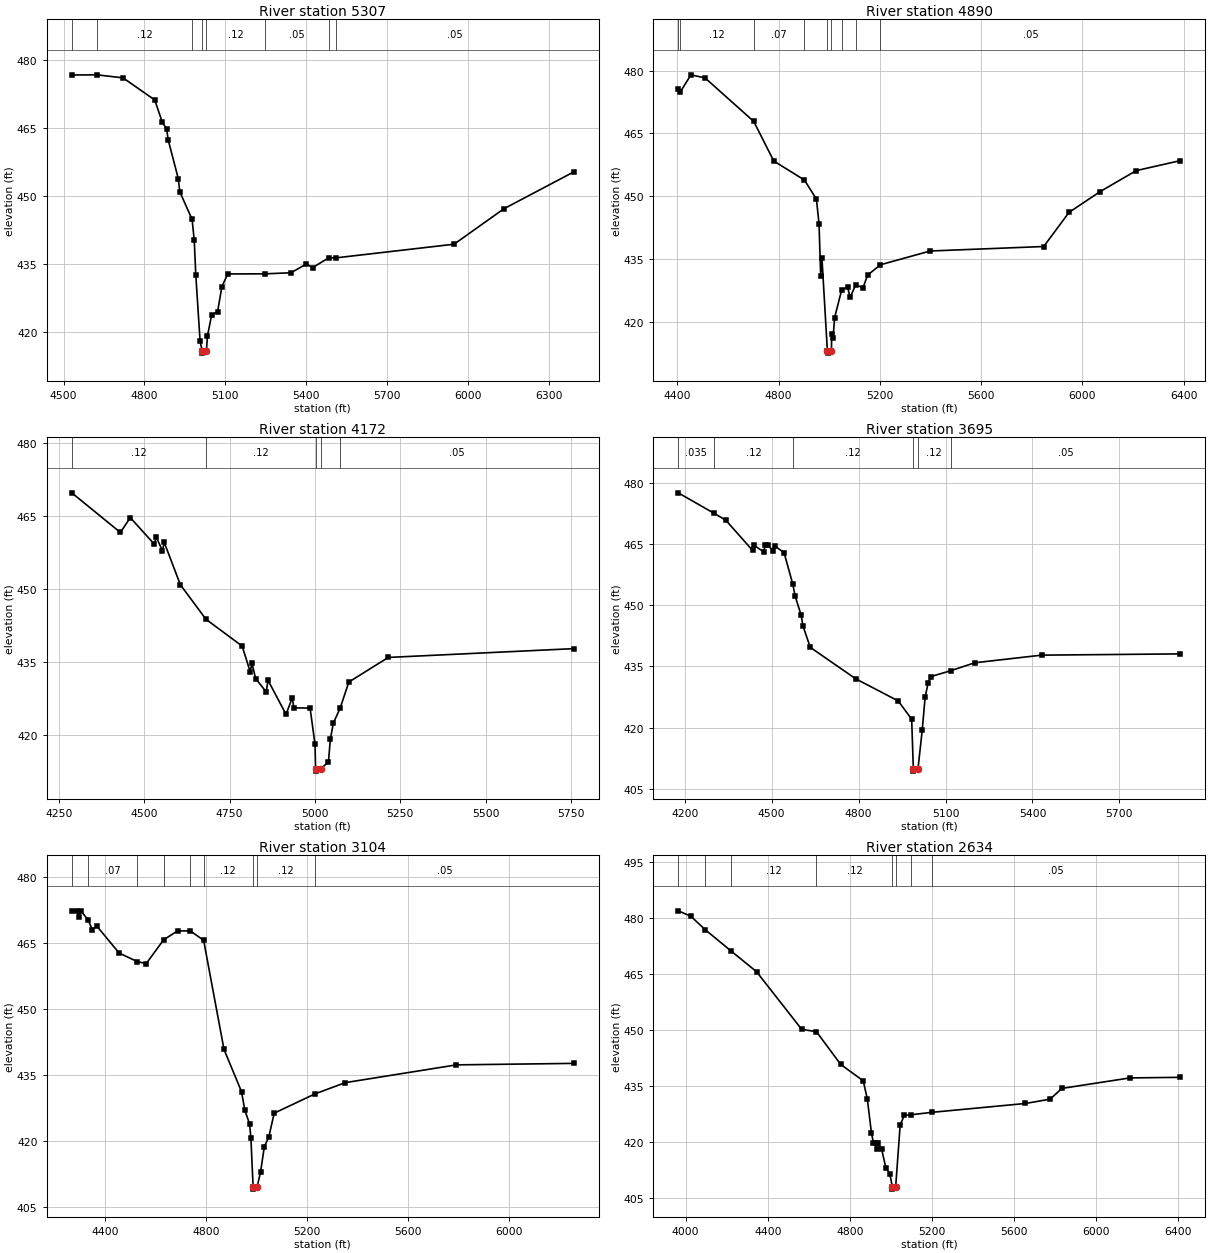
Type RM Length L Ch R = 1,5307,417,417,417
BEGIN DESCRIPTION:
E20750
END DESCRIPTION:
XS GIS Cut Line= 3
      2332183.23     13747944.84      2331271.87     13747430.18
      2330510.61     13747135.33
#Sta/Elev= 30
  4530.2  476.70  4623.4  476.74  4720.4  476.07  4838.2  471.19  4866.2  466.25
  4882.1  464.86  4887.8  462.44  4925.4  453.85  4931.1  450.95  4976.7  444.84
  4984.6  440.30  4990.4  432.61  5006.3  418.01  5014.1  415.87  5014.6  415.37
  5029.8  415.87  5033.7  419.20  5049.6  423.86  5071.2  424.45  5087.1  430.00
  5108.8  432.83  5249.0  432.86  5343.6  433.09  5401.0  435.04  5423.9  434.22
  5484.2  436.42  5509.3  436.37  5948.8  439.39  6133.8  447.21  6393.2  455.34
#Mann=8,-1,0
  4530.2    0.07       0  4623.4    0.12       0  4976.7    0.12       0
  5014.1    0.07       0  5029.8    0.12       0  5249.0    0.05       0
  5484.2    0.12       0  5509.3    0.05       0
Bank Sta=5014.1,5029.8
Exp/Cntr=0.3,0.1

Type RM Length L Ch R = 1,4890,718,718,718
BEGIN DESCRIPTION:
E20749
END DESCRIPTION:
XS GIS Cut Line= 3
      2332408.44     13747440.91      2331577.45     13747258.63
      2330463.51     13747049.76
#Sta/Elev= 30
  4403.2  475.59  4411.3  474.91  4453.4  479.00  4509.1  478.26  4701.7  467.85
  4780.6  458.40  4902.0  453.84  4949.3  449.28  4959.6  443.38  4966.1  431.00
  4971.2  435.09  4992.6  412.96  4993.1  412.46  5008.4  412.96  5009.9  416.94
  5015.0  415.97  5021.0  420.90  5049.1  427.58  5072.2  428.33  5082.4  425.77
  5104.2  428.75  5133.6  428.14  5151.6  431.11  5202.5  433.59  5398.9  436.88
  5847.5  437.95  5947.6  446.12  6070.4  451.08  6212.8  456.09  6387.3  458.49
#Mann=9,-1,0
  4403.2    0.07       0  4411.3    0.12       0  4701.7    0.07       0
  4902.0    0.12       0  4992.6    0.07       0  5008.4    0.12       0
  5049.1    0.12       0  5104.2    0.12       0  5202.5    0.05       0
Bank Sta=4992.6,5008.4
Exp/Cntr=0.3,0.1

Type RM Length L Ch R = 1,4172,477,477,477
BEGIN DESCRIPTION:
SAUL CREEK 9.0
END DESCRIPTION:
XS GIS Cut Line= 3
      2332579.94     13747156.75      2331925.00     13746875.00
      2331218.28     13746599.21
#Sta/Elev= 30
  4287.3  469.70  4429.8  461.56  4458.8  464.61  4529.4  459.14  4534.9  460.62
  4553.0  457.82  4558.4  459.51  4605.5  450.83  4680.6  443.73  4786.6  438.23
  4810.1  432.99  4815.6  434.65  4826.1  431.55  4857.2  428.82  4862.6  431.18
  4915.2  424.21  4933.3  427.52  4938.7  425.54  4985.8  425.48  5000.3  418.04
  5001.9  413.04  5002.4  412.54  5017.7  413.04  5039.7  414.47  5045.1  419.05
  5053.9  422.39  5074.1  425.52  5099.4  430.84  5215.0  435.89  5758.9  437.70
#Mann=5,-1,0
  4287.3    0.12       0  4680.6    0.12       0  5001.9    0.07       0
  5017.7    0.12       0  5074.1    0.05       0
Bank Sta=5001.9,5017.7
Exp/Cntr=0.3,0.1

Type RM Length L Ch R = 1,3695,591,591,591
BEGIN DESCRIPTION:
SAUL CREEK 8.0
END DESCRIPTION:
XS GIS Cut Line= 3
      2332810.50     13746717.15      2332025.00     13746475.00
      2331118.22     13746390.29
#Sta/Elev= 30
  4177.5  477.67  4301.7  472.62  4341.5  470.95  4434.3  463.50  4439.5  464.74
  4472.2  463.18  4477.4  464.80  4486.7  464.80  4504.8  463.46  4510.1  464.63
  4542.7  462.98  4572.8  455.23  4580.9  452.29  4601.8  447.58  4608.1  444.91
  4633.2  439.69  4790.2  431.96  4936.7  426.53  4983.1  422.04  4988.9  409.78
  4989.4  409.28  5004.8  409.78  5019.6  419.39  5029.6  427.51  5039.7  430.86
  5049.0  432.51  5117.7  433.95  5200.3  435.90  5431.3  437.78  5910.2  438.09
#Mann=6,-1,0
  4177.5   0.035       0  4301.7    0.12       0  4572.8    0.12       0
  4988.9    0.07       0  5004.8    0.12       0  5117.7    0.05       0
Bank Sta=4988.9,5004.8
Exp/Cntr=0.3,0.1

Type RM Length L Ch R = 1,3104,470,470,470
BEGIN DESCRIPTION:
E20748
END DESCRIPTION:
XS GIS Cut Line= 3
      2333078.53     13746379.38      2332188.62     13746014.84
      2331159.65     13746084.51
#Sta/Elev= 30
  4266.2  472.19  4288.6  472.13  4294.0  470.86  4302.4  472.24  4332.1  470.08
  4347.4  467.97  4366.0  468.75  4454.2  462.66  4525.8  460.73  4561.8  460.27
  4631.0  465.68  4686.4  467.69  4736.1  467.69  4789.6  465.57  4870.5  440.79
  4940.0  431.22  4953.3  426.97  4971.9  423.92  4977.3  420.70  4986.0  409.60
  4986.5  409.10  5002.0  409.60  5015.7  413.03  5030.7  418.75  5048.1  420.88
  5069.7  426.33  5231.3  430.70  5351.8  433.26  5792.8  437.29  6259.2  437.63
#Mann=9,-1,0
  4266.2    0.05       0  4332.1    0.07       0  4525.8   0.035       0
  4631.0    0.12       0  4736.1    0.12       0  4789.6    0.12       0
  4986.0    0.07       0  5002.0    0.12       0  5231.3    0.05       0
Bank Sta=4986,5002
Exp/Cntr=0.3,0.1

Type RM Length L Ch R = 1,2634,421,421,421
BEGIN DESCRIPTION:
E20747
END DESCRIPTION:
XS GIS Cut Line= 3
      2333496.73     13745703.89      2332376.26     13745687.81
      2331073.49     13745939.79
#Sta/Elev= 30
  3963.7  481.96  4025.4  480.50  4095.2  476.90  4222.3  471.15  4345.5  465.64
  4565.5  450.20  4637.3  449.58  4755.5  440.81  4865.5  436.40  4885.5  431.53
  4905.5  422.44  4915.5  419.74  4925.5  419.72  4931.2  418.22  4936.2  419.80
  4955.5  418.05  4975.5  413.16  4995.5  411.44  5007.5  407.88  5008.0  407.38
  5023.5  407.88  5045.5  424.53  5065.5  427.16  5097.5  427.30  5198.4  427.95
  5655.9  430.33  5776.7  431.49  5833.6  434.37  6165.2  437.18  6411.2  437.34
#Mann=8,-1,0
  3963.7   0.035       0  4095.2    0.07       0  4222.3    0.12       0
  4637.3    0.12       0  5007.5    0.07       0  5023.5    0.12       0
  5097.5    0.12       0  5198.4    0.05       0
Bank Sta=5007.5,5023.5
Exp/Cntr=0.3,0.1

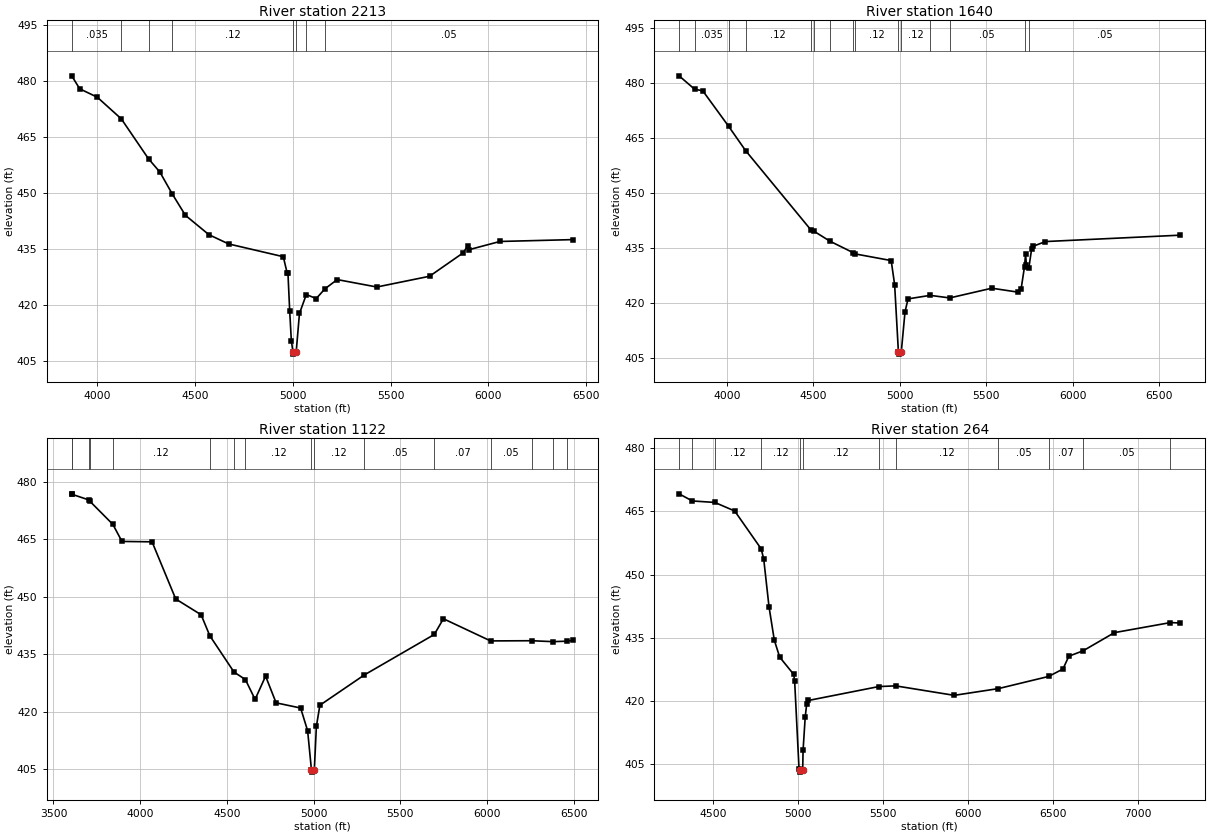
Type RM Length L Ch R = 1,2213,573,573,573
BEGIN DESCRIPTION:
E20746
END DESCRIPTION:
XS GIS Cut Line= 3
      2333555.70     13745253.56      2332451.32     13745317.89
      2331084.26     13745827.19
#Sta/Elev= 30
  3868.3  481.38  3909.1  477.90  3999.2  475.64  4122.0  469.84  4261.4  459.11
  4318.9  455.61  4382.6  449.71  4450.0  443.97  4570.2  438.78  4671.1  436.30
  4950.8  432.88  4970.2  428.60  4974.6  428.60  4983.6  418.34  4992.0  410.40
  5000.6  407.25  5001.1  406.75  5016.7  407.25  5033.6  417.66  5068.7  422.73
  5119.3  421.65  5164.0  424.26  5226.7  426.74  5429.5  424.75  5699.2  427.63
  5870.5  433.88  5895.5  435.85  5900.8  434.75  6059.1  436.96  6433.4  437.46
#Mann=8,-1,0
  3868.3   0.035       0  4122.0    0.07       0  4261.4    0.12       0
  4382.6    0.12       0  5000.6    0.07       0  5016.7    0.12       0
  5068.7    0.12       0  5164.0    0.05       0
Bank Sta=5000.6,5016.7
Exp/Cntr=0.3,0.1

Type RM Length L Ch R = 1,1640,518,518,518
BEGIN DESCRIPTION:
E20745
END DESCRIPTION:
XS GIS Cut Line= 3
      2333652.24     13745092.72      2332086.76     13745065.92
      2330758.60     13745199.81
#Sta/Elev= 30
  3723.4  481.97  3813.3  478.33  3860.7  477.88  4010.1  468.22  4108.5  461.59
  4484.9  440.07  4505.8  439.58  4596.7  436.91  4730.0  433.81  4742.5  433.45
  4950.8  431.64  4970.8  425.06  4992.7  406.65  4993.2  406.15  5009.0  406.65
  5030.8  417.67  5048.3  421.20  5176.4  422.16  5289.7  421.46  5533.2  424.11
  5682.9  423.05  5703.0  424.02  5722.3  430.01  5728.3  433.43  5733.4  430.39
  5746.9  429.50  5763.3  434.77  5773.3  435.56  5843.7  436.82  6624.0  438.56
#Mann=15,-1,0
  3723.4    0.07       0  3813.3   0.035       0  4010.1    0.07       0
  4108.5    0.12       0  4484.9    0.12       0  4505.8    0.12       0
  4596.7    0.12       0  4730.0    0.12       0  4742.5    0.12       0
  4992.7    0.07       0  5009.0    0.12       0  5176.4    0.12       0
  5289.7    0.05       0  5722.3    0.12       0  5746.9    0.05       0
Bank Sta=4992.7,5009
Exp/Cntr=0.3,0.1

Type RM Length L Ch R = 1,1122,858,858,858
BEGIN DESCRIPTION:
E20744
END DESCRIPTION:
XS GIS Cut Line= 3
      2333571.75     13744905.08      2332070.68     13744690.64
      2330699.11     13744781.72
#Sta/Elev= 30
  3605.4  476.79  3609.3  476.63  3704.2  475.20  3708.4  474.93  3842.5  468.83
  3895.1  464.38  4068.7  464.28  4205.1  449.38  4351.5  445.27  4401.7  439.80
  4541.3  430.33  4606.7  428.39  4662.8  423.21  4723.4  429.27  4784.0  422.31
  4925.4  420.96  4965.8  415.04  4988.0  404.75  4988.5  404.25  5004.3  404.75
  5016.3  416.18  5036.5  421.69  5292.8  429.58  5696.3  440.13  5748.8  444.23
  6020.9  438.45  6257.9  438.50  6380.4  438.26  6461.2  438.38  6496.3  438.61
#Mann=16,-1,0
  3605.4    0.05       0  3609.3    0.07       0  3704.2    0.05       0
  3708.4   0.035       0  3842.5    0.12       0  4401.7    0.12       0
  4541.3    0.12       0  4606.7    0.12       0  4988.0    0.07       0
  5004.3    0.12       0  5292.8    0.05       0  5696.3    0.07       0
  6020.9    0.05       0  6257.9    0.12       0  6380.4    0.05       0
  6461.2    0.12       0
Bank Sta=4988,5004.3
Exp/Cntr=0.3,0.1

Type RM Length L Ch R = 1,264,0,0,0
BEGIN DESCRIPTION:
E20743
END DESCRIPTION:
XS GIS Cut Line= 4
      2333534.25     13744551.24      2332805.15     13744299.27
      2331850.87     13744181.33      2330725.04     13744637.02
#Sta/Elev= 30
  4299.2  469.14  4377.2  467.45  4509.3  467.10  4626.4  465.07  4781.9  456.10
  4796.9  453.71  4828.1  442.37  4859.3  434.44  4890.9  430.43  4973.4  426.33
  4978.7  424.84  5004.6  403.92  5009.7  403.67  5010.2  403.17  5026.1  403.67
  5028.4  408.35  5041.0  416.28  5049.6  419.29  5060.2  420.16  5473.3  423.45
  5572.1  423.62  5917.1  421.37  6176.9  422.97  6472.0  425.85  6556.3  427.61
  6591.2  430.65  6674.9  431.93  6859.3  436.24  7188.5  438.62  7246.7  438.52
#Mann=12,-1,0
  4299.2    0.05       0  4377.2   0.035       0  4509.3    0.12       0
  4781.9    0.12       0  5009.7    0.07       0  5026.1    0.12       0
  5473.3    0.12       0  5572.1    0.12       0  6176.9    0.05       0
  6472.0    0.07       0  6674.9    0.05       0  7188.5    0.12       0
Bank Sta=5009.7,5026.1
Exp/Cntr=0.3,0.1

Chan Stop Cuts=-1