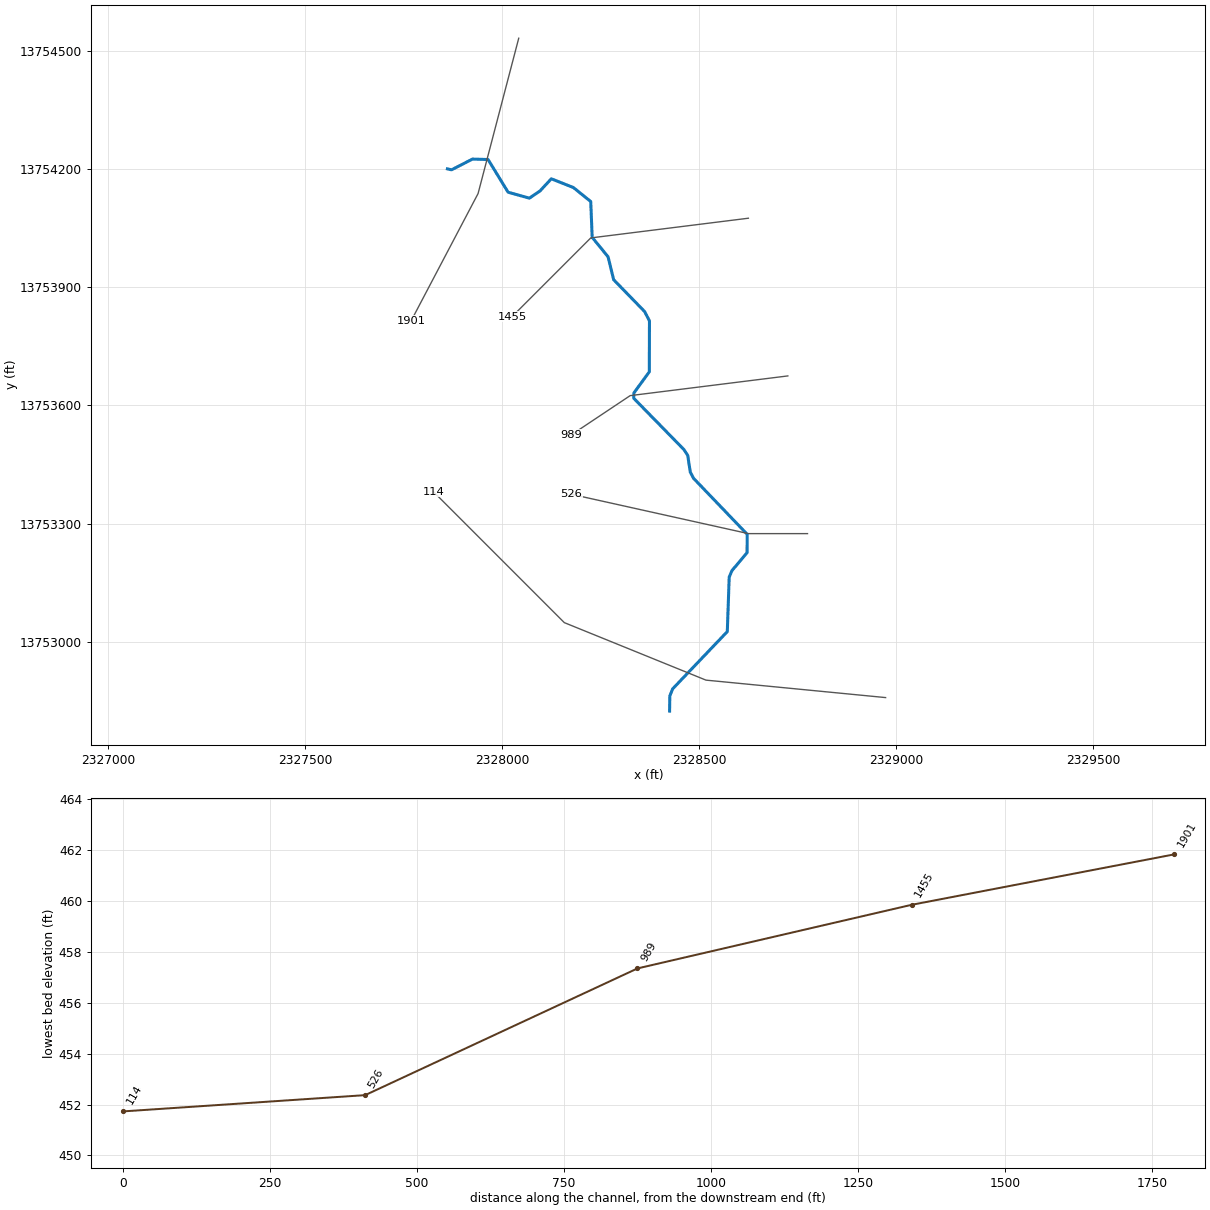
--- SAUL TRIBUTARY 1.prj (project) ---

Proj Title=SAUL TRIBUTARY 1 Base Level Engineering
Current Plan=p01
Default Exp/Contr=0.3,0.1
English Units
Geom File=g01
Flow File=f01
Plan File=p01
BEGIN DESCRIPTION:
SAUL TRIBUTARY 1
END DESCRIPTION:

--- SAUL TRIBUTARY 1.p01 (plan) ---

Plan Title=Multiple Run
Short Identifier=Multiple
Geom File=g01
Flow File=f01
Subcritical Flow
K Sum by GR= 0
Std Step Tol= 0.01
Critical Tol= 0.01
Num of Std Step Trials= 20
Max Error Tol= 0.3
Flow Tol Ratio= 0.001
Split Flow NTrial= 30
Split Flow Tol= 0.02
Split Flow Ratio= 0.02
Log Output Level= 0
Friction Slope Method= 1
Unsteady Friction Slope Method= 2
Unsteady Bridges Friction Slope Method= 1
Parabolic Critical Depth
Global Vel Dist=  1 , 1 , 1
Global Log Level= 0
CheckData=True
Encroach Param= -1, 0, 0, 0
BEGIN DESCRIPTION:
Multiple Run
END DESCRIPTION:

--- SAUL TRIBUTARY 1.f01 (steady flow) ---

Flow Title=Multiple
Number of Profiles=7
Profile Names=10-year,25-year,50-year,1pct_min,100-year,1pct_plu,500-year
River Rch & RM= SAUL TRIBUTARY 1,Reach-1,1901
     553     882    1175     758    1512    3017    2482
River Rch & RM= SAUL TRIBUTARY 1,Reach-1,1455
     931    1530    2080    1367    2727    5441    4650
Boundary for River Rch & Prof#=SAUL TRIBUTARY 1,Reach-1,1
Up Type=0
Dn Type=3
Dn Slope=0.005
Boundary for River Rch & Prof#=SAUL TRIBUTARY 1,Reach-1,2
Up Type=0
Dn Type=3
Dn Slope=0.005
Boundary for River Rch & Prof#=SAUL TRIBUTARY 1,Reach-1,3
Up Type=0
Dn Type=3
Dn Slope=0.005
Boundary for River Rch & Prof#=SAUL TRIBUTARY 1,Reach-1,4
Up Type=0
Dn Type=3
Dn Slope=0.005
Boundary for River Rch & Prof#=SAUL TRIBUTARY 1,Reach-1,5
Up Type=0
Dn Type=3
Dn Slope=0.005
Boundary for River Rch & Prof#=SAUL TRIBUTARY 1,Reach-1,6
Up Type=0
Dn Type=3
Dn Slope=0.005
Boundary for River Rch & Prof#=SAUL TRIBUTARY 1,Reach-1,7
Up Type=0
Dn Type=3
Dn Slope=0.005

--- SAUL TRIBUTARY 1.g01 (geometry) ---

Geom Title=Existing Conditions

River Reach=SAUL TRIBUTARY 1,Reach-1
Reach XY= 30
      2327861.37     13754200.13      2327871.83     13754197.75
      2327925.00     13754225.00      2327964.52     13754223.80
      2328015.25     13754140.95      2328069.31     13754125.85
      2328096.41     13754144.33      2328125.00     13754175.00
      2328180.96     13754152.78      2328224.96     13754117.33
      2328228.63     13754026.50      2328268.89     13753977.18
      2328283.16     13753918.95      2328361.61     13753838.31
      2328373.96     13753814.56      2328373.62     13753685.44
      2328334.29     13753631.53      2328334.13     13753618.26
      2328461.37     13753488.21      2328471.02     13753473.35
      2328477.54     13753431.05      2328485.78     13753415.32
      2328621.87     13753273.37      2328621.66     13753226.75
      2328583.20     13753181.07      2328576.25     13753164.50
      2328571.46     13753026.47      2328432.76     13752881.21
      2328425.59     13752863.16      2328425.00     13752825.00

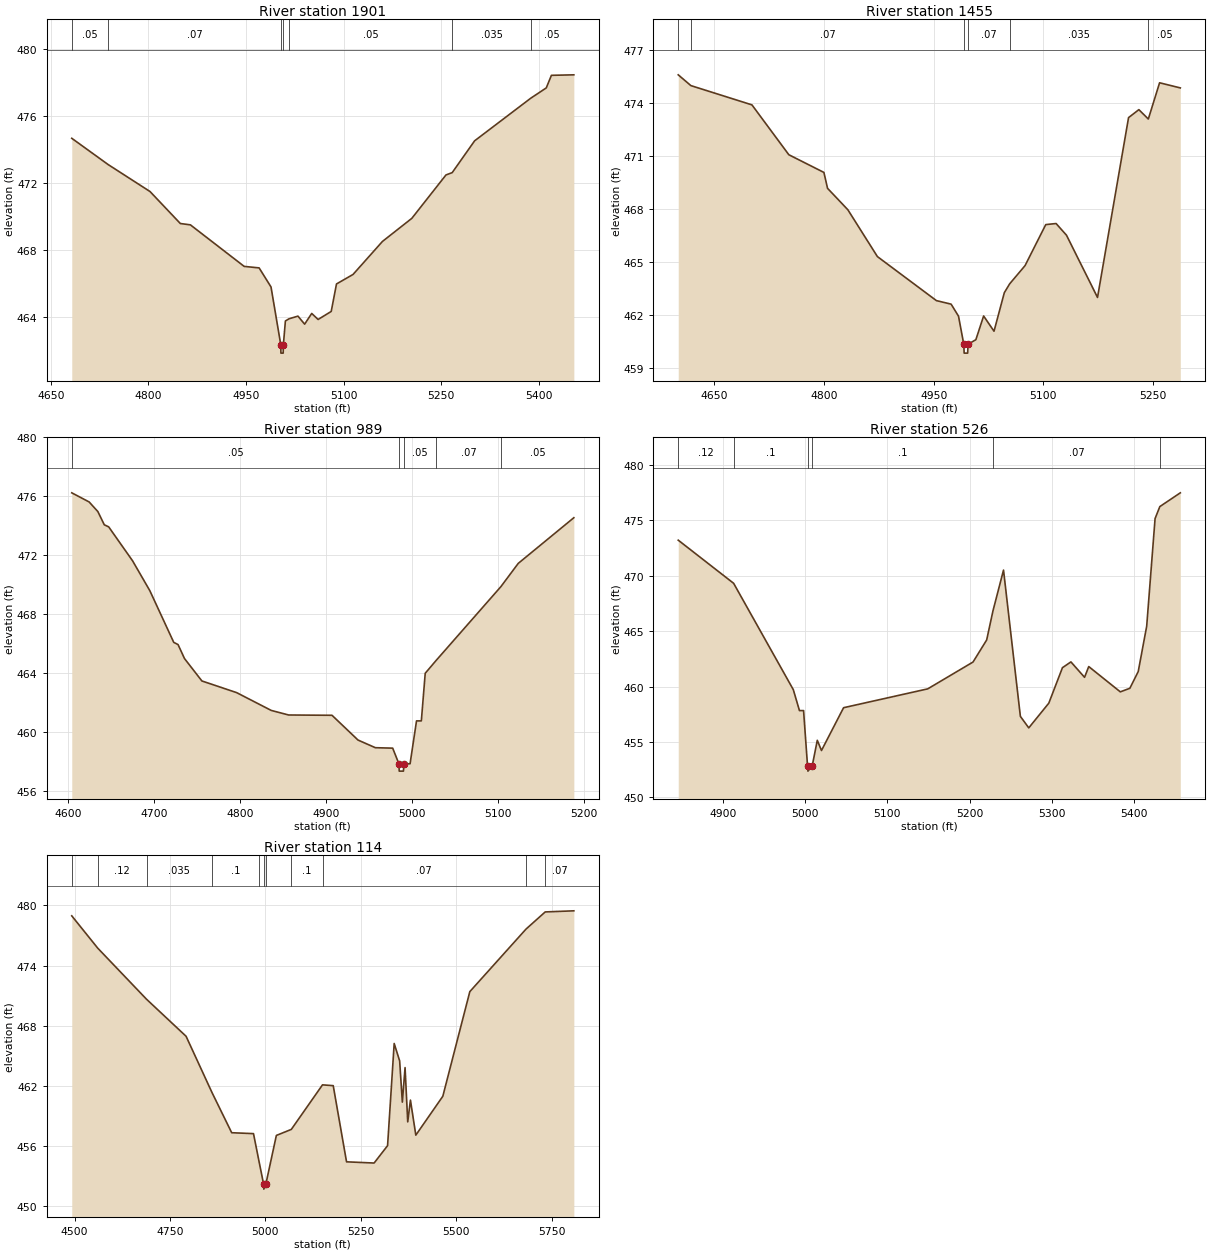
Type RM Length L Ch R = 1,1901,446,446,446
BEGIN DESCRIPTION:
E21658
END DESCRIPTION:
XS GIS Cut Line= 3
      2328042.29     13754531.52      2327939.15     13754137.56
      2327769.19     13753814.47
#Sta/Elev= 30
  4682.0  474.66  4738.0  473.09  4802.4  471.48  4849.0  469.57  4864.5  469.49
  4947.2  467.01  4970.2  466.92  4988.5  465.78  5003.5  462.33  5003.7  461.83
  5007.2  461.83  5007.5  462.33  5010.6  463.75  5016.2  463.88  5029.9  464.04
  5040.2  463.56  5051.1  464.20  5060.9  463.84  5081.1  464.32  5089.2  465.96
  5114.7  466.53  5159.9  468.50  5205.1  469.88  5257.6  472.47  5267.2  472.61
  5301.7  474.51  5387.9  477.05  5411.9  477.67  5419.8  478.42  5454.3  478.45
#Mann=7,-1,0
  4682.0    0.05       0  4738.0    0.07       0  5003.5    0.05       0
  5007.5    0.07       0  5016.2    0.05       0  5267.2   0.035       0
  5387.9    0.05       0
Bank Sta=5003.5,5007.5
Exp/Cntr=0.3,0.1

Type RM Length L Ch R = 1,1455,466,466,466
BEGIN DESCRIPTION:
SAUL TRIBUTARY 1 3.0
END DESCRIPTION:
XS GIS Cut Line= 3
      2328624.96     13754074.99      2328225.00     13754025.00
      2328025.01     13753825.01
#Sta/Elev= 30
  4601.1  475.59  4618.4  474.98  4701.8  473.89  4752.2  471.07  4800.1  470.07
  4805.1  469.17  4832.8  467.96  4873.2  465.31  4953.8  462.82  4973.9  462.62
  4984.0  461.94  4991.2  460.35  4991.7  459.85  4996.5  459.85  4997.0  460.35
  5007.7  460.61  5018.3  461.95  5032.5  461.09  5046.6  463.27  5053.9  463.77
  5074.9  464.80  5103.2  467.12  5117.3  467.18  5131.5  466.52  5173.9  463.00
  5216.3  473.17  5230.4  473.62  5243.3  473.09  5258.7  475.14  5287.0  474.85
#Mann=6,-1,0
  4601.1    0.05       0  4618.4    0.07       0  4991.2    0.05       0
  4997.0    0.07       0  5053.9   0.035       0  5243.3    0.05       0
Bank Sta=4991.2,4997
Exp/Cntr=0.3,0.1

Type RM Length L Ch R = 1,989,463,463,463
BEGIN DESCRIPTION:
SAUL TRIBUTARY 1 2.0
END DESCRIPTION:
XS GIS Cut Line= 3
      2328725.04     13753675.00      2328325.00     13753625.00
      2328175.02     13753525.02
#Sta/Elev= 30
  4604.4  476.24  4624.6  475.62  4634.7  474.97  4642.2  474.07  4647.3  473.93
  4675.0  471.63  4695.1  469.60  4722.9  466.09  4727.9  465.94  4735.4  464.99
  4755.6  463.47  4795.9  462.68  4836.2  461.47  4856.4  461.16  4906.8  461.14
  4937.0  459.46  4957.2  458.94  4977.3  458.91  4984.5  457.85  4984.9  457.35
  4989.8  457.35  4990.3  457.85  4997.5  457.85  5005.0  460.76  5010.6  460.76
  5015.1  463.99  5027.6  464.85  5103.0  469.87  5123.2  471.45  5187.8  474.55
#Mann=5,-1,0
  4604.4    0.05       0  4984.5    0.05       0  4990.3    0.05       0
  5027.6    0.07       0  5103.0    0.05       0
Bank Sta=4984.5,4990.3
Exp/Cntr=0.3,0.1

Type RM Length L Ch R = 1,526,412,412,412
BEGIN DESCRIPTION:
SAUL TRIBUTARY 1 1.0
END DESCRIPTION:
XS GIS Cut Line= 3
      2328774.96     13753275.00      2328625.00     13753275.00
      2328175.03     13753374.99
#Sta/Elev= 30
  4845.5  473.20  4912.9  469.31  4985.5  459.72  4993.0  457.83  4998.0  457.83
  5002.8  452.87  5003.3  452.37  5008.6  452.87  5014.7  455.15  5019.8  454.23
  5046.7  458.09  5149.1  459.79  5204.2  462.21  5220.8  464.20  5228.4  466.81
  5241.3  470.50  5261.8  457.31  5272.0  456.27  5296.4  458.50  5313.0  461.70
  5323.3  462.22  5339.9  460.83  5345.0  461.80  5383.4  459.52  5395.0  459.84
  5405.2  461.35  5415.5  465.44  5425.7  475.15  5431.5  476.23  5456.4  477.47
#Mann=6,-1,0
  4845.5    0.12       0  4912.9     0.1       0  5002.8    0.05       0
  5008.6     0.1       0  5228.4    0.07       0  5431.5   0.035       0
Bank Sta=5002.8,5008.6
Exp/Cntr=0.3,0.1

Type RM Length L Ch R = 1,114,0,0,0
BEGIN DESCRIPTION:
E20756
END DESCRIPTION:
XS GIS Cut Line= 4
      2328973.11     13752859.11      2328517.34     13752903.39
      2328157.96     13753049.22      2327825.87     13753381.31
#Sta/Elev= 30
  4492.8  478.96  4560.9  475.74  4688.7  470.65  4792.3  466.96  4860.5  461.33
  4911.8  457.35  4968.9  457.26  4983.5  454.47  4995.4  452.23  4995.9  451.73
  5001.3  452.23  5028.8  457.08  5068.0  457.68  5149.7  462.12  5177.8  462.04
  5212.7  454.45  5284.9  454.33  5320.2  456.06  5337.5  466.24  5351.8  464.51
  5358.9  460.40  5366.0  463.84  5373.0  458.43  5380.1  460.60  5394.2  457.11
  5464.9  460.98  5535.7  471.41  5682.9  477.64  5733.2  479.35  5808.2  479.46
#Mann=11,-1,0
  4492.8    0.05       0  4560.9    0.12       0  4688.7   0.035       0
  4860.5     0.1       0  4983.5   0.035       0  4995.4   0.035       0
  5001.3   0.035       0  5068.0     0.1       0  5149.7    0.07       0
  5682.9   0.035       0  5733.2    0.07       0
Bank Sta=4995.4,5001.3
Exp/Cntr=0.3,0.1

Chan Stop Cuts=-1