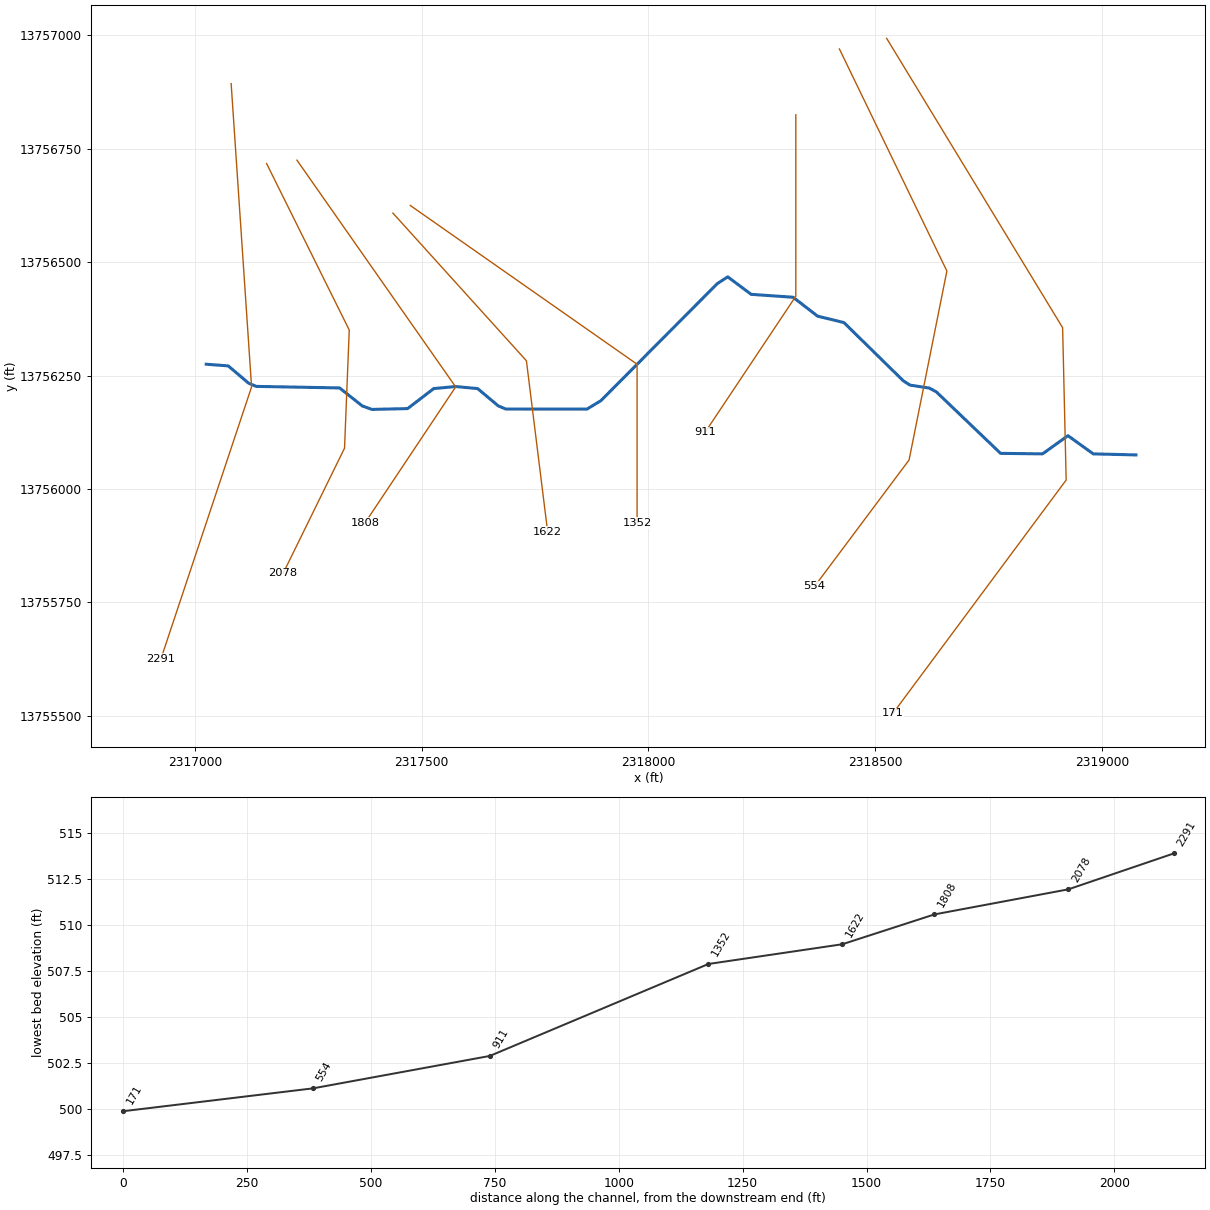
--- SAUL TRIBUTARY C.prj (project) ---

Proj Title=SAUL TRIBUTARY C Base Level Engineering
Current Plan=p01
Default Exp/Contr=0.3,0.1
English Units
Geom File=g01
Flow File=f01
Plan File=p01
BEGIN DESCRIPTION:
SAUL TRIBUTARY C
END DESCRIPTION:

--- SAUL TRIBUTARY C.p01 (plan) ---

Plan Title=Multiple Run
Short Identifier=Multiple
Geom File=g01
Flow File=f01
Subcritical Flow
K Sum by GR= 0
Std Step Tol= 0.01
Critical Tol= 0.01
Num of Std Step Trials= 20
Max Error Tol= 0.3
Flow Tol Ratio= 0.001
Split Flow NTrial= 30
Split Flow Tol= 0.02
Split Flow Ratio= 0.02
Log Output Level= 0
Friction Slope Method= 1
Unsteady Friction Slope Method= 2
Unsteady Bridges Friction Slope Method= 1
Parabolic Critical Depth
Global Vel Dist=  1 , 1 , 1
Global Log Level= 0
CheckData=True
Encroach Param= -1, 0, 0, 0
BEGIN DESCRIPTION:
Multiple Run
END DESCRIPTION:

--- SAUL TRIBUTARY C.f01 (steady flow) ---

Flow Title=Multiple
Number of Profiles=7
Profile Names=10-year,25-year,50-year,1pct_min,100-year,1pct_plu,500-year
River Rch & RM= SAUL TRIBUTARY C,Reach-1,2291
     375     582     761     482     963    1921    1525
Boundary for River Rch & Prof#=SAUL TRIBUTARY C,Reach-1,1
Up Type=0
Dn Type=3
Dn Slope=0.005
Boundary for River Rch & Prof#=SAUL TRIBUTARY C,Reach-1,2
Up Type=0
Dn Type=3
Dn Slope=0.005
Boundary for River Rch & Prof#=SAUL TRIBUTARY C,Reach-1,3
Up Type=0
Dn Type=3
Dn Slope=0.005
Boundary for River Rch & Prof#=SAUL TRIBUTARY C,Reach-1,4
Up Type=0
Dn Type=3
Dn Slope=0.005
Boundary for River Rch & Prof#=SAUL TRIBUTARY C,Reach-1,5
Up Type=0
Dn Type=3
Dn Slope=0.005
Boundary for River Rch & Prof#=SAUL TRIBUTARY C,Reach-1,6
Up Type=0
Dn Type=3
Dn Slope=0.005
Boundary for River Rch & Prof#=SAUL TRIBUTARY C,Reach-1,7
Up Type=0
Dn Type=3
Dn Slope=0.005

--- SAUL TRIBUTARY C.g01 (geometry) ---

Geom Title=Existing Conditions

River Reach=SAUL TRIBUTARY C,Reach-1
Reach XY= 30
      2317025.00     13756275.00      2317073.49     13756271.35
      2317118.84     13756232.89      2317135.46     13756226.12
      2317319.06     13756222.74      2317368.97     13756183.09
      2317390.27     13756175.38      2317469.03     13756177.17
      2317526.60     13756221.29      2317575.00     13756225.82
      2317623.40     13756221.30      2317668.94     13756183.15
      2317685.50     13756176.22      2317864.57     13756176.05
      2317895.16     13756194.60      2318151.64     13756452.55
      2318174.90     13756467.69      2318226.50     13756429.10
      2318319.03     13756422.67      2318372.83     13756381.14
      2318431.06     13756366.86      2318561.79     13756238.63
      2318576.65     13756228.98      2318618.95     13756222.46
      2318634.68     13756214.22      2318776.50     13756078.46
      2318869.10     13756077.36      2318925.01     13756117.48
      2318980.77     13756077.34      2319075.00     13756075.00

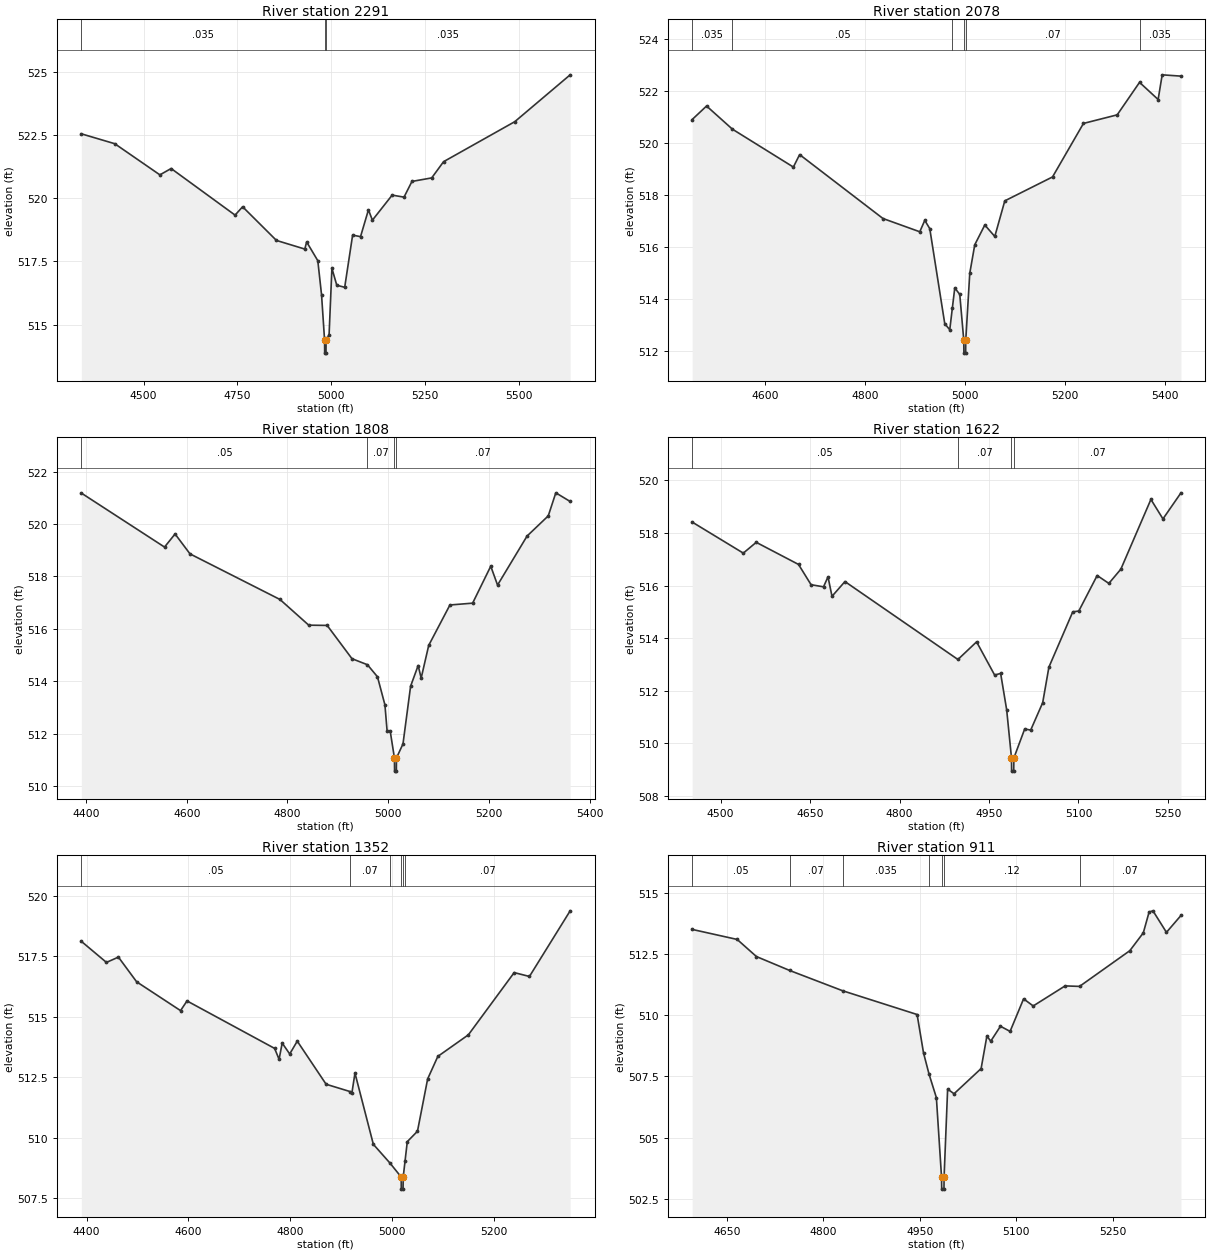
Type RM Length L Ch R = 1,2291,213,213,213
BEGIN DESCRIPTION:
SAUL TRIBUTARY C 4.0
END DESCRIPTION:
XS GIS Cut Line= 3
      2317079.95     13756893.78      2317125.00     13756225.00
      2316924.99     13755624.96
#Sta/Elev= 30
  4334.2  522.54  4423.2  522.15  4543.5  520.92  4573.5  521.17  4743.9  519.33
  4764.0  519.66  4854.2  518.33  4929.7  517.99  4934.7  518.27  4964.4  517.53
  4974.4  516.18  4982.5  514.38  4982.7  513.88  4986.2  513.88  4986.5  514.38
  4994.5  514.61  5002.0  517.23  5015.0  516.56  5036.1  516.48  5057.2  518.54
  5078.3  518.48  5099.4  519.54  5109.9  519.13  5162.6  520.12  5194.2  520.04
  5215.3  520.66  5268.0  520.80  5299.6  521.44  5489.4  523.02  5637.0  524.87
#Mann=3,-1,0
  4334.2   0.035       0  4982.5   0.035       0  4986.5   0.035       0
Bank Sta=4982.5,4986.5
Exp/Cntr=0.3,0.1

Type RM Length L Ch R = 1,2078,270,270,270
BEGIN DESCRIPTION:
E20759
END DESCRIPTION:
XS GIS Cut Line= 4
      2317158.07     13756717.55      2317340.36     13756350.36
      2317329.95     13756089.94      2317194.55     13755813.94
#Sta/Elev= 30
  4453.5  520.92  4482.3  521.44  4533.9  520.55  4656.0  519.09  4668.5  519.57
  4835.3  517.11  4908.9  516.60  4918.9  517.04  4928.9  516.72  4958.9  513.06
  4968.9  512.83  4974.1  513.67  4978.9  514.44  4988.9  514.19  4996.9  512.43
  4997.2  511.93  5000.7  511.93  5000.9  512.43  5008.9  515.00  5018.9  516.10
  5039.0  516.86  5059.0  516.42  5079.0  517.79  5174.5  518.71  5236.4  520.77
  5303.9  521.10  5348.6  522.35  5385.8  521.69  5393.9  522.64  5431.5  522.59
#Mann=6,-1,0
  4453.5   0.035       0  4533.9    0.05       0  4974.1    0.07       0
  4996.9    0.05       0  5000.9    0.07       0  5348.6   0.035       0
Bank Sta=4996.9,5000.9
Exp/Cntr=0.3,0.1

Type RM Length L Ch R = 1,1808,186,186,186
BEGIN DESCRIPTION:
SAUL TRIBUTARY C 3.0
END DESCRIPTION:
XS GIS Cut Line= 3
      2317225.02     13756724.97      2317575.00     13756225.00
      2317375.03     13755925.04
#Sta/Elev= 30
  4390.7  521.18  4555.9  519.12  4576.8  519.62  4606.5  518.86  4785.2  517.12
  4842.3  516.14  4878.9  516.13  4928.2  514.86  4958.9  514.63  4978.8  514.17
  4993.6  513.10  4997.9  512.11  5004.0  512.11  5012.5  511.07  5012.8  510.57
  5016.3  510.57  5016.5  511.07  5029.5  511.61  5044.6  513.81  5059.6  514.60
  5065.6  514.12  5080.6  515.37  5122.7  516.91  5167.8  516.98  5203.8  518.39
  5217.3  517.67  5275.9  519.54  5318.0  520.31  5333.0  521.19  5361.5  520.86
#Mann=4,-1,0
  4390.7    0.05       0  4958.9    0.07       0  5012.5    0.05       0
  5016.5    0.07       0
Bank Sta=5012.5,5016.5
Exp/Cntr=0.3,0.1

Type RM Length L Ch R = 1,1622,270,270,270
BEGIN DESCRIPTION:
E20760
END DESCRIPTION:
XS GIS Cut Line= 3
      2317436.69     13756608.20      2317730.99     13756282.65
      2317777.87     13755905.00
#Sta/Elev= 30
  4452.4  518.41  4538.1  517.23  4559.8  517.64  4630.7  516.80  4651.7  516.03
  4672.6  515.95  4680.1  516.33  4686.8  515.59  4708.5  516.15  4897.9  513.19
  4929.2  513.86  4959.4  512.60  4969.5  512.66  4979.6  511.28  4987.7  509.45
  4987.9  508.95  4991.4  508.95  4991.7  509.45  5009.8  510.55  5019.9  510.51
  5040.0  511.55  5050.4  512.90  5090.4  515.00  5100.5  515.03  5131.3  516.38
  5150.9  516.08  5171.0  516.62  5221.4  519.27  5241.6  518.53  5271.8  519.52
#Mann=4,-1,0
  4452.4    0.05       0  4897.9    0.07       0  4987.7    0.05       0
  4991.7    0.07       0
Bank Sta=4987.7,4991.7
Exp/Cntr=0.3,0.1

Type RM Length L Ch R = 1,1352,441,441,441
BEGIN DESCRIPTION:
SAUL TRIBUTARY C 2.0
END DESCRIPTION:
XS GIS Cut Line= 3
      2317474.97     13756625.02      2317975.00     13756275.00
      2317975.00     13755924.97
#Sta/Elev= 30
  4389.6  518.11  4438.9  517.24  4462.4  517.46  4498.2  516.44  4584.5  515.25
  4597.2  515.65  4769.3  513.69  4778.1  513.24  4784.2  513.91  4799.0  513.46
  4813.8  513.99  4870.5  512.21  4917.3  511.91  4921.1  511.84  4927.2  512.67
  4963.3  509.73  4995.8  508.96  5018.0  508.38  5018.2  507.88  5021.7  507.88
  5022.0  508.38  5025.7  509.06  5030.0  509.84  5050.0  510.27  5070.0  512.43
  5090.0  513.36  5150.0  514.25  5240.0  516.82  5270.0  516.66  5350.0  519.37
#Mann=6,-1,0
  4389.6    0.05       0  4917.3    0.07       0  4995.8    0.12       0
  5018.0    0.05       0  5022.0    0.12       0  5025.7    0.07       0
Bank Sta=5018,5022
Exp/Cntr=0.3,0.1

Type RM Length L Ch R = 1,911,357,357,357
BEGIN DESCRIPTION:
SAUL TRIBUTARY C 1.0
END DESCRIPTION:
XS GIS Cut Line= 3
      2318325.00     13756825.03      2318325.00     13756425.00
      2318124.99     13756124.99
#Sta/Elev= 30
  4595.7  513.51  4665.7  513.10  4695.7  512.40  4747.5  511.83  4830.0  511.00
  4945.7  510.03  4955.7  508.46  4964.3  507.59  4975.7  506.63  4983.7  503.39
  4984.0  502.89  4987.5  502.89  4987.7  503.39  4993.2  506.98  5003.2  506.79
  5045.3  507.82  5054.3  509.15  5060.3  508.94  5075.4  509.55  5090.4  509.34
  5111.4  510.67  5126.4  510.38  5176.0  511.20  5198.5  511.18  5276.7  512.64
  5297.7  513.37  5306.7  514.22  5312.7  514.27  5333.7  513.39  5356.3  514.08
#Mann=7,-1,0
  4595.7    0.05       0  4747.5    0.07       0  4830.0   0.035       0
  4964.3    0.12       0  4983.7    0.05       0  4987.7    0.12       0
  5198.5    0.07       0
Bank Sta=4983.7,4987.7
Exp/Cntr=0.3,0.1

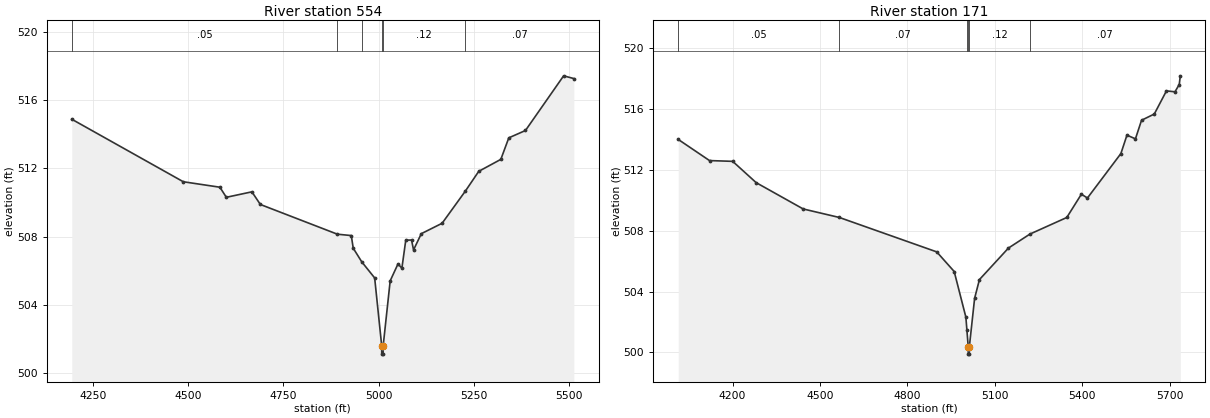
Type RM Length L Ch R = 1,554,383,383,383
BEGIN DESCRIPTION:
E20758
END DESCRIPTION:
XS GIS Cut Line= 4
      2318421.09     13756970.17      2318658.07     13756480.57
      2318574.74     13756063.90      2318366.39     13755785.24
#Sta/Elev= 30
  4194.8  514.88  4487.3  511.22  4583.2  510.90  4600.2  510.31  4667.2  510.63
  4689.4  509.89  4891.4  508.15  4927.9  508.07  4933.0  507.33  4955.4  506.53
  4989.2  505.59  5007.6  501.63  5007.8  501.13  5011.3  501.13  5011.6  501.63
  5029.9  505.42  5050.4  506.41  5060.6  506.16  5070.8  507.80  5085.9  507.81
  5091.2  507.23  5111.5  508.18  5166.1  508.79  5227.3  510.68  5262.2  511.83
  5320.1  512.53  5341.0  513.79  5384.7  514.22  5484.8  517.42  5511.6  517.26
#Mann=6,-1,0
  4194.8    0.05       0  4891.4    0.07       0  4955.4    0.12       0
  5007.6    0.05       0  5011.6    0.12       0  5227.3    0.07       0
Bank Sta=5007.6,5011.6
Exp/Cntr=0.3,0.1

Type RM Length L Ch R = 1,171,0,0,0
BEGIN DESCRIPTION:
E20757
END DESCRIPTION:
XS GIS Cut Line= 4
      2318525.27     13756993.57      2318913.28     13756355.57
      2318921.09     13756019.63      2318539.14     13755505.16
#Sta/Elev= 30
  4013.4  514.00  4120.8  512.61  4200.3  512.56  4280.9  511.16  4442.4  509.43
  4566.7  508.87  4900.7  506.61  4960.7  505.32  5000.8  502.32  5004.4  501.45
  5008.8  500.39  5009.0  499.89  5012.5  499.89  5012.8  500.39  5030.8  503.56
  5047.4  504.79  5146.9  506.86  5220.7  507.78  5347.2  508.87  5397.3  510.40
  5418.1  510.15  5532.9  513.07  5553.7  514.28  5582.9  514.04  5603.8  515.26
  5647.6  515.67  5689.3  517.19  5718.6  517.13  5733.2  517.61  5736.9  518.18
#Mann=6,-1,0
  4013.4    0.05       0  4566.7    0.07       0  5004.4    0.12       0
  5008.8    0.05       0  5012.8    0.12       0  5220.7    0.07       0
Bank Sta=5008.8,5012.8
Exp/Cntr=0.3,0.1

Chan Stop Cuts=-1