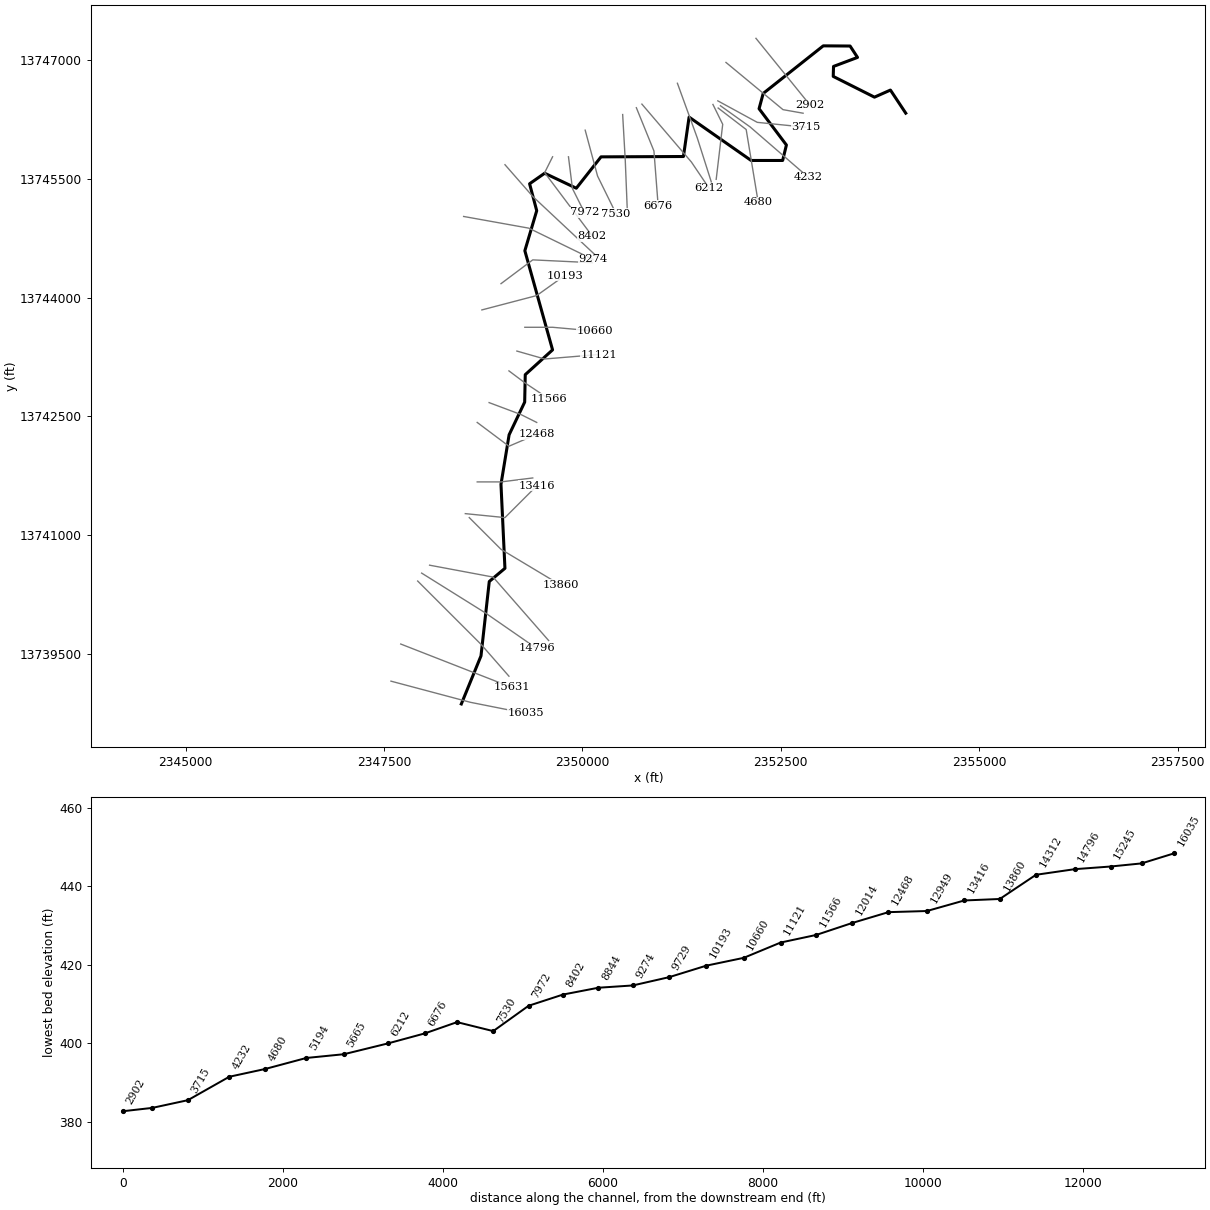
--- SAWLOG CREEK.prj (project) ---

Proj Title=SAWLOG CREEK Base Level Engineering
Current Plan=p01
Default Exp/Contr=0.3,0.1
English Units
Geom File=g01
Flow File=f01
Plan File=p01
Y Axis Title=Elevation
X Axis Title(PF)=Main Channel Distance
X Axis Title(XS)=Station
BEGIN DESCRIPTION:
SAWLOG CREEK
END DESCRIPTION:
DSS Export Rating Curves= 0
DSS Export Rating Curve Sorted= 0
DSS Export Volume Flow Curves= 0
DXF OffsetX= 0
DXF OffsetY= 0
DXF ScaleX= 1
DXF ScaleY= 10

--- SAWLOG CREEK.p01 (plan) ---

Plan Title=Multiple Run
Short Identifier=Multiple
Geom File=g01
Flow File=f01
Subcritical Flow
K Sum by GR= 0
Std Step Tol= 0.01
Critical Tol= 0.01
Num of Std Step Trials= 20
Max Error Tol= 0.3
Flow Tol Ratio= 0.001
Split Flow NTrial= 30
Split Flow Tol= 0.02
Split Flow Ratio= 0.02
Log Output Level= 0
Friction Slope Method= 1
Unsteady Friction Slope Method= 2
Unsteady Bridges Friction Slope Method= 1
Parabolic Critical Depth
Global Vel Dist=  1 , 1 , 1
Global Log Level= 0
CheckData=True
Encroach Param= -1, 0, 0, 0
BEGIN DESCRIPTION:
Multiple Run
END DESCRIPTION:

--- SAWLOG CREEK.f01 (steady flow) ---

Flow Title=Multiple
Number of Profiles=7
Profile Names=10-year,25-year,50-year,1pct_min,100-year,1pct_plu,500-year
River Rch & RM= SAWLOG CREEK,Reach-1,16035
     722    1178    1594    1045    2084    4158    3531
River Rch & RM= SAWLOG CREEK,Reach-1,14312
     878    1445    1967    1295    2583    5154    4417
River Rch & RM= SAWLOG CREEK,Reach-1,9274
    1206    2014    2768    1837    3666    7314    6377
River Rch & RM= SAWLOG CREEK,Reach-1,602
    1209    2019    2774    1841    3673    7328    6388
Boundary for River Rch & Prof#=SAWLOG CREEK,Reach-1,1
Up Type=0
Dn Type=3
Dn Slope=0.005
Boundary for River Rch & Prof#=SAWLOG CREEK,Reach-1,2
Up Type=0
Dn Type=3
Dn Slope=0.005
Boundary for River Rch & Prof#=SAWLOG CREEK,Reach-1,3
Up Type=0
Dn Type=3
Dn Slope=0.005
Boundary for River Rch & Prof#=SAWLOG CREEK,Reach-1,4
Up Type=0
Dn Type=3
Dn Slope=0.005
Boundary for River Rch & Prof#=SAWLOG CREEK,Reach-1,5
Up Type=0
Dn Type=3
Dn Slope=0.005
Boundary for River Rch & Prof#=SAWLOG CREEK,Reach-1,6
Up Type=0
Dn Type=3
Dn Slope=0.005
Boundary for River Rch & Prof#=SAWLOG CREEK,Reach-1,7
Up Type=0
Dn Type=3
Dn Slope=0.005

--- SAWLOG CREEK.g01 (geometry) ---

Geom Title=Existing Conditions
Program Version=4.10

River Reach=SAWLOG CREEK    ,Reach-1
Reach XY= 30
        2348475.       13738875.      2348722.74     13739480.94
      2348827.05     13740419.16      2349024.47     13740585.47
      2348974.61     13741645.13      2349077.07     13742269.14
      2349273.18     13742681.12      2349280.46     13743027.46
      2349624.62     13743340.16      2349275.38     13744590.16
      2349424.96     13745095.03      2349335.18      13745434.7
        2349525.      13745567.5      2349923.74     13745378.44
      2350235.28     13745774.01      2351273.75     13745778.36
      2351344.94     13746275.27      2352126.46     13745728.54
      2352523.78     13745728.43      2352571.26     13745923.44
       2352226.8     13746381.11      2352278.61      13746573.5
      2353035.48     13747173.81      2353373.75     13747171.55
      2353467.25     13747028.02      2353164.88     13746914.37
      2353161.29     13746788.48      2353680.71     13746526.89
        2353882.     13746616.17        2354075.       13746325.

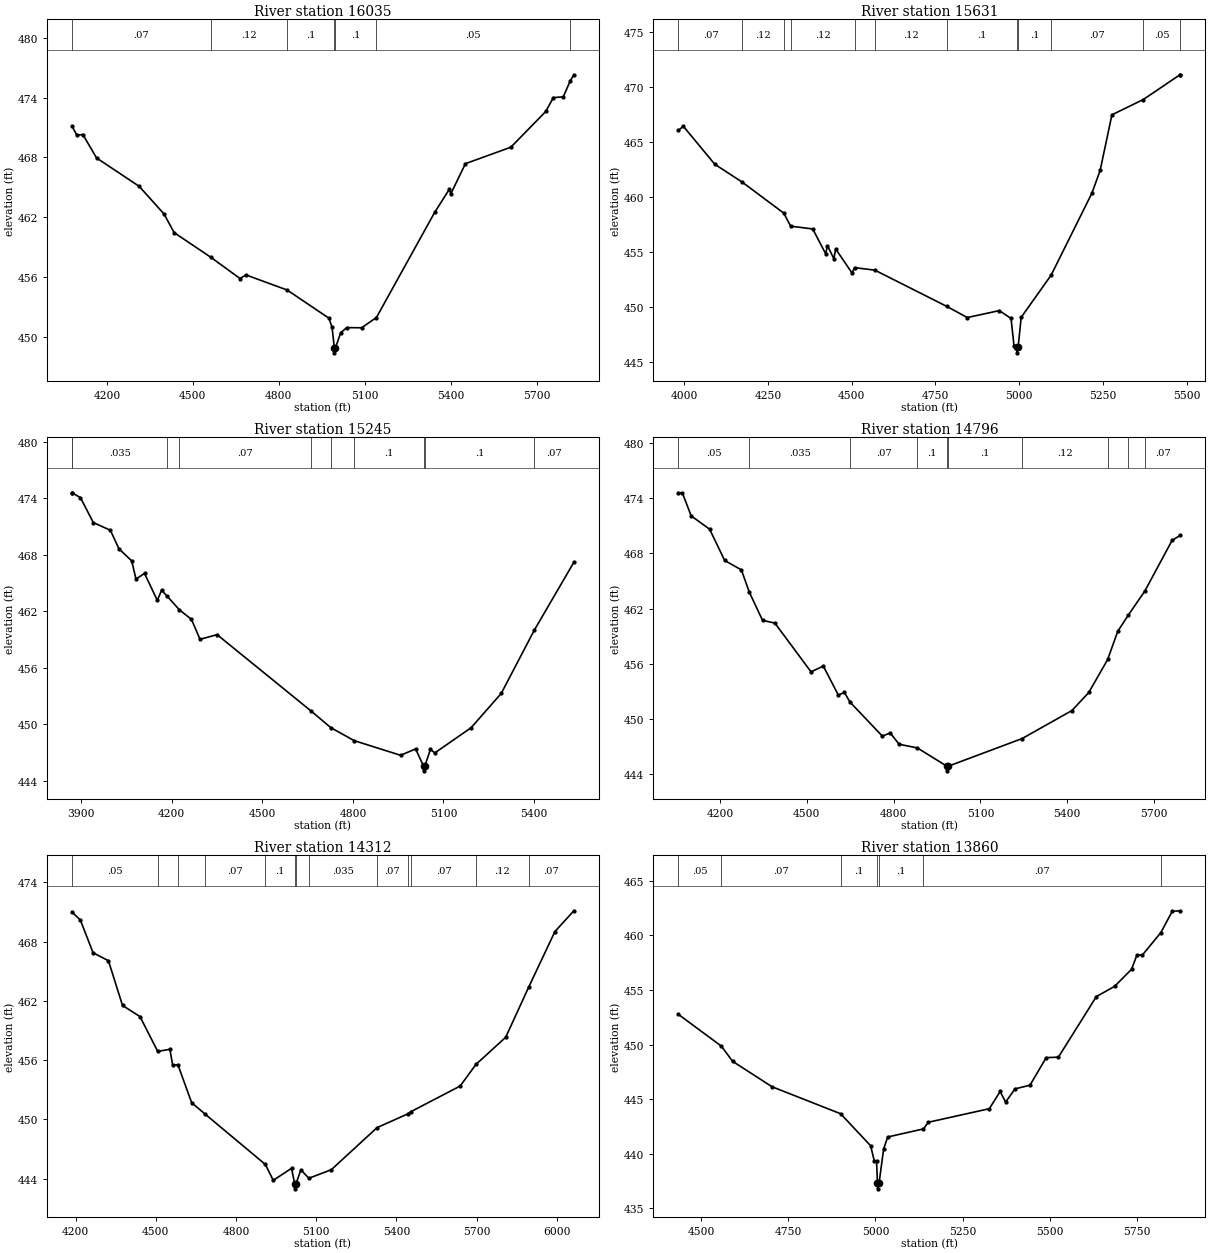
Type RM Length L Ch R = 1 ,16035   ,404,404,404
BEGIN DESCRIPTION:
E20777
END DESCRIPTION:
XS GIS Cut Line= 3
      2347588.26     13739162.52      2348590.23      13738895.6
       2349291.2     13738756.22
#Sta/Elev= 30
  4078.1  471.14  4095.4  470.22  4116.1  470.29  4164.1  467.94  4312.7   465.1
  4399.7  462.32  4434.6  460.46  4561.7  458.01  4664.6  455.86  4685.3  456.22
  4828.9  454.71  4975.1  451.88    4986  450.95  4993.8  448.91    4994  448.41
  4997.8  448.91  5015.8  450.42  5037.2  450.94  5088.9  450.92  5140.7  451.95
    5344  462.49  5395.1   464.8  5400.2  464.34  5451.3  467.37  5609.8  469.02
  5731.6   472.6  5758.1  473.99  5792.8  474.07  5817.2  475.68  5829.7  476.28
#Mann= 7 ,-1 , 0
  4078.1     .07       0  4561.7     .12       0  4828.9      .1       0
  4993.8     .05       0  4997.8      .1       0  5140.7     .05       0
  5817.2    .045       0
Bank Sta=4993.8,4997.8
XS Rating Curve= 0 ,0
Exp/Cntr=0.3,0.1

Type RM Length L Ch R = 1 ,15631   ,386,386,386
BEGIN DESCRIPTION:
E20776
END DESCRIPTION:
XS GIS Cut Line= 2
      2347711.43     13739630.66      2349107.61     13739084.51
#Sta/Elev= 30
  3982.1  466.09  3996.7  466.47  4090.8  463.01  4173.5  461.37  4296.7  458.57
  4317.4  457.38  4383.2  457.13    4422  454.87  4427.3  455.61  4446.4  454.42
  4451.8  455.31  4500.7  453.12  4508.4  453.61  4568.9  453.38  4783.3  450.09
    4845  449.07  4940.5   449.7  4975.7  448.99  4984.6  446.47  4992.7  446.36
  4992.9  445.86  4996.8  446.36    5006  449.09  5095.5  452.93  5217.3  460.39
  5241.8  462.45    5277  467.51  5370.8   468.9  5479.6  471.14  5481.3  471.15
#Mann= 12 ,-1 , 0
  3982.1     .07       0  4173.5     .12       0  4296.7     .07       0
  4317.4     .12       0  4508.4     .07       0  4568.9     .12       0
  4783.3      .1       0  4992.7     .05       0  4996.8      .1       0
  5095.5     .07       0  5370.8     .05       0  5479.6     .07       0
Bank Sta=4992.7,4996.8
XS Rating Curve= 0 ,0
Exp/Cntr=0.3,0.1

Type RM Length L Ch R = 1 ,15245   ,449,449,449
BEGIN DESCRIPTION:
SAWLOG CREEK 31.0
END DESCRIPTION:
XS GIS Cut Line= 3
      2347925.01     13740424.99        2348725.       13739625.
      2349075.02     13739224.98
#Sta/Elev= 30
  3869.2  474.59  3869.7  474.59  3897.5  474.07  3939.9  471.43  3996.5  470.61
  4024.8  468.65  4067.2  467.36  4081.3  465.43  4109.6  466.03    4152  463.17
  4166.2  464.24  4185.6  463.58  4224.9  462.17  4265.2  461.15  4293.5  459.03
    4350  459.53  4660.4  451.45  4726.7  449.66  4803.9  448.28  4958.1  446.72
  5007.7   447.4  5034.1  445.57  5034.3  445.07  5038.3  445.57    5057  447.36
  5071.3  446.97  5191.8  449.65  5291.5  453.29    5401     460  5532.1  467.21
#Mann= 10 ,-1 , 0
  3869.2     .05       0  3869.7    .035       0  4185.6     .12       0
  4224.9     .07       0  4660.4     .12       0  4726.7     .07       0
  4803.9      .1       0  5034.1     .05       0  5038.3      .1       0
    5401     .07       0
Bank Sta=5034.1,5038.3
XS Rating Curve= 0 ,0
Exp/Cntr=0.3,0.1

Type RM Length L Ch R = 1 ,14796   ,484,484,484
BEGIN DESCRIPTION:
SAWLOG CREEK 30.0
END DESCRIPTION:
XS GIS Cut Line= 3
      2347974.99     13740525.01        2348775.       13740025.
      2349425.01     13739574.99
#Sta/Elev= 30
  4056.5  474.59  4070.1  474.57  4100.7  472.08  4164.4  470.63  4216.3  467.24
  4274.1  466.21  4301.6  463.78  4347.2  460.73  4389.7  460.44  4514.7  455.14
  4557.1  455.77    4609  452.62  4630.2   452.9  4649.2  451.86  4761.1  448.16
  4788.2  448.51  4818.9  447.28  4881.9  446.88  4984.2  444.89  4984.5  444.39
  4988.5  444.89  5243.6  447.89  5416.1  450.94  5474.3   452.9  5539.6  456.49
  5574.3  459.54  5611.3  461.33  5667.6   463.9  5762.1  469.42  5790.5  469.97
#Mann= 10 ,-1 , 0
  4056.5     .05       0  4301.6    .035       0  4649.2     .07       0
  4881.9      .1       0  4984.2     .05       0  4988.5      .1       0
  5243.6     .12       0  5539.6     .07       0  5611.3     .12       0
  5667.6     .07       0
Bank Sta=4984.2,4988.5
XS Rating Curve= 0 ,0
Exp/Cntr=0.3,0.1

Type RM Length L Ch R = 1 ,14312   ,452,452,452
BEGIN DESCRIPTION:
SAWLOG CREEK 29.0
END DESCRIPTION:
XS GIS Cut Line= 3
      2348074.99       13740625.        2348875.       13740475.
      2349575.02     13739674.98
#Sta/Elev= 30
  4186.6  470.99    4218  470.19  4265.5  466.87  4323.1  466.06  4375.7  461.53
    4441  460.41  4507.3  456.88  4552.9  457.09  4563.1  455.51  4582.8  455.53
  4634.3  451.68  4683.6  450.55  4909.9  445.43  4939.5  443.82  5007.7  445.04
  5019.7  443.46    5020  442.96  5024.2  443.46  5042.8  444.88  5072.6  444.03
  5156.7   444.9  5327.7  449.16  5441.9  450.54  5455.3  450.79  5638.4  453.37
  5697.5  455.56  5808.7  458.31  5895.1  463.41  5992.9  469.02  6063.6  471.12
#Mann= 13 ,-1 , 0
  4186.6     .05       0  4507.3     .07       0  4582.8    .035       0
  4683.6     .07       0  4909.9      .1       0  5019.7     .05       0
  5024.2      .1       0  5072.6    .035       0  5327.7     .07       0
  5441.9     .12       0  5455.3     .07       0  5697.5     .12       0
  5895.1     .07       0
Bank Sta=5019.7,5024.2
XS Rating Curve= 0 ,0
Exp/Cntr=0.3,0.1

Type RM Length L Ch R = 1 ,13860   ,444,444,444
BEGIN DESCRIPTION:
SAWLOG CREEK 28.0
END DESCRIPTION:
XS GIS Cut Line= 3
      2348575.02     13741224.98        2348975.       13740825.
        2349725.       13740375.
#Sta/Elev= 30
  4434.5  452.77  4557.8  449.86    4590  448.47  4703.2  446.14  4899.9  443.67
    4986  440.74  4996.6  439.35  5003.1  439.35  5005.7  437.29    5006  436.79
  5010.2  437.29  5023.5  440.46  5035.1  441.54  5137.7  442.28  5151.8  442.89
  5326.7  444.13  5357.8  445.71  5373.3  444.73  5400.5  445.95  5443.3  446.28
    5490  448.81  5524.9  448.85  5633.8   454.4  5686.3  455.34  5734.9   456.9
  5750.4  458.22    5766  458.21  5819.1  460.27  5851.5  462.21  5874.8  462.26
#Mann= 7 ,-1 , 0
  4434.5     .05       0  4557.8     .07       0  4899.9      .1       0
  5005.7     .05       0  5010.2      .1       0  5137.7     .07       0
  5819.1    .035       0
Bank Sta=5005.7,5010.2
XS Rating Curve= 0 ,0
Exp/Cntr=0.3,0.1

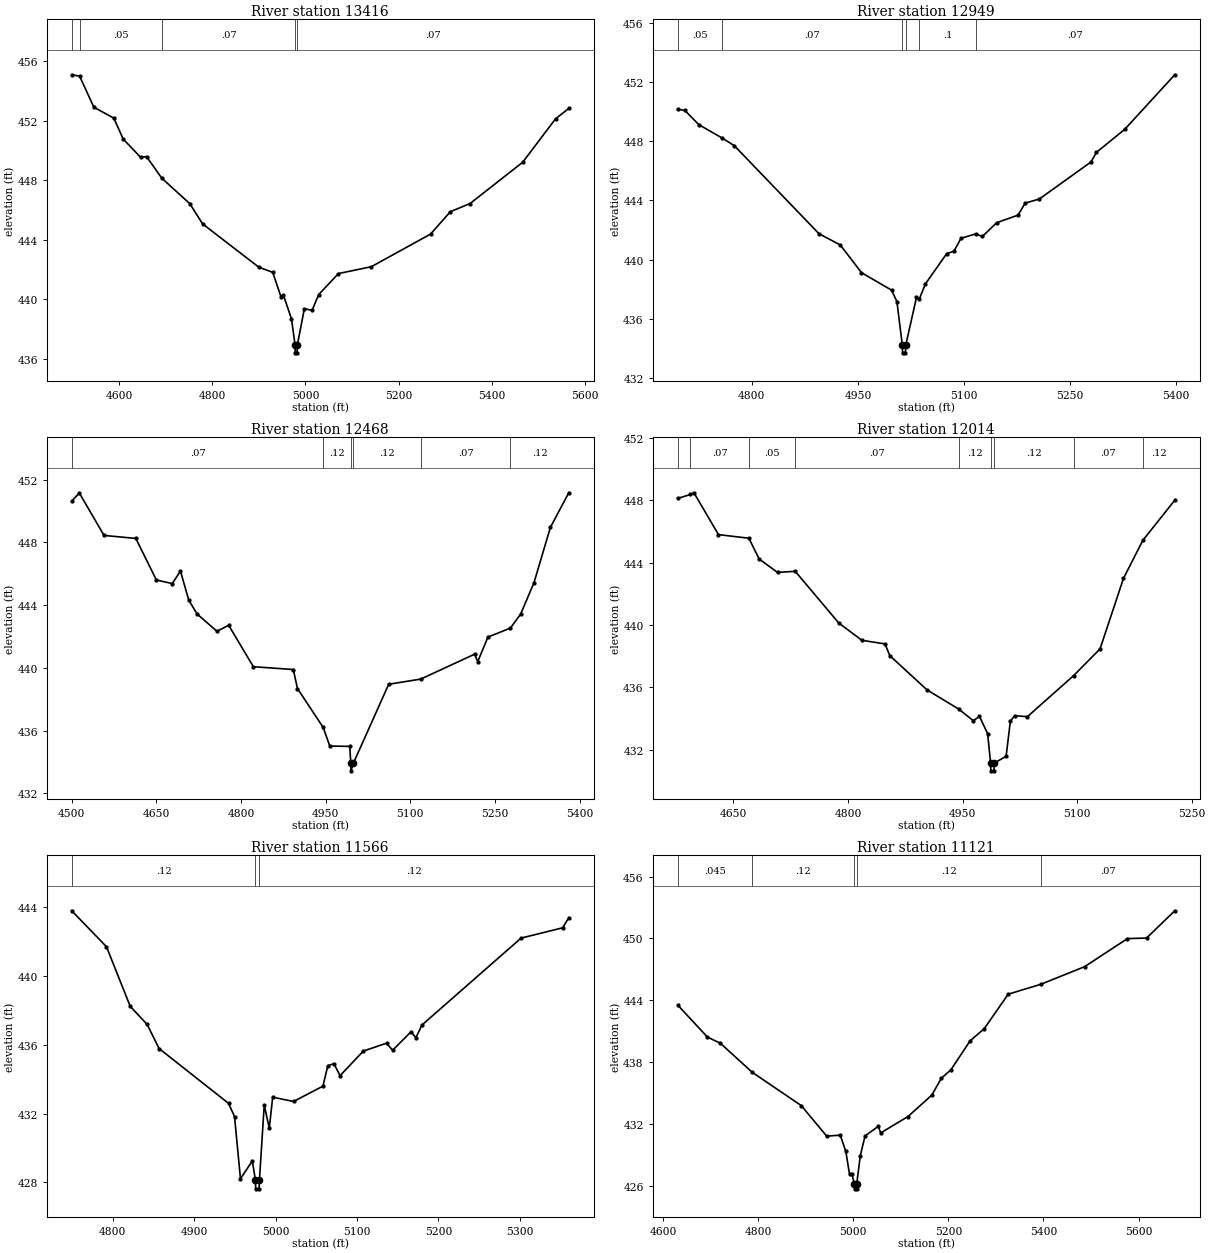
Type RM Length L Ch R = 1 ,13416   ,467,467,467
BEGIN DESCRIPTION:
SAWLOG CREEK 27.0
END DESCRIPTION:
XS GIS Cut Line= 3
        2348525.       13741275.        2349025.       13741225.
      2349425.01     13741625.01
#Sta/Elev= 30
  4497.6  455.07  4514.5  454.98  4545.3  452.89  4588.1  452.16  4608.2  450.76
  4645.8  449.53  4658.4  449.58  4691.2  448.13  4751.4  446.42    4779  445.06
  4899.6  442.16  4929.7  441.81  4947.3  440.17  4952.4   440.3  4969.9  438.69
  4977.7  436.91    4978  436.41    4982  436.41  4982.3  436.91  4997.6  439.37
  5014.2  439.26  5028.4  440.32  5070.8  441.73  5141.5  442.19  5268.8  444.38
  5311.2  445.88  5353.7  446.43  5466.8   449.2  5537.5  452.12  5565.8  452.81
#Mann= 5 ,-1 , 0
  4497.6    .035       0  4514.5     .05       0  4691.2     .07       0
  4977.7     .05       0  4982.3     .07       0
Bank Sta=4977.7,4982.3
XS Rating Curve= 0 ,0
Exp/Cntr=0.3,0.1

Type RM Length L Ch R = 1 ,12949   ,481,481,481
BEGIN DESCRIPTION:
SAWLOG CREEK 26.0
END DESCRIPTION:
XS GIS Cut Line= 3
      2348675.01       13741675.        2348975.       13741675.
        2349375.       13741725.
#Sta/Elev= 30
  4695.1  450.15  4705.1  450.08  4725.1  449.11  4758.1  448.21  4775.1   447.7
  4895.1  441.75  4925.1     441  4955.1  439.13  4997.6  437.95  5005.2  437.18
  5012.9  434.22  5013.2  433.72  5017.2  433.72  5017.6  434.22  5032.9  437.46
  5036.7  437.33  5045.5  438.37  5075.7  440.42  5085.8  440.57  5095.9  441.45
  5116.5  441.74  5126.1  441.57  5146.3   442.5  5176.5  443.01  5186.6  443.82
  5206.7   444.1  5279.8   446.6  5287.3  447.24  5327.7  448.81  5398.2  452.48
#Mann= 6 ,-1 , 0
  4695.1     .05       0  4758.1     .07       0  5012.9     .05       0
  5017.6     .07       0  5036.7      .1       0  5116.5     .07       0
Bank Sta=5012.9,5017.6
XS Rating Curve= 0 ,0
Exp/Cntr=0.3,0.1

Type RM Length L Ch R = 1 ,12468   ,454,454,454
BEGIN DESCRIPTION:
SAWLOG CREEK 25.0
END DESCRIPTION:
XS GIS Cut Line= 3
      2348674.97     13742425.02        2349075.       13742125.
      2349424.98     13742274.99
#Sta/Elev= 30
    4500  450.63  4513.6  451.14  4557.3  448.44  4613.6  448.25    4650   445.6
  4678.2  445.37  4692.7  446.17  4707.3  444.33  4721.9  443.44  4757.3  442.33
  4778.2  442.71  4821.9  440.07  4892.7  439.89    4900  438.68  4945.6   436.2
  4957.3  435.01  4992.7  434.99  4994.5  433.93  4994.9  433.43  4999.3  433.93
  5061.7  438.95  5118.5  439.28    5214  440.87  5219.4  440.39  5237.6  441.96
  5277.3  442.53  5295.6  443.43  5319.2  445.43  5348.2  448.95  5380.8  451.16
#Mann= 6 ,-1 , 0
    4500     .07       0  4945.6     .12       0  4994.5     .05       0
  4999.3     .12       0  5118.5     .07       0  5277.3     .12       0
Bank Sta=4994.5,4999.3
XS Rating Curve= 0 ,0
Exp/Cntr=0.3,0.1

Type RM Length L Ch R = 1 ,12014   ,448,448,448
BEGIN DESCRIPTION:
SAWLOG CREEK 24.0
END DESCRIPTION:
XS GIS Cut Line= 3
      2348825.02     13742674.99        2349225.       13742525.
      2349425.01       13742425.
#Sta/Elev= 30
    4577  448.11  4593.7  448.36  4598.3  448.47  4630.4  445.79  4670.2  445.56
  4683.8  444.22  4707.8  443.37  4730.9  443.44  4787.9  440.13  4818.2  439.02
  4848.4  438.79  4854.7  438.04  4903.6  435.84  4944.8  434.62  4964.1  433.87
  4972.1  434.15  4982.8  433.04  4986.7  431.16    4987  430.66  4991.1  430.66
  4991.5  431.16    5007  431.59  5012.6  433.85  5018.2  434.19  5034.9  434.13
  5095.4  436.76    5130  438.47  5160.7  442.99  5186.1  445.43  5227.8  447.99
#Mann= 9 ,-1 , 0
    4577     .05       0  4593.7     .07       0  4670.2     .05       0
  4730.9     .07       0  4944.8     .12       0  4986.7     .05       0
  4991.5     .12       0  5095.4     .07       0  5186.1     .12       0
Bank Sta=4986.7,4991.5
XS Rating Curve= 0 ,0
Exp/Cntr=0.3,0.1

Type RM Length L Ch R = 1 ,11566   ,445,445,445
BEGIN DESCRIPTION:
SAWLOG CREEK 23.0
END DESCRIPTION:
XS GIS Cut Line= 3
      2349074.99       13743075.        2349275.       13742925.
      2349575.03     13742724.98
#Sta/Elev= 30
  4749.6  443.79  4792.3   441.7  4821.5  438.23  4842.3  437.18  4856.9  435.78
  4942.3  432.59  4949.6  431.82  4956.9  428.21  4971.5  429.24  4975.3  428.12
  4975.6  427.62  4979.8  427.62  4980.2  428.12  4986.1  432.49  4992.3  431.15
  4996.5  432.95  5022.1   432.7  5058.2  433.59  5064.2  434.78  5071.7   434.9
  5079.2   434.2  5107.8  435.63  5136.3  436.09  5143.8  435.68  5166.4  436.75
  5172.4  436.41  5179.9  437.15  5301.6   442.2  5352.7   442.8  5360.2  443.39
#Mann= 3 ,-1 , 0
  4749.6     .12       0  4975.3     .05       0  4980.2     .12       0
Bank Sta=4975.3,4980.2
XS Rating Curve= 0 ,0
Exp/Cntr=0.3,0.1

Type RM Length L Ch R = 1 ,11121   ,461,461,461
BEGIN DESCRIPTION:
SAWLOG CREEK 22.0
END DESCRIPTION:
XS GIS Cut Line= 3
      2349175.02     13743324.99        2349525.       13743225.
      2350204.09     13743281.27
#Sta/Elev= 30
  4630.7  443.53  4693.1  440.42  4720.4  439.82  4787.1  437.01  4890.7  433.76
    4944   430.8  4972.6  430.89  4984.3  429.32  4992.1   427.1  4997.2   427.1
  5002.2  426.18  5002.6  425.68  5006.9  425.68  5007.3  426.18  5014.8  428.91
  5024.8  430.82  5052.6  431.75  5057.6  431.11  5115.1   432.7  5165.3  434.79
  5185.3  436.42  5205.4  437.24  5245.5  440.04  5275.6  441.24  5325.8  444.58
    5395  445.55  5486.4  447.25  5576.7  449.98  5616.8  450.03  5676.1  452.68
#Mann= 5 ,-1 , 0
  4630.7    .045       0  4787.1     .12       0  5002.2     .05       0
  5007.3     .12       0    5395     .07       0
Bank Sta=5002.2,5007.3
XS Rating Curve= 0 ,0
Exp/Cntr=0.3,0.1

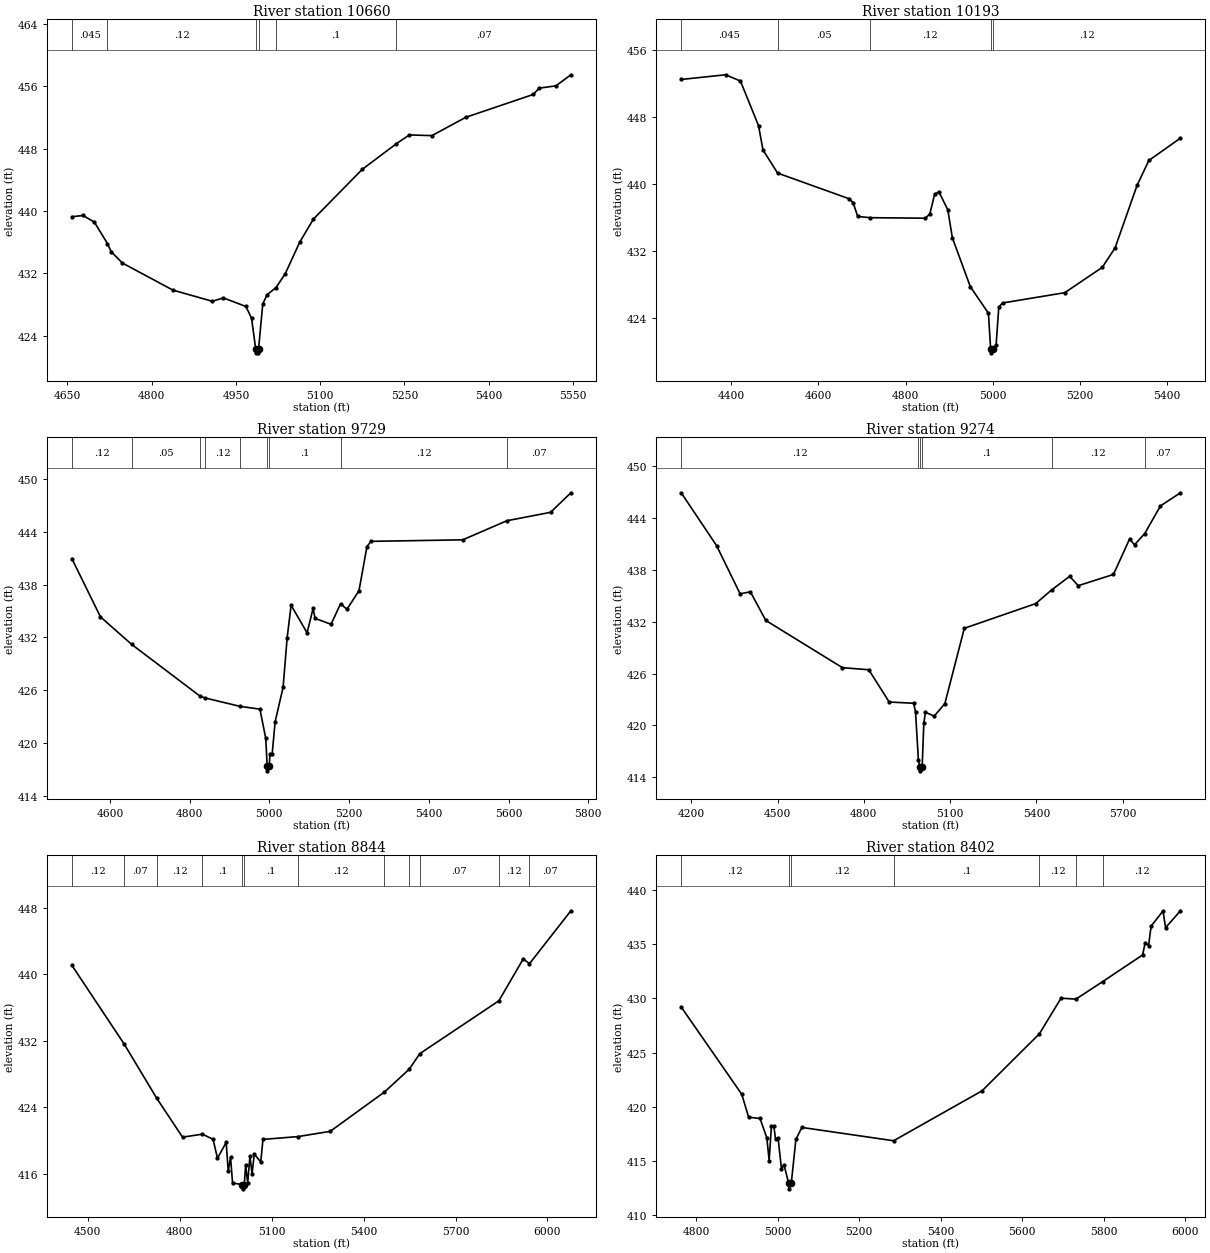
Type RM Length L Ch R = 1 ,10660   ,467,467,467
BEGIN DESCRIPTION:
SAWLOG CREEK 21.0
END DESCRIPTION:
XS GIS Cut Line= 3
      2349275.02       13743625.        2349625.       13743625.
      2350161.49     13743577.06
#Sta/Elev= 30
  4657.8  439.25  4677.8  439.41  4697.8  438.57  4721.3   435.8  4727.8  434.77
  4747.8  433.31  4837.8  429.83  4907.8   428.4  4927.8  428.83  4967.8  427.73
  4977.8  426.22  4985.2  422.28  4985.6  421.78    4990  421.78  4990.3  422.28
  4997.8  428.05  5005.3  429.22  5021.4  430.16  5037.9  431.95  5063.5  435.97
  5088.1  438.96  5174.9  445.33  5235.8  448.63  5258.8  449.75  5298.9  449.66
  5359.2  452.01  5479.6  454.95  5489.7  455.75  5519.8  456.05  5546.4  457.47
#Mann= 6 ,-1 , 0
  4657.8    .045       0  4721.3     .12       0  4985.2     .05       0
  4990.3     .12       0  5021.4      .1       0  5235.8     .07       0
Bank Sta=4985.2,4990.3
XS Rating Curve= 0 ,0
Exp/Cntr=0.3,0.1

Type RM Length L Ch R = 1 ,10193   ,464,464,464
BEGIN DESCRIPTION:
SAWLOG CREEK 20.0
END DESCRIPTION:
XS GIS Cut Line= 3
      2348733.92     13743843.84        2349425.       13744025.
      2349774.96     13744274.97
#Sta/Elev= 30
    4286  452.52  4387.3  453.08  4421.5  452.33  4462.9  446.99  4473.2  444.08
  4506.7  441.31    4670  438.25    4680  437.76  4690.3  436.12  4718.9  435.97
  4845.4  435.91  4855.7  436.41  4866.8  438.77  4876.4  439.08  4896.9  436.93
  4907.4  433.57  4948.7   427.7  4990.1  424.54  4995.2  420.29  4995.6  419.79
  5000.4  420.29  5007.8  420.76  5013.9  425.27  5022.6  425.76  5165.1  426.99
  5251.1  430.02  5280.6  432.36    5331  439.84    5358  442.82  5430.5   445.5
#Mann= 5 ,-1 , 0
    4286    .045       0  4506.7     .05       0  4718.9     .12       0
  4995.2     .05       0  5000.4     .12       0
Bank Sta=4995.2,5000.4
XS Rating Curve= 0 ,0
Exp/Cntr=0.3,0.1

Type RM Length L Ch R = 1 ,9729    ,455,455,455
BEGIN DESCRIPTION:
SAWLOG CREEK 19.0
END DESCRIPTION:
XS GIS Cut Line= 3
        2348975.       13744175.        2349375.       13744475.
      2350126.05     13744439.28
#Sta/Elev= 30
  4504.5  440.95  4576.4  434.33  4654.8   431.2  4825.7  425.35  4837.7  425.14
    4927  424.17  4976.4  423.86    4991  420.53  4994.6  417.36    4995  416.86
  4999.8  417.36  5001.4  418.74    5007  418.74  5014.5  422.43  5034.5  426.34
  5044.6  431.94  5054.6  435.65  5094.6  432.52  5109.7  435.28  5114.7  434.16
  5154.7  433.49  5178.5   435.8  5194.7   435.2  5224.8  437.29  5244.8   442.3
  5254.8   442.9    5485  443.07    5596  445.24  5705.3  446.19  5756.4  448.41
#Mann= 9 ,-1 , 0
  4504.5     .12       0  4654.8     .05       0  4825.7      .1       0
  4837.7     .12       0    4927      .1       0  4994.6     .05       0
  4999.8      .1       0  5178.5     .12       0    5596     .07       0
Bank Sta=4994.6,4999.8
XS Rating Curve= 0 ,0
Exp/Cntr=0.3,0.1

Type RM Length L Ch R = 1 ,9274    ,430,430,430
BEGIN DESCRIPTION:
SAWLOG CREEK 18.0
END DESCRIPTION:
XS GIS Cut Line= 3
      2348504.02     13745022.39        2349325.       13744875.
      2350134.29     13744480.33
#Sta/Elev= 30
  4165.9  446.92  4288.2  440.83  4370.1  435.24  4405.7  435.48  4459.4  432.16
  4725.7  426.69  4817.1  426.45  4888.2  422.71  4973.2  422.57  4979.7  421.54
  4989.7  415.96  4994.4  415.24  4994.9  414.74  5000.5  415.24  5002.8  415.24
  5008.5  420.26  5014.1  421.53  5044.5  421.07  5081.6  422.53  5149.2  431.25
  5397.1  434.11  5453.6  435.72  5515.3  437.27  5545.2  436.19  5667.5  437.49
  5723.7   441.6  5740.7  440.92  5776.3  442.23  5830.8  445.43  5900.4  446.95
#Mann= 6 ,-1 , 0
  4165.9     .12       0  4989.7      .1       0  4994.4     .05       0
  5000.5      .1       0  5453.6     .12       0  5776.3     .07       0
Bank Sta=4994.4,5000.5
XS Rating Curve= 0 ,0
Exp/Cntr=0.3,0.1

Type RM Length L Ch R = 1 ,8844    ,442,442,442
BEGIN DESCRIPTION:
SAWLOG CREEK 17.0
END DESCRIPTION:
XS GIS Cut Line= 3
      2349024.97     13745675.03        2349375.       13745275.
      2350174.97     13744525.02
#Sta/Elev= 30
  4448.3  441.08  4619.3  431.58  4724.7   425.1  4809.5  420.38  4874.4  420.74
  4909.1  420.12  4923.4  417.85  4951.9  419.74  4958.5  416.31  4966.1  417.95
  4972.7  414.87  5004.8  414.66  5005.3  414.16    5011  414.66  5015.3  417.01
  5022.1  414.88  5029.4  418.08  5036.3  415.98  5043.6  418.35  5064.6  417.38
  5071.9  420.11  5186.2  420.45  5291.2  421.08  5468.1  425.81  5548.8  428.55
  5583.5  430.43  5841.6   436.8  5920.9  441.84  5941.3  441.26  6076.4  447.63
#Mann= 12 ,-1 , 0
  4448.3     .12       0  4619.3     .07       0  4724.7     .12       0
  4874.4      .1       0  5004.8     .05       0    5011      .1       0
  5186.2     .12       0  5468.1      .1       0  5548.8     .12       0
  5583.5     .07       0  5841.6     .12       0  5941.3     .07       0
Bank Sta=5004.8,5011
XS Rating Curve= 0 ,0
Exp/Cntr=0.3,0.1

Type RM Length L Ch R = 1 ,8402    ,430,430,430
BEGIN DESCRIPTION:
SAWLOG CREEK 16.0
END DESCRIPTION:
XS GIS Cut Line= 3
      2349624.98     13745774.96        2349525.       13745575.
      2350125.03     13744774.97
#Sta/Elev= 30
  4764.1  429.19  4912.2  421.15    4929  419.03  4956.9  418.92  4973.7  417.12
  4979.3  415.02  4984.9  418.21  4990.8  418.21  4994.9  417.03  5001.2  417.12
  5009.5  414.27  5015.8  414.64  5027.2  412.92  5027.7  412.42  5033.5  412.92
  5044.9  416.99  5059.5  418.09  5284.4  416.86  5501.2  421.47  5641.9  426.74
  5694.9  430.03  5731.4  429.94  5796.7  431.55  5894.9  434.02  5901.2  435.16
  5909.5  434.89  5915.8  436.69  5944.9  438.08  5951.2  436.54  5987.7   438.1
#Mann= 7 ,-1 , 0
  4764.1     .12       0  5027.2     .05       0  5033.5     .12       0
  5284.4      .1       0  5641.9     .12       0  5731.4     .07       0
  5796.7     .12       0
Bank Sta=5027.2,5033.5
XS Rating Curve= 0 ,0
Exp/Cntr=0.3,0.1

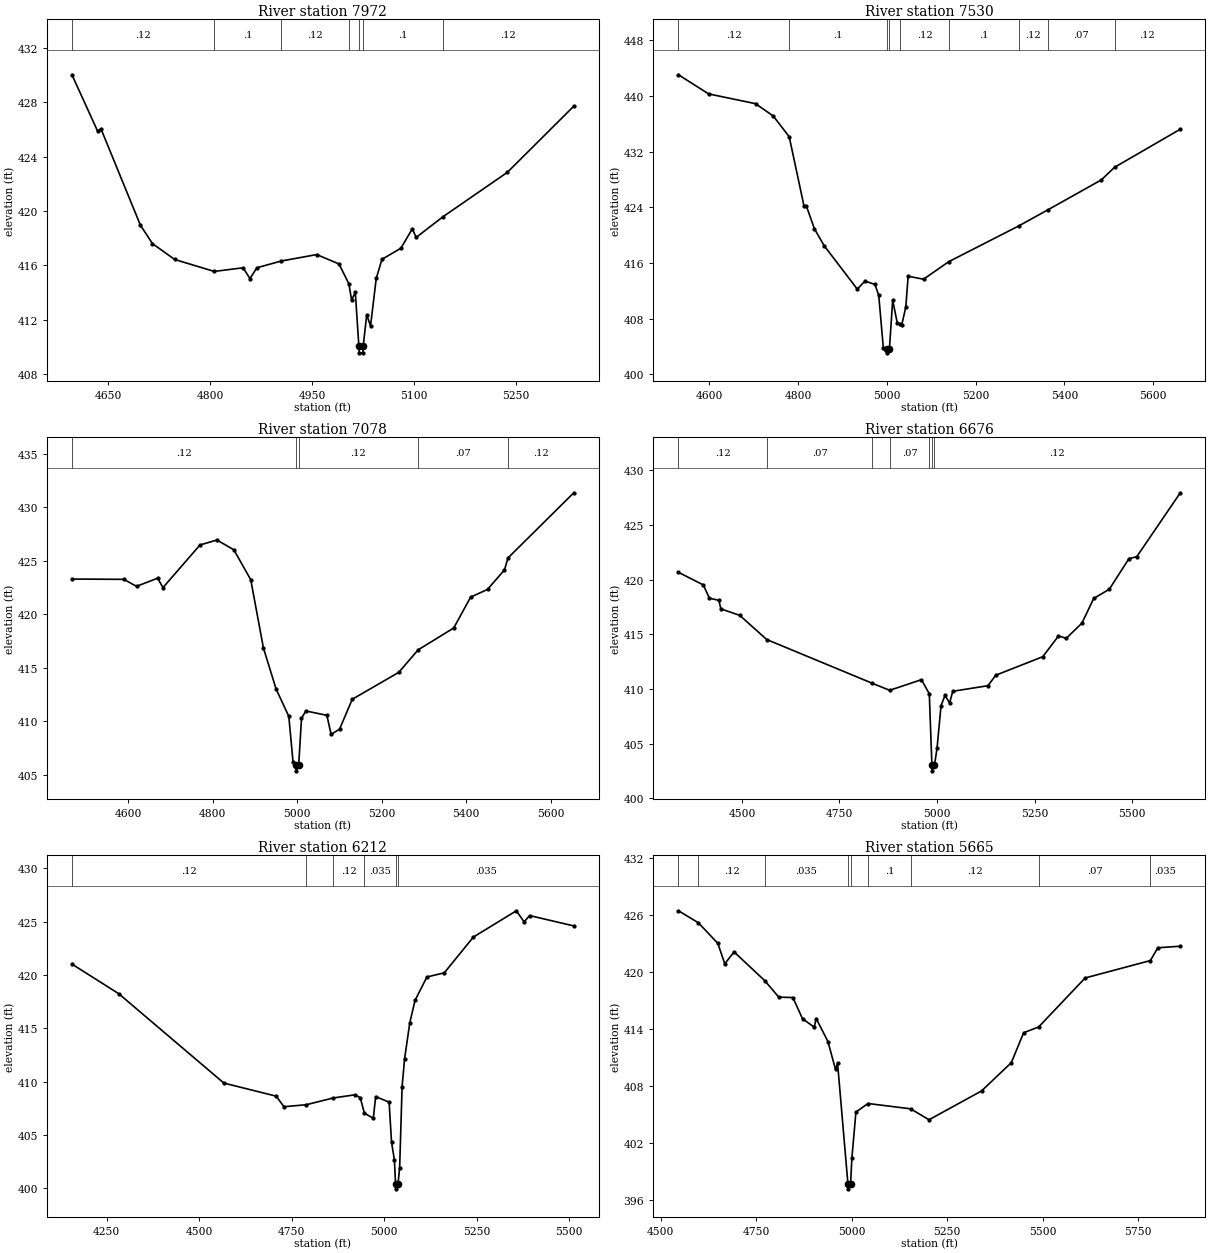
Type RM Length L Ch R = 1 ,7972    ,442,442,442
BEGIN DESCRIPTION:
SAWLOG CREEK 15.0
END DESCRIPTION:
XS GIS Cut Line= 3
      2349825.01     13745774.96        2349875.       13745375.
      2350025.01     13745074.98
#Sta/Elev= 30
  4596.3  430.02    4634  425.88  4639.1  426.03    4697  418.96  4714.7   417.6
  4747.4  416.43  4805.7  415.55  4848.2  415.82  4858.3  415.02  4868.4  415.82
  4904.6  416.32  4956.5  416.79  4989.3   416.1  5003.8  414.64  5007.8  413.45
  5013.3  414.01  5018.5  410.06    5019  409.56  5024.4  409.56  5024.9  410.06
  5030.1  412.36  5035.7  411.54  5044.1  415.04  5052.5  416.44  5080.4  417.26
  5097.2  418.69  5102.8  418.05  5141.9  419.56    5237  422.84  5334.8  427.71
#Mann= 7 ,-1 , 0
  4596.3     .12       0  4805.7      .1       0  4904.6     .12       0
  5003.8      .1       0  5018.5     .05       0  5024.9      .1       0
  5141.9     .12       0
Bank Sta=5018.5,5024.9
XS Rating Curve= 0 ,0
Exp/Cntr=0.3,0.1

Type RM Length L Ch R = 1 ,7530    ,452,452,452
BEGIN DESCRIPTION:
E20775
END DESCRIPTION:
XS GIS Cut Line= 3
       2350035.7      13746110.6      2350191.74     13745531.59
       2350425.8     13745055.26
#Sta/Elev= 30
  4530.5  443.06  4598.4  440.31    4704  438.91  4743.9  437.14  4779.9  434.16
  4813.4  424.16  4818.6   424.2  4836.7  420.93  4858.5  418.51  4933.2  412.26
  4950.6  413.41  4973.1  412.93  4981.6  411.35    4992  403.76  4999.2   403.6
  4999.7   403.1  5005.6   403.6    5013  410.67  5023.1  407.46  5029.8  407.23
  5033.4  407.11  5042.6   409.7  5047.8  414.11  5082.5  413.68  5139.3   416.2
  5296.4  421.32  5362.6  423.65  5482.9  427.95  5512.7  429.76  5660.9  435.24
#Mann= 9 ,-1 , 0
  4530.5     .12       0  4779.9      .1       0  4999.2     .05       0
  5005.6      .1       0  5029.8     .12       0  5139.3      .1       0
  5296.4     .12       0  5362.6     .07       0  5512.7     .12       0
Bank Sta=4999.2,5005.6
XS Rating Curve= 0 ,0
Exp/Cntr=0.3,0.1

Type RM Length L Ch R = 1 ,7078    ,402,402,402
BEGIN DESCRIPTION:
E20774
END DESCRIPTION:
XS GIS Cut Line= 3
      2350507.94     13746307.67      2350540.79      13745728.7
      2350565.43      13745120.9
#Sta/Elev= 30
  4466.9  423.29  4589.8  423.26  4619.8  422.61  4669.9  423.37  4682.4  422.49
  4770.1  426.47  4810.1  426.93  4850.2  426.02  4890.2  423.23  4920.3  416.85
  4950.3  413.02  4980.4  410.47  4990.4   406.2  4997.2  405.89  4997.7  405.39
  5003.7  405.89  5010.4  410.28  5020.5  410.98  5070.5  410.57  5080.5  408.79
  5100.5  409.28  5130.6  412.07  5240.7  414.58  5286.5  416.68  5370.8  418.72
  5410.8   421.6  5450.8  422.32  5490.9  424.14  5499.3  425.26  5655.1  431.34
#Mann= 5 ,-1 , 0
  4466.9     .12       0  4997.2     .05       0  5003.7     .12       0
  5286.5     .07       0  5499.3     .12       0
Bank Sta=4997.2,5003.7
XS Rating Curve= 0 ,0
Exp/Cntr=0.3,0.1

Type RM Length L Ch R = 1 ,6676    ,464,464,464
BEGIN DESCRIPTION:
E20773
END DESCRIPTION:
XS GIS Cut Line= 3
      2350680.41     13746393.93      2350902.16     13745847.78
      2350955.54     13745153.77
#Sta/Elev= 30
  4337.6  420.66  4401.2  419.51  4416.8   418.3  4440.9   418.1  4446.3  417.32
  4494.5  416.73  4563.6  414.52  4834.1  410.52  4878.6  409.88  4959.9  410.85
  4980.1  409.56  4986.8  403.02  4987.3  402.52  4993.3  403.02    5000  404.61
  5010.1  408.46  5020.1  409.41  5032.2  408.73  5040.2  409.79  5130.4   410.3
  5150.5  411.26  5270.8  412.95    5311  414.84    5331  414.63  5371.1  416.02
  5401.2  418.27  5441.3  419.12  5491.5  421.91  5511.5  422.09  5623.1  427.93
#Mann= 7 ,-1 , 0
  4337.6     .12       0  4563.6     .07       0  4834.1     .12       0
  4878.6     .07       0  4980.1     .12       0  4986.8     .05       0
  4993.3     .12       0
Bank Sta=4986.8,4993.3
XS Rating Curve= 0 ,0
Exp/Cntr=0.3,0.1

Type RM Length L Ch R = 1 ,6212    ,547,547,547
BEGIN DESCRIPTION:
E20772
END DESCRIPTION:
XS GIS Cut Line= 3
      2350750.23      13746439.1       2351374.4     13745708.17
      2351596.02     13745379.83
#Sta/Elev= 30
  4155.8  421.03  4282.4  418.25  4566.7  409.87  4708.4  408.64  4729.2  407.65
  4789.7  407.84  4861.9  408.47  4921.4  408.77  4935.6   408.5  4946.7  407.05
  4970.8  406.57  4977.3   408.6  5013.6  408.08  5020.2  404.31  5027.9  402.67
    5031  400.45  5031.5  399.95  5037.8  400.45  5042.1  401.92  5048.7  409.51
  5055.4  412.14  5069.6  415.54  5083.8  417.63  5115.8  419.82  5162.9  420.21
  5241.4  423.56  5357.7  426.03  5378.7  424.99  5393.7  425.58  5513.1  424.61
#Mann= 6 ,-1 , 0
  4155.8     .12       0  4789.7    .035       0  4861.9     .12       0
  4946.7    .035       0    5031    .035       0  5037.8    .035       0
Bank Sta=5031,5037.8
XS Rating Curve= 0 ,0
Exp/Cntr=0.3,0.1

Type RM Length L Ch R = 1 ,5665    ,471,471,471
BEGIN DESCRIPTION:
E20771
END DESCRIPTION:
XS GIS Cut Line= 3
      2351197.83     13746701.89      2351448.31     13746012.04
      2351624.52     13745458.84
#Sta/Elev= 30
  4546.5  426.47  4598.6  425.21  4649.6  423.04  4667.8  420.89  4692.1  422.14
  4772.2  419.13  4809.2  417.38  4846.1  417.34  4871.4  415.11    4902  414.22
  4907.3  415.13    4938  412.71  4957.9  409.77  4963.2  410.44  4990.4  397.71
  4990.9  397.21  4997.3  397.71  5000.7  400.45  5011.3  405.29    5043  406.19
  5154.5  405.63  5202.8  404.48  5340.3  407.51  5418.4  410.49  5450.6  413.64
  5489.8  414.24  5611.7   419.4  5782.6  421.23  5802.1  422.58    5861  422.74
#Mann= 9 ,-1 , 0
  4546.5     .07       0  4598.6     .12       0  4772.2    .035       0
  4990.4    .035       0  4997.3    .035       0    5043      .1       0
  5154.5     .12       0  5489.8     .07       0  5782.6    .035       0
Bank Sta=4990.4,4997.3
XS Rating Curve= 0 ,0
Exp/Cntr=0.3,0.1

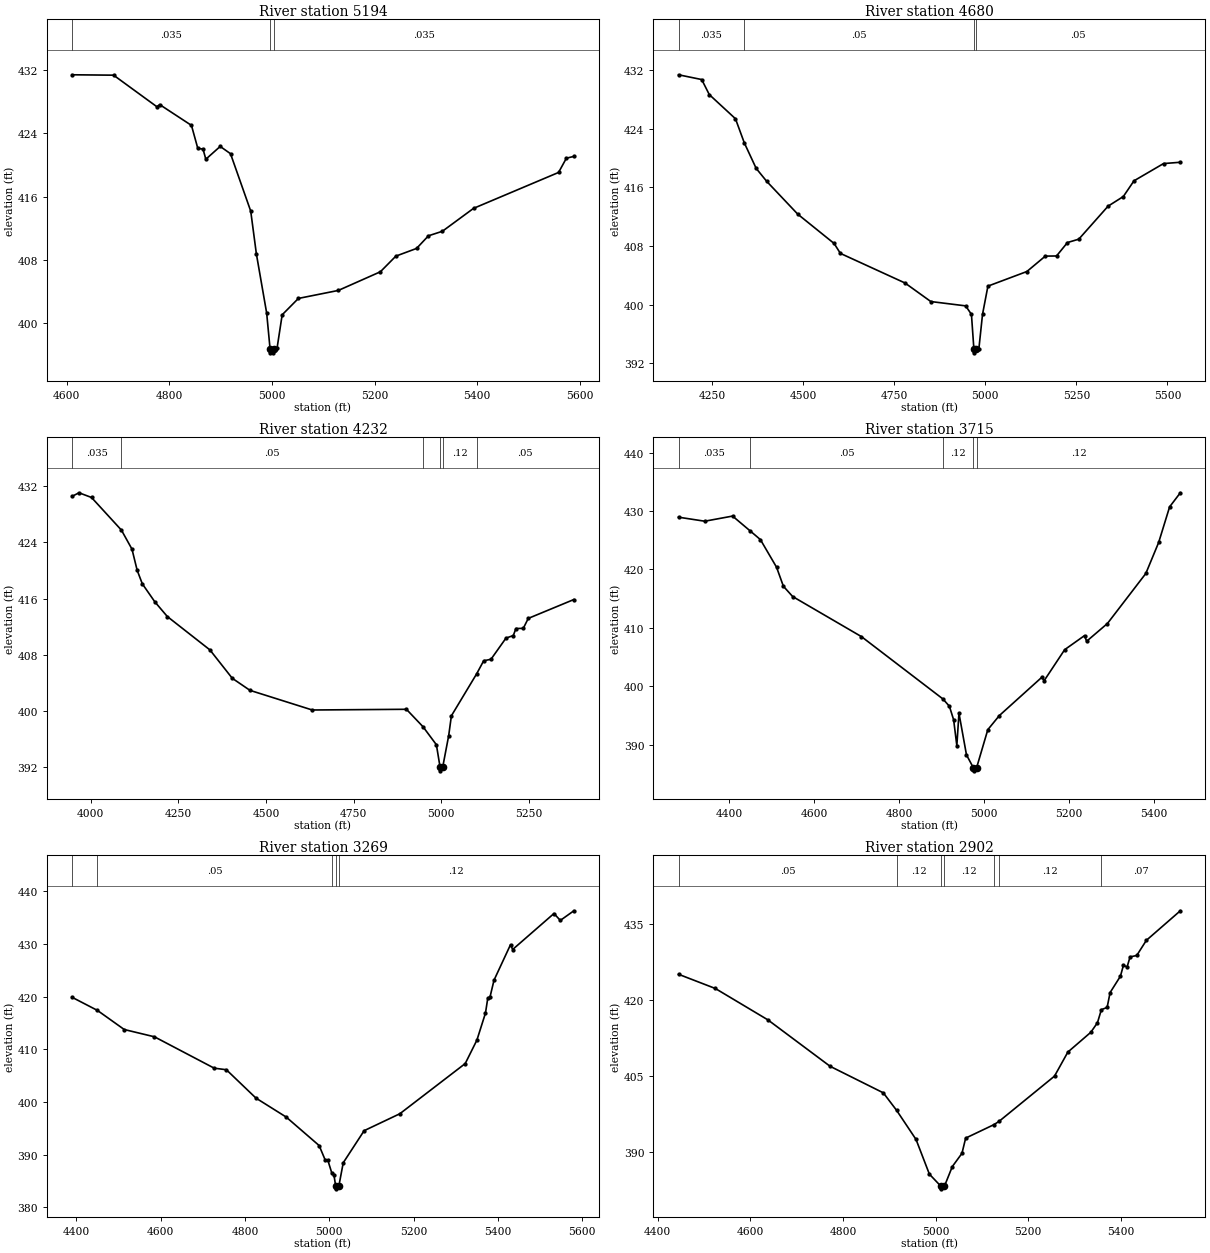
Type RM Length L Ch R = 1 ,5194    ,514,514,514
BEGIN DESCRIPTION:
E20770
END DESCRIPTION:
XS GIS Cut Line= 3
      2351645.43     13746434.98      2351768.61     13746184.51
      2351686.48     13745490.48
#Sta/Elev= 30
  4610.2  431.41  4691.1  431.36  4775.5  427.37    4781  427.64  4842.9  425.01
  4855.3  422.09  4865.4  422.02  4870.9  420.73  4898.9  422.35    4919  421.43
  4958.4  414.17  4969.4  408.77  4989.5  401.27  4996.1  396.75  4996.6  396.25
  5002.5  396.25    5003  396.75  5009.7  396.82  5019.7  401.06  5051.3  403.13
  5129.1  404.14  5211.1   406.5  5241.3  408.48  5281.6  409.45  5304.8  411.05
  5331.9  411.62  5392.7  414.52  5558.4  419.06  5573.6  420.86  5588.2  421.09
#Mann= 3 ,-1 , 0
  4610.2    .035       0  4996.1    .035       0    5003    .035       0
Bank Sta=4996.1,5003
XS Rating Curve= 0 ,0
Exp/Cntr=0.3,0.1

Type RM Length L Ch R = 1 ,4680    ,448,448,448
BEGIN DESCRIPTION:
E20769
END DESCRIPTION:
XS GIS Cut Line= 3
      2351711.08     13746389.86      2352064.28     13746118.81
      2352216.13     13745199.48
#Sta/Elev= 30
  4158.4  431.33    4222  430.68  4242.8  428.63  4314.6  425.34  4338.9  422.05
  4371.5  418.57  4400.5   416.8  4485.7  412.33  4585.4  408.34  4602.6  406.99
  4779.8  402.96  4850.7  400.43  4946.3  399.84  4962.2  398.68  4968.9  393.94
  4969.4  393.44  4975.8  393.94  4982.5  393.95  4992.6  398.69  5007.4  402.53
  5114.3  404.52  5164.9  406.62  5195.7  406.64  5225.7  408.47  5256.8  408.93
  5337.2  413.43    5379  414.74  5408.2  416.88  5489.3  419.23  5535.4  419.41
#Mann= 4 ,-1 , 0
  4158.4    .035       0  4338.9     .05       0  4968.9     .05       0
  4975.8     .05       0
Bank Sta=4968.9,4975.8
XS Rating Curve= 0 ,0
Exp/Cntr=0.3,0.1

Type RM Length L Ch R = 1 ,4232    ,517,517,517
BEGIN DESCRIPTION:
E20768
END DESCRIPTION:
XS GIS Cut Line= 3
      2351739.86     13746418.58      2352113.55     13746151.66
      2352848.63     13745515.14
#Sta/Elev= 30
  3946.4  430.57  3966.2  431.08  4001.9  430.41  4087.2  425.76  4117.3  423.05
  4132.1  420.04  4146.8  418.11  4182.4  415.55  4218.1  413.45  4339.7  408.69
  4403.4  404.65  4453.9  402.93  4631.6  400.13  4900.3  400.23  4947.7  397.74
  4985.8  395.18  4996.4  391.96  4996.9  391.46  5003.7  391.96  5020.9  396.48
  5028.6   399.3  5100.4  405.26  5120.7  407.14  5141.6  407.36  5184.3  410.37
  5205.2  410.74  5212.8  411.74  5233.7  411.76  5247.9  413.18    5378  415.87
#Mann= 6 ,-1 , 0
  3946.4    .035       0  4087.2     .05       0  4947.7     .12       0
  4996.4     .05       0  5003.7     .12       0  5100.4     .05       0
Bank Sta=4996.4,5003.7
XS Rating Curve= 0 ,0
Exp/Cntr=0.3,0.1

Type RM Length L Ch R = 1 ,3715    ,446,446,446
BEGIN DESCRIPTION:
E20767
END DESCRIPTION:
XS GIS Cut Line= 3
      2351706.99     13746480.19      2352203.89     13746209.15
      2352815.79     13746147.55
#Sta/Elev= 30
    4281  428.93  4342.7  428.24  4408.2  429.12  4449.1  426.61  4473.7  425.09
  4511.7  420.36  4527.8   417.1  4549.6  415.34  4711.6  408.47  4903.1  397.81
  4918.5  396.55  4928.5  394.22    4936   389.8    4941  395.36  4958.7  388.22
  4975.1  385.99  4975.6  385.49  4982.4  385.99  5008.9  392.54  5036.1  394.96
  5136.3  401.53  5141.3  400.91  5189.8  406.24  5236.5  408.65  5241.5  407.68
  5290.4  410.72  5380.8  419.29    5411   424.6  5436.8   430.7    5462  433.11
#Mann= 5 ,-1 , 0
    4281    .035       0  4449.1     .05       0  4903.1     .12       0
  4975.1     .05       0  4982.4     .12       0
Bank Sta=4975.1,4982.4
XS Rating Curve= 0 ,0
Exp/Cntr=0.3,0.1

Type RM Length L Ch R = 1 ,3269    ,367,367,367
BEGIN DESCRIPTION:
E20766
END DESCRIPTION:
XS GIS Cut Line= 3
      2351809.68     13746964.74       2352528.3      13746369.3
      2352781.49     13746324.38
#Sta/Elev= 30
  4389.8  419.88  4449.9  417.39  4513.6  413.76  4585.2  412.38  4727.1  406.42
  4755.8  406.13  4826.1  400.74  4897.7  397.15  4975.9  391.74  4990.2  389.01
  4996.7  388.91  5005.7  386.59    5011  386.18  5015.2  384.02  5015.7  383.52
  5022.6  384.02  5033.1  388.47  5082.7  394.56  5167.3  397.77  5322.5   407.3
  5350.2  411.75  5370.5  416.88  5375.9  419.67    5381  419.84  5390.8  423.13
  5429.9  429.86    5435  428.95    5533  435.78  5548.1  434.47  5580.2   436.3
#Mann= 5 ,-1 , 0
  4389.8    .035       0  4449.9     .05       0  5005.7     .12       0
  5015.2     .05       0  5022.6     .12       0
Bank Sta=5015.2,5022.6
XS Rating Curve= 0 ,0
Exp/Cntr=0.3,0.1

Type RM Length L Ch R = 1 ,2902    ,345,345,345
BEGIN DESCRIPTION:
E20765
END DESCRIPTION:
XS GIS Cut Line= 2
      2352187.48      13747268.6      2352869.14     13746426.78
#Sta/Elev= 30
    4445  425.14  4524.4  422.33    4638  416.11  4772.3  406.92  4887.1  401.67
  4915.8   398.2  4957.7  392.44  4986.5  385.58  5011.5  383.17    5012  382.67
  5018.9  383.17    5036  387.08  5056.8  389.69  5064.8  392.71  5125.9  395.38
  5136.8  396.02  5256.6  404.98  5285.4  409.74    5335  413.66  5349.3  415.55
  5357.8  418.14  5370.2  418.58  5376.6  421.52  5398.9  424.76  5405.3  426.89
  5413.3  426.59  5419.7  428.58  5434.1  428.86  5454.9  431.86  5528.2  437.71
#Mann= 7 ,-1 , 0
    4445     .05       0  4915.8     .12       0  5011.5     .05       0
  5018.9     .12       0  5125.9      .1       0  5136.8     .12       0
  5357.8     .07       0
Bank Sta=5011.5,5018.9
XS Rating Curve= 0 ,0
Exp/Cntr=0.3,0.1