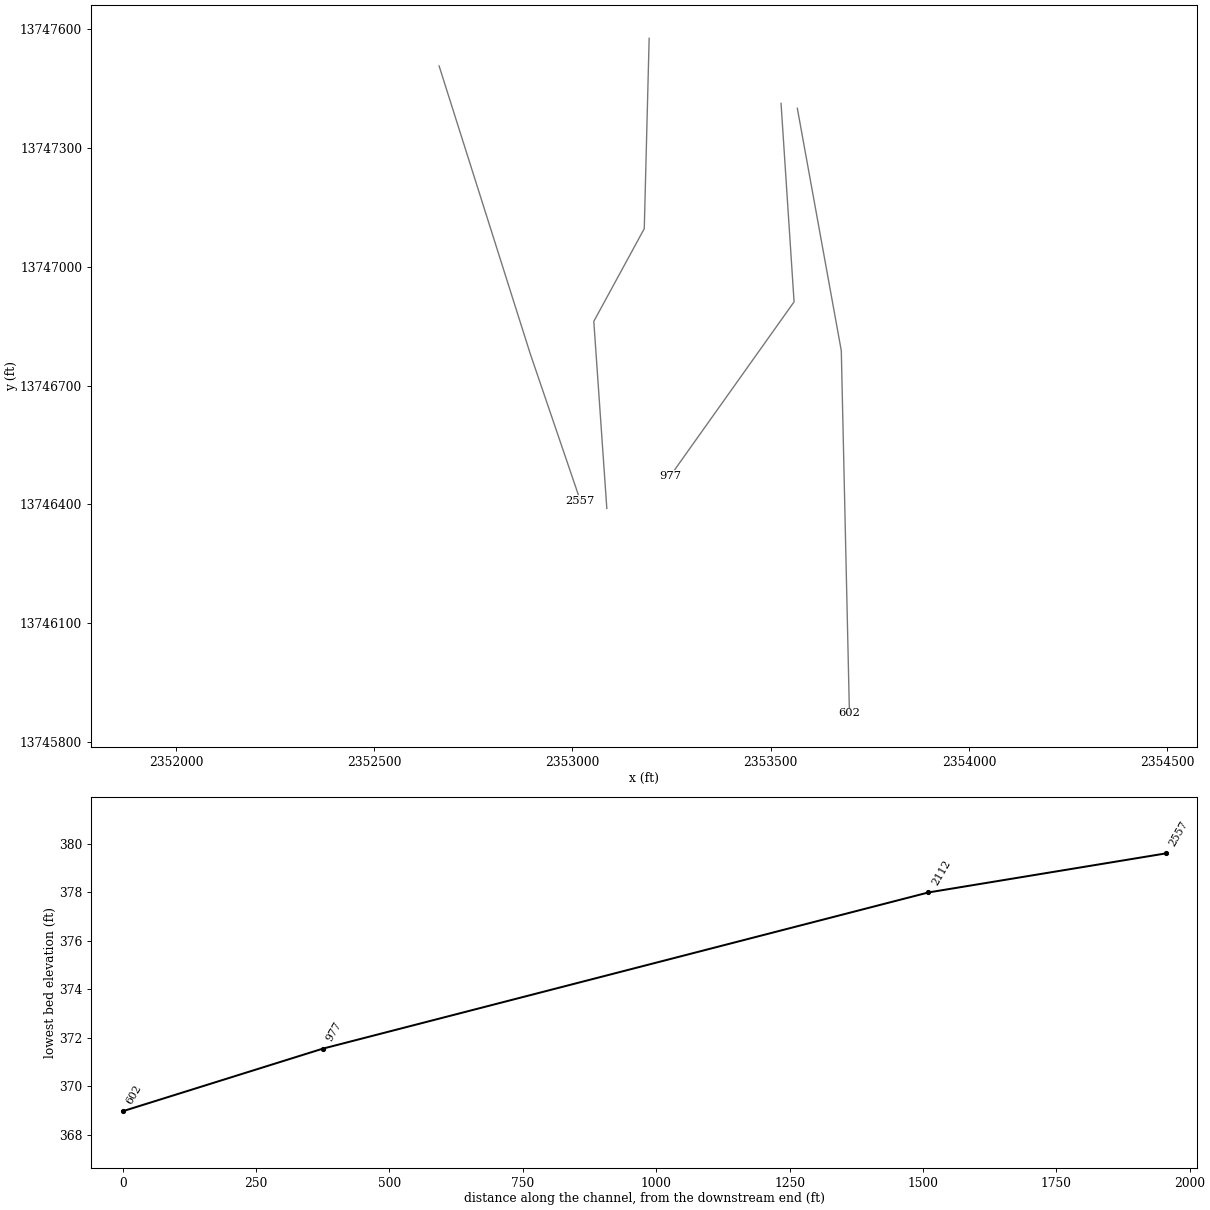
HEC-RAS study SAWLOG CREEK.prj: SAWLOG CREEK Base Level Engineering

--- SAWLOG CREEK.g01 (geometry) --- (continued)

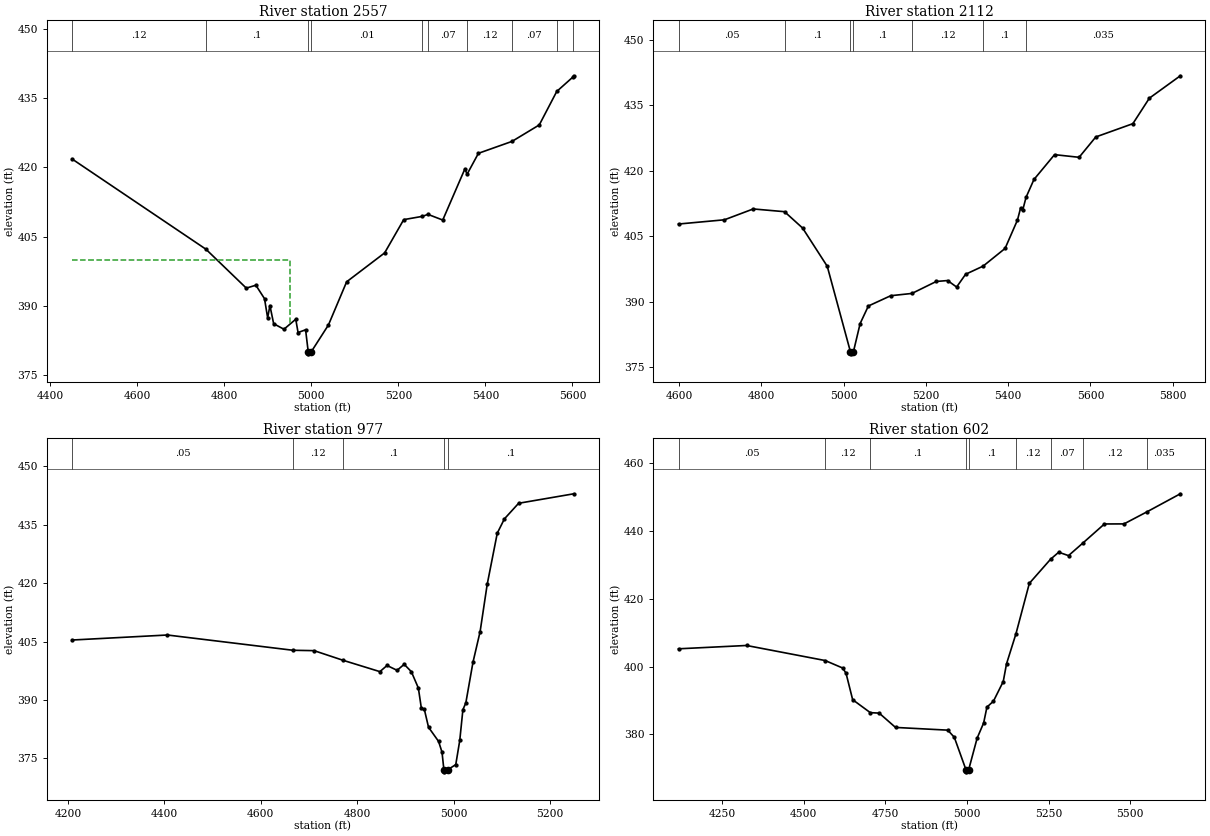
Type RM Length L Ch R = 1 ,2557    ,445,445,445
BEGIN DESCRIPTION:
E20764
END DESCRIPTION:
XS GIS Cut Line= 3
       2352663.8     13747506.82      2352893.77     13746779.94
      2353019.89     13746409.72
#Sta/Elev= 30
  4449.9  421.82  4757.6  402.27  4850.4  393.84  4872.4  394.47  4892.3  391.55
  4899.5  387.38  4904.7  390.06  4913.3  386.13    4937  384.93  4964.1   387.1
  4969.4  384.22  4986.7  384.81  4992.7   380.1  4993.2   379.6  5000.1   380.1
  5039.2  385.85  5081.1  395.21  5168.4  401.47  5212.3  408.68  5255.2  409.39
    5268  409.82    5302  408.59  5352.6  419.61  5358.2  418.56    5384  423.05
  5461.2  425.63  5523.9   429.2  5564.1  436.46    5602  439.64  5603.4  439.85
#Mann= 10 ,-1 , 0
  4449.9     .12       0  4757.6      .1       0  4992.7     .05       0
  5000.1     .01       0  5255.2     .12       0    5268     .07       0
  5358.2     .12       0  5461.2     .07       0  5564.1     .12       0
    5602     .07       0
#XS Ineff= 2 , 0
       0    4950     400               0
Permanent Ineff=
       F       F
Bank Sta=4992.7,5000.1
XS Rating Curve= 0 ,0
Exp/Cntr=0.3,0.1

Type RM Length L Ch R = 1 ,2112    ,1135,1135,1135
BEGIN DESCRIPTION:
E20763
END DESCRIPTION:
XS GIS Cut Line= 4
      2353193.54      13747576.6      2353181.22     13747096.14
      2353053.93     13746862.07      2353086.77     13746389.87
#Sta/Elev= 30
  4598.3  407.78  4709.9  408.75    4780  411.24  4856.1  410.61    4900  406.86
    4960  398.08  5016.3  378.49  5016.8  377.99  5023.7  378.49    5040  384.95
    5060  388.97  5114.4  391.33  5165.9  391.85  5225.2   394.6  5252.8  394.81
  5274.6  393.32  5296.5  396.25  5339.1  398.12  5392.5  402.18  5422.6  408.69
  5430.3  411.49  5435.3  410.93  5443.5  413.91  5462.7     418  5512.8   423.7
  5572.5  423.09  5613.1  427.76  5703.3  430.81  5743.4  436.66  5818.7   441.8
#Mann= 7 ,-1 , 0
  4598.3     .05       0  4856.1      .1       0  5016.3     .05       0
  5023.7      .1       0  5165.9     .12       0  5339.1      .1       0
  5443.5    .035       0
Bank Sta=5016.3,5023.7
XS Rating Curve= 0 ,0
Exp/Cntr=0.3,0.1

Type RM Length L Ch R = 1 ,977     ,375,375,375
BEGIN DESCRIPTION:
E20762
END DESCRIPTION:
XS GIS Cut Line= 3
      2353526.16     13747412.36      2353559.02     13746911.35
      2353246.94     13746471.98
#Sta/Elev= 30
  4208.5  405.41  4406.3   406.7  4666.7  402.78  4710.6  402.68  4770.8   400.2
  4847.1  397.29  4861.9  398.87  4882.8  397.63  4897.5  399.17  4912.3  397.29
  4926.9  393.08  4933.2  387.83  4939.3   387.6    4948     383  4968.9  379.36
    4976  376.59  4979.9  372.05  4980.4  371.55  4987.4  372.05  5004.5  373.41
  5012.8  379.62  5019.3  387.51  5025.4  389.27  5040.2   399.7    5055  407.57
  5069.7   419.7  5090.6  432.86  5105.4  436.53  5134.9  440.54  5249.5  442.98
#Mann= 5 ,-1 , 0
  4208.5     .05       0  4666.7     .12       0  4770.8      .1       0
  4979.9     .05       0  4987.4      .1       0
Bank Sta=4979.9,4987.4
XS Rating Curve= 0 ,0
Exp/Cntr=0.3,0.1

Type RM Length L Ch R = 1 ,602     ,0,0,0
BEGIN DESCRIPTION:
E20761
END DESCRIPTION:
XS GIS Cut Line= 3
      2353567.23     13747400.03       2353678.1     13746788.16
      2353698.64     13745872.43
#Sta/Elev= 30
  4116.1  405.24  4324.5  406.22  4565.5  401.78  4619.2  399.57  4629.4  398.04
  4649.7  390.24  4703.8  386.42    4731  386.28  4781.1  382.06  4941.2  381.26
  4961.2  379.16  4997.4  369.47  4997.9  368.97  5004.9  369.47  5031.2   378.9
  5051.2  383.39  5061.2  388.05  5081.2   389.8  5111.2  395.59  5121.2  400.79
  5150.2  409.68  5191.2  424.54  5256.3  431.65  5281.2  433.71  5311.2  432.71
  5354.7  436.37  5421.3  442.04  5481.3  442.06  5551.5  445.61  5653.9  450.94
#Mann= 9 ,-1 , 0
  4116.1     .05       0  4565.5     .12       0  4703.8      .1       0
  4997.4     .05       0  5004.9      .1       0  5150.2     .12       0
  5256.3     .07       0  5354.7     .12       0  5551.5    .035       0
Bank Sta=4997.4,5004.9
XS Rating Curve= 0 ,0
Exp/Cntr=0.3,0.1

Chan Stop Cuts=-1
Use User Specified Reach Order=0
Composite Channel Slope=5