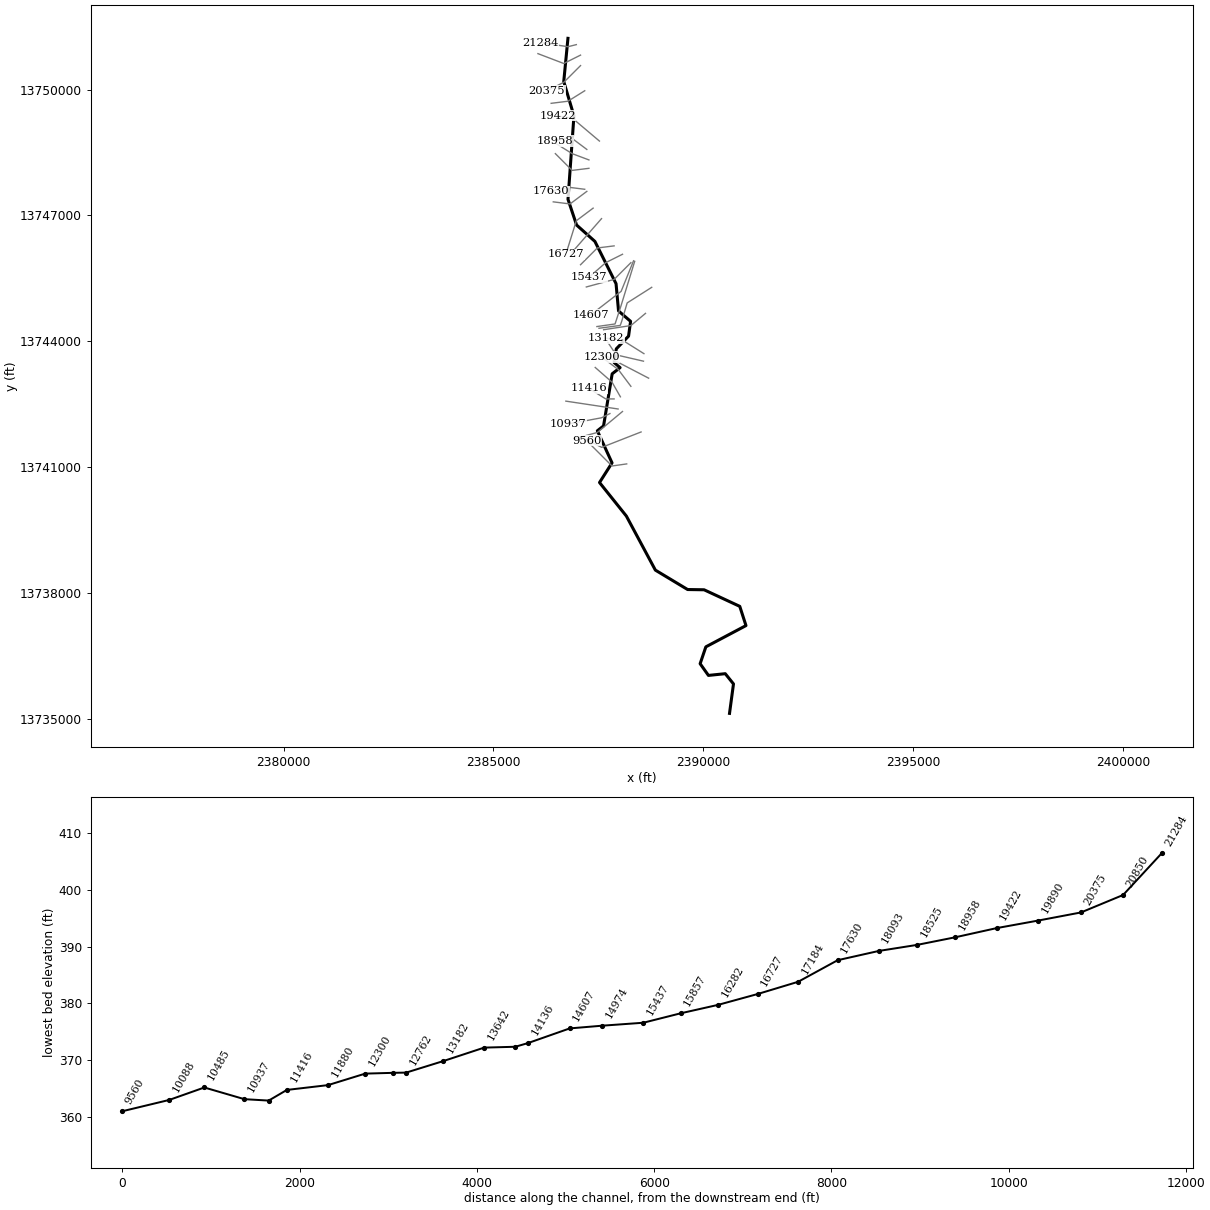
--- Stream0256.prj (project) ---

Proj Title=Stream0256 Base Level Engineering
Current Plan=p01
Default Exp/Contr=0.3,0.1
English Units
Geom File=g01
Flow File=f01
Plan File=p01
Y Axis Title=Elevation
X Axis Title(PF)=Main Channel Distance
X Axis Title(XS)=Station
BEGIN DESCRIPTION:
Stream0256
END DESCRIPTION:
DSS Export Rating Curves= 0
DSS Export Rating Curve Sorted= 0
DSS Export Volume Flow Curves= 0
DXF OffsetX= 0
DXF OffsetY= 0
DXF ScaleX= 1
DXF ScaleY= 10

--- Stream0256.p01 (plan) ---

Plan Title=Multiple Run
Short Identifier=Multiple
Geom File=g01
Flow File=f01
Subcritical Flow
K Sum by GR= 0
Std Step Tol= 0.01
Critical Tol= 0.01
Num of Std Step Trials= 20
Max Error Tol= 0.3
Flow Tol Ratio= 0.001
Split Flow NTrial= 30
Split Flow Tol= 0.02
Split Flow Ratio= 0.02
Log Output Level= 0
Friction Slope Method= 1
Unsteady Friction Slope Method= 2
Unsteady Bridges Friction Slope Method= 1
Parabolic Critical Depth
Global Vel Dist=  1 , 1 , 1
Global Log Level= 0
CheckData=True
Encroach Param= -1, 0, 0, 0
BEGIN DESCRIPTION:
Multiple Run
END DESCRIPTION:

--- Stream0256.f01 (steady flow) ---

Flow Title=Multiple
Number of Profiles=7
Profile Names=10-year,25-year,50-year,1pct_min,100-year,1pct_plu,500-year
River Rch & RM= Stream0256,Reach-1,21284
     870    1431    1949    1285    2563    5115    4394
River Rch & RM= Stream0256,Reach-1,20375
    1349    2277    3155    2113    4216    8411    7462
River Rch & RM= Stream0256,Reach-1,18958
    1697    2893    4033    2716    5420   10814    9703
River Rch & RM= Stream0256,Reach-1,17184
    1866    3187    4446    2995    5976   11924   10705
River Rch & RM= Stream0256,Reach-1,12300
    2194    3774    5292    3581    7144   14255   12913
River Rch & RM= Stream0256,Reach-1,10937
    2345    4029    5646    3815    7612   15188   13724
River Rch & RM= Stream0256,Reach-1,6871
    2446    4195    5869    3958    7898   15758   14185
Boundary for River Rch & Prof#=Stream0256,Reach-1,1
Up Type=0
Dn Type=3
Dn Slope=0.005
Boundary for River Rch & Prof#=Stream0256,Reach-1,2
Up Type=0
Dn Type=3
Dn Slope=0.005
Boundary for River Rch & Prof#=Stream0256,Reach-1,3
Up Type=0
Dn Type=3
Dn Slope=0.005
Boundary for River Rch & Prof#=Stream0256,Reach-1,4
Up Type=0
Dn Type=3
Dn Slope=0.005
Boundary for River Rch & Prof#=Stream0256,Reach-1,5
Up Type=0
Dn Type=3
Dn Slope=0.005
Boundary for River Rch & Prof#=Stream0256,Reach-1,6
Up Type=0
Dn Type=3
Dn Slope=0.005
Boundary for River Rch & Prof#=Stream0256,Reach-1,7
Up Type=0
Dn Type=3
Dn Slope=0.005

--- Stream0256.g01 (geometry) ---

Geom Title=Existing Conditions
Program Version=4.10

River Reach=Stream0256      ,Reach-1
Reach XY= 30
        2386775.       13751225.      2386675.05     13750195.04
      2386917.67      13749375.1      2386776.09     13747385.54
      2386980.52     13746772.57      2387417.26     13746381.45
      2387921.17     13745373.42      2387980.45     13744722.55
      2388267.54     13744475.22      2388219.27     13744122.45
      2387927.26     13743819.06      2387875.52     13743490.89
      2388017.53     13743371.39      2387828.81     13743223.45
      2387623.46     13741980.85      2387475.49     13741864.51
      2387825.49     13741099.81      2387527.16     13740630.98
      2388166.84     13739831.05      2388858.29     13738541.64
      2389626.55     13738078.75      2390019.06     13738072.74
      2390869.27     13737677.55      2391017.25     13737218.81
      2390061.26      13736711.8      2389924.84     13736309.76
      2390122.56     13736030.39      2390523.75     13736071.55
      2390719.54     13735827.45        2390625.       13735125.

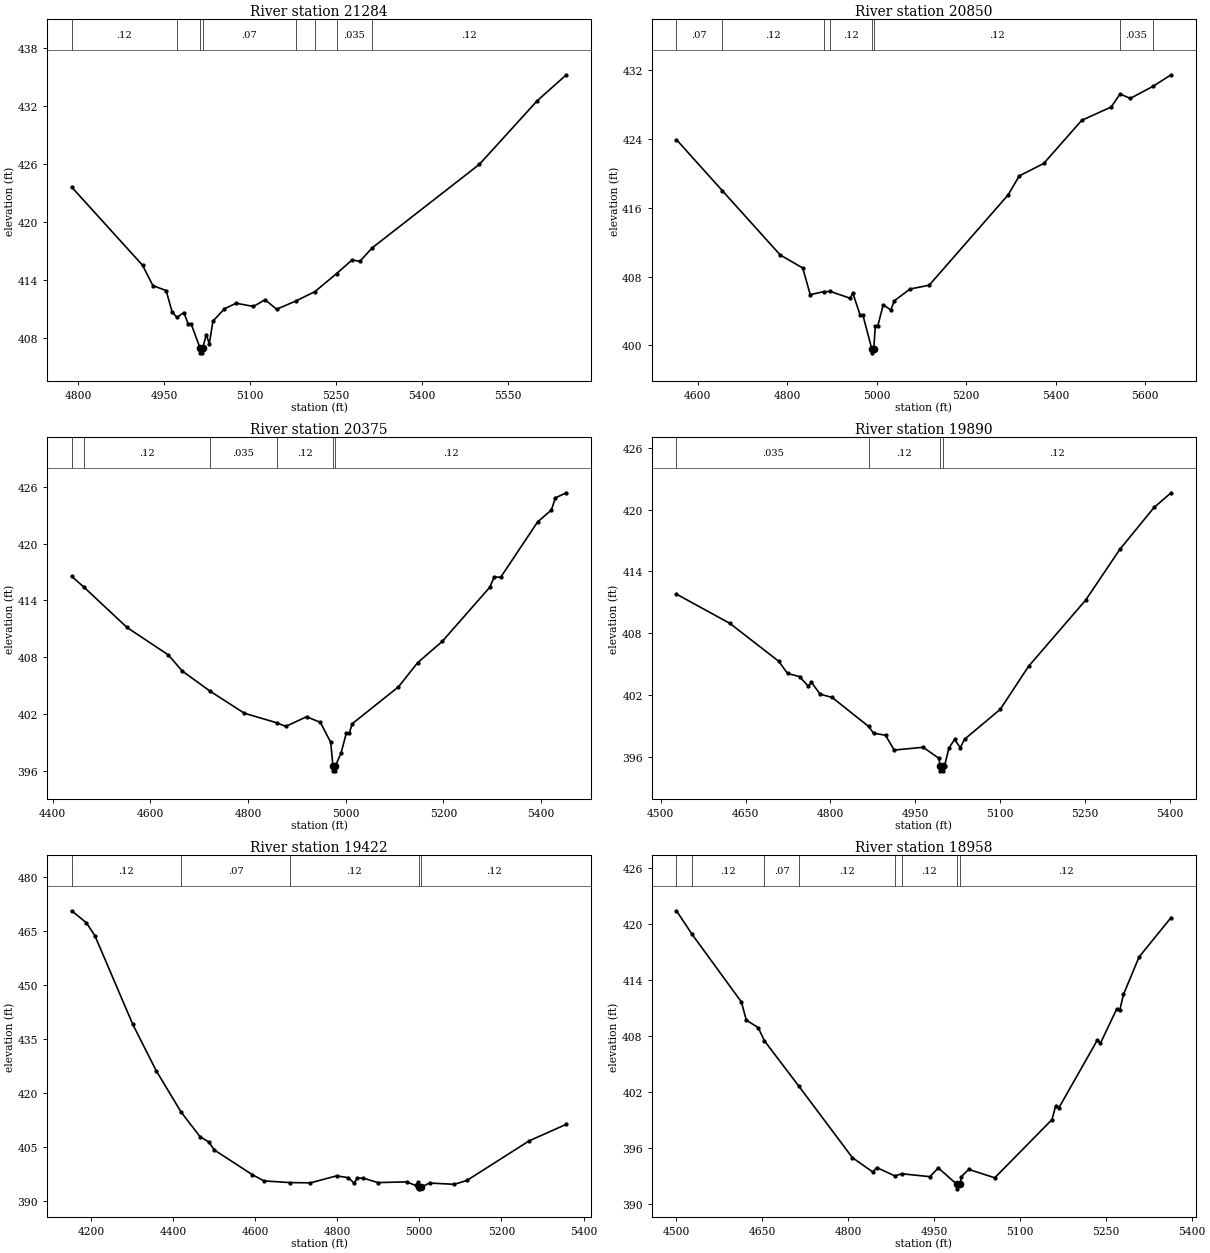
Type RM Length L Ch R = 1 ,21284   ,434,434,434
BEGIN DESCRIPTION:
Stream0256 41.0
END DESCRIPTION:
XS GIS Cut Line= 3
      2386974.96     13751074.99        2386775.       13751025.
      2386124.97     13751125.01
#Sta/Elev= 30
  4788.9  423.61  4912.6  415.53  4930.6  413.43  4953.8  412.91  4964.1  410.73
  4972.6  410.13  4984.7  410.64  4992.4  409.45  4997.5  409.45    5013  406.97
  5013.3  406.47  5017.3  406.47  5017.6  406.97  5024.1  408.36  5029.2  407.38
  5035.5  409.75  5055.7  411.03    5076   411.6  5106.3  411.27  5126.5  411.96
  5146.8  410.98  5179.9  411.82  5213.6   412.8  5251.5  414.67  5278.3  416.07
  5292.2  415.94  5313.7  417.33  5500.9  425.97  5602.1  432.56  5652.7  435.23
#Mann= 8 ,-1 , 0
  4788.9     .12       0  4972.6     .07       0    5013     .05       0
  5017.6     .07       0  5179.9     .12       0  5213.6     .07       0
  5251.5    .035       0  5313.7     .12       0
Bank Sta=5013,5017.6
XS Rating Curve= 0 ,0
Exp/Cntr=0.3,0.1

Type RM Length L Ch R = 1 ,20850   ,475,475,475
BEGIN DESCRIPTION:
Stream0256 40.0
END DESCRIPTION:
XS GIS Cut Line= 3
      2387074.96     13750824.98        2386675.       13750625.
       2386059.8     13750859.94
#Sta/Elev= 30
  4552.4  423.94  4654.9     418  4784.3  410.52  4834.7     409  4851.4   405.9
  4881.6  406.25  4896.6  406.27  4940.9  405.48  4946.5   406.1  4963.2  403.49
  4968.8  403.58  4988.8  399.63  4989.2  399.13  4993.5  399.63  4996.8  402.22
  5002.2  402.22  5014.6  404.73  5031.7  404.11  5039.3  405.19  5074.7  406.56
  5117.3     407  5293.9  417.52  5318.6  419.72  5373.4  421.17  5458.3  426.19
  5524.1  427.74  5543.9  429.25  5566.9  428.74  5617.4  430.14  5658.1  431.49
#Mann= 8 ,-1 , 0
  4552.4     .07       0  4654.9     .12       0  4881.6    .035       0
  4896.6     .12       0  4988.8     .05       0  4993.5     .12       0
  5543.9    .035       0  5617.4     .12       0
Bank Sta=4988.8,4993.5
XS Rating Curve= 0 ,0
Exp/Cntr=0.3,0.1

Type RM Length L Ch R = 1 ,20375   ,485,485,485
BEGIN DESCRIPTION:
Stream0256 39.0
END DESCRIPTION:
XS GIS Cut Line= 3
      2387075.03     13750575.03        2386675.       13750175.
      2386275.04     13749975.02
#Sta/Elev= 30
  4438.8  416.54  4463.8  415.41    4552  411.16  4636.8  408.26  4665.1  406.57
  4722.8  404.42  4792.4  402.12  4858.2  401.12  4877.2  400.73  4919.7  401.75
    4948  401.16  4969.2  399.05  4973.7  396.55  4974.1  396.05  4978.4  396.05
  4978.7  396.55  4990.4  397.93    5001     400  5007.3     400  5012.9     401
  5107.9   404.9  5147.1  407.44  5197.4  409.68  5295.2  415.41  5303.6  416.45
  5317.6  416.47    5393  422.29    5421  423.53  5429.4  424.82  5451.7  425.35
#Mann= 6 ,-1 , 0
  4438.8     .07       0  4463.8     .12       0  4722.8    .035       0
  4858.2     .12       0  4973.7     .05       0  4978.7     .12       0
Bank Sta=4973.7,4978.7
XS Rating Curve= 0 ,0
Exp/Cntr=0.3,0.1

Type RM Length L Ch R = 1 ,19890   ,468,468,468
BEGIN DESCRIPTION:
Stream0256 38.0
END DESCRIPTION:
XS GIS Cut Line= 3
      2387175.01     13749975.01        2386775.       13749725.
      2386375.02       13749675.
#Sta/Elev= 30
  4527.9  411.78  4622.3  408.94  4708.9  405.25  4724.3  404.07  4745.5  403.77
  4760.8  402.85  4766.7   403.2    4782  402.06  4803.3  401.74  4867.8  398.92
  4876.4  398.27  4897.6  398.07  4912.9  396.63  4964.2   396.9  4991.9  395.83
  4994.1  395.11  4994.5  394.61  4998.8  394.61  4999.2  395.11  5002.1  395.11
  5009.7  396.82  5019.8  397.66  5029.8  396.86  5037.4  397.68  5100.4  400.58
  5150.8  404.78  5251.6   411.2    5312  416.13  5372.5   420.2  5402.7  421.63
#Mann= 4 ,-1 , 0
  4527.9    .035       0  4867.8     .12       0  4994.1     .05       0
  4999.2     .12       0
Bank Sta=4994.1,4999.2
XS Rating Curve= 0 ,0
Exp/Cntr=0.3,0.1

Type RM Length L Ch R = 1 ,19422   ,464,464,464
BEGIN DESCRIPTION:
Stream0256 37.0
END DESCRIPTION:
XS GIS Cut Line= 3
      2387525.01     13748774.99        2386875.       13749325.
      2386525.03       13749375.
#Sta/Elev= 30
  4153.1  470.56  4188.8  467.23  4209.7  463.61    4302  438.96  4359.1  426.08
  4419.5  414.63  4465.7  407.78  4486.6  406.33  4500.8  404.06  4593.1  397.21
  4621.7  395.48  4684.7  395.02  4734.8  394.95  4798.6  396.89  4827.1  396.37
  4841.4  394.85    4848  396.21  4862.3   396.3  4898.6  395.02  4968.9  395.21
  4990.9  394.23  4997.4  395.11    4998  393.78  4998.5  393.28  5004.7  393.78
  5024.8  394.89  5085.4  394.54  5115.7   395.6  5267.2  406.59  5358.1  411.23
#Mann= 5 ,-1 , 0
  4153.1     .12       0  4419.5     .07       0  4684.7     .12       0
    4998     .05       0  5004.7     .12       0
Bank Sta=4998,5004.7
XS Rating Curve= 0 ,0
Exp/Cntr=0.3,0.1

Type RM Length L Ch R = 1 ,18958   ,433,433,433
BEGIN DESCRIPTION:
Stream0256 36.0
END DESCRIPTION:
XS GIS Cut Line= 3
      2387224.99       13748575.        2386825.       13748875.
        2386475.       13748775.
#Sta/Elev= 30
    4500  421.38  4527.1  418.88  4613.5  411.63  4621.9   409.7  4642.7   408.9
  4653.7  407.48  4713.5  402.66  4807.3     395  4842.7  393.48    4850  393.94
  4881.6  393.05  4893.5  393.28  4942.7  392.97  4957.3  393.91  4989.3  392.17
  4989.8  391.67  4996.1  392.17  4996.9  392.92  5010.4  393.75  5055.9  392.85
    5156  399.07  5162.5  400.57  5167.7   400.3  5235.3  407.58  5240.5  407.22
  5269.1   410.9  5274.3  410.76  5280.8  412.44  5308.1  416.45    5364  420.66
#Mann= 8 ,-1 , 0
    4500     .07       0  4527.1     .12       0  4653.7     .07       0
  4713.5     .12       0  4881.6    .035       0  4893.5     .12       0
  4989.3     .05       0  4996.1     .12       0
Bank Sta=4989.3,4996.1
XS Rating Curve= 0 ,0
Exp/Cntr=0.3,0.1

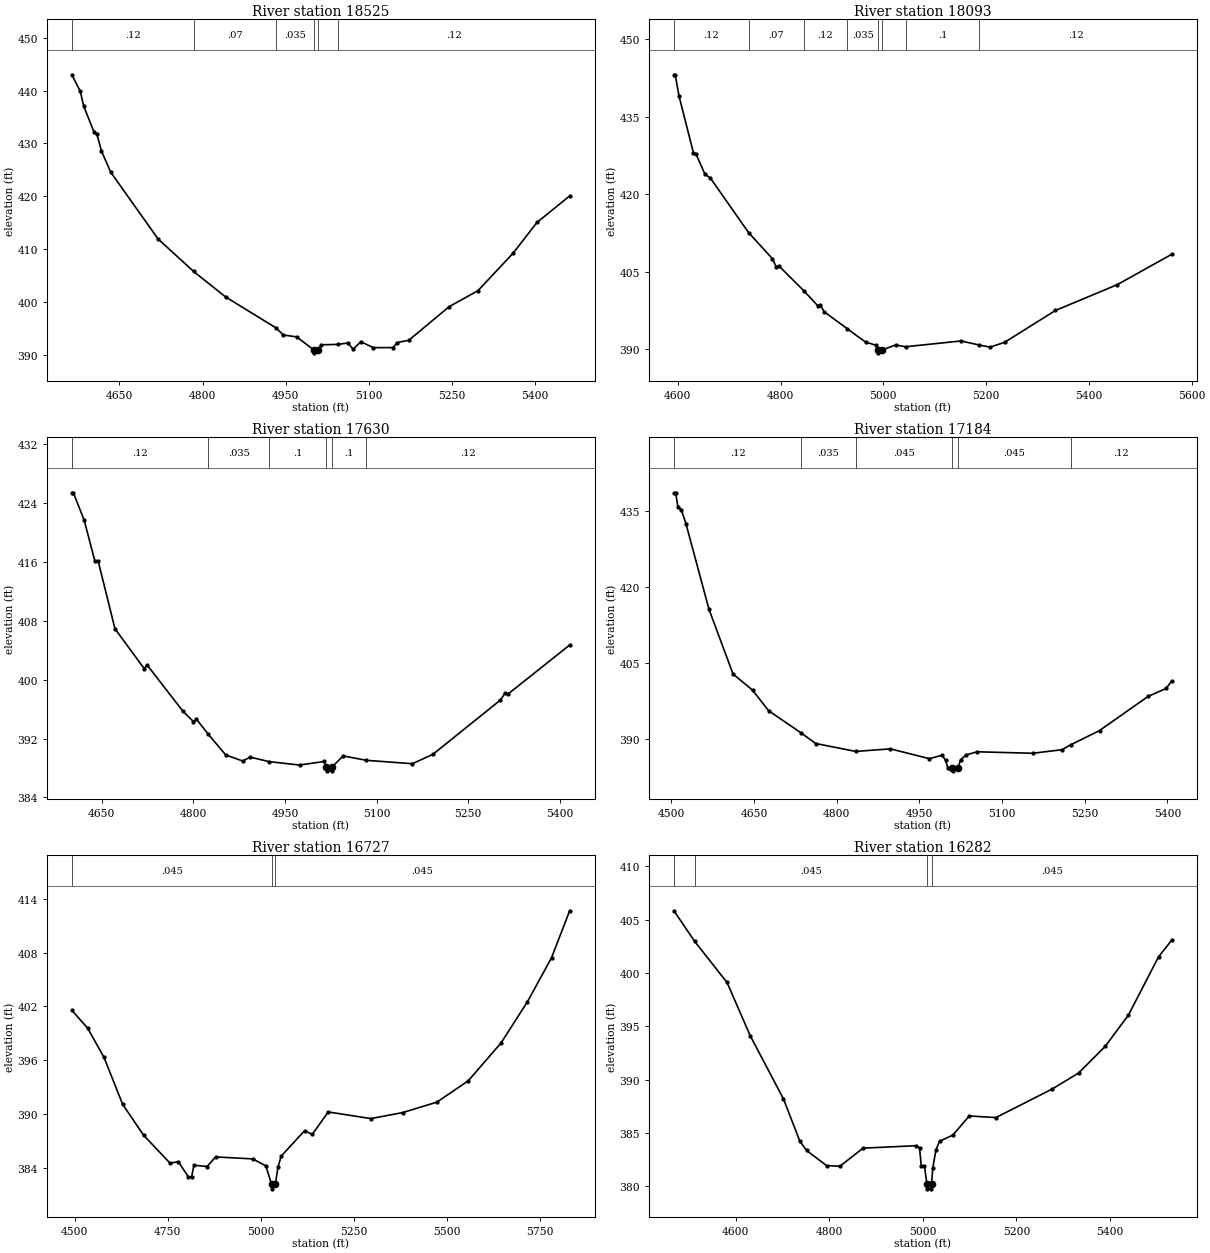
Type RM Length L Ch R = 1 ,18525   ,432,432,432
BEGIN DESCRIPTION:
Stream0256 35.0
END DESCRIPTION:
XS GIS Cut Line= 3
      2387275.04     13748324.99        2386875.       13748475.
      2386475.03     13748724.98
#Sta/Elev= 30
    4564  442.98  4579.2  439.84  4585.4  437.04  4604.1  432.12  4609.4  431.67
  4617.4  428.55  4634.4  424.49  4719.8  411.87  4783.9  405.73  4841.7   400.9
  4932.7  395.04  4945.9  393.69  4969.9  393.35  5001.4  390.82  5001.9  390.32
  5008.2  390.82  5014.2  391.84  5044.4  391.92  5062.6  392.18    5072  390.98
  5085.6  392.43  5108.6   391.3  5144.5  391.32    5151  392.27  5172.3  392.69
  5245.4  399.07  5297.3  402.09  5360.9  409.21    5404  415.03  5462.9  420.03
#Mann= 6 ,-1 , 0
    4564     .12       0  4783.9     .07       0  4932.7    .035       0
  5001.4    .035       0  5008.2    .035       0  5044.4     .12       0
Bank Sta=5001.4,5008.2
XS Rating Curve= 0 ,0
Exp/Cntr=0.3,0.1

Type RM Length L Ch R = 1 ,18093   ,463,463,463
BEGIN DESCRIPTION:
Stream0256 34.0
END DESCRIPTION:
XS GIS Cut Line= 3
      2387275.02       13748125.        2386875.       13748075.
      2386475.01     13748474.99
#Sta/Elev= 30
  4592.4  443.15  4594.9  443.15  4602.5  438.95  4630.2  428.08  4635.2  427.82
  4652.9  423.84    4663  423.18  4737.7  412.56  4783.9  407.51  4791.5  405.92
  4796.5  406.12  4844.7  401.33  4872.1  398.41  4877.1  398.56  4884.7  397.22
  4929.4  393.95  4965.3  391.33  4985.5  390.73  4989.6  389.75  4990.1  389.25
  4996.4  389.75  5023.8  390.78  5043.1  390.43  5151.1  391.55  5186.5  390.77
  5207.7  390.35  5235.9  391.29  5334.9  397.46  5455.1  402.46  5561.2  408.35
#Mann= 8 ,-1 , 0
  4592.4     .12       0  4737.7     .07       0  4844.7     .12       0
  4929.4    .035       0  4989.6    .035       0  4996.4    .035       0
  5043.1      .1       0  5186.5     .12       0
Bank Sta=4989.6,4996.4
XS Rating Curve= 0 ,0
Exp/Cntr=0.3,0.1

Type RM Length L Ch R = 1 ,17630   ,446,446,446
BEGIN DESCRIPTION:
Stream0256 33.0
END DESCRIPTION:
XS GIS Cut Line= 3
      2387175.02       13747625.        2386775.       13747675.
      2386375.04     13747575.01
#Sta/Elev= 30
  4600.9  425.42  4603.4  425.42  4621.1  421.68  4638.7   416.1  4643.8  416.19
  4671.5  406.93  4719.3  401.53  4724.4  401.98  4782.3  395.78    4800  394.31
    4805  394.63  4824.6  392.57  4852.9  389.78  4880.6  388.96  4893.2  389.48
  4924.2  388.87  4973.8  388.41  5014.3  388.89  5017.5  388.12    5018  387.62
  5026.2  387.62  5026.7  388.12  5045.3  389.65  5083.3  389.05  5158.7  388.59
  5192.2  389.86    5303  397.25  5310.7  398.22  5315.8  398.09  5416.3  404.72
#Mann= 6 ,-1 , 0
  4600.9     .12       0  4824.6    .035       0  4924.2      .1       0
  5017.5     .05       0  5026.7      .1       0  5083.3     .12       0
Bank Sta=5017.5,5026.7
XS Rating Curve= 0 ,0
Exp/Cntr=0.3,0.1

Type RM Length L Ch R = 1 ,17184   ,457,457,457
BEGIN DESCRIPTION:
Stream0256 32.0
END DESCRIPTION:
XS GIS Cut Line= 3
      2387224.97     13747574.97        2386825.       13747275.
      2386424.97       13747325.
#Sta/Elev= 30
  4504.8  438.56  4507.9  438.56    4512  435.75  4518.3  435.24  4526.6  432.48
  4568.3  415.64    4612  402.88  4647.5  399.69  4676.6  395.64  4735.3   391.3
    4762  389.19  4834.7  387.63  4897.5  388.14  4968.3   386.2  4991.2  386.89
  4997.5  385.91  5001.6  384.44  5009.8  384.31  5010.3  383.81  5019.8  384.31
  5024.9  385.97    5035  386.95  5055.1  387.56  5155.9  387.27  5208.8  387.97
  5224.5  388.93  5276.9  391.74    5365  398.46  5397.8  400.04  5407.9  401.52
#Mann= 6 ,-1 , 0
  4504.8     .12       0  4735.3    .035       0  4834.7    .045       0
  5009.8    .045       0  5019.8    .045       0  5224.5     .12       0
Bank Sta=5009.8,5019.8
XS Rating Curve= 0 ,0
Exp/Cntr=0.3,0.1

Type RM Length L Ch R = 1 ,16727   ,445,445,445
BEGIN DESCRIPTION:
Stream0256 31.0
END DESCRIPTION:
XS GIS Cut Line= 3
      2387374.98     13747174.99        2386975.       13746875.
      2386725.01     13746075.03
#Sta/Elev= 30
  4492.8  401.57  4535.5  399.57  4579.2  396.31  4629.2  391.09  4685.5  387.64
  4756.3  384.53  4779.2  384.66  4806.3  382.97  4814.7  382.99  4820.9  384.29
  4856.3  384.14  4879.2  385.21  4979.2  384.99  5014.3  384.21  5029.7  382.15
  5030.2  381.65  5039.7  382.15  5046.7  384.05  5055.6  385.31  5118.5  388.14
  5138.9  387.72  5181.9  390.23  5296.6  389.49    5382  390.16  5474.2  391.33
  5558.5  393.71  5647.1  397.97  5717.3  402.52  5782.2  407.44  5830.9  412.68
#Mann= 3 ,-1 , 0
  4492.8    .045       0  5029.7    .045       0  5039.7    .045       0
Bank Sta=5029.7,5039.7
XS Rating Curve= 0 ,0
Exp/Cntr=0.3,0.1

Type RM Length L Ch R = 1 ,16282   ,425,425,425
BEGIN DESCRIPTION:
Stream0256 30.0
END DESCRIPTION:
XS GIS Cut Line= 3
      2387574.98     13746924.97        2387225.       13746525.
      2386874.99     13746124.99
#Sta/Elev= 30
  4468.5  405.84  4512.7  402.97  4581.9  399.11  4631.2  394.13  4702.4  388.18
  4737.5   384.2  4751.8  383.34  4794.5  381.92    4823  381.86  4872.3  383.56
  4986.2  383.79  4992.9  383.58  4996.7  381.91  5003.3  381.91  5008.7  380.24
  5009.2  379.74  5018.2  379.74  5018.7  380.24  5021.3  381.72    5028  383.39
  5035.6  384.21    5064  384.78  5099.2  386.58  5156.1  386.43  5276.6  389.12
  5332.6  390.61  5389.6  393.12  5438.9  396.04  5503.5  401.53  5531.5  403.08
#Mann= 4 ,-1 , 0
  4468.5    .035       0  4512.7    .045       0  5008.7    .045       0
  5018.7    .045       0
Bank Sta=5008.7,5018.7
XS Rating Curve= 0 ,0
Exp/Cntr=0.3,0.1

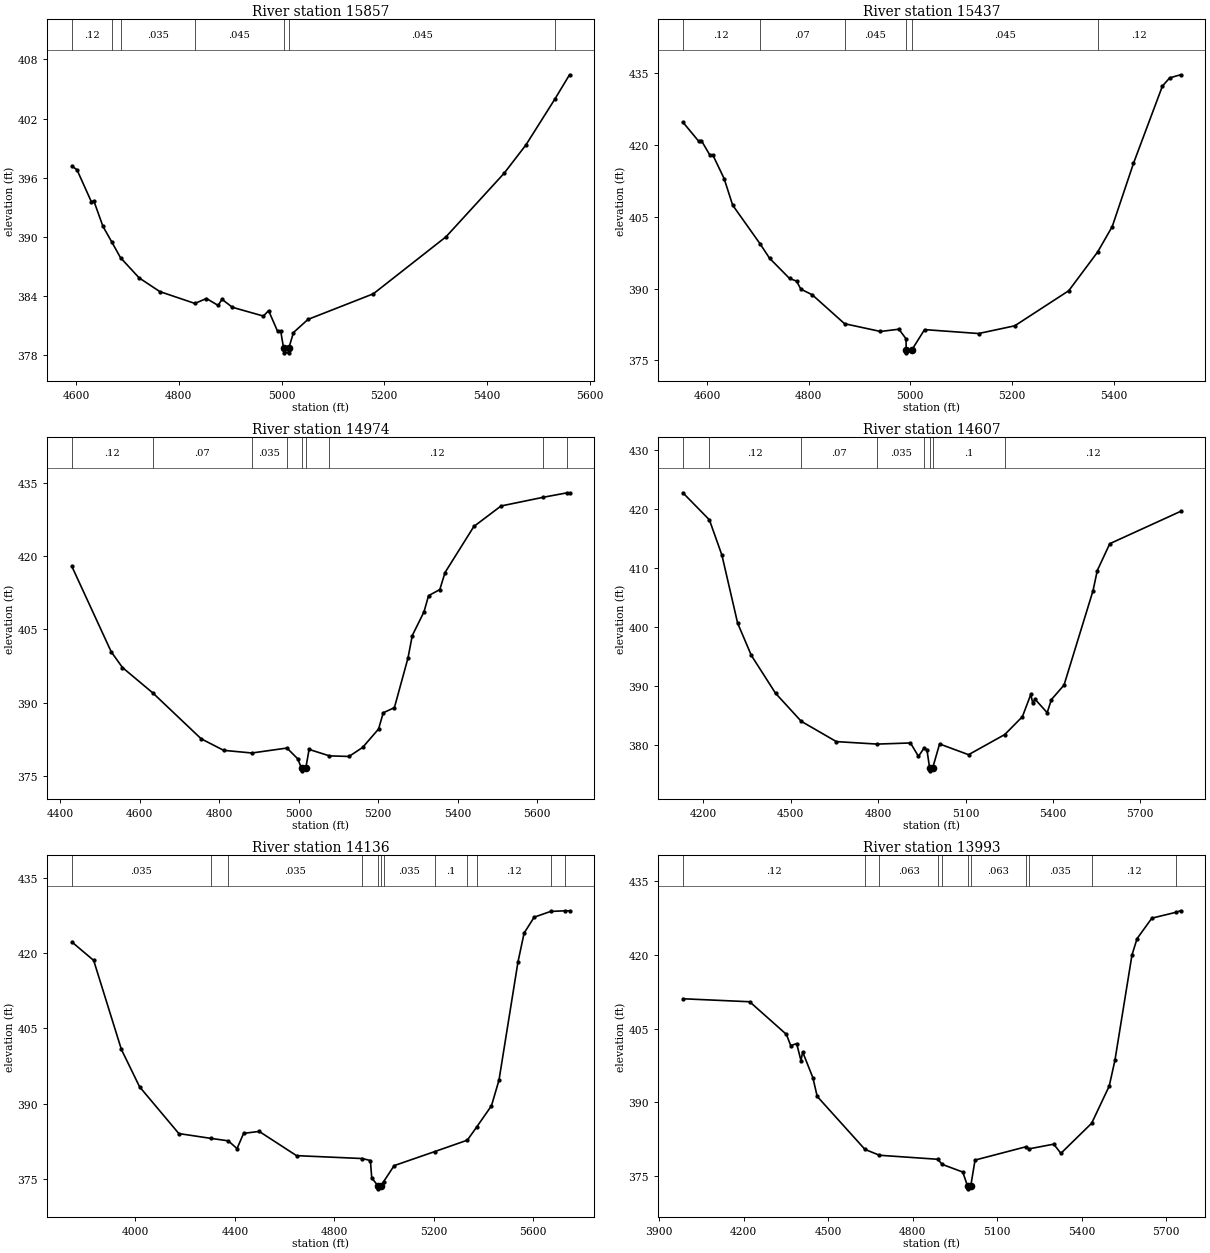
Type RM Length L Ch R = 1 ,15857   ,420,420,420
BEGIN DESCRIPTION:
Stream0256 29.0
END DESCRIPTION:
XS GIS Cut Line= 3
        2387875.       13746275.        2387475.       13746225.
        2387075.       13745825.
#Sta/Elev= 30
  4591.8  397.19  4601.9  396.79  4629.6  393.58  4634.6  393.64  4652.3  391.07
  4669.2  389.51  4686.5  387.89  4722.8  385.84  4763.1  384.45  4831.3  383.25
  4853.8  383.75  4876.5  383.05  4884.1  383.67  4904.2  382.86  4964.7  381.97
  4974.8  382.52  4992.4  380.41  4998.5  380.41  5003.9  378.74  5004.4  378.24
  5013.8  378.24  5014.3  378.74  5023.2   380.3  5051.5  381.63  5178.8  384.23
  5320.2  390.01  5433.3  396.45  5475.8  399.33  5532.5  404.01  5560.6  406.44
#Mann= 7 ,-1 , 0
  4591.8     .12       0  4669.2     .07       0  4686.5    .035       0
  4831.3    .045       0  5003.9    .045       0  5014.3    .045       0
  5532.5     .12       0
Bank Sta=5003.9,5014.3
XS Rating Curve= 0 ,0
Exp/Cntr=0.3,0.1

Type RM Length L Ch R = 1 ,15437   ,463,463,463
BEGIN DESCRIPTION:
Stream0256 28.0
END DESCRIPTION:
XS GIS Cut Line= 3
      2388075.04     13746075.02        2387675.       13745875.
      2387274.97     13745524.97
#Sta/Elev= 30
  4552.8  424.72  4583.6  420.78  4589.2  420.87  4605.9  417.85  4611.5  417.91
  4633.9  412.95  4650.7   407.4  4704.3  399.38  4723.3  396.32  4762.5  392.11
  4776.4  391.55  4784.8  389.87  4807.2   388.7  4870.8  382.66  4941.4  381.04
  4977.7  381.51  4991.7  379.51    4992  377.08  4992.5  376.58  5002.5  377.08
  5028.1  381.43  5134.4  380.61  5205.5  382.22  5311.8  389.55  5368.6  397.63
  5397.3  402.94    5439  416.11    5496  432.26  5510.2  433.96  5531.6  434.61
#Mann= 6 ,-1 , 0
  4552.8     .12       0  4704.3     .07       0  4870.8    .045       0
    4992    .045       0  5002.5    .045       0  5368.6     .12       0
Bank Sta=4992,5002.5
XS Rating Curve= 0 ,0
Exp/Cntr=0.3,0.1

Type RM Length L Ch R = 1 ,14974   ,367,367,367
BEGIN DESCRIPTION:
Stream0256 27.0
END DESCRIPTION:
XS GIS Cut Line= 3
      2388275.03     13745875.03        2387875.       13745475.
      2387212.85     13745295.02
#Sta/Elev= 30
  4429.7  417.86  4528.7   400.4    4557  397.18  4633.6  391.97    4755  382.61
  4811.6  380.25  4882.6  379.71  4970.8  380.72    4998  378.51  5007.5  376.56
    5008  376.06    5018  376.56  5026.5  380.44  5077.7  379.12  5126.9     379
  5161.2  380.85  5201.3  384.62    5213  387.93  5241.1  388.98  5275.2  399.11
  5286.1  403.73  5315.5  408.56    5327  411.87  5355.3  413.12  5368.5  416.61
    5441  426.02  5509.3  430.21  5616.1     432    5676  432.91  5681.6  432.85
#Mann= 9 ,-1 , 0
  4429.7     .12       0  4633.6     .07       0  4882.6    .035       0
  4970.8      .1       0  5007.5     .05       0    5018      .1       0
  5077.7     .12       0  5616.1     .07       0    5676     .12       0
Bank Sta=5007.5,5018
XS Rating Curve= 0 ,0
Exp/Cntr=0.3,0.1

Type RM Length L Ch R = 1 ,14607   ,471,471,471
BEGIN DESCRIPTION:
XS6270
END DESCRIPTION:
XS GIS Cut Line= 3
      2388337.79     13745919.19      2388041.99     13745190.01
       2387312.8     13744625.92
#Sta/Elev= 30
  4129.5  422.76  4220.5  418.17  4263.5  412.18  4317.5  400.64  4364.5  395.17
  4447.6  388.75  4535.8  383.99  4656.5  380.54  4796.4  380.12    4911  380.31
  4938.5  378.03  4957.1  379.41  4967.5  379.17  4976.7  376.08  4977.2  375.58
  4987.3  376.08  5010.9  380.14  5110.5  378.32  5234.8  381.74  5295.3  384.77
  5324.2  388.55  5330.6  387.12  5338.7  387.73  5380.4  385.45  5394.9  387.67
  5438.3  390.14  5537.9  406.16  5552.4  409.56  5595.3  414.12  5838.3   419.6
#Mann= 8 ,-1 , 0
  4129.5    .035       0  4220.5     .12       0  4535.8     .07       0
  4796.4    .035       0  4957.1      .1       0  4976.7     .05       0
  4987.3      .1       0  5234.8     .12       0
Bank Sta=4976.7,4987.3
XS Rating Curve= 0 ,0
Exp/Cntr=0.3,0.1

Type RM Length L Ch R = 1 ,14136   ,143,143,143
BEGIN DESCRIPTION:
XS6269
END DESCRIPTION:
XS GIS Cut Line= 4
       2388365.3     13745905.41      2388035.11      13744832.3
      2387897.53     13744412.68      2387464.19     13744350.77
#Sta/Elev= 30
  3744.2  422.21  3831.9  418.54  3943.4  400.79  4016.7  393.33  4174.6  384.01
  4303.7  383.05  4373.6  382.56  4408.7  381.01  4435.2  384.05  4497.9  384.44
    4648  379.61  4913.2  379.03  4945.3  378.63  4950.6  375.18  4977.1  373.49
  4977.6  372.99  4987.8  373.49    4998  374.39  5040.8  377.62  5203.6  380.41
  5335.1  382.69  5372.5  385.29  5432.3  389.55  5462.6  394.67    5539  418.24
  5563.7  423.99  5604.1  427.15  5670.3   428.3  5730.1  428.43  5746.3  428.42
#Mann= 12 ,-1 , 0
  3744.2    .035       0  4303.7     .07       0  4373.6    .035       0
  4913.2      .1       0  4977.1    .035       0  4987.8      .1       0
    4998    .035       0  5203.6      .1       0  5335.1    .035       0
  5372.5     .12       0  5670.3     .07       0  5730.1     .12       0
Bank Sta=4977.1,4987.8
XS Rating Curve= 0 ,0
Exp/Cntr=0.3,0.1

Type RM Length L Ch R = 1 ,13993   ,351,351,351
BEGIN DESCRIPTION:
XS6268
END DESCRIPTION:
XS GIS Cut Line= 5
      2388771.18     13745286.32      2388186.45     13744914.85
      2388055.75     13744474.59      2388021.36     13744378.28
      2387514.23     13744309.75
#Sta/Elev= 30
  3984.4  411.06  4221.4  410.45  4351.8   403.8    4367  401.52  4388.2  401.92
  4403.5  398.46  4409.4  400.23  4445.8  394.96    4461  391.17  4630.4  380.38
  4681.9  379.18  4889.1  378.36  4904.3  377.33  4977.6  375.76    4995  372.84
  4995.5  372.34  5005.7  372.84  5021.2   378.2  5201.1   380.9  5213.1  380.49
  5300.5  381.44  5325.8  379.57    5435   385.7  5497.3  393.27  5517.5  398.49
  5578.1  419.98  5596.2  423.31  5648.7  427.48  5734.2  428.67  5750.4  428.98
#Mann= 11 ,-1 , 0
  3984.4     .12       0  4630.4    .035       0  4681.9    .063       0
  4889.1      .1       0  4904.3    .063       0    4995    .063       0
  5005.7    .063       0  5201.1      .1       0  5213.1    .035       0
    5435     .12       0  5734.2     .07       0
Bank Sta=4995,5005.7
XS Rating Curve= 0 ,0
Exp/Cntr=0.3,0.1

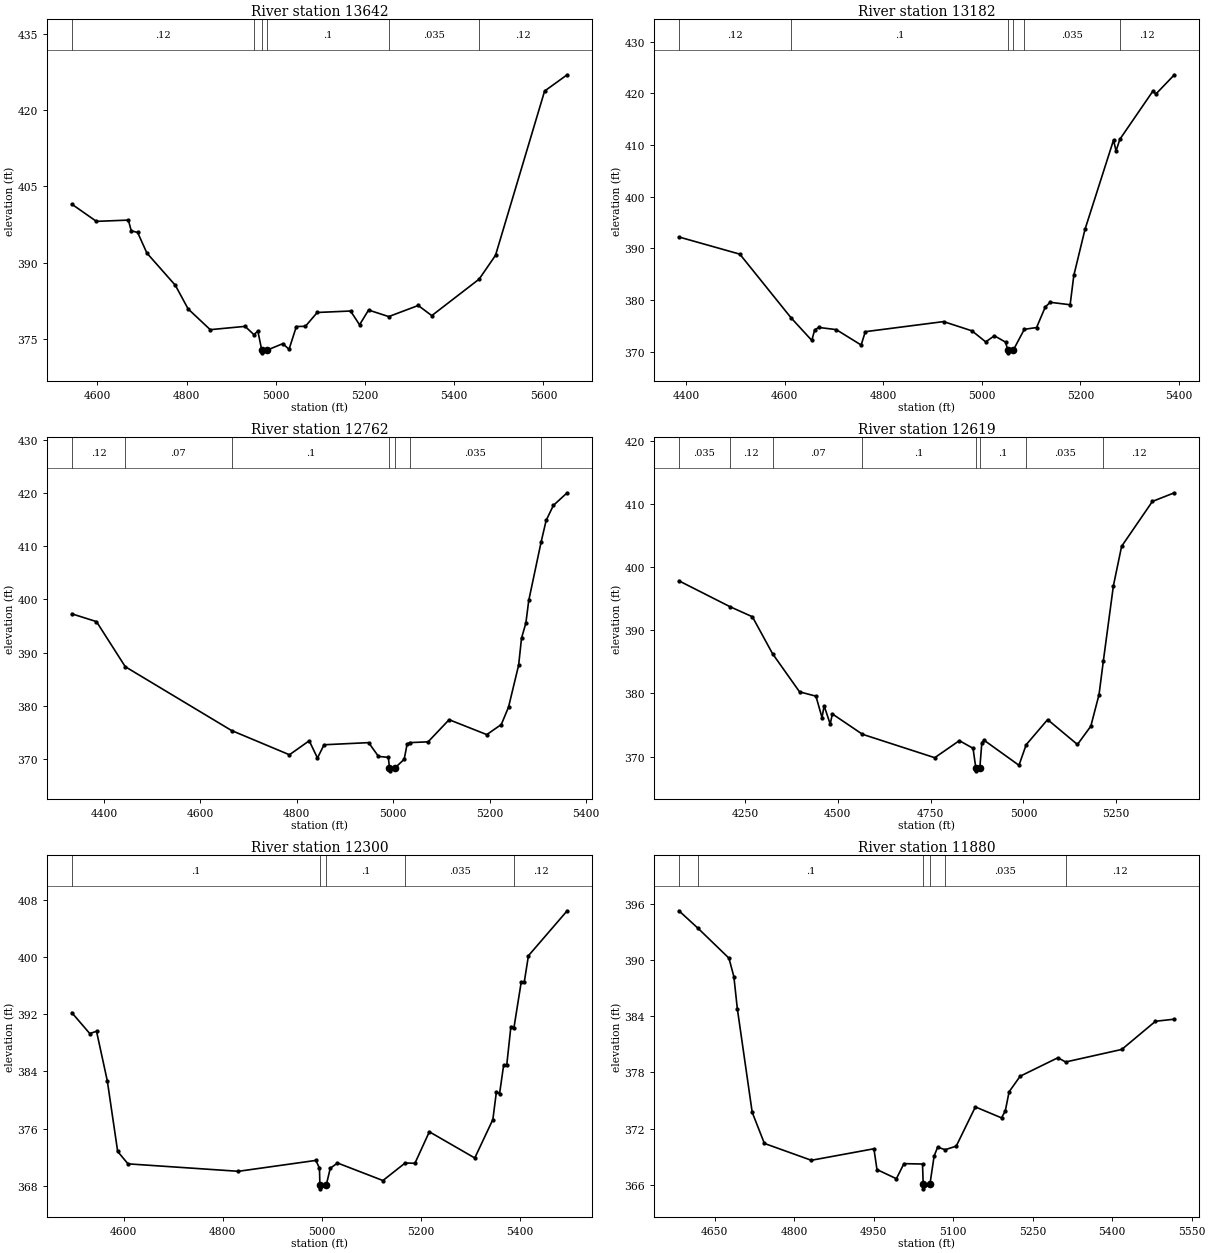
Type RM Length L Ch R = 1 ,13642   ,460,460,460
BEGIN DESCRIPTION:
Stream0256 24.0
END DESCRIPTION:
XS GIS Cut Line= 3
        2388623.     13744664.93        2388275.       13744375.
        2387625.       13744275.
#Sta/Elev= 30
  4542.6  401.52  4597.9  398.12  4669.5  398.37    4676  396.26  4690.3  395.93
  4711.1  391.86  4774.9   385.5  4803.5  380.85    4853  376.76  4931.1  377.41
    4951  375.78  4959.8  376.48  4968.6  372.69  4969.1  372.19  4979.5  372.69
  5015.8     374  5029.7  372.88  5046.1  377.38  5066.4  377.42  5092.9  380.15
  5167.6  380.44  5187.8  377.72    5208  380.63  5253.2  379.34  5319.3  381.53
  5349.7  379.53  5455.9  386.73  5492.6  391.43  5602.6  423.82  5653.2  427.03
#Mann= 6 ,-1 , 0
  4542.6     .12       0    4951      .1       0  4968.6     .05       0
  4979.5      .1       0  5253.2    .035       0  5455.9     .12       0
Bank Sta=4968.6,4979.5
XS Rating Curve= 0 ,0
Exp/Cntr=0.3,0.1

Type RM Length L Ch R = 1 ,13182   ,420,420,420
BEGIN DESCRIPTION:
Stream0256 23.0
END DESCRIPTION:
XS GIS Cut Line= 3
      2388585.47     13743704.82        2388075.       13744025.
      2387674.99       13744075.
#Sta/Elev= 30
  4385.2  392.22  4508.8   388.9  4612.9  376.58  4654.9  372.22  4660.8  374.27
  4669.1  374.73  4704.5  374.31  4755.1  371.33  4763.5  373.91  4922.4  375.86
  4980.1  374.07  5007.9  371.94  5025.6  373.12  5048.2  371.89  5052.8  370.32
  5053.3  369.82  5063.8  370.32  5086.3  374.37  5111.2  374.71  5128.9   378.7
  5138.9  379.59  5179.3  379.12  5186.8  384.79  5209.5   393.7  5267.4  410.95
  5272.5  408.86  5280.3  411.12  5348.1  420.53  5353.1  419.83  5390.9  423.58
#Mann= 6 ,-1 , 0
  4385.2     .12       0  4612.9      .1       0  5052.8     .05       0
  5063.8      .1       0  5086.3    .035       0  5280.3     .12       0
Bank Sta=5052.8,5063.8
XS Rating Curve= 0 ,0
Exp/Cntr=0.3,0.1

Type RM Length L Ch R = 1 ,12762   ,143,143,143
BEGIN DESCRIPTION:
Stream0256 22.0
END DESCRIPTION:
XS GIS Cut Line= 3
      2388575.03     13743524.99        2387925.       13743675.
      2387724.98     13743975.03
#Sta/Elev= 30
  4333.3  397.29  4384.6  395.82  4444.3  387.35  4664.7  375.36  4784.9   370.8
  4825.9  373.43    4843  370.19  4856.7  372.68  4949.1  373.08  4969.6  370.49
  4990.1  370.31  4992.3  368.28  4992.8  367.78  5003.3  368.28  5022.9  369.95
    5029  372.81  5034.1  373.08  5072.5  373.23  5116.1  377.39  5194.2  374.59
  5224.3  376.48  5239.3  379.74  5260.3  387.63  5266.3  392.71  5275.3  395.54
  5281.3  399.79    5307   410.8  5317.4  414.84  5332.4  417.66    5361  420.03
#Mann= 7 ,-1 , 0
  4333.3     .12       0  4444.3     .07       0  4664.7      .1       0
  4992.3     .05       0  5003.3      .1       0  5034.1    .035       0
    5307     .12       0
Bank Sta=4992.3,5003.3
XS Rating Curve= 0 ,0
Exp/Cntr=0.3,0.1

Type RM Length L Ch R = 1 ,12619   ,319,319,319
BEGIN DESCRIPTION:
E20848
END DESCRIPTION:
XS GIS Cut Line= 3
      2388697.98     13743119.74      2387977.92     13743494.77
      2387512.88     13743734.79
#Sta/Elev= 30
  4071.7  397.82  4208.8  393.74  4269.7  392.13  4323.9  386.29  4396.7  380.25
  4440.9  379.56  4457.3  376.16    4463  378.04  4479.4  375.13  4485.1  376.75
  4566.2  373.53  4761.1  369.82  4827.4  372.52  4864.3  371.31  4871.7  368.24
  4872.2  367.74  4882.7  368.24    4888   372.2  4893.7   372.6  4988.1  368.62
  5007.5  371.87  5065.3  375.85  5145.7  371.91  5181.7   374.8  5203.9  379.82
  5215.6  385.18  5242.6  397.04  5264.7  403.28  5347.7  410.39  5406.9  411.76
#Mann= 8 ,-1 , 0
  4071.7    .035       0  4208.8     .12       0  4323.9     .07       0
  4566.2      .1       0  4871.7     .05       0  4882.7      .1       0
  5007.5    .035       0  5215.6     .12       0
Bank Sta=4871.7,4882.7
XS Rating Curve= 0 ,0
Exp/Cntr=0.3,0.1

Type RM Length L Ch R = 1 ,12300   ,420,420,420
BEGIN DESCRIPTION:
Stream0256 21.0
END DESCRIPTION:
XS GIS Cut Line= 3
      2388274.97     13742925.04        2387975.       13743325.
      2387574.96     13743625.03
#Sta/Elev= 30
  4495.4  392.22  4531.8  389.29  4545.4  389.61  4567.2  382.67  4588.1  372.82
  4608.9  371.09  4831.8  370.05  4988.1  371.57  4995.4   370.5  4996.3   368.1
  4996.8   367.6    5009   368.1  5017.2  370.47  5031.8  371.21  5123.5  368.76
  5168.4  371.21  5188.1  371.17  5217.2  375.57  5308.9  371.91  5345.4  377.28
  5352.6  381.18  5358.9  380.87  5367.2   384.9  5373.5  384.93  5381.8  390.27
    5388  390.12  5402.6  396.46  5408.9  396.53  5417.2  400.16  5495.4  406.44
#Mann= 5 ,-1 , 0
  4495.4      .1       0  4996.3     .05       0    5009      .1       0
  5168.4    .035       0    5388     .12       0
Bank Sta=4996.3,5009
XS Rating Curve= 0 ,0
Exp/Cntr=0.3,0.1

Type RM Length L Ch R = 1 ,11880   ,464,464,464
BEGIN DESCRIPTION:
Stream0256 20.0
END DESCRIPTION:
XS GIS Cut Line= 3
      2388024.98     13742675.04        2387825.       13743025.
      2387424.98     13743375.02
#Sta/Elev= 30
  4582.8  395.27  4619.2  393.38  4677.1  390.21  4686.4  388.24  4692.9  384.83
    4721  373.74    4744  370.42  4832.5  368.62  4950.6  369.85  4956.4  367.63
    4993  366.65  5007.2  368.26  5042.3  368.22  5043.6  366.07  5044.1  365.57
  5056.3  366.07  5064.2  369.07  5070.8  370.02    5085  369.75  5105.9  370.13
    5142  374.32  5191.3  373.15  5198.5   373.9  5205.6  375.93  5226.5   377.6
  5297.6  379.57  5312.4  379.12  5418.2  380.46  5481.8  383.47  5517.4  383.69
#Mann= 6 ,-1 , 0
  4582.8     .12       0  4619.2      .1       0  5043.6     .05       0
  5056.3      .1       0    5085    .035       0  5312.4     .12       0
Bank Sta=5043.6,5056.3
XS Rating Curve= 0 ,0
Exp/Cntr=0.3,0.1

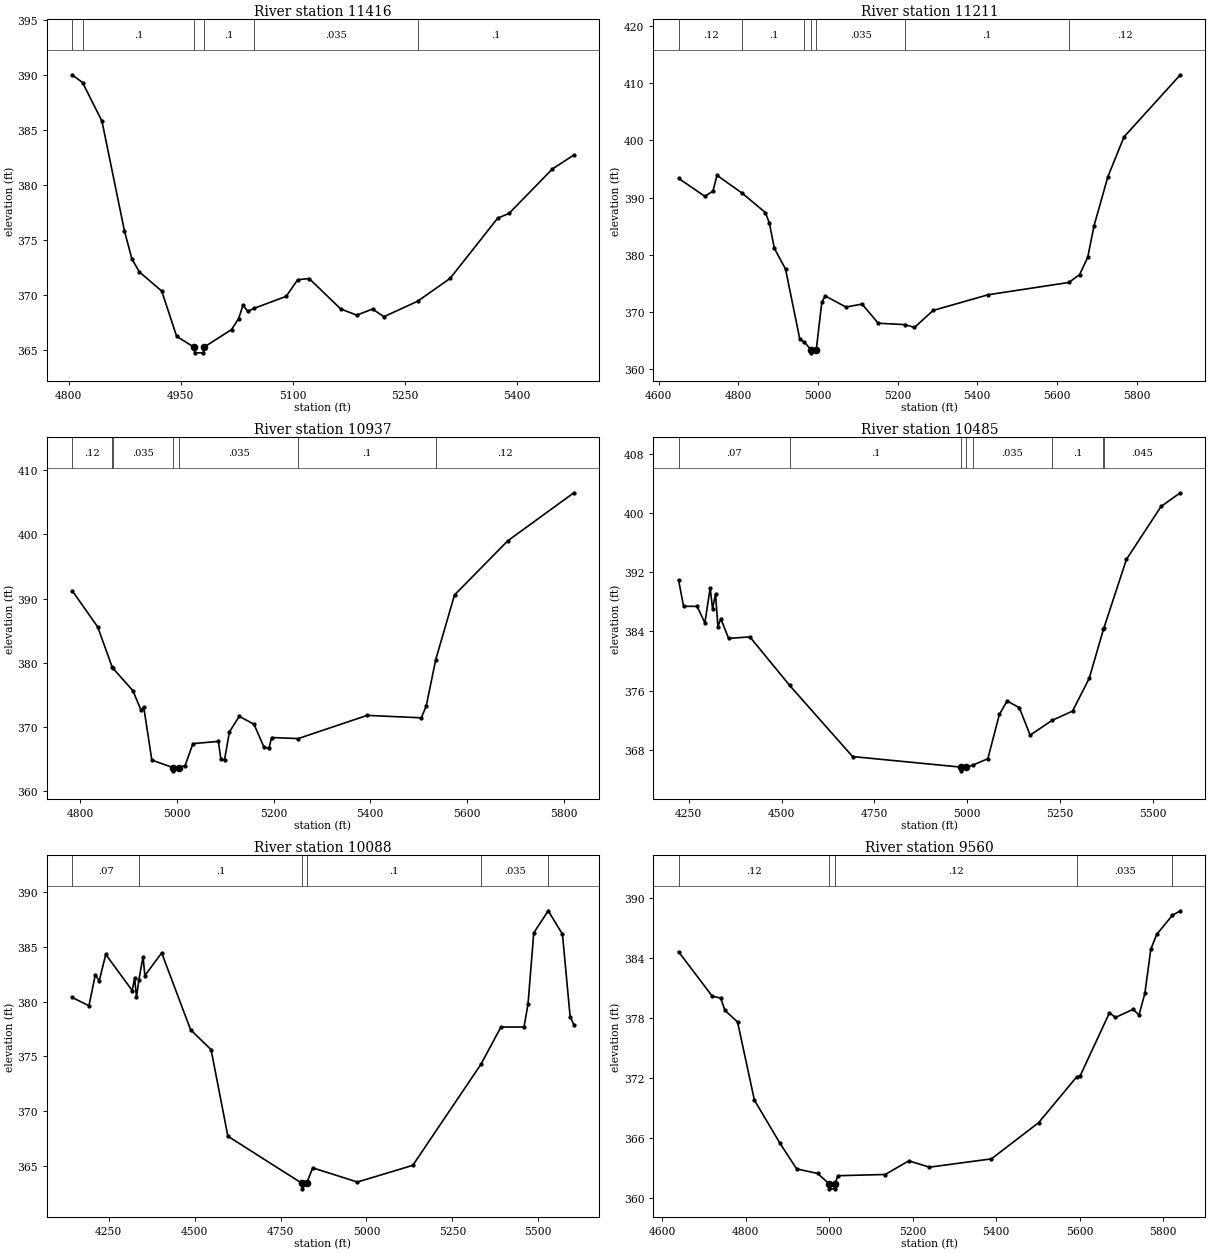
Type RM Length L Ch R = 1 ,11416   ,205,205,205
BEGIN DESCRIPTION:
Stream0256 19.0
END DESCRIPTION:
XS GIS Cut Line= 3
      2387874.96       13742625.        2387675.       13742625.
      2387274.96     13742875.02
#Sta/Elev= 30
  4804.4  390.02  4818.5  389.31  4844.4   385.8  4874.4  375.85  4884.4  373.28
  4894.4  372.09  4924.4  370.34  4944.4  366.22    4968  365.22  4968.5  364.72
  4980.2  364.72  4980.7  365.22  5017.9  366.84  5027.4  367.84  5033.2  369.06
  5039.7  368.49  5048.1  368.77    5091  369.86  5106.4  371.37  5121.7  371.48
  5164.1  368.71  5185.4  368.15  5206.6   368.7  5221.9  368.01  5267.1  369.42
  5310.4  371.49  5374.1  376.97  5389.4  377.41  5447.2  381.44  5476.1  382.72
#Mann= 6 ,-1 , 0
  4804.4     .12       0  4818.5      .1       0    4968     .05       0
  4980.7      .1       0  5048.1    .035       0  5267.1      .1       0
Bank Sta=4968,4980.7
XS Rating Curve= 0 ,0
Exp/Cntr=0.3,0.1

Type RM Length L Ch R = 1 ,11211   ,274,274,274
BEGIN DESCRIPTION:
E20847
END DESCRIPTION:
XS GIS Cut Line= 2
      2387970.46     13742384.61      2386725.21     13742572.15
#Sta/Elev= 30
  4650.2  393.37  4716.4  390.21  4736.6  391.14  4746.7   393.9  4810.5  390.74
  4868.1  387.38  4878.2  385.54  4890.6  381.13  4918.7   377.5  4954.5  365.25
    4966  364.71  4983.1  363.34  4983.6  362.84  4995.8  363.34  5009.7  371.68
  5018.4  372.79  5070.3  370.85  5110.8  371.37  5151.3  368.02  5218.2  367.78
  5242.3  367.28  5289.2  370.26  5427.2     373  5629.7  375.15  5656.9  376.53
  5677.1  379.56  5692.9  385.06  5727.7  393.65  5768.1  400.61  5909.5  411.48
#Mann= 7 ,-1 , 0
  4650.2     .12       0  4810.5      .1       0    4966    .035       0
  4983.1    .035       0  4995.8    .035       0  5218.2      .1       0
  5629.7     .12       0
Bank Sta=4983.1,4995.8
XS Rating Curve= 0 ,0
Exp/Cntr=0.3,0.1

Type RM Length L Ch R = 1 ,10937   ,452,452,452
BEGIN DESCRIPTION:
Stream0256 18.0
END DESCRIPTION:
XS GIS Cut Line= 3
      2387775.02     13742275.01        2387575.       13742175.
      2386774.97     13742024.99
#Sta/Elev= 30
  4783.3  391.25  4836.4  385.55  4866.3  379.26  4867.5  379.13  4909.1  375.61
  4925.9  372.55  4931.5  373.06  4948.2  364.77  4992.2  363.59  4992.7  363.09
  5004.9  363.59  5017.1  363.92  5033.2  367.34  5085.8  367.69  5090.9  364.98
  5098.5  364.78  5108.7  369.17    5129   371.6  5159.5  370.37  5179.9  366.82
  5190.1  366.58    5196  368.29    5251  368.13  5393.5  371.75  5505.5  371.37
  5515.6  373.21  5535.3  380.46  5574.1  390.55  5684.4  399.02  5820.9  406.51
#Mann= 7 ,-1 , 0
  4783.3     .12       0  4866.3      .1       0  4867.5    .035       0
  4992.2    .035       0  5004.9    .035       0    5251      .1       0
  5535.3     .12       0
Bank Sta=4992.2,5004.9
XS Rating Curve= 0 ,0
Exp/Cntr=0.3,0.1

Type RM Length L Ch R = 1 ,10485   ,397,397,397
BEGIN DESCRIPTION:
Stream0256 17.0
END DESCRIPTION:
XS GIS Cut Line= 3
      2388074.98     13742324.99        2387475.       13741825.
      2386924.99       13741675.
#Sta/Elev= 30
  4222.7  390.96  4236.3  387.39  4272.8  387.39  4293.6  385.15  4307.9  389.88
  4314.4  387.05  4322.3  389.06  4328.8  384.64  4336.6  385.73  4357.4  383.05
  4414.7  383.26    4522  376.69  4691.3  367.08  4983.4  365.65  4983.9  365.15
  4996.7  365.65  5015.5  365.93  5055.5  366.79  5086.6  372.78  5107.4  374.59
  5140.2  373.69  5169.5  369.97  5228.3  371.97  5283.6  373.22  5328.5  377.66
  5366.8  384.28  5367.8  384.42  5428.7  393.74    5522  400.89  5573.8  402.74
#Mann= 8 ,-1 , 0
  4222.7     .07       0    4522      .1       0  4983.4     .05       0
  4996.7      .1       0  5015.5    .035       0  5228.3      .1       0
  5366.8     .12       0  5367.8    .045       0
Bank Sta=4983.4,4996.7
XS Rating Curve= 0 ,0
Exp/Cntr=0.3,0.1

Type RM Length L Ch R = 1 ,10088   ,528,528,528
BEGIN DESCRIPTION:
E20846
END DESCRIPTION:
XS GIS Cut Line= 3
      2388517.95     13741837.03      2387580.36      13741469.5
      2387175.32     13741672.02
#Sta/Elev= 30
  4143.5  380.38  4192.6  379.61  4211.1  382.43  4222.4  381.87  4241.5  384.29
  4318.5     381  4325.5  382.14  4330.9  380.39    4338     382    4350  384.08
  4355.3  382.36  4404.2  384.43  4488.3  377.43  4547.9  375.62  4596.8  367.74
  4812.5  363.45    4813  362.95  4825.8  363.45  4843.6  364.86  4973.7  363.57
  5134.8  365.09  5332.7  374.27  5391.3  377.68  5458.4  377.68    5470  379.76
  5486.7  386.25  5528.8  388.26  5570.2  386.13  5592.6   378.6  5603.4  377.89
#Mann= 6 ,-1 , 0
  4143.5     .07       0    4338      .1       0  4812.5     .05       0
  4825.8      .1       0  5332.7    .035       0  5528.8      .1       0
Bank Sta=4812.5,4825.8
XS Rating Curve= 0 ,0
Exp/Cntr=0.3,0.1

Type RM Length L Ch R = 1 ,9560    ,438,438,438
BEGIN DESCRIPTION:
Stream0256 16.0
END DESCRIPTION:
XS GIS Cut Line= 3
      2388175.02       13741075.        2387825.       13741025.
        2387225.       13741625.
#Sta/Elev= 30
  4638.9  384.61  4719.7  380.17  4739.9  379.99    4750  378.76  4780.3   377.6
  4820.7   369.8  4881.4  365.54  4921.8  362.95  4972.3  362.49  4999.7  361.46
  5000.2  360.96  5013.1  360.96  5013.6  361.46  5020.8  362.27  5133.9  362.39
  5190.5  363.75    5240  363.12  5388.5  363.95  5501.6  367.56  5593.2  372.15
  5600.6  372.19  5671.3  378.52  5685.4  378.05  5727.9  378.86    5742  378.29
  5756.1  380.47  5770.3  384.86  5784.4  386.33  5821.8  388.23    5841  388.69
#Mann= 5 ,-1 , 0
  4638.9     .12       0  4999.7     .05       0  5013.6     .12       0
  5593.2    .035       0  5821.8      .1       0
Bank Sta=4999.7,5013.6
XS Rating Curve= 0 ,0
Exp/Cntr=0.3,0.1