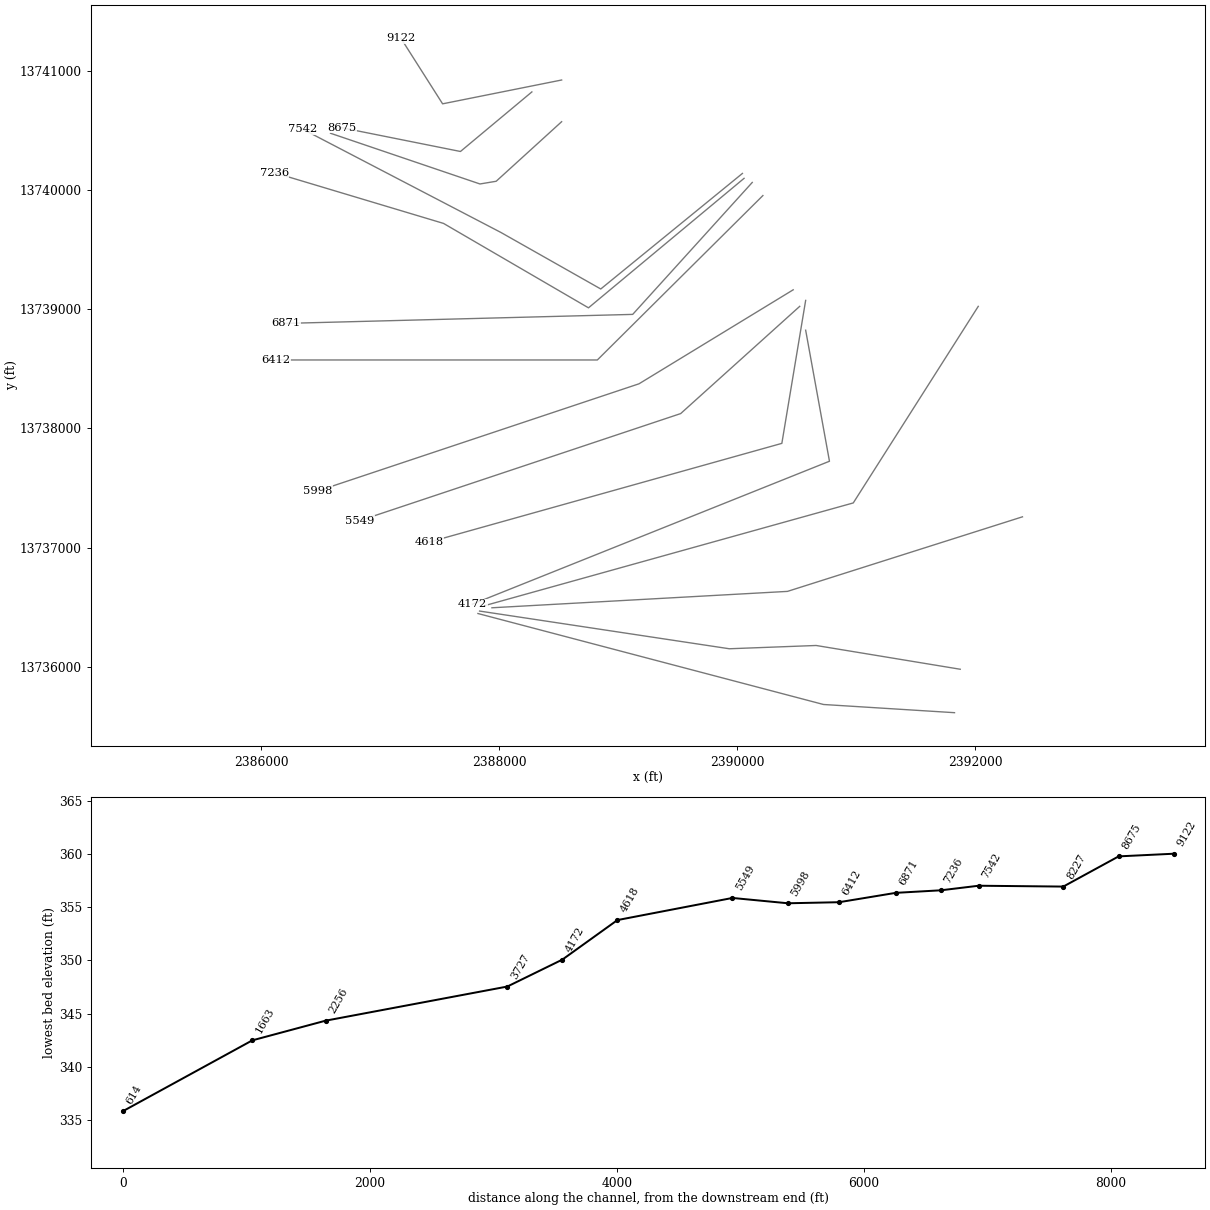
HEC-RAS study Stream0256.prj: Stream0256 Base Level Engineering

--- Stream0256.g01 (geometry) --- (continued)

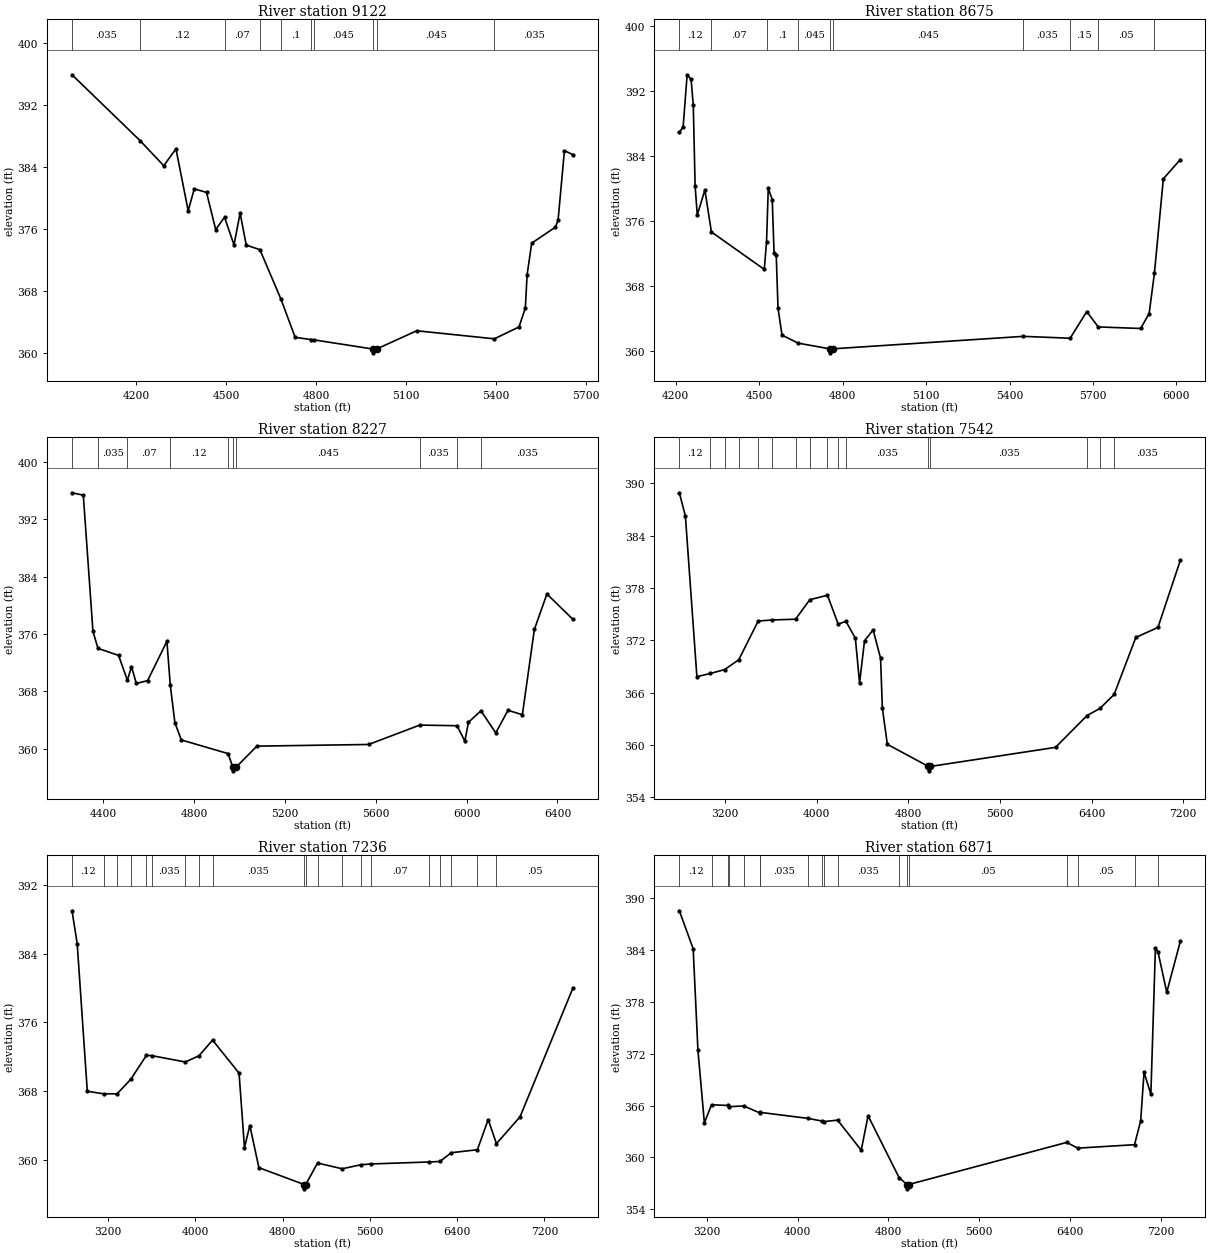
Type RM Length L Ch R = 1 ,9122    ,447,447,447
BEGIN DESCRIPTION:
Stream0256 15.0
END DESCRIPTION:
XS GIS Cut Line= 3
      2388525.05     13740925.01        2387525.       13740725.
      2387174.99     13741275.02
#Sta/Elev= 30
  3984.9  395.94  4211.9  387.44  4290.9   384.2  4331.7  386.37  4372.5  378.39
  4392.9  381.21  4433.7  380.75  4464.3  375.95  4493.7  377.55  4525.4  373.98
  4545.8  378.08  4566.2  373.95  4611.8  373.36  4682.3  366.95  4729.4  362.04
  4782.1  361.76  4792.9  361.71  4987.6  360.54  4988.1  360.04  5001.5  360.54
  5135.1  362.89  5394.1  361.85  5476.3  363.38  5497.5  365.82  5503.4  370.11
  5518.7   374.2  5597.4  376.25  5606.7  377.14  5627.9  386.15  5656.7  385.62
#Mann= 10 ,-1 , 0
  3984.9    .035       0  4211.9     .12       0  4493.7     .07       0
  4611.8     .12       0  4682.3      .1       0  4782.1     .12       0
  4792.9    .045       0  4987.6    .045       0  5001.5    .045       0
  5394.1    .035       0
Bank Sta=4987.6,5001.5
XS Rating Curve= 0 ,0
Exp/Cntr=0.3,0.1

Type RM Length L Ch R = 1 ,8675    ,448,448,448
BEGIN DESCRIPTION:
Stream0256 14.0
END DESCRIPTION:
XS GIS Cut Line= 3
      2388274.99     13740824.99        2387675.       13740325.
      2386675.01       13740525.
#Sta/Elev= 30
  4213.3  386.94  4226.9  387.63  4241.3  394.04  4255.6  393.47  4263.4  390.26
  4269.9  380.39  4277.7  376.76  4305.1  379.86  4328.5  374.68  4518.5  370.07
  4526.7  373.44  4532.9  380.04  4547.2  378.67  4553.7  372.13  4561.5  371.82
    4568  365.28  4582.3  361.97  4640.8  360.98    4753  360.29  4753.5  359.79
  4766.9  360.29  5449.8  361.82    5618  361.59  5677.6  364.87    5719  362.98
  5871.3  362.79  5901.9  364.63    5921  369.64  5952.9  381.23  6014.1   383.6
#Mann= 10 ,-1 , 0
  4213.3     .12       0  4328.5     .07       0  4526.7      .1       0
  4640.8    .045       0    4753    .045       0  4766.9    .045       0
  5449.8    .035       0    5618     .15       0    5719     .05       0
    5921    .035       0
Bank Sta=4753,4766.9
XS Rating Curve= 0 ,0
Exp/Cntr=0.3,0.1

Type RM Length L Ch R = 1 ,8227    ,685,685,685
BEGIN DESCRIPTION:
Stream0256 13.0
END DESCRIPTION:
XS GIS Cut Line= 4
      2388524.97     13740574.97        2387975.       13740075.
       2387838.9     13740052.32      2386583.61     13740477.87
#Sta/Elev= 30
  4261.8  395.66  4311.4  395.33    4354  376.36  4376.1     374  4466.8  373.02
  4505.7  369.55  4523.6  371.45  4545.2  369.11  4594.6  369.51  4679.7  374.97
  4694.6  368.87  4714.8  363.66  4743.2  361.25  4949.3  359.35    4970  357.45
  4970.5  356.95  4984.1  357.45    5076  360.39  5568.1  360.62  5793.4  363.32
  5957.8  363.23  5991.9  361.08  6007.8  363.71  6062.8   365.3  6128.2  362.23
  6181.9  365.38  6245.3  364.76  6298.1  376.63  6353.4  381.57  6468.5  378.02
#Mann= 10 ,-1 , 0
  4261.8     .12       0  4376.1    .035       0  4505.7     .07       0
  4694.6     .12       0  4949.3    .045       0    4970    .045       0
  4984.1    .045       0  5793.4    .035       0  5957.8     .15       0
  6062.8    .035       0
Bank Sta=4970,4984.1
XS Rating Curve= 0 ,0
Exp/Cntr=0.3,0.1

Type RM Length L Ch R = 1 ,7542    ,306,306,306
BEGIN DESCRIPTION:
Stream0256 12.0
END DESCRIPTION:
XS GIS Cut Line= 4
      2390043.83     13740140.82      2388853.72     13739170.84
      2388014.48      13739645.5      2386349.88     13740512.19
#Sta/Elev= 30
  2799.8   388.9  2852.5  386.24    2953  367.82  3070.3  368.19  3194.4  368.63
  3318.5  369.76  3488.7   374.2  3608.7  374.32  3814.9  374.41    3939  376.64
  4093.4  377.16  4187.1  373.85    4255  374.16  4337.3  372.23  4373.9  367.09
  4417.2  371.94  4492.3  373.18  4557.3  369.94  4573.2   364.2  4616.5  360.07
  4975.9  357.53  4976.4  357.03  4990.3  357.53  6085.4  359.72  6361.3  363.37
    6474  364.19  6597.3  365.78    6787  372.32  6980.3  373.47    7176  381.17
#Mann= 16 ,-1 , 0
  2799.8     .12       0  3070.3     .05       0  3194.4    .035       0
  3318.5     .12       0  3488.7     .07       0  3608.7    .035       0
  3814.9     .07       0    3939     .05       0  4093.4    .035       0
  4187.1     .05       0    4255    .035       0  4975.9    .035       0
  4990.3    .035       0  6361.3    .094       0    6474     .15       0
  6597.3    .035       0
Bank Sta=4975.9,4990.3
XS Rating Curve= 0 ,0
Exp/Cntr=0.3,0.1

Type RM Length L Ch R = 1 ,7236    ,365,365,365
BEGIN DESCRIPTION:
Stream0256 11.0
END DESCRIPTION:
XS GIS Cut Line= 4
      2390057.59     13740099.55      2388750.53     13739012.63
      2387532.94     13739721.17       2386109.5     13740147.51
#Sta/Elev= 30
  2868.4  389.02  2915.9  385.16  3008.4  367.98    3157  367.68    3282  367.68
  3407.1  369.37  3551.1  372.17  3599.5  372.13  3907.2  371.39  4032.3  372.11
  4157.3  373.94  4400.2  370.09  4449.7   361.4  4499.1  363.98  4581.8  359.07
  4997.4   357.1  4997.9   356.6  5011.8   357.1  5119.7  359.61  5346.1  358.94
  5514.2   359.4  5607.1   359.5  6138.9  359.73    6242  359.79  6345.6  360.81
  6585.9  361.16  6684.8  364.68  6760.4  361.87  6977.1     365    7463  380.05
#Mann= 20 ,-1 , 0
  2868.4     .12       0    3157     .05       0    3282    .035       0
  3407.1     .12       0  3551.1     .07       0  3599.5    .035       0
  3907.2     .07       0  4032.3     .05       0  4157.3    .035       0
  4997.4    .035       0  5011.8    .035       0  5119.7     .05       0
  5346.1     .07       0  5514.2    .035       0  5607.1     .07       0
  6138.9     .07       0    6242    .035       0  6345.6     .05       0
  6585.9    .094       0  6760.4     .05       0
Bank Sta=4997.4,5011.8
XS Rating Curve= 0 ,0
Exp/Cntr=0.3,0.1

Type RM Length L Ch R = 1 ,6871    ,459,459,459
BEGIN DESCRIPTION:
Stream0256 10.0
END DESCRIPTION:
XS GIS Cut Line= 3
      2390126.34     13740065.12        2389122.     13738957.59
      2386205.28     13738881.92
#Sta/Elev= 30
  2958.1  388.54  3079.8  384.15  3121.7  372.43  3178.5     364  3241.6  366.09
  3383.6  366.01  3396.7  365.87  3525.7  365.95  3667.7  365.14  3669.6  365.21
  4093.8  364.51  4215.6   364.2  4235.8  364.15  4352.1  364.31  4560.2  360.83
  4620.3  364.82  4893.1  357.67  4963.1  356.86  4963.6  356.36  4977.6  356.86
  6369.3  361.73  6467.7  361.07    6967  361.47  7021.1  364.21  7051.1  369.86
  7111.1  367.31  7151.1  384.21  7173.3  383.82  7251.1  379.11  7370.9  385.02
#Mann= 18 ,-1 , 0
  2958.1     .12       0  3241.6     .07       0  3383.6     .05       0
  3396.7     .07       0  3525.7    .035       0  3667.7     .07       0
  3669.6    .035       0  4093.8     .05       0  4215.6    .035       0
  4235.8     .05       0  4352.1    .035       0  4893.1     .05       0
  4963.1     .05       0  4977.6     .05       0  6369.3    .035       0
  6467.7     .05       0    6967    .035       0  7173.3     .05       0
Bank Sta=4963.1,4977.6
XS Rating Curve= 0 ,0
Exp/Cntr=0.3,0.1

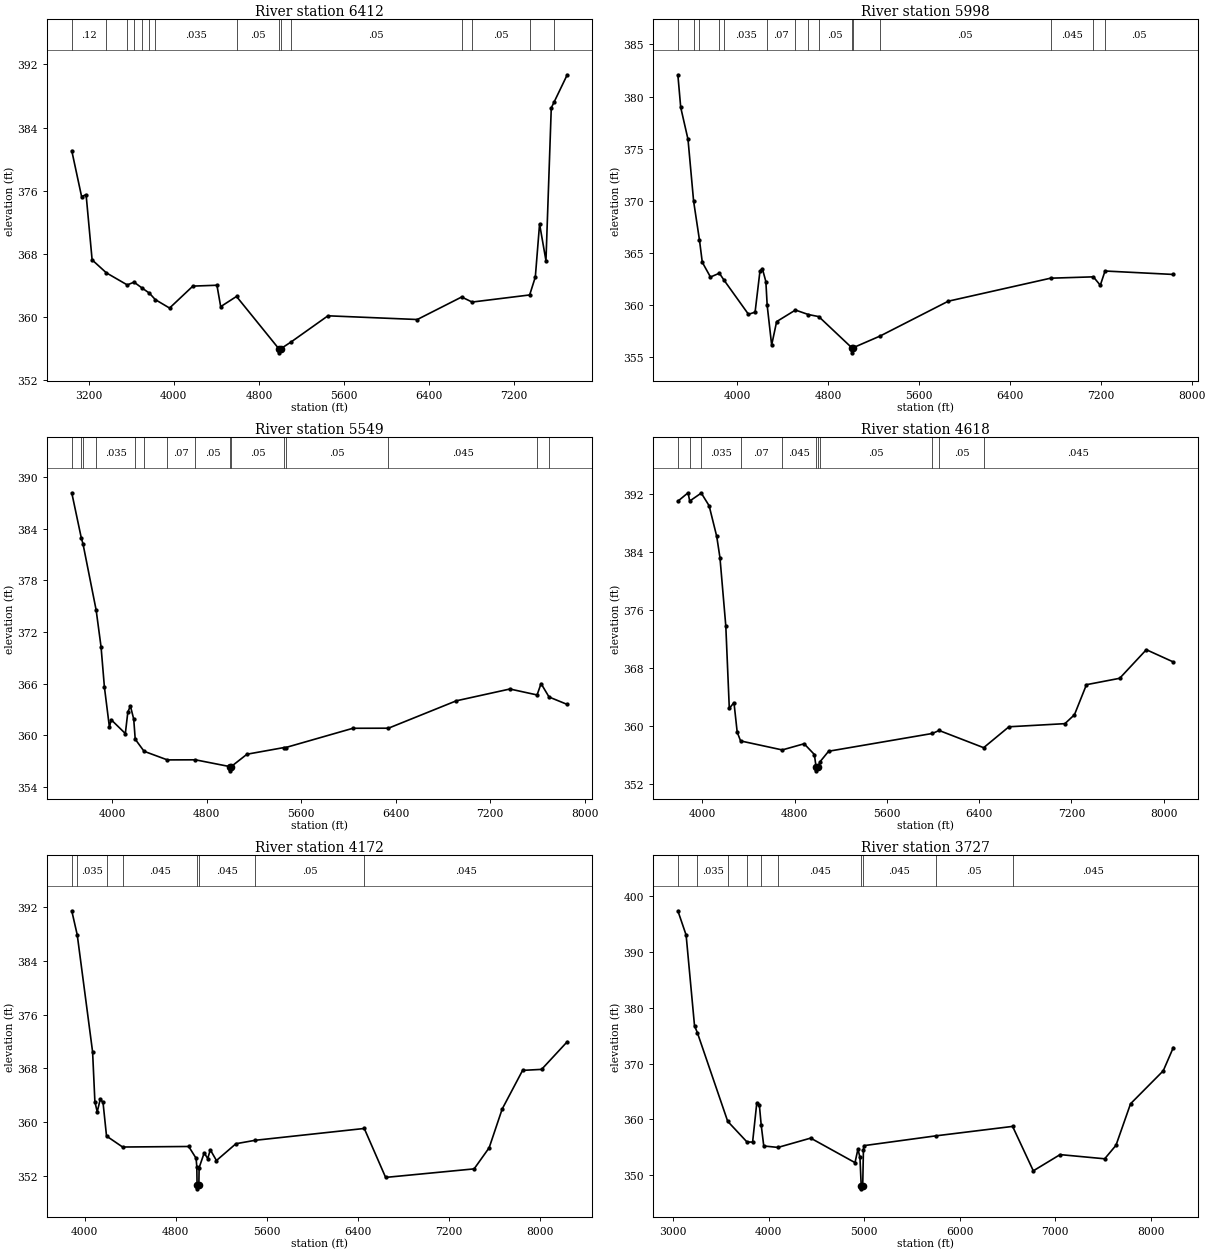
Type RM Length L Ch R = 1 ,6412    ,414,414,414
BEGIN DESCRIPTION:
Stream0256 9.0
END DESCRIPTION:
XS GIS Cut Line= 3
      2390215.75     13739955.03        2388825.       13738575.
      2386124.95       13738575.
#Sta/Elev= 30
  3040.1  381.08  3132.6  375.27    3175  375.51  3231.6  367.25  3365.6  365.61
  3562.1  364.08  3625.9  364.43    3697  363.73  3769.8  363.04  3825.8  362.22
  3959.9  361.15  4179.1  363.93  4405.4  364.04  4440.7  361.33  4589.4  362.62
  4988.5  355.98    4989  355.48  5003.1  355.98  5099.9  356.83  5449.4  360.17
  6289.4   359.7  6706.6  362.55  6805.1  361.91  7346.1  362.81  7399.4  365.08
  7439.4   371.8  7499.4  367.15  7549.4   386.5  7577.9  387.29  7699.4  390.69
#Mann= 15 ,-1 , 0
  3040.1     .12       0  3365.6     .05       0  3562.1     .07       0
  3625.9     .05       0    3697     .07       0  3769.8     .05       0
  3825.8    .035       0  4589.4     .05       0  4988.5     .05       0
  5003.1     .05       0  5099.9     .05       0  6706.6    .035       0
  6805.1     .05       0  7346.1    .035       0  7577.9     .05       0
Bank Sta=4988.5,5003.1
XS Rating Curve= 0 ,0
Exp/Cntr=0.3,0.1

Type RM Length L Ch R = 1 ,5998    ,449,449,449
BEGIN DESCRIPTION:
Stream0256 8.0
END DESCRIPTION:
XS GIS Cut Line= 3
      2390470.32     13739163.98        2389175.       13738375.
      2386475.04     13737475.01
#Sta/Elev= 30
    3476  382.09  3501.3  378.95  3565.3  375.89  3614.7  369.95  3666.5   366.2
  3691.1  364.08  3763.2  362.66  3841.3  363.03  3883.3  362.35  4097.9  359.08
    4156  359.29  4198.6   363.2  4219.9  363.47  4250.9  362.23  4262.6  359.93
  4301.9  356.13  4345.8  358.38  4511.3  359.49    4625  359.06  4716.9  358.86
  5006.4  355.88  5006.9  355.38  5021.1  355.88    5256  356.99    5857  360.34
  6757.4  362.55  7134.5  362.68  7195.7  361.87  7237.3  363.24  7838.7  362.91
#Mann= 15 ,-1 , 0
    3476     .12       0  3614.7     .05       0  3666.5     .12       0
  3841.3     .05       0  3883.3    .035       0  4262.6     .07       0
  4511.3     .05       0    4625     .07       0  4716.9     .05       0
  5006.4     .05       0  5021.1     .05       0    5256     .05       0
  6757.4    .045       0  7134.5    .035       0  7237.3     .05       0
Bank Sta=5006.4,5021.1
XS Rating Curve= 0 ,0
Exp/Cntr=0.3,0.1

Type RM Length L Ch R = 1 ,5549    ,931,931,931
BEGIN DESCRIPTION:
Stream0256 7.0
END DESCRIPTION:
XS GIS Cut Line= 3
      2390524.99     13739024.99        2389525.       13738125.
        2386825.       13737225.
#Sta/Elev= 30
  3659.8  388.16  3740.5  382.92  3755.2  382.21  3866.2  374.54  3907.6  370.28
    3936  365.61  3978.6  360.93  3992.8  361.82  4113.1  360.21    4134  362.68
  4155.7  363.42  4184.1  361.88  4196.7  359.55  4271.6  358.15  4468.7  357.15
  4705.7  357.16  4994.4  356.38  4994.9  355.88  5009.1  356.38  5142.2  357.81
  5453.9  358.58  5468.3  358.58  6038.2  360.82  6338.8  360.83  6913.1  364.01
  7366.3  365.38  7596.2  364.69  7629.8  366.01  7697.5  364.45  7851.2  363.59
#Mann= 15 ,-1 , 0
  3659.8     .12       0  3740.5     .07       0  3755.2     .12       0
  3866.2    .035       0  4196.7     .07       0  4271.6     .05       0
  4468.7     .07       0  4705.7     .05       0  4994.4     .05       0
  5009.1     .05       0  5453.9    .035       0  5468.3     .05       0
  6338.8    .045       0  7596.2    .035       0  7697.5     .05       0
Bank Sta=4994.4,5009.1
XS Rating Curve= 0 ,0
Exp/Cntr=0.3,0.1

Type RM Length L Ch R = 1 ,4618    ,446,446,446
BEGIN DESCRIPTION:
Stream0256 6.0
END DESCRIPTION:
XS GIS Cut Line= 3
        2390575.       13739075.        2390375.       13737875.
      2387409.53     13737045.33
#Sta/Elev= 30
  3787.9  390.95  3876.6  392.11  3890.6  390.97  3990.9  392.07  4059.1  390.32
    4125  386.09  4152.9  383.18  4203.6  373.76    4234   362.4  4274.5   363.2
  4302.4  359.13  4331.9  357.92  4692.9  356.68  4882.8  357.53  4971.5  356.05
  4986.6   354.3  4987.1   353.8  5002.1   354.3  5021.1  355.06    5095   356.5
  5994.6  358.95  6053.3  359.36  6439.3  356.99  6658.4  359.87  7143.7   360.3
  7226.6  361.53  7330.5  365.67  7618.6  366.55  7849.7  370.49  8083.8   368.8
#Mann= 11 ,-1 , 0
  3787.9     .12       0  3890.6     .07       0  3990.9    .035       0
  4331.9     .07       0  4692.9    .045       0  4986.6    .045       0
  5002.1    .045       0  5021.1     .05       0  5994.6    .035       0
  6053.3     .05       0  6439.3    .045       0
Bank Sta=4986.6,5002.1
XS Rating Curve= 0 ,0
Exp/Cntr=0.3,0.1

Type RM Length L Ch R = 1 ,4172    ,445,445,445
BEGIN DESCRIPTION:
Stream0256 5.0
END DESCRIPTION:
XS GIS Cut Line= 3
      2390575.01     13738824.95        2390775.       13737725.
      2387774.99       13736525.
#Sta/Elev= 30
  3887.7  391.44  3935.9  387.85  4070.6  370.46  4090.9  363.01  4111.3  361.54
  4137.9   363.4  4162.1  362.94  4192.9  357.93  4334.1   356.3  4914.2  356.38
    4979  354.63  4985.4  353.38  4987.8  350.58  4988.3  350.08  5003.3  350.58
  5005.7  353.22  5050.1  355.42  5081.1  354.59    5104  355.88  5157.8  354.29
  5328.8  356.79  5497.3   357.3  6455.3  359.06  6642.8  351.78  7419.6  353.05
  7551.5  356.19    7666  361.96    7845   367.7    8012  367.85  8236.8  371.96
#Mann= 8 ,-1 , 0
  3887.7     .12       0  3935.9    .035       0  4192.9     .07       0
  4334.1    .045       0  4987.8    .045       0  5003.3    .045       0
  5497.3     .05       0  6455.3    .045       0
Bank Sta=4987.8,5003.3
XS Rating Curve= 0 ,0
Exp/Cntr=0.3,0.1

Type RM Length L Ch R = 1 ,3727    ,1471,1471,1471
BEGIN DESCRIPTION:
Stream0256 4.0
END DESCRIPTION:
XS GIS Cut Line= 3
      2392025.02     13739025.04        2390975.       13737375.
      2387863.15     13736508.66
#Sta/Elev= 30
    3050  397.43  3136.4  393.08  3224.5  376.79  3254.1  375.57  3571.7  359.66
    3774  355.95  3832.4  355.94  3876.4     363  3903.5  362.51  3922.5  358.96
  3949.2  355.24    4098  354.98  4440.2  356.65  4904.2  352.25  4934.7  354.66
  4955.9  353.22  4969.3  348.05  4969.8  347.55  4984.8  348.05  4992.3  354.47
  4998.2   355.3    5752  357.06  6553.7  358.75  6770.5  350.78  7050.7  353.69
  7517.6  352.94  7635.8  355.36  7788.2  362.81  8130.3  368.72    8236   372.9
#Mann= 10 ,-1 , 0
    3050     .07       0  3254.1    .035       0  3571.7     .07       0
    3774    .035       0  3922.5     .07       0    4098    .045       0
  4969.3    .045       0  4984.8    .045       0    5752     .05       0
  6553.7    .045       0
Bank Sta=4969.3,4984.8
XS Rating Curve= 0 ,0
Exp/Cntr=0.3,0.1

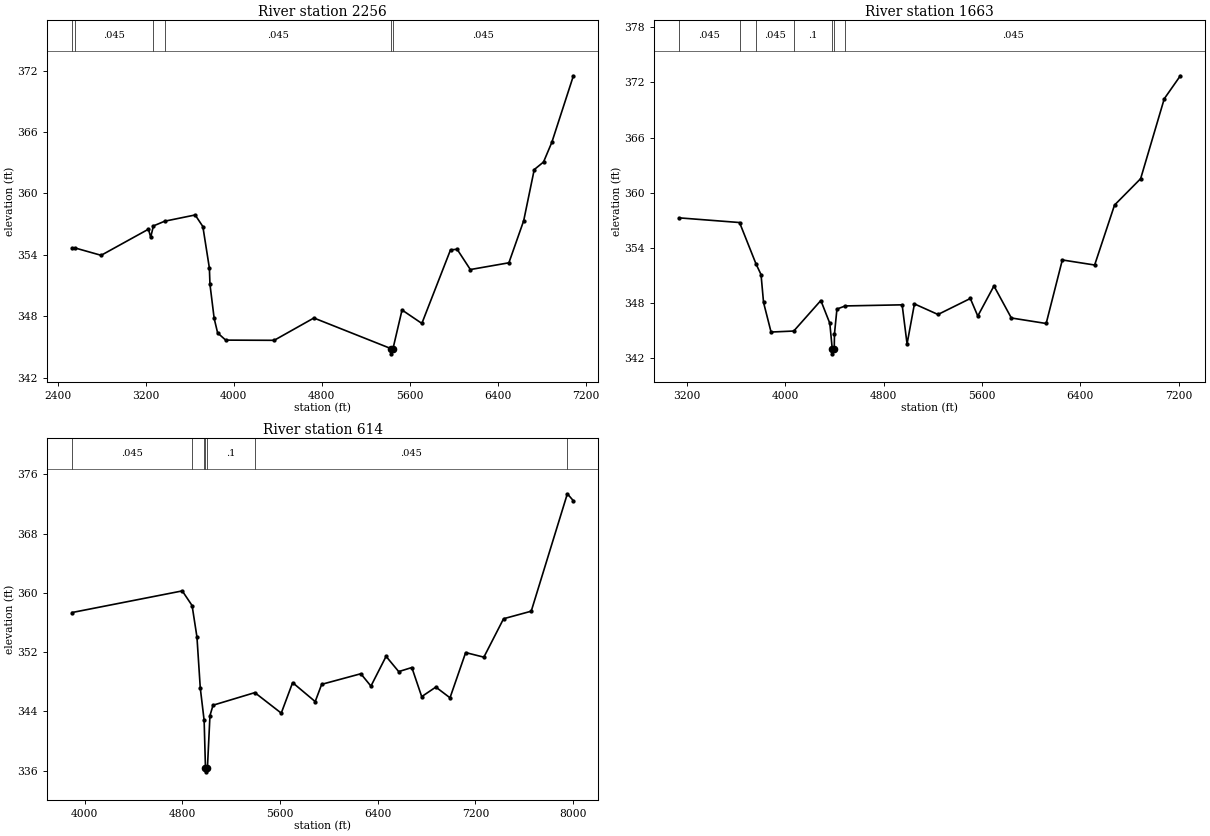
Type RM Length L Ch R = 1 ,2256    ,593,593,593
BEGIN DESCRIPTION:
XS6267
END DESCRIPTION:
XS GIS Cut Line= 3
      2392396.46     13737258.48      2390422.14     13736632.48
      2387939.44     13736494.93
#Sta/Elev= 30
  2530.6  354.64  2553.9  354.69    2795  353.96  3225.1  356.51  3245.5  355.73
  3270.3  356.83  3372.7  357.29  3649.9   357.9  3719.7  356.77  3779.1  352.71
  3784.3  351.13  3822.5   347.8  3854.1  346.38  3927.4  345.68    4368  345.66
  4729.1  347.84  5432.4  344.84  5432.9  344.34    5448  344.84  5530.4  348.62
  5710.6  347.31    5971  354.49  6031.1  354.55  6151.3  352.57  6501.8  353.23
  6636.1  357.33  6732.2  362.33  6816.6  363.07  6892.4     365  7088.3  371.49
#Mann= 6 ,-1 , 0
  2530.6    .035       0  2553.9    .045       0  3270.3    .035       0
  3372.7    .045       0  5432.4    .045       0    5448    .045       0
Bank Sta=5432.4,5448
XS Rating Curve= 0 ,0
Exp/Cntr=0.3,0.1

Type RM Length L Ch R = 1 ,1663    ,1049,1049,1049
BEGIN DESCRIPTION:
XS6266
END DESCRIPTION:
XS GIS Cut Line= 4
      2391873.62     13735978.97      2390662.91     13736178.46
      2389933.73     13736150.94      2387835.59     13736467.38
#Sta/Elev= 30
  3134.2  357.28  3626.9  356.77  3761.4  352.25  3801.7  351.11  3822.1  348.08
  3883.2  344.86  4067.9  344.97  4288.2  348.29  4361.2  345.81  4381.3  342.99
  4381.8  342.49  4397.1  342.99  4399.2  344.68  4419.2  347.36    4487   347.7
  4949.6  347.82  4989.6  343.57  5049.6  347.92  5241.3  346.77  5504.3  348.51
    5565   346.6  5696.4  349.87    5838  346.39  6121.2  345.79  6252.7   352.7
  6515.6  352.15  6677.4  358.67  6889.8  361.54  7081.9  370.23  7212.8  372.73
#Mann= 7 ,-1 , 0
  3134.2    .045       0  3626.9    .035       0  3761.4    .045       0
  4067.9      .1       0  4381.3    .045       0  4397.1      .1       0
    4487    .045       0
Bank Sta=4381.3,4397.1
XS Rating Curve= 0 ,0
Exp/Cntr=0.3,0.1

Type RM Length L Ch R = 1 ,614     ,0,0,0
BEGIN DESCRIPTION:
XS6265
END DESCRIPTION:
XS GIS Cut Line= 3
      2391825.51     13735614.38      2390724.82     13735683.17
       2387821.9     13736446.73
#Sta/Elev= 30
  3897.7  357.34    4800  360.26  4880.5  358.28  4920.2  354.04  4947.5  347.14
  4979.1  342.76    4990  336.32  4990.5  335.82  5005.9  336.32  5026.8  343.42
    5052  344.82    5394  346.52  5610.4  343.75  5703.5  347.87  5888.3  345.31
  5941.3  347.64  6261.8  349.07  6344.6   347.4  6468.6  351.42    6572  349.36
  6679.5  349.91  6760.2  345.98    6876  347.27  6991.9  345.82  7120.1  351.93
  7269.1  351.31  7430.4   356.5  7656.9  357.52  7952.6  373.38  8002.2  372.43
#Mann= 7 ,-1 , 0
  3897.7    .045       0  4880.5     .12       0  4979.1      .1       0
    4990     .05       0  5005.9      .1       0    5394    .045       0
  7952.6     .12       0
Bank Sta=4990,5005.9
XS Rating Curve= 0 ,0
Exp/Cntr=0.3,0.1

Chan Stop Cuts=-1
Use User Specified Reach Order=0
Composite Channel Slope=5