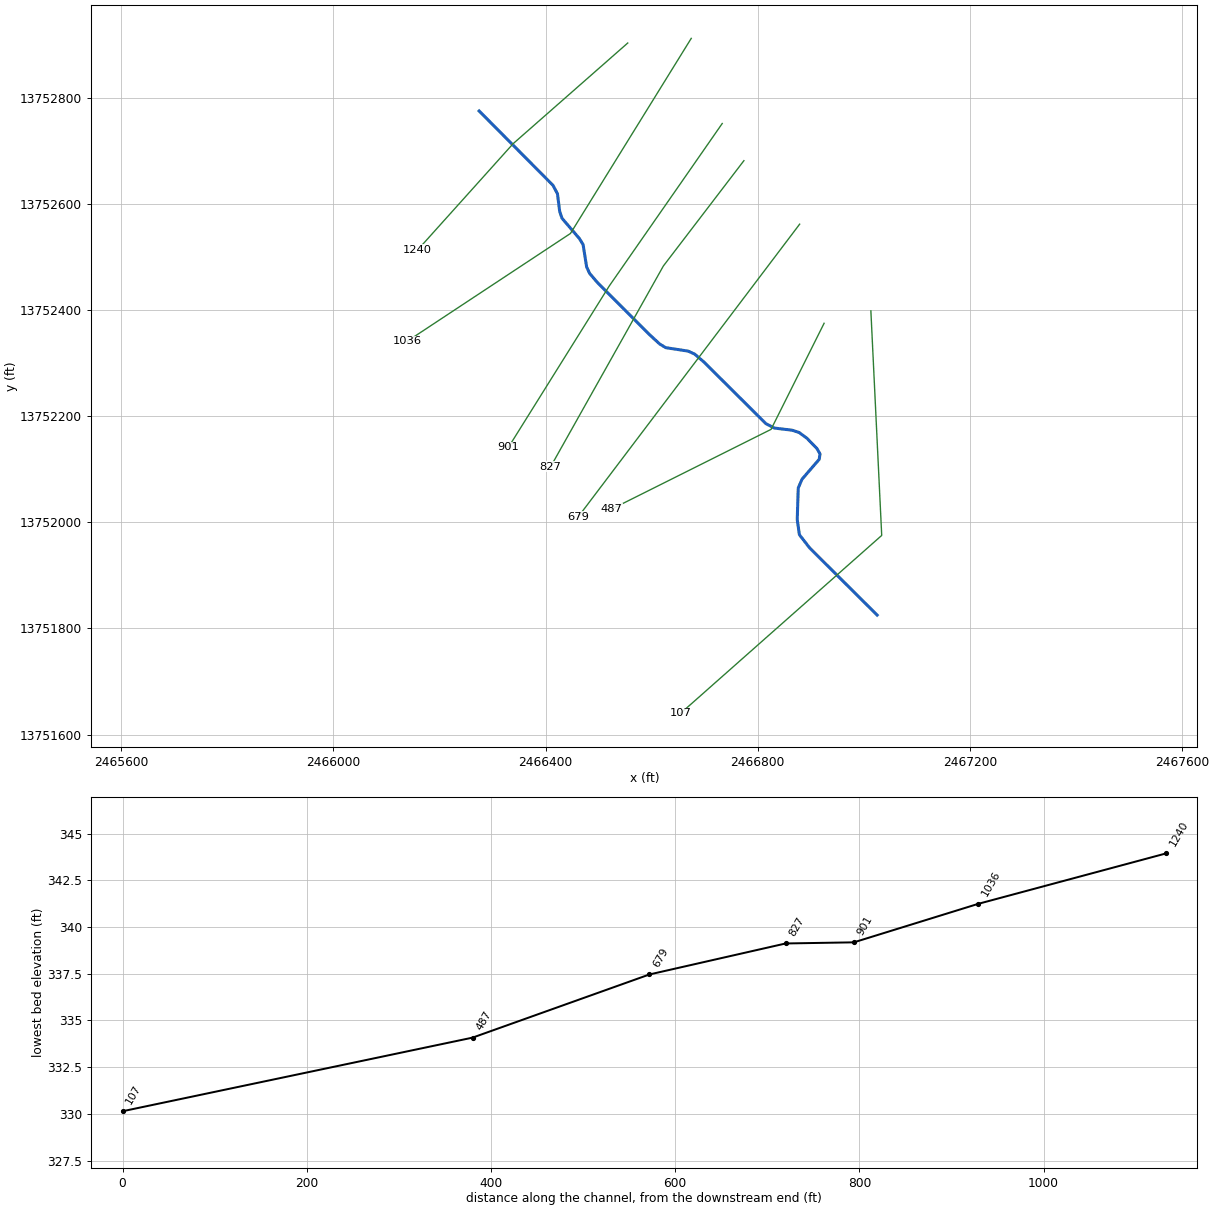
--- Stream0259.prj (project) ---

Proj Title=Stream0259 Base Level Engineering
Current Plan=p01
Default Exp/Contr=0.3,0.1
English Units
Geom File=g01
Flow File=f01
Plan File=p01
BEGIN DESCRIPTION:
Stream0259
END DESCRIPTION:

--- Stream0259.p01 (plan) ---

Plan Title=Multiple Run
Short Identifier=Multiple
Geom File=g01
Flow File=f01
Subcritical Flow
K Sum by GR= 0
Std Step Tol= 0.01
Critical Tol= 0.01
Num of Std Step Trials= 20
Max Error Tol= 0.3
Flow Tol Ratio= 0.001
Split Flow NTrial= 30
Split Flow Tol= 0.02
Split Flow Ratio= 0.02
Log Output Level= 0
Friction Slope Method= 1
Unsteady Friction Slope Method= 2
Unsteady Bridges Friction Slope Method= 1
Parabolic Critical Depth
Global Vel Dist=  1 , 1 , 1
Global Log Level= 0
CheckData=True
Encroach Param= -1, 0, 0, 0
BEGIN DESCRIPTION:
Multiple Run
END DESCRIPTION:

--- Stream0259.f01 (steady flow) ---

Flow Title=Multiple
Number of Profiles=7
Profile Names=10-year,25-year,50-year,1pct_min,100-year,1pct_plu,500-year
River Rch & RM= Stream0259,Reach-1,1240
     227     341     438     274     547    1092     841
Boundary for River Rch & Prof#=Stream0259,Reach-1,1
Up Type=0
Dn Type=3
Dn Slope=0.005
Boundary for River Rch & Prof#=Stream0259,Reach-1,2
Up Type=0
Dn Type=3
Dn Slope=0.005
Boundary for River Rch & Prof#=Stream0259,Reach-1,3
Up Type=0
Dn Type=3
Dn Slope=0.005
Boundary for River Rch & Prof#=Stream0259,Reach-1,4
Up Type=0
Dn Type=3
Dn Slope=0.005
Boundary for River Rch & Prof#=Stream0259,Reach-1,5
Up Type=0
Dn Type=3
Dn Slope=0.005
Boundary for River Rch & Prof#=Stream0259,Reach-1,6
Up Type=0
Dn Type=3
Dn Slope=0.005
Boundary for River Rch & Prof#=Stream0259,Reach-1,7
Up Type=0
Dn Type=3
Dn Slope=0.005

--- Stream0259.g01 (geometry) ---

Geom Title=Existing Conditions

River Reach=Stream0259,Reach-1
Reach XY= 30
      2466275.00     13752775.00      2466414.24     13752634.69
      2466422.50     13752618.97      2466426.70     13752585.70
      2466431.10     13752572.81      2466463.90     13752534.55
      2466470.81     13752523.26      2466477.50     13752481.03
      2466483.14     13752468.94      2466498.01     13752451.53
      2466594.84     13752354.61      2466615.32     13752335.78
      2466626.65     13752328.98      2466668.95     13752322.46
      2466681.05     13752316.84      2466698.46     13752301.98
      2466815.36     13752185.78      2466831.13     13752177.54
      2466864.69     13752173.46      2466877.85     13752169.15
      2466892.56     13752158.36      2466911.62     13752138.73
      2466917.31     13752128.67      2466915.77     13752118.62
      2466883.43     13752081.19      2466876.27     13752064.52
      2466874.34     13752004.93      2466878.46     13751976.50
      2466897.83     13751951.47      2467025.00     13751825.00

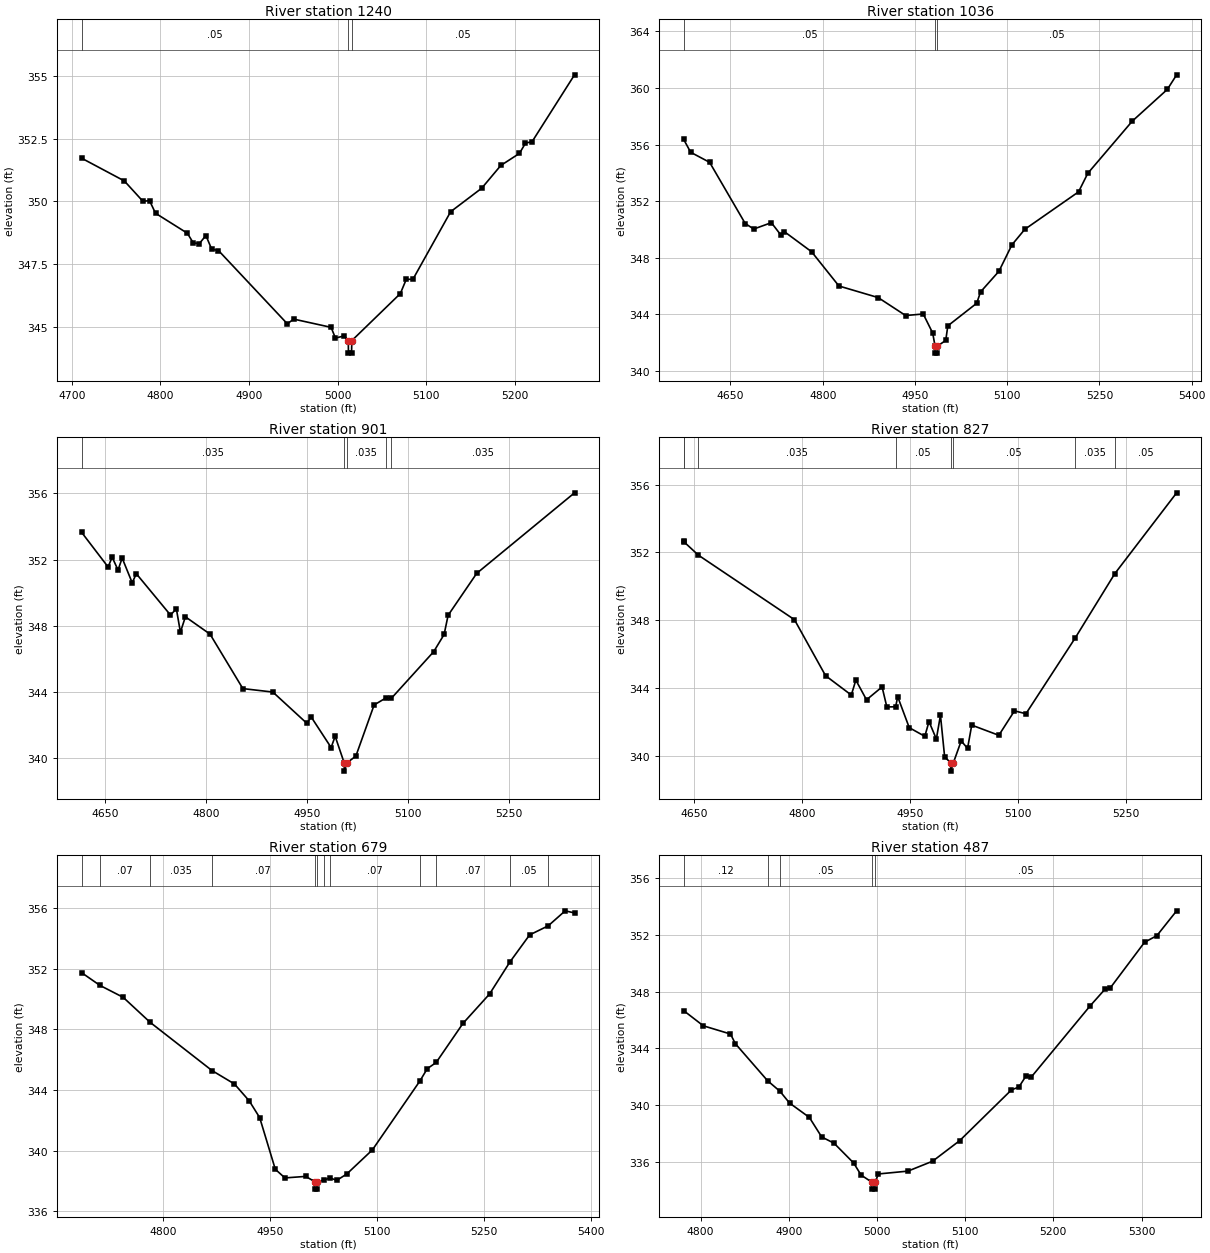
Type RM Length L Ch R = 1,1240,204,204,204
BEGIN DESCRIPTION:
XS6290
END DESCRIPTION:
XS GIS Cut Line= 3
      2466554.96     13752903.10      2466339.05     13752713.45
      2466159.05     13752513.12
#Sta/Elev= 30
  4710.9  351.73  4759.2  350.82  4780.1  350.01  4787.7  350.03  4794.4  349.53
  4830.4  348.73  4837.1  348.34  4844.0  348.32  4851.3  348.64  4857.9  348.09
  4865.5  348.04  4943.3  345.11  4950.4  345.30  4992.7  344.97  4997.6  344.54
  5007.4  344.63  5012.1  344.44  5012.3  343.94  5015.8  343.94  5016.1  344.44
  5070.9  346.32  5077.6  346.89  5085.1  346.89  5127.7  349.59  5162.8  350.53
  5184.4  351.44  5205.4  351.92  5212.2  352.33  5219.7  352.39  5267.6  355.06
#Mann=3,-1,0
  4710.9    0.05       0  5012.1    0.05       0  5016.1    0.05       0
Bank Sta=5012.1,5016.1
Exp/Cntr=0.3,0.1

Type RM Length L Ch R = 1,1036,135,135,135
BEGIN DESCRIPTION:
Stream0259 2.0
END DESCRIPTION:
XS GIS Cut Line= 3
      2466674.65     13752911.91      2466447.02     13752544.20
      2466138.90     13752340.73
#Sta/Elev= 30
  4573.9  356.36  4585.3  355.45  4616.1  354.74  4674.0  350.41  4687.9  350.02
  4716.5  350.47  4731.9  349.60  4737.8  349.83  4782.0  348.41  4826.4  345.99
  4890.2  345.17  4934.9  343.90  4963.5  344.01  4978.9  342.66  4982.7  341.74
  4983.0  341.24  4986.5  341.24  4986.7  341.74  5000.1  342.14  5003.5  343.17
  5050.5  344.77  5056.7  345.57  5086.6  347.03  5107.7  348.90  5128.7  350.00
  5216.1  352.65  5231.1  353.96  5303.4  357.65  5360.5  359.90  5375.6  360.93
#Mann=3,-1,0
  4573.9    0.05       0  4982.7    0.05       0  4986.7    0.05       0
Bank Sta=4982.7,4986.7
Exp/Cntr=0.3,0.1

Type RM Length L Ch R = 1,901,74,74,74
BEGIN DESCRIPTION:
XS6293
END DESCRIPTION:
XS GIS Cut Line= 3
      2466733.01     13752751.42      2466519.97     13752444.99
      2466330.29     13752141.50
#Sta/Elev= 30
  4615.6  353.65  4654.9  351.55  4661.0  352.14  4669.7  351.36  4675.8  352.09
  4690.7  350.59  4696.8  351.14  4747.4  348.64  4756.2  349.01  4762.2  347.60
  4769.6  348.53  4806.1  347.48  4854.8  344.18  4899.3  343.97  4949.9  342.07
  4956.0  342.47  4985.7  340.61  4991.7  341.29  5005.1  339.68  5005.3  339.18
  5009.1  339.68  5022.4  340.09  5049.5  343.19  5066.4  343.60  5074.8  343.58
  5137.9  346.42  5153.3  347.46  5159.2  348.62  5201.6  351.16  5346.7  356.04
#Mann=5,-1,0
  4615.6   0.035       0  5005.1   0.035       0  5009.1   0.035       0
  5066.4    0.05       0  5074.8   0.035       0
Bank Sta=5005.1,5009.1
Exp/Cntr=0.3,0.1

Type RM Length L Ch R = 1,827,148,148,148
BEGIN DESCRIPTION:
XS6292
END DESCRIPTION:
XS GIS Cut Line= 3
      2466773.86     13752681.38      2466622.10     13752482.92
      2466409.52     13752104.35
#Sta/Elev= 30
  4636.1  352.67  4637.1  352.60  4656.5  351.84  4789.8  348.04  4833.0  344.74
  4868.7  343.60  4875.0  344.48  4889.8  343.32  4911.4  344.08  4918.0  342.90
  4930.2  342.91  4933.1  343.50  4949.1  341.68  4970.7  341.17  4976.5  342.04
  4986.7  341.01  4992.4  342.41  4998.2  339.96  5006.4  339.62  5006.6  339.12
  5010.4  339.62  5021.2  340.90  5030.0  340.46  5035.8  341.83  5073.4  341.23
  5095.1  342.67  5111.0  342.50  5179.2  346.95  5234.3  350.75  5320.1  355.51
#Mann=8,-1,0
  4636.1   0.035       0  4637.1    0.07       0  4656.5   0.035       0
  4930.2    0.05       0  5006.4    0.05       0  5010.4    0.05       0
  5179.2   0.035       0  5234.3    0.05       0
Bank Sta=5006.4,5010.4
Exp/Cntr=0.3,0.1

Type RM Length L Ch R = 1,679,192,192,192
BEGIN DESCRIPTION:
XS6291
END DESCRIPTION:
XS GIS Cut Line= 2
      2466878.91     13752561.74      2466461.62     13752010.22
#Sta/Elev= 30
  4685.2  351.75  4710.9  350.91  4743.6  350.12  4781.4  348.47  4868.1  345.29
  4899.7  344.40  4920.5  343.28  4935.1  342.18  4957.0  338.77  4970.5  338.20
  4999.6  338.30  5012.1  337.96  5012.4  337.46  5015.9  337.46  5016.1  337.96
  5025.4  338.06  5033.7  338.20  5043.3  338.04  5057.3  338.46  5093.2  340.05
  5159.9  344.60  5170.2  345.41  5182.7  345.82  5220.3  348.40  5257.6  350.34
  5286.1  352.45  5313.8  354.24  5339.9  354.84  5363.7  355.83  5376.8  355.69
#Mann=12,-1,0
  4685.2   0.035       0  4710.9    0.07       0  4781.4   0.035       0
  4868.1    0.07       0  5012.1    0.05       0  5016.1    0.07       0
  5025.4    0.05       0  5033.7    0.07       0  5159.9    0.05       0
  5182.7    0.07       0  5286.1    0.05       0  5339.9    0.07       0
Bank Sta=5012.1,5016.1
Exp/Cntr=0.3,0.1

Type RM Length L Ch R = 1,487,380,380,380
BEGIN DESCRIPTION:
Stream0259 1.0
END DESCRIPTION:
XS GIS Cut Line= 3
      2466924.98     13752374.96      2466825.00     13752175.00
      2466524.97     13752024.99
#Sta/Elev= 30
  4780.8  346.67  4803.1  345.60  4833.9  345.02  4839.4  344.34  4875.9  341.73
  4890.0  340.98  4900.9  340.15  4923.3  339.14  4937.3  337.76  4951.3  337.32
  4973.6  335.92  4982.0  335.07  4994.0  334.58  4994.2  334.08  4997.7  334.08
  4998.0  334.58  5001.6  335.15  5035.1  335.35  5063.1  336.05  5093.8  337.50
  5152.5  341.08  5160.9  341.28  5169.3  342.09  5174.9  341.98  5241.9  347.02
  5258.7  348.19  5264.3  348.25  5303.4  351.49  5317.4  351.96  5339.8  353.71
#Mann=5,-1,0
  4780.8    0.12       0  4875.9    0.07       0  4890.0    0.05       0
  4994.0    0.05       0  4998.0    0.05       0
Bank Sta=4994,4998
Exp/Cntr=0.3,0.1

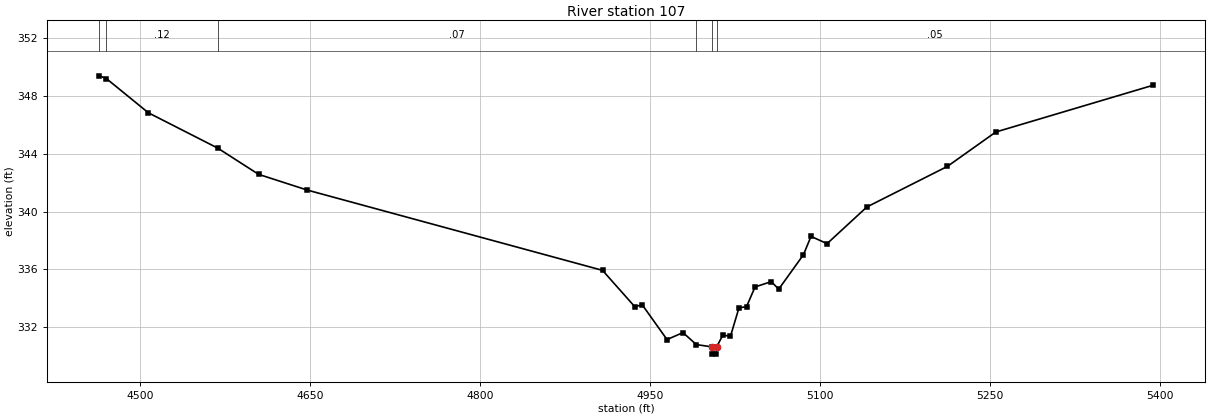
Type RM Length L Ch R = 1,107,0,0,0
BEGIN DESCRIPTION:
XS6289
END DESCRIPTION:
XS GIS Cut Line= 3
      2467013.12     13752398.26      2467033.55     13751975.18
      2466654.46     13751639.84
#Sta/Elev= 30
  4463.9  349.41  4470.1  349.22  4507.2  346.85  4568.5  344.40  4604.4  342.59
  4647.4  341.50  4908.0  335.94  4936.4  333.43  4943.1  333.55  4964.9  331.15
  4979.0  331.63  4990.8  330.80  5004.7  330.64  5004.9  330.14  5008.4  330.14
  5008.7  330.64  5014.2  331.46  5020.9  331.37  5028.4  333.34  5035.1  333.43
  5042.6  334.79  5056.9  335.16  5063.5  334.64  5085.3  337.02  5092.0  338.29
  5106.2  337.79  5141.3  340.33  5212.4  343.14  5255.1  345.52  5393.6  348.75
#Mann=6,-1,0
  4463.9   0.035       0  4470.1    0.12       0  4568.5    0.07       0
  4990.8    0.05       0  5004.7    0.05       0  5008.7    0.05       0
Bank Sta=5004.7,5008.7
Exp/Cntr=0.3,0.1

Chan Stop Cuts=-1