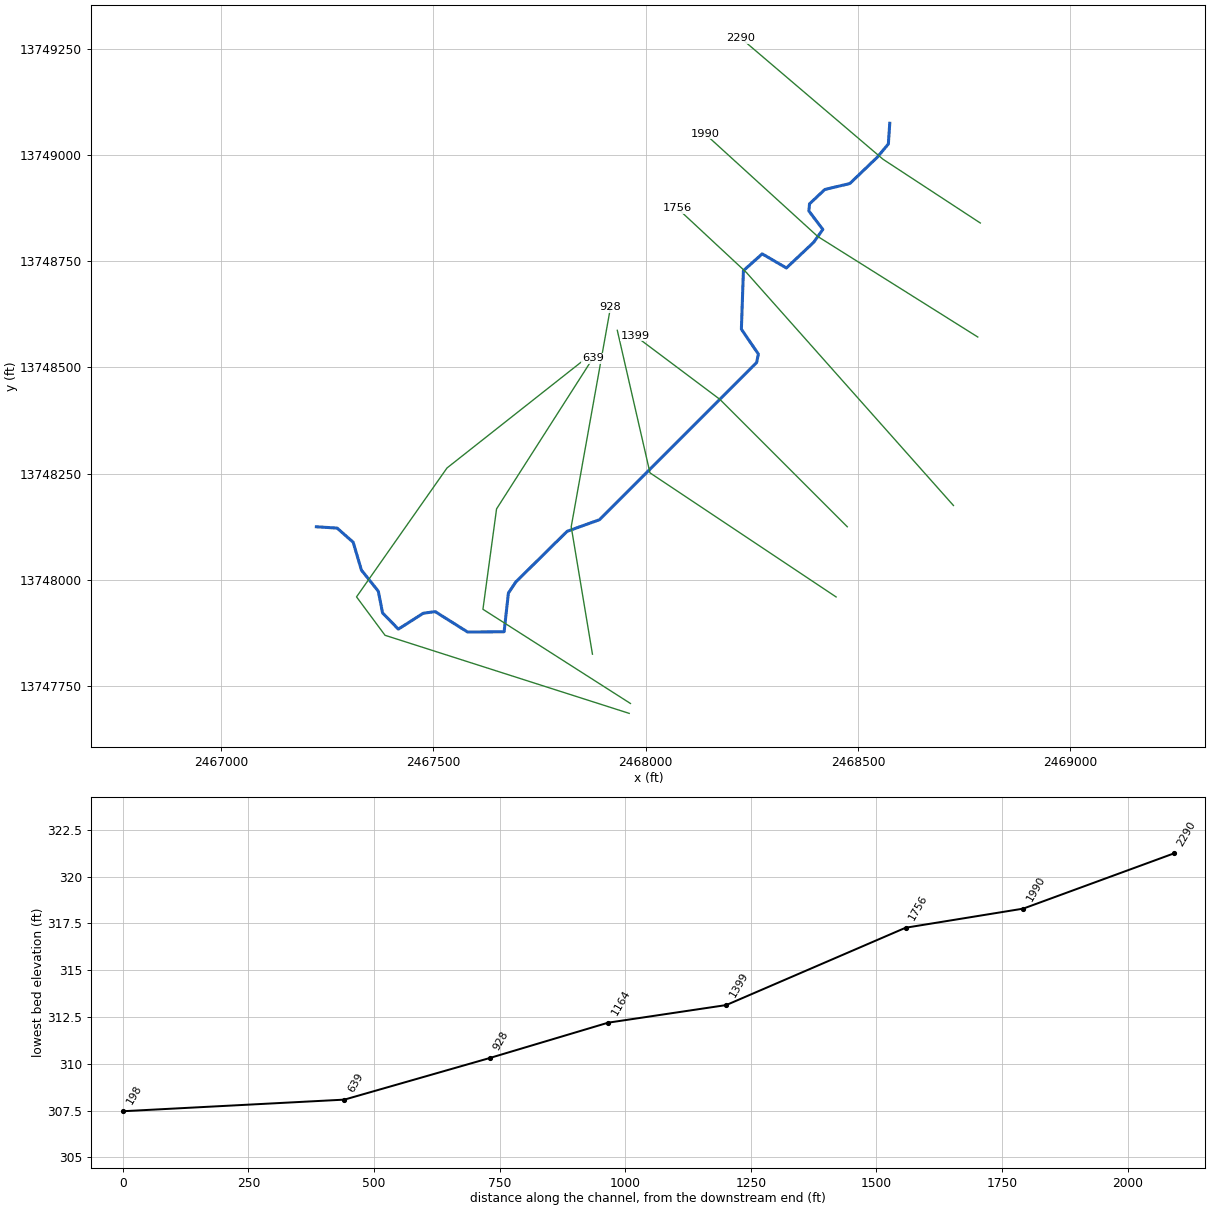
--- Stream0260.prj (project) ---

Proj Title=Stream0260 Base Level Engineering
Current Plan=p01
Default Exp/Contr=0.3,0.1
English Units
Geom File=g01
Flow File=f01
Plan File=p01
BEGIN DESCRIPTION:
Stream0260
END DESCRIPTION:

--- Stream0260.p01 (plan) ---

Plan Title=Multiple Run
Short Identifier=Multiple
Geom File=g01
Flow File=f01
Subcritical Flow
K Sum by GR= 0
Std Step Tol= 0.01
Critical Tol= 0.01
Num of Std Step Trials= 20
Max Error Tol= 0.3
Flow Tol Ratio= 0.001
Split Flow NTrial= 30
Split Flow Tol= 0.02
Split Flow Ratio= 0.02
Log Output Level= 0
Friction Slope Method= 1
Unsteady Friction Slope Method= 2
Unsteady Bridges Friction Slope Method= 1
Parabolic Critical Depth
Global Vel Dist=  1 , 1 , 1
Global Log Level= 0
CheckData=True
Encroach Param= -1, 0, 0, 0
BEGIN DESCRIPTION:
Multiple Run
END DESCRIPTION:

--- Stream0260.f01 (steady flow) ---

Flow Title=Multiple
Number of Profiles=7
Profile Names=10-year,25-year,50-year,1pct_min,100-year,1pct_plu,500-year
River Rch & RM= Stream0260,Reach-1,2290
     416     650     854     545    1088    2171    1745
Boundary for River Rch & Prof#=Stream0260,Reach-1,1
Up Type=0
Dn Type=3
Dn Slope=0.005
Boundary for River Rch & Prof#=Stream0260,Reach-1,2
Up Type=0
Dn Type=3
Dn Slope=0.005
Boundary for River Rch & Prof#=Stream0260,Reach-1,3
Up Type=0
Dn Type=3
Dn Slope=0.005
Boundary for River Rch & Prof#=Stream0260,Reach-1,4
Up Type=0
Dn Type=3
Dn Slope=0.005
Boundary for River Rch & Prof#=Stream0260,Reach-1,5
Up Type=0
Dn Type=3
Dn Slope=0.005
Boundary for River Rch & Prof#=Stream0260,Reach-1,6
Up Type=0
Dn Type=3
Dn Slope=0.005
Boundary for River Rch & Prof#=Stream0260,Reach-1,7
Up Type=0
Dn Type=3
Dn Slope=0.005

--- Stream0260.g01 (geometry) ---

Geom Title=Existing Conditions

River Reach=Stream0260,Reach-1
Reach XY= 30
      2468575.00     13749075.00      2468571.73     13749026.34
      2468545.35     13748994.78      2468481.02     13748933.14
      2468422.17     13748919.15      2468386.11     13748885.32
      2468384.55     13748868.49      2468417.43     13748824.99
      2468395.90     13748794.84      2468331.70     13748734.31
      2468274.76     13748767.54      2468230.45     13748727.99
      2468225.65     13748590.17      2468265.71     13748531.53
      2468261.47     13748511.62      2467891.67     13748141.65
      2467815.32     13748114.22      2467694.64     13747995.13
      2467677.19     13747969.01      2467666.99     13747877.84
      2467581.06     13747877.15      2467504.79     13747925.20
      2467476.62     13747921.38      2467417.98     13747884.03
      2467380.83     13747922.14      2467370.81     13747973.20
      2467331.09     13748022.82      2467311.63     13748088.55
      2467273.97     13748121.86      2467225.00     13748125.00

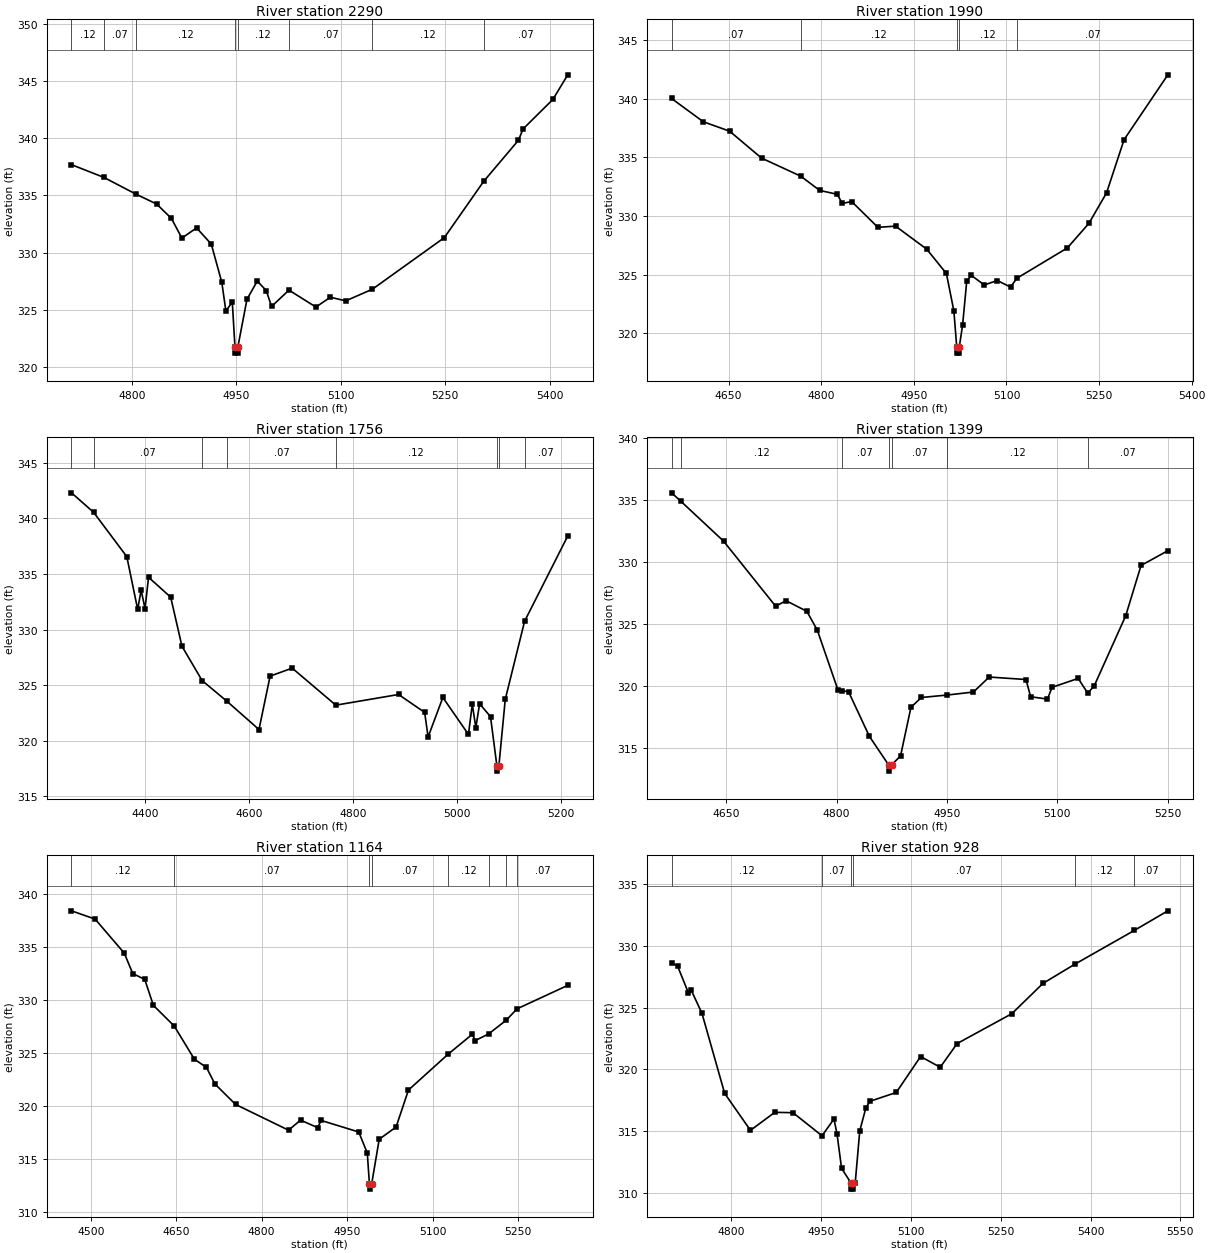
Type RM Length L Ch R = 1,2290,300,300,300
BEGIN DESCRIPTION:
Stream0260 4.0
END DESCRIPTION:
XS GIS Cut Line= 3
      2468788.25     13748840.18      2468559.26     13748990.20
      2468224.99     13749275.01
#Sta/Elev= 30
  4713.1  337.69  4759.5  336.58  4805.6  335.12  4835.5  334.25  4856.6  333.00
  4871.7  331.28  4892.8  332.17  4913.9  330.76  4929.0  327.43  4934.9  324.92
  4944.1  325.69  4948.0  321.74  4948.3  321.24  4951.8  321.24  4952.0  321.74
  4965.2  325.94  4980.0  327.53  4992.9  326.70  5000.5  325.31  5025.5  326.74
  5064.2  325.26  5085.0  326.12  5107.0  325.80  5145.4  326.82  5248.7  331.32
  5305.2  336.23  5355.2  339.82  5361.7  340.80  5404.6  343.38  5426.0  345.53
#Mann=8,-1,0
  4713.1    0.12       0  4759.5    0.07       0  4805.6    0.12       0
  4948.0    0.05       0  4952.0    0.12       0  5025.5    0.07       0
  5145.4    0.12       0  5305.2    0.07       0
Bank Sta=4948,4952
Exp/Cntr=0.3,0.1

Type RM Length L Ch R = 1,1990,234,234,234
BEGIN DESCRIPTION:
XS6294
END DESCRIPTION:
XS GIS Cut Line= 3
      2468782.29     13748571.73      2468405.28     13748808.60
      2468140.16     13749050.15
#Sta/Elev= 30
  4557.5  340.03  4609.0  338.04  4651.5  337.24  4703.3  334.94  4766.7  333.40
  4797.5  332.18  4825.9  331.85  4834.0  331.07  4849.3  331.23  4891.7  329.03
  4920.4  329.13  4970.7  327.17  5002.7  325.09  5014.8  321.89  5019.5  318.79
  5019.8  318.29  5023.3  318.29  5023.5  318.79  5029.0  320.71  5035.7  324.47
  5043.2  324.92  5064.1  324.11  5085.1  324.49  5106.7  323.93  5116.8  324.68
  5198.6  327.27  5233.7  329.38  5262.1  331.97  5290.5  336.51  5361.4  342.05
#Mann=5,-1,0
  4557.5    0.07       0  4766.7    0.12       0  5019.5    0.05       0
  5023.5    0.12       0  5116.8    0.07       0
Bank Sta=5019.5,5023.5
Exp/Cntr=0.3,0.1

Type RM Length L Ch R = 1,1756,357,357,357
BEGIN DESCRIPTION:
Stream0260 3.0
END DESCRIPTION:
XS GIS Cut Line= 3
      2468725.00     13748175.00      2468237.49     13748723.71
      2468075.01     13748874.99
#Sta/Elev= 30
  4257.6  342.29  4300.4  340.53  4364.2  336.55  4385.1  331.81  4391.8  333.54
  4399.3  331.87  4406.0  334.70  4448.7  332.91  4470.4  328.50  4509.3  325.41
  4557.3  323.54  4618.8  321.01  4640.2  325.81  4682.8  326.53  4766.8  323.20
  4887.7  324.16  4937.9  322.55  4944.6  320.34  4973.0  323.89  5022.3  320.57
  5029.7  323.28  5036.5  321.18  5043.8  323.32  5064.8  322.17  5077.0  317.77
  5077.3  317.27  5081.0  317.77  5093.2  323.72  5130.5  330.75  5213.6  338.41
#Mann=8,-1,0
  4257.6    0.12       0  4300.4    0.07       0  4509.3    0.12       0
  4557.3    0.07       0  4766.8    0.12       0  5077.0    0.05       0
  5081.0    0.12       0  5130.5    0.07       0
Bank Sta=5077,5081
Exp/Cntr=0.3,0.1

Type RM Length L Ch R = 1,1399,235,235,235
BEGIN DESCRIPTION:
Stream0260 2.0
END DESCRIPTION:
XS GIS Cut Line= 3
      2468474.97     13748125.03      2468175.00     13748425.00
      2467975.02     13748574.98
#Sta/Elev= 30
  4575.8  335.59  4588.6  334.90  4646.5  331.69  4717.2  326.44  4731.3  326.89
  4759.6  326.03  4773.8  324.51  4802.0  319.66  4807.3  319.62  4816.2  319.55
  4844.5  315.95  4870.7  313.64  4871.0  313.14  4874.7  313.64  4886.9  314.37
  4901.0  318.29  4915.2  319.08  4950.6  319.28  4985.9  319.52  5007.3  320.73
  5057.3  320.53  5063.6  319.14  5086.5  318.95  5092.7  319.90  5128.2  320.62
  5141.2  319.43  5150.0  320.02  5192.7  325.66  5213.6  329.73  5250.0  330.92
#Mann=7,-1,0
  4575.8    0.07       0  4588.6    0.12       0  4807.3    0.07       0
  4870.7    0.05       0  4874.7    0.07       0  4950.6    0.12       0
  5141.2    0.07       0
Bank Sta=4870.7,4874.7
Exp/Cntr=0.3,0.1

Type RM Length L Ch R = 1,1164,236,236,236
BEGIN DESCRIPTION:
XS6295
END DESCRIPTION:
XS GIS Cut Line= 3
      2468448.71     13747959.77      2468010.48     13748251.92
      2467933.49     13748587.52
#Sta/Elev= 30
  4466.2  338.41  4507.7  337.63  4558.8  334.43  4573.8  332.50  4594.8  331.95
  4609.9  329.51  4646.5  327.56  4682.0  324.43  4703.0  323.67  4718.0  322.10
  4754.1  320.18  4847.2  317.75  4868.2  318.70  4898.3  317.99  4904.3  318.67
  4970.4  317.58  4985.4  315.59  4989.1  312.70  4989.4  312.20  4993.1  312.70
  5006.3  316.90  5035.9  318.05  5057.6  321.53  5127.9  324.94  5169.6  326.78
  5174.8  326.19  5198.4  326.82  5229.0  328.10  5248.2  329.18  5337.2  331.39
#Mann=8,-1,0
  4466.2    0.12       0  4646.5    0.07       0  4989.1    0.05       0
  4993.1    0.07       0  5127.9    0.12       0  5198.4    0.07       0
  5229.0    0.12       0  5248.2    0.07       0
Bank Sta=4989.1,4993.1
Exp/Cntr=0.3,0.1

Type RM Length L Ch R = 1,928,289,289,289
BEGIN DESCRIPTION:
Stream0260 1.0
END DESCRIPTION:
XS GIS Cut Line= 3
      2467875.01     13747824.97      2467825.00     13748125.00
      2467917.47     13748641.41
#Sta/Elev= 30
  4700.3  328.63  4710.5  328.36  4728.2  326.23  4733.3  326.40  4751.0  324.56
  4789.0  318.06  4832.1  315.07  4872.7  316.53  4903.1  316.50  4951.6  314.63
  4971.5  315.99  4976.6  314.79  4984.2  312.00  4999.9  310.81  5000.2  310.31
  5003.7  310.31  5003.9  310.81  5007.0  310.81  5014.6  315.03  5024.8  316.89
  5031.4  317.42  5075.6  318.14  5116.2  321.05  5149.0  320.18  5177.2  322.10
  5268.6  324.52  5320.5  326.97  5373.9  328.53  5473.4  331.27  5529.1  332.85
#Mann=6,-1,0
  4700.3    0.12       0  4951.6    0.07       0  4999.9    0.05       0
  5003.9    0.07       0  5373.9    0.12       0  5473.4    0.07       0
Bank Sta=4999.9,5003.9
Exp/Cntr=0.3,0.1

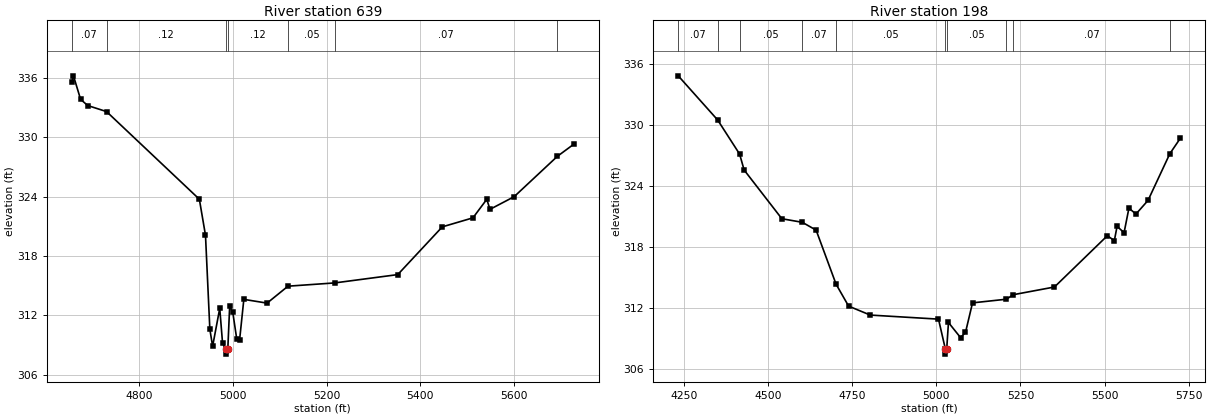
Type RM Length L Ch R = 1,639,441,441,441
BEGIN DESCRIPTION:
XS6284
END DESCRIPTION:
XS GIS Cut Line= 4
      2467964.41     13747708.99      2467617.16     13747930.76
      2467649.26     13748167.13      2467875.84     13748521.53
#Sta/Elev= 30
  4656.3  335.54  4659.9  336.19  4675.1  333.82  4690.3  333.19  4730.5  332.58
  4928.5  323.73  4941.6  320.09  4950.9  310.60  4956.8  308.88  4972.0  312.71
  4978.0  309.21  4985.2  308.59  4985.5  308.09  4989.2  308.59  4993.2  312.93
  4999.7  312.35  5008.4  309.58  5014.3  309.49  5023.4  313.62  5073.0  313.24
  5117.6  314.95  5217.3  315.28  5351.8  316.12  5446.8  320.94  5512.2  321.85
  5541.7  323.72  5548.6  322.71  5600.2  323.99  5692.3  328.06  5727.5  329.29
#Mann=7,-1,0
  4656.3    0.07       0  4730.5    0.12       0  4985.2    0.05       0
  4989.2    0.12       0  5117.6    0.05       0  5217.3    0.07       0
  5692.3    0.12       0
Bank Sta=4985.2,4989.2
Exp/Cntr=0.3,0.1

Type RM Length L Ch R = 1,198,0,0,0
BEGIN DESCRIPTION:
XS6283
END DESCRIPTION:
XS GIS Cut Line= 5
      2467961.53     13747685.64      2467386.63     13747869.49
      2467319.52     13747959.95      2467532.53     13748263.42
      2467850.34     13748514.16
#Sta/Elev= 30
  4233.1  334.83  4350.2  330.49  4415.4  327.14  4428.9  325.57  4541.0  320.78
  4601.7  320.43  4642.8  319.66  4702.0  314.35  4739.3  312.19  4803.6  311.31
  5006.4  310.91  5026.8  307.97  5027.0  307.47  5030.8  307.97  5036.0  310.58
  5071.8  309.10  5086.6  309.60  5107.5  312.51  5208.4  312.87  5228.2  313.31
  5351.0  314.07  5508.1  319.11  5528.9  318.63  5537.0  320.03  5557.8  319.41
  5572.2  321.82  5593.1  321.24  5628.9  322.58  5693.7  327.17  5724.9  328.69
#Mann=10,-1,0
  4233.1    0.07       0  4350.2    0.12       0  4415.4    0.05       0
  4601.7    0.07       0  4702.0    0.05       0  5026.8    0.05       0
  5030.8    0.05       0  5208.4    0.12       0  5228.2    0.07       0
  5693.7    0.12       0
Bank Sta=5026.8,5030.8
Exp/Cntr=0.3,0.1

Chan Stop Cuts=-1