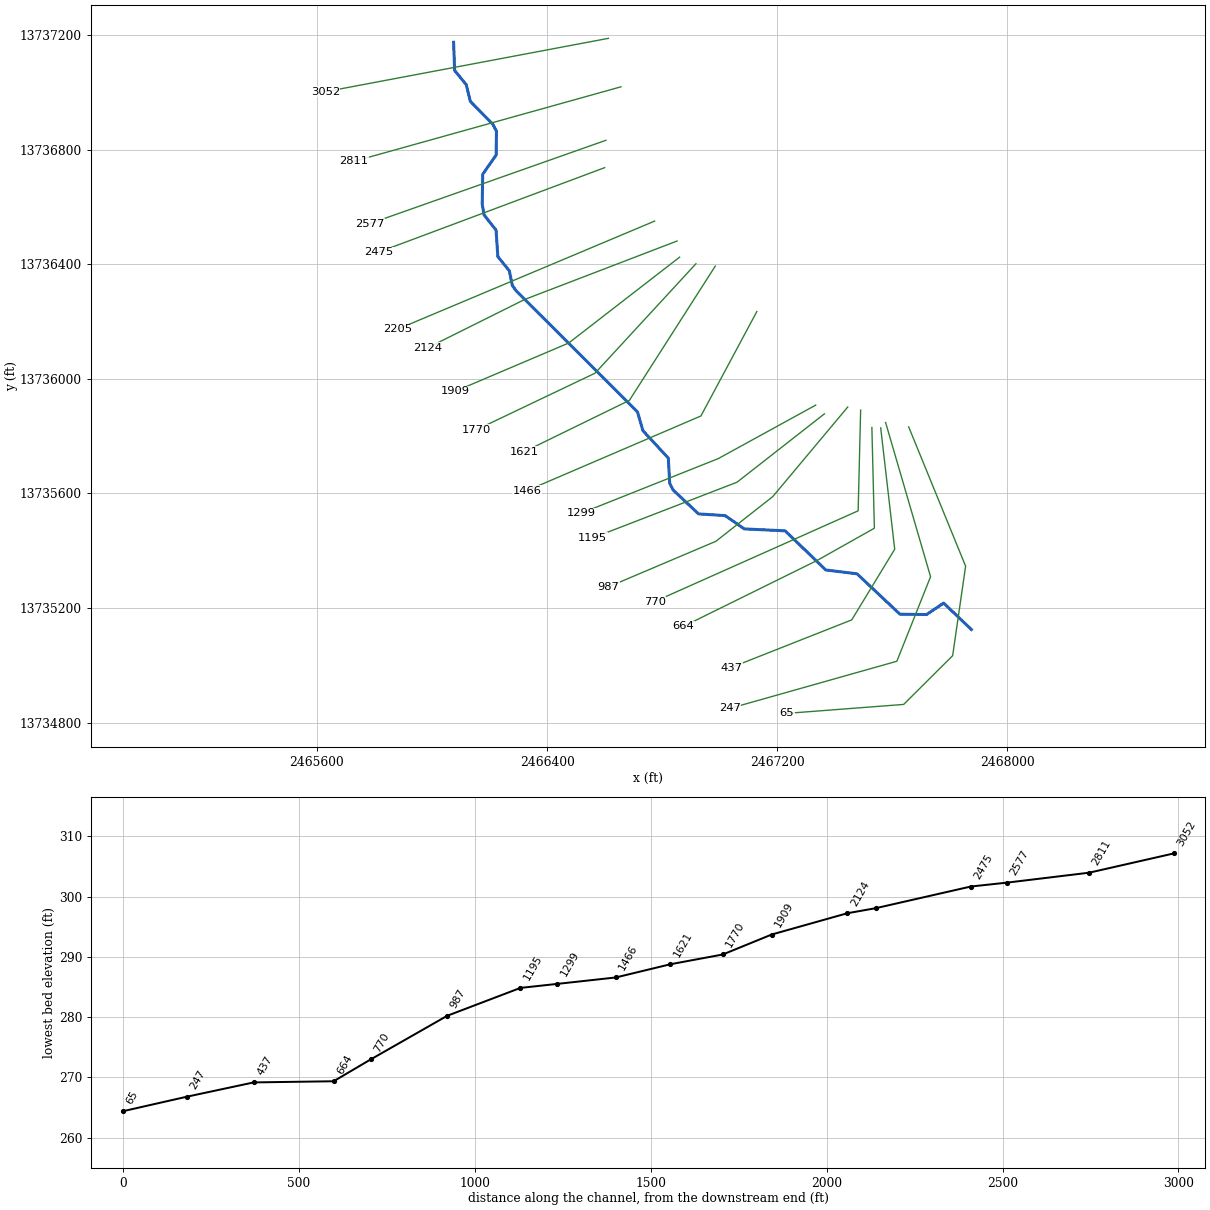
--- Stream0263.prj (project) ---

Proj Title=Stream0263 Base Level Engineering
Current Plan=p01
Default Exp/Contr=0.3,0.1
English Units
Geom File=g01
Flow File=f01
Plan File=p01
BEGIN DESCRIPTION:
Stream0263
END DESCRIPTION:

--- Stream0263.p01 (plan) ---

Plan Title=Multiple Run
Short Identifier=Multiple
Geom File=g01
Flow File=f01
Subcritical Flow
K Sum by GR= 0
Std Step Tol= 0.01
Critical Tol= 0.01
Num of Std Step Trials= 20
Max Error Tol= 0.3
Flow Tol Ratio= 0.001
Split Flow NTrial= 30
Split Flow Tol= 0.02
Split Flow Ratio= 0.02
Log Output Level= 0
Friction Slope Method= 1
Unsteady Friction Slope Method= 2
Unsteady Bridges Friction Slope Method= 1
Parabolic Critical Depth
Global Vel Dist=  1 , 1 , 1
Global Log Level= 0
CheckData=True
Encroach Param= -1, 0, 0, 0
BEGIN DESCRIPTION:
Multiple Run
END DESCRIPTION:

--- Stream0263.f01 (steady flow) ---

Flow Title=Multiple
Number of Profiles=7
Profile Names=10-year,25-year,50-year,1pct_min,100-year,1pct_plu,500-year
River Rch & RM= Stream0263,Reach-1,3052
     259     395     512     323     644    1285    1007
Boundary for River Rch & Prof#=Stream0263,Reach-1,1
Up Type=0
Dn Type=3
Dn Slope=0.005
Boundary for River Rch & Prof#=Stream0263,Reach-1,2
Up Type=0
Dn Type=3
Dn Slope=0.005
Boundary for River Rch & Prof#=Stream0263,Reach-1,3
Up Type=0
Dn Type=3
Dn Slope=0.005
Boundary for River Rch & Prof#=Stream0263,Reach-1,4
Up Type=0
Dn Type=3
Dn Slope=0.005
Boundary for River Rch & Prof#=Stream0263,Reach-1,5
Up Type=0
Dn Type=3
Dn Slope=0.005
Boundary for River Rch & Prof#=Stream0263,Reach-1,6
Up Type=0
Dn Type=3
Dn Slope=0.005
Boundary for River Rch & Prof#=Stream0263,Reach-1,7
Up Type=0
Dn Type=3
Dn Slope=0.005

--- Stream0263.g01 (geometry) ---

Geom Title=Existing Conditions

River Reach=Stream0263,Reach-1
Reach XY= 30
      2466075.00     13737175.00      2466078.63     13737076.50
      2466118.89     13737027.18      2466133.16     13736968.95
      2466211.64     13736888.29      2466224.06     13736864.52
      2466222.84     13736780.98      2466176.21     13736714.49
      2466174.53     13736609.84      2466180.74     13736572.67
      2466222.64     13736519.02      2466228.82     13736426.58
      2466268.86     13736377.17      2466278.94     13736326.63
      2466291.64     13736308.32      2466714.22     13735884.68
      2466733.18     13735818.96      2466821.37     13735723.50
      2466826.16     13735635.48      2466838.39     13735611.67
      2466926.48     13735528.61      2467019.02     13735522.64
      2467085.51     13735476.23      2467227.45     13735469.53
      2467368.83     13735332.86      2467477.43     13735319.48
      2467626.50     13735178.46      2467719.11     13735177.36
      2467778.42     13735217.32      2467875.00     13735125.00

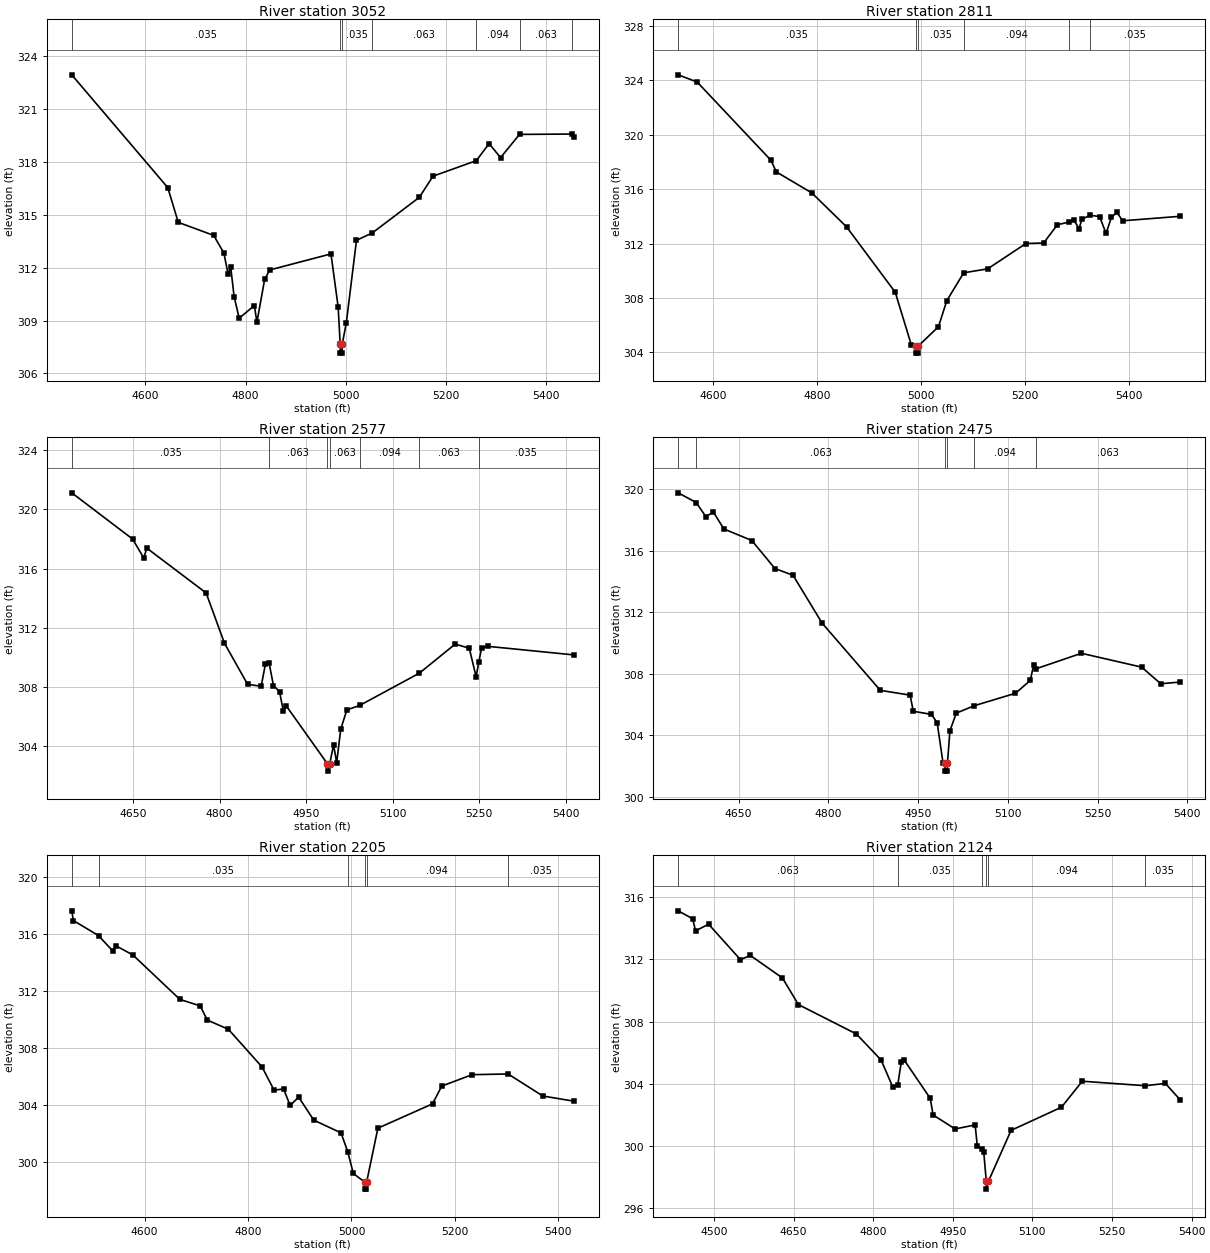
Type RM Length L Ch R = 1,3052,241,241,241
BEGIN DESCRIPTION:
XS6304
END DESCRIPTION:
XS GIS Cut Line= 2
      2466613.21     13737188.72      2465629.01     13737002.28
#Sta/Elev= 30
  4453.0  322.94  4644.6  316.54  4665.5  314.57  4736.2  313.83  4756.5  312.83
  4765.0  311.62  4770.1  312.04  4776.9  310.36  4787.0  309.13  4817.4  309.85
  4822.4  308.90  4837.9  311.34  4848.1  311.87  4970.2  312.78  4984.5  309.77
  4988.6  307.65  4988.9  307.15  4992.4  307.15  4992.6  307.65  5000.8  308.87
  5021.1  313.55  5052.7  313.97  5146.5  315.99  5173.8  317.19  5260.2  318.07
  5285.8  319.04  5308.5  318.24  5346.4  319.56  5451.3  319.58  5454.7  319.41
#Mann=7,-1,0
  4453.0   0.035       0  4988.6   0.035       0  4992.6   0.035       0
  5052.7   0.063       0  5260.2   0.094       0  5346.4   0.063       0
  5451.3   0.094       0
Bank Sta=4988.6,4992.6
Exp/Cntr=0.3,0.1

Type RM Length L Ch R = 1,2811,234,234,234
BEGIN DESCRIPTION:
XS6305
END DESCRIPTION:
XS GIS Cut Line= 2
      2466656.58     13737019.44      2465727.79     13736759.03
#Sta/Elev= 30
  4533.1  324.39  4569.6  323.86  4711.2  318.12  4721.7  317.26  4789.8  315.72
  4856.7  313.22  4950.2  308.42  4981.3  304.52  4989.7  304.45  4990.0  303.95
  4993.5  303.95  4993.7  304.45  5033.2  305.89  5049.2  307.80  5081.7  309.85
  5127.8  310.14  5201.2  312.00  5235.3  312.04  5261.7  313.38  5284.6  313.58
  5292.9  313.75  5303.3  313.09  5308.7  313.77  5324.1  314.08  5342.8  313.98
  5355.2  312.74  5365.6  313.93  5376.0  314.28  5387.3  313.67  5497.7  314.00
#Mann=6,-1,0
  4533.1   0.035       0  4989.7   0.035       0  4993.7   0.035       0
  5081.7   0.094       0  5284.6   0.063       0  5324.1   0.035       0
Bank Sta=4989.7,4993.7
Exp/Cntr=0.3,0.1

Type RM Length L Ch R = 1,2577,102,102,102
BEGIN DESCRIPTION:
XS6303
END DESCRIPTION:
XS GIS Cut Line= 2
      2466604.53     13736832.82      2465784.25     13736542.03
#Sta/Elev= 30
  4543.8  321.12  4649.4  317.99  4668.6  316.71  4673.9  317.38  4776.7  314.35
  4808.5  310.95  4848.6  308.17  4872.2  308.04  4879.5  309.54  4886.0  309.59
  4893.4  308.09  4904.0  307.68  4910.4  306.39  4915.7  306.71  4986.9  302.80
  4987.2  302.30  4990.9  302.80  4997.7  304.07  5003.0  302.87  5010.1  305.14
  5020.7  306.44  5042.8  306.74  5146.2  308.92  5208.5  310.89  5232.9  310.61
  5244.7  308.69  5249.6  309.70  5254.2  310.64  5264.8  310.74  5414.1  310.16
#Mann=7,-1,0
  4543.8   0.035       0  4886.0   0.063       0  4986.9    0.05       0
  4990.9   0.063       0  5042.8   0.094       0  5146.2   0.063       0
  5249.6   0.035       0
Bank Sta=4986.9,4990.9
Exp/Cntr=0.3,0.1

Type RM Length L Ch R = 1,2475,270,270,270
BEGIN DESCRIPTION:
XS6302
END DESCRIPTION:
XS GIS Cut Line= 2
      2466600.21     13736737.34      2465814.62     13736442.20
#Sta/Elev= 30
  4549.0  319.75  4579.1  319.12  4595.1  318.21  4608.0  318.49  4625.4  317.40
  4672.1  316.65  4710.7  314.83  4741.0  314.39  4789.6  311.28  4886.9  306.91
  4936.7  306.60  4942.0  305.55  4972.2  305.35  4981.9  304.81  4991.8  302.17
  4995.1  302.16  4995.4  301.66  4998.9  301.66  4999.1  302.16  5003.2  304.28
  5013.9  305.43  5043.7  305.91  5112.8  306.72  5137.7  307.56  5143.0  308.55
  5147.7  308.32  5223.0  309.32  5323.7  308.42  5355.7  307.34  5388.2  307.45
#Mann=6,-1,0
  4549.0   0.035       0  4579.1   0.063       0  4995.1    0.05       0
  4999.1   0.063       0  5043.7   0.094       0  5147.7   0.063       0
Bank Sta=4995.1,4999.1
Exp/Cntr=0.3,0.1

Type RM Length L Ch R = 1,2205,81,81,81
BEGIN DESCRIPTION:
XS6301
END DESCRIPTION:
XS GIS Cut Line= 2
      2466773.81     13736550.71      2465879.87     13736173.17
#Sta/Elev= 30
  4459.4  317.62  4462.4  316.94  4511.1  315.88  4538.9  314.79  4545.0  315.16
  4577.5  314.52  4668.3  311.40  4707.8  310.94  4721.2  309.95  4762.1  309.30
  4827.2  306.65  4850.5  305.02  4868.8  305.11  4881.5  303.95  4898.0  304.53
  4927.1  302.92  4979.9  302.02  4993.0  300.68  5003.6  299.17  5025.4  298.57
  5025.6  298.07  5029.1  298.07  5029.4  298.57  5051.1  302.35  5156.7  304.06
  5174.6  305.31  5233.3  306.11  5302.8  306.16  5370.0  304.61  5429.8  304.25
#Mann=6,-1,0
  4459.4   0.063       0  4511.1   0.035       0  4993.0   0.094       0
  5025.4    0.05       0  5029.4   0.094       0  5302.8   0.035       0
Bank Sta=5025.4,5029.4
Exp/Cntr=0.3,0.1

Type RM Length L Ch R = 1,2124,215,215,215
BEGIN DESCRIPTION:
XS6300
END DESCRIPTION:
XS GIS Cut Line= 3
      2466851.87     13736481.24      2466322.40     13736277.26
      2465983.86     13736107.99
#Sta/Elev= 30
  4432.6  315.13  4459.9  314.62  4465.3  313.84  4489.9  314.27  4549.9  311.99
  4568.6  312.26  4629.1  310.81  4659.1  309.10  4768.3  307.21  4815.0  305.53
  4836.5  303.83  4846.4  303.95  4852.9  305.40  4858.3  305.54  4907.5  303.07
  4912.9  302.00  4954.4  301.10  4992.1  301.36  4996.2  299.99  5004.5  299.79
  5008.3  299.62  5013.1  297.73  5013.3  297.23  5017.1  297.73  5059.8  301.01
  5154.8  302.50  5193.9  304.17  5312.8  303.88  5350.5  304.03  5378.5  302.97
#Mann=6,-1,0
  4432.6   0.063       0  4846.4   0.035       0  5004.5   0.094       0
  5013.1   0.035       0  5017.1   0.094       0  5312.8   0.035       0
Bank Sta=5013.1,5017.1
Exp/Cntr=0.3,0.1

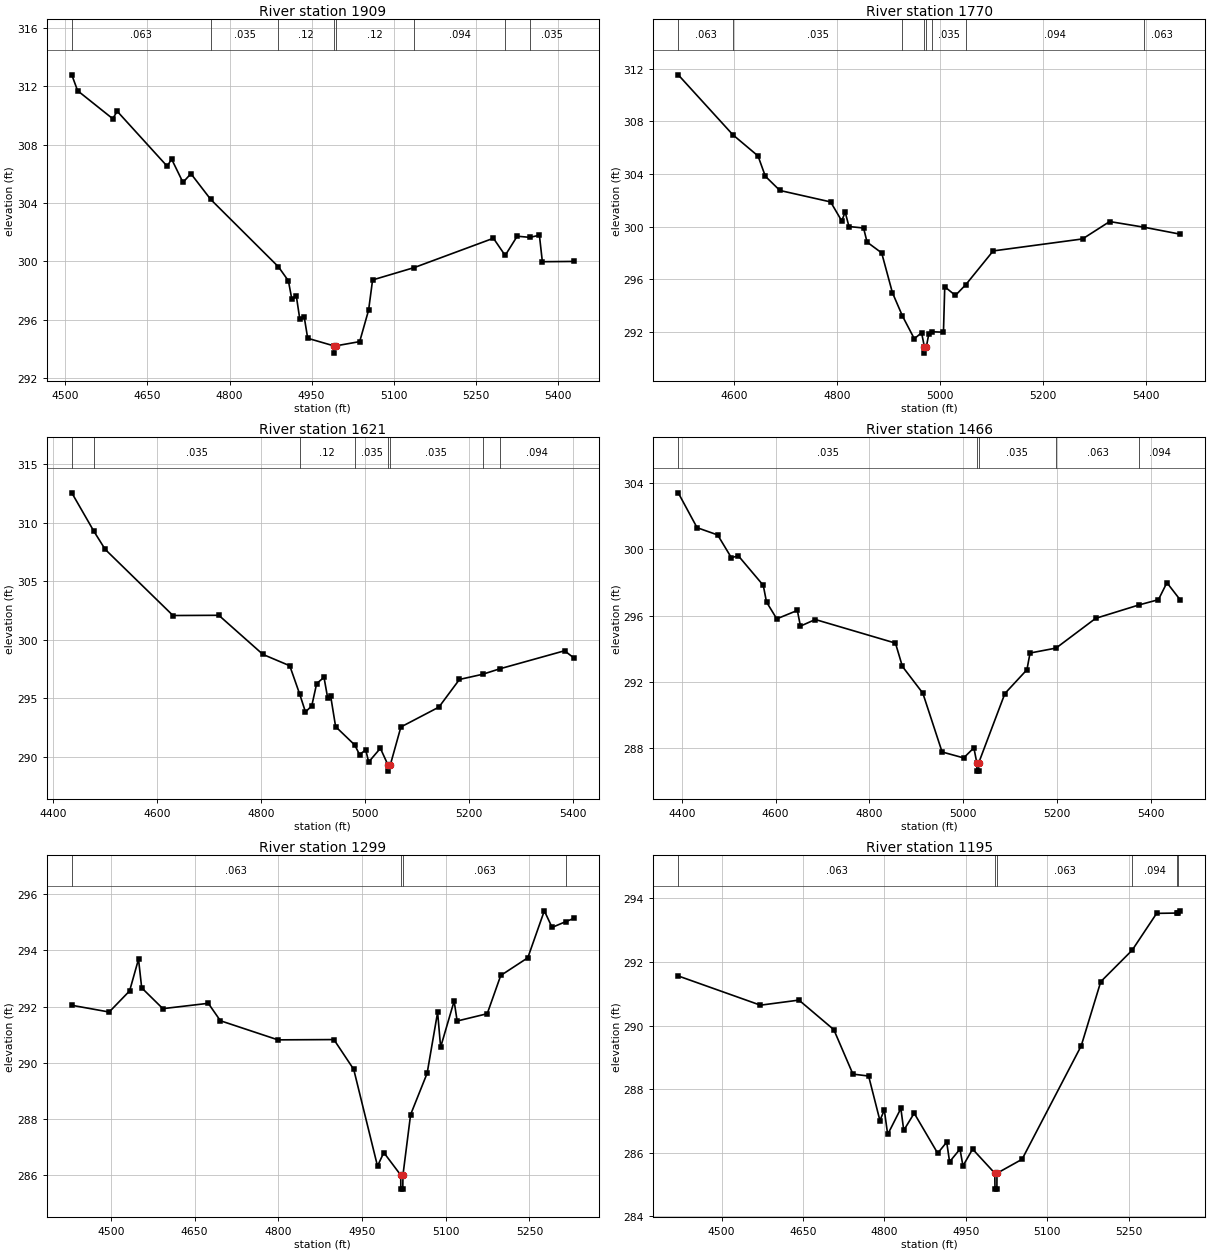
Type RM Length L Ch R = 1,1909,139,139,139
BEGIN DESCRIPTION:
Stream0263 4.0
END DESCRIPTION:
XS GIS Cut Line= 3
      2466860.63     13736424.85      2466475.00     13736125.00
      2466079.71     13735956.23
#Sta/Elev= 30
  4511.5  312.79  4522.2  311.70  4586.4  309.78  4594.6  310.29  4686.0  306.52
  4694.1  307.01  4714.9  305.41  4729.4  306.01  4765.7  304.24  4889.5  299.62
  4907.7  298.66  4914.0  297.40  4922.2  297.62  4928.5  296.05  4936.6  296.19
  4943.0  294.72  4990.7  294.20  4991.0  293.70  4994.7  294.20  5038.1  294.49
  5054.4  296.65  5061.7  298.72  5138.0  299.57  5282.7  301.58  5304.2  300.40
  5326.2  301.72  5349.5  301.64  5366.8  301.79  5372.2  299.97  5429.8  299.99
#Mann=8,-1,0
  4511.5   0.063       0  4765.7   0.035       0  4889.5    0.12       0
  4990.7    0.05       0  4994.7    0.12       0  5138.0   0.094       0
  5304.2   0.063       0  5349.5   0.035       0
Bank Sta=4990.7,4994.7
Exp/Cntr=0.3,0.1

Type RM Length L Ch R = 1,1770,149,149,149
BEGIN DESCRIPTION:
E20859
END DESCRIPTION:
XS GIS Cut Line= 3
      2466917.33     13736401.72      2466566.66     13736019.79
      2466153.50     13735821.90
#Sta/Elev= 30
  4491.1  311.52  4597.3  306.97  4646.3  305.36  4660.5  303.82  4688.8  302.74
  4787.5  301.87  4809.1  300.43  4815.8  301.10  4823.2  300.00  4851.6  299.89
  4858.4  298.82  4886.8  298.00  4907.7  294.98  4927.2  293.21  4950.3  291.48
  4964.4  291.94  4969.8  290.89  4970.1  290.39  4973.8  290.89  4978.6  291.87
  4985.0  292.01  5007.0  291.98  5009.5  295.43  5030.2  294.77  5050.5  295.59
  5103.7  298.15  5277.5  299.06  5330.3  300.38  5397.0  299.95  5467.7  299.42
#Mann=8,-1,0
  4491.1   0.063       0  4597.3   0.035       0  4927.2    0.12       0
  4969.8   0.035       0  4973.8    0.12       0  4985.0   0.035       0
  5050.5   0.094       0  5397.0   0.063       0
Bank Sta=4969.8,4973.8
Exp/Cntr=0.3,0.1

Type RM Length L Ch R = 1,1621,155,155,155
BEGIN DESCRIPTION:
Stream0263 3.0
END DESCRIPTION:
XS GIS Cut Line= 3
      2466984.71     13736393.73      2466686.11     13735925.00
      2466319.06     13735744.94
#Sta/Elev= 30
  4436.2  312.54  4478.9  309.24  4500.4  307.71  4630.7  302.06  4718.7  302.08
  4803.4  298.74  4855.0  297.77  4874.3  295.32  4885.2  293.82  4897.3  294.35
  4906.7  296.25  4920.8  296.78  4927.8  295.03  4933.7  295.15  4943.1  292.57
  4979.9  291.00  4989.0  290.19  5001.0  290.58  5006.6  289.55  5029.1  290.72
  5044.0  289.27  5044.3  288.77  5048.0  289.27  5068.5  292.54  5141.6  294.24
  5181.0  296.60  5225.4  297.04  5258.6  297.51  5383.0  299.05  5400.8  298.44
#Mann=8,-1,0
  4436.2   0.063       0  4478.9   0.035       0  4874.3    0.12       0
  4979.9   0.035       0  5044.0   0.035       0  5048.0   0.035       0
  5225.4   0.063       0  5258.6   0.094       0
Bank Sta=5044,5048
Exp/Cntr=0.3,0.1

Type RM Length L Ch R = 1,1466,167,167,167
BEGIN DESCRIPTION:
E20858
END DESCRIPTION:
XS GIS Cut Line= 3
      2467129.16     13736235.07      2466934.71     13735870.49
      2466330.54     13735610.07
#Sta/Elev= 30
  4392.3  303.43  4432.5  301.32  4476.4  300.88  4505.7  299.50  4520.4  299.62
  4573.7  297.83  4580.6  296.82  4602.5  295.80  4646.4  296.31  4653.0  295.36
  4684.7  295.76  4855.7  294.33  4870.5  292.92  4914.1  291.30  4955.2  287.74
  5001.2  287.38  5023.0  287.99  5029.3  287.08  5029.5  286.58  5033.0  286.58
  5033.3  287.08  5089.2  291.28  5136.2  292.72  5142.8  293.73  5198.3  294.03
  5282.8  295.83  5375.0  296.64  5416.7  296.96  5434.8  297.99  5463.4  296.94
#Mann=5,-1,0
  4392.3   0.035       0  5029.3   0.035       0  5033.3   0.035       0
  5198.3   0.063       0  5375.0   0.094       0
Bank Sta=5029.3,5033.3
Exp/Cntr=0.3,0.1

Type RM Length L Ch R = 1,1299,104,104,104
BEGIN DESCRIPTION:
XS6299
END DESCRIPTION:
XS GIS Cut Line= 3
      2467333.69     13735908.34      2466995.14     13735721.70
      2466518.82     13735531.17
#Sta/Elev= 30
  4430.0  292.05  4497.0  291.81  4533.6  292.56  4549.6  293.69  4555.3  292.67
  4593.2  291.93  4674.6  292.12  4696.3  291.50  4799.5  290.82  4899.7  290.83
  4935.2  289.77  4977.8  286.33  4989.1  286.81  5019.4  286.01  5019.6  285.51
  5023.1  285.51  5023.4  286.01  5037.1  288.16  5066.7  289.63  5085.5  291.80
  5090.9  290.56  5115.1  292.20  5120.5  291.49  5174.4  291.75  5198.6  293.11
  5247.1  293.74  5276.7  295.41  5290.6  294.82  5315.6  295.03  5329.6  295.14
#Mann=4,-1,0
  4430.0   0.063       0  5019.4    0.05       0  5023.4   0.063       0
  5315.6   0.094       0
Bank Sta=5019.4,5023.4
Exp/Cntr=0.3,0.1

Type RM Length L Ch R = 1,1195,208,208,208
BEGIN DESCRIPTION:
XS6298
END DESCRIPTION:
XS GIS Cut Line= 3
      2467364.03     13735877.93      2467060.24     13735639.24
      2466558.43     13735444.57
#Sta/Elev= 30
  4420.3  291.56  4571.7  290.64  4642.6  290.80  4706.8  289.87  4742.0  288.47
  4770.9  288.41  4791.7  287.01  4799.8  287.34  4806.0  286.57  4830.3  287.39
  4835.6  286.70  4854.8  287.24  4898.1  285.98  4914.7  286.33  4920.0  285.71
  4939.2  286.11  4944.6  285.58  4962.4  286.11  5003.3  285.35  5003.6  284.85
  5007.1  284.85  5007.3  285.35  5053.5  285.79  5162.4  289.36  5198.4  291.38
  5256.2  292.37  5301.3  293.53  5339.1  293.54  5340.2  293.55  5344.9  293.61
#Mann=6,-1,0
  4420.3   0.063       0  5003.3    0.05       0  5007.3   0.063       0
  5256.2   0.094       0  5339.1   0.035       0  5340.2   0.063       0
Bank Sta=5003.3,5007.3
Exp/Cntr=0.3,0.1

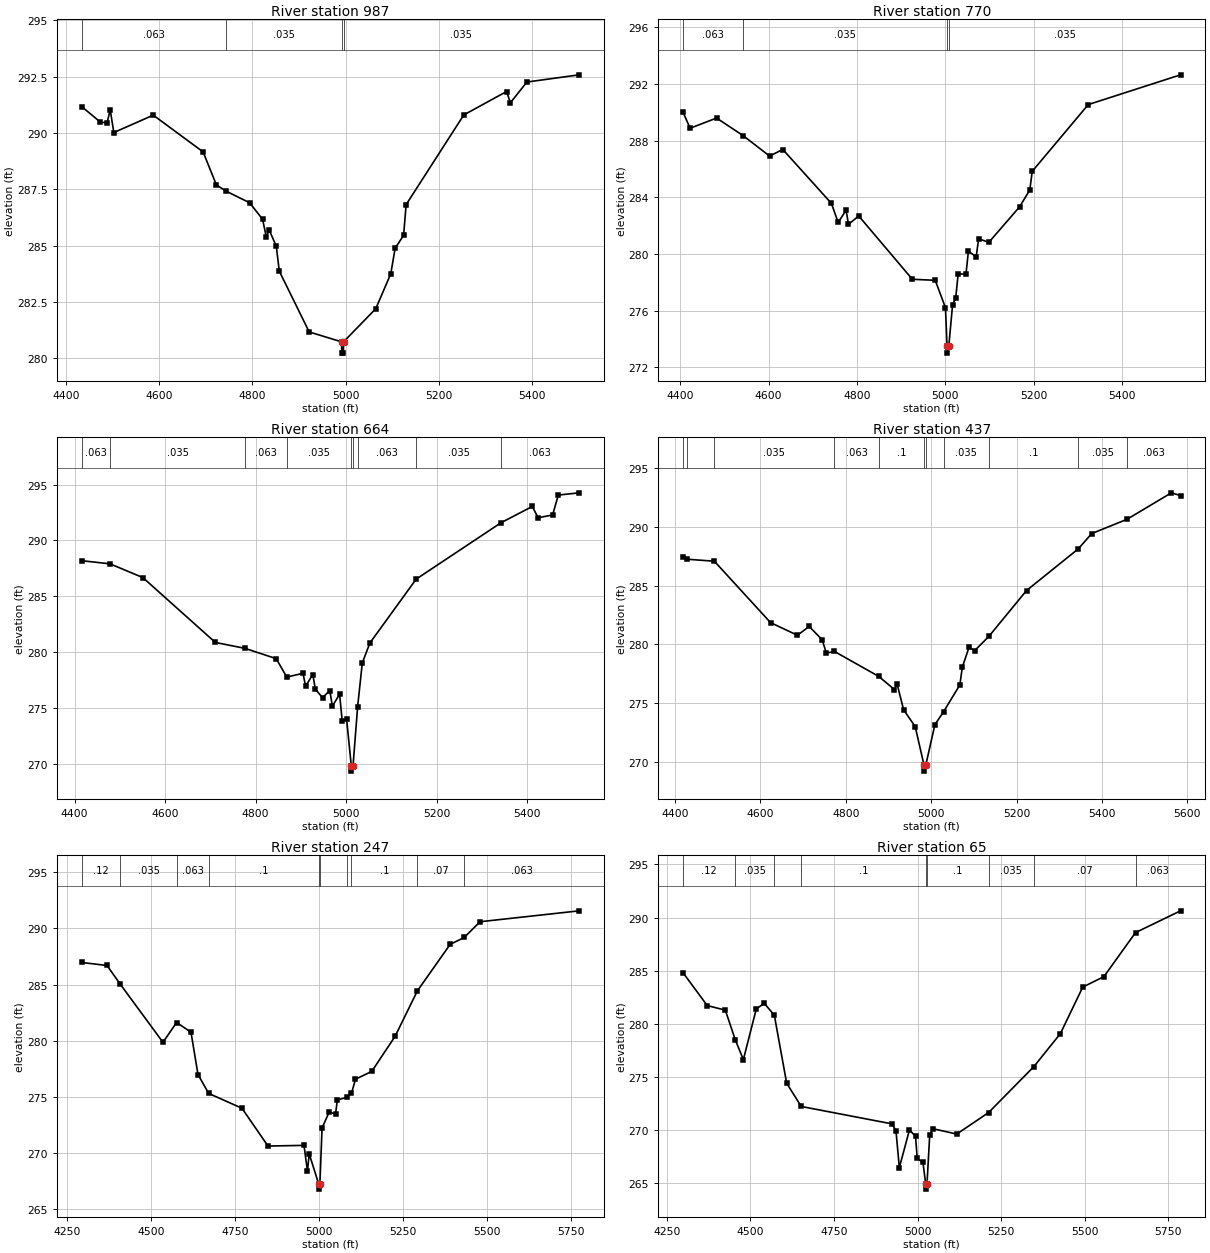
Type RM Length L Ch R = 1,987,217,217,217
BEGIN DESCRIPTION:
E20857
END DESCRIPTION:
XS GIS Cut Line= 4
      2467445.12     13735901.73      2467184.71     13735589.24
      2466986.79     13735432.99      2466611.82     13735273.28
#Sta/Elev= 30
  4434.1  291.17  4474.4  290.48  4488.7  290.45  4495.2  291.04  4503.0  290.02
  4587.6  290.79  4694.4  289.16  4723.0  287.69  4744.5  287.41  4794.3  286.90
  4821.9  286.17  4829.7  285.40  4836.2  285.69  4851.3  284.97  4857.7  283.87
  4921.8  281.17  4991.4  280.73  4991.6  280.23  4995.1  280.23  4995.4  280.73
  5064.5  282.20  5096.7  283.75  5106.0  284.88  5124.2  285.46  5129.6  286.82
  5253.2  290.80  5345.0  291.84  5353.1  291.34  5388.5  292.26  5500.6  292.58
#Mann=4,-1,0
  4434.1   0.063       0  4744.5   0.035       0  4991.4   0.035       0
  4995.4   0.035       0
Bank Sta=4991.4,4995.4
Exp/Cntr=0.3,0.1

Type RM Length L Ch R = 1,770,106,106,106
BEGIN DESCRIPTION:
Stream0263 2.0
END DESCRIPTION:
XS GIS Cut Line= 3
      2467489.93     13735890.99      2467481.25     13735539.41
      2466773.75     13735222.55
#Sta/Elev= 30
  4406.1  290.02  4422.1  288.88  4482.1  289.60  4542.2  288.36  4602.1  286.92
  4632.2  287.38  4742.2  283.58  4757.5  282.23  4775.5  283.10  4780.9  282.10
  4804.1  282.69  4925.6  278.22  4977.4  278.15  5000.6  276.21  5004.1  273.51
  5004.3  273.01  5008.1  273.51  5016.6  276.40  5023.8  276.92  5029.3  278.60
  5047.0  278.59  5052.5  280.19  5070.2  279.82  5075.7  281.08  5098.8  280.83
  5168.4  283.33  5191.6  284.53  5197.1  285.84  5324.0  290.55  5533.0  292.65
#Mann=4,-1,0
  4406.1   0.063       0  4542.2   0.035       0  5004.1   0.035       0
  5008.1   0.035       0
Bank Sta=5004.1,5008.1
Exp/Cntr=0.3,0.1

Type RM Length L Ch R = 1,664,227,227,227
BEGIN DESCRIPTION:
Stream0263 1.0
END DESCRIPTION:
XS GIS Cut Line= 4
      2467528.99     13735830.17      2467537.67     13735478.65
      2467338.02     13735365.80      2466873.64     13735135.78
#Sta/Elev= 30
  4415.8  288.19  4478.4  287.91  4551.0  286.68  4711.1  280.88  4776.5  280.35
  4845.6  279.43  4868.9  277.78  4904.8  278.12  4910.5  276.96  4926.4  278.01
  4932.2  276.68  4948.1  275.94  4964.0  276.58  4969.7  275.18  4985.6  276.24
  4991.4  273.86  5001.2  274.00  5011.4  269.87  5011.6  269.37  5015.4  269.87
  5025.5  275.14  5035.8  279.05  5052.6  280.83  5154.8  286.54  5342.1  291.58
  5411.4  293.04  5424.2  292.03  5456.3  292.28  5468.8  294.06  5515.0  294.26
#Mann=9,-1,0
  4415.8   0.063       0  4478.4   0.035       0  4776.5   0.063       0
  4868.9   0.035       0  5011.4   0.035       0  5015.4   0.035       0
  5025.5   0.063       0  5154.8   0.035       0  5342.1   0.063       0
Bank Sta=5011.4,5015.4
Exp/Cntr=0.3,0.1

Type RM Length L Ch R = 1,437,190,190,190
BEGIN DESCRIPTION:
E20856
END DESCRIPTION:
XS GIS Cut Line= 4
      2467559.71     13735828.80      2467608.32     13735405.21
      2467459.02     13735158.68      2467039.41     13734992.23
#Sta/Elev= 30
  4418.4  287.43  4428.5  287.24  4491.9  287.07  4623.5  281.84  4686.5  280.76
  4714.1  281.51  4744.3  280.39  4754.4  279.24  4773.3  279.38  4877.2  277.25
  4914.0  276.13  4919.9  276.64  4935.4  274.41  4962.6  272.97  4983.3  269.68
  4983.6  269.18  4987.3  269.68  5008.7  273.14  5029.3  274.26  5067.1  276.52
  5073.1  278.05  5088.6  279.72  5102.2  279.46  5135.1  280.66  5223.4  284.57
  5344.6  288.12  5376.4  289.43  5458.8  290.64  5562.8  292.90  5584.4  292.67
#Mann=11,-1,0
  4418.4   0.063       0  4428.5    0.12       0  4491.9   0.035       0
  4773.3   0.063       0  4877.2     0.1       0  4983.3    0.05       0
  4987.3     0.1       0  5029.3   0.035       0  5135.1     0.1       0
  5344.6   0.035       0  5458.8   0.063       0
Bank Sta=4983.3,4987.3
Exp/Cntr=0.3,0.1

Type RM Length L Ch R = 1,247,182,182,182
BEGIN DESCRIPTION:
XS6297
END DESCRIPTION:
XS GIS Cut Line= 4
      2467576.74     13735847.54      2467732.99     13735309.38
      2467615.80     13735014.24      2467035.42     13734849.65
#Sta/Elev= 30
  4294.2  286.96  4369.7  286.69  4409.5  285.01  4536.3  279.86  4576.7  281.62
  4619.6  280.77  4640.5  277.00  4672.3  275.32  4771.4  274.00  4848.9  270.64
  4956.1  270.70  4966.3  268.43  4971.7  269.94  4999.4  267.31  4999.6  266.81
  5003.4  267.31  5009.9  272.25  5031.4  273.68  5050.0  273.48  5055.4  274.74
  5082.7  274.96  5097.5  275.33  5109.4  276.58  5158.0  277.28  5227.2  280.39
  5293.8  284.44  5391.3  288.57  5433.1  289.18  5480.2  290.58  5775.4  291.55
#Mann=10,-1,0
  4294.2    0.12       0  4409.5   0.035       0  4576.7   0.063       0
  4672.3     0.1       0  4999.4    0.05       0  5003.4     0.1       0
  5082.7   0.035       0  5097.5     0.1       0  5293.8    0.07       0
  5433.1   0.063       0
Bank Sta=4999.4,5003.4
Exp/Cntr=0.3,0.1

Type RM Length L Ch R = 1,65,0,0,0
BEGIN DESCRIPTION:
E20855
END DESCRIPTION:
XS GIS Cut Line= 5
      2467656.94     13735832.29      2467854.85     13735346.18
      2467809.71     13735033.68      2467639.57     13734863.54
      2467233.28     13734832.29
#Sta/Elev= 30
  4298.2  284.80  4370.8  281.70  4424.8  281.27  4455.0  278.44  4478.8  276.61
  4517.5  281.39  4541.6  281.91  4571.5  280.78  4608.4  274.38  4652.0  272.19
  4923.6  270.55  4935.4  269.90  4945.5  266.43  4975.8  269.98  4993.9  269.38
  4999.0  267.29  5016.2  266.91  5024.3  264.90  5024.6  264.40  5028.3  264.90
  5036.4  269.51  5046.5  270.09  5117.3  269.59  5212.7  271.62  5348.1  275.95
  5427.4  279.06  5494.3  283.44  5557.7  284.43  5652.2  288.58  5786.9  290.63
#Mann=9,-1,0
  4298.2    0.12       0  4455.0   0.035       0  4571.5   0.063       0
  4652.0     0.1       0  5024.3    0.05       0  5028.3     0.1       0
  5212.7   0.035       0  5348.1    0.07       0  5652.2   0.063       0
Bank Sta=5024.3,5028.3
Exp/Cntr=0.3,0.1

Chan Stop Cuts=-1