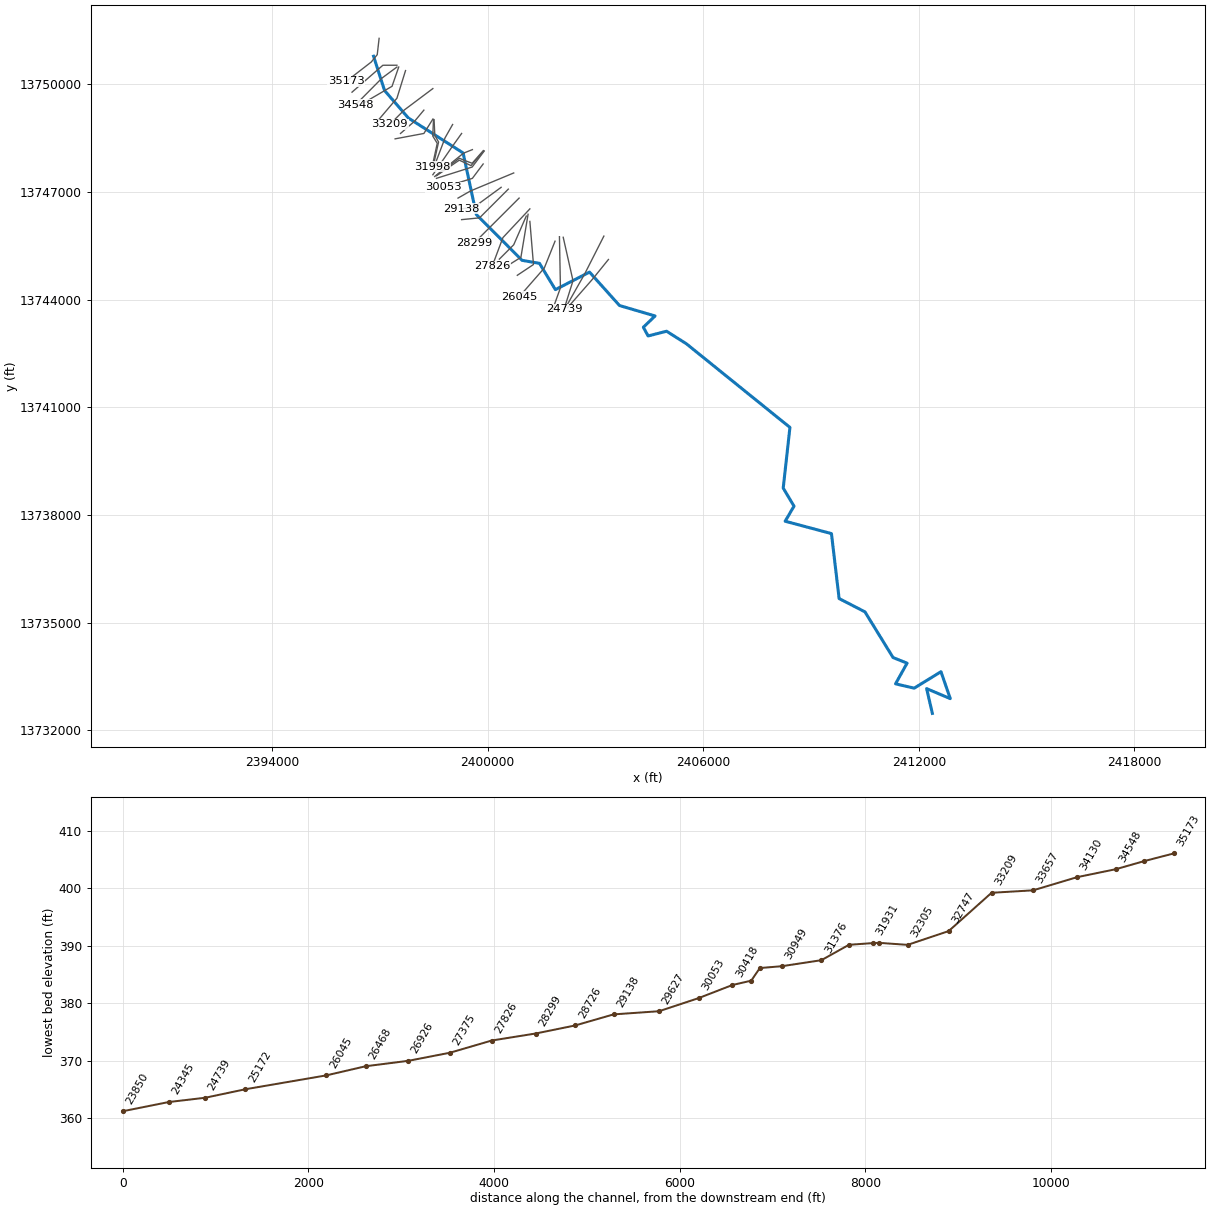
--- Stream0278.prj (project) ---

Proj Title=Stream0278 Base Level Engineering
Current Plan=p01
Default Exp/Contr=0.3,0.1
English Units
Geom File=g01
Flow File=f01
Plan File=p01
Y Axis Title=Elevation
X Axis Title(PF)=Main Channel Distance
X Axis Title(XS)=Station
BEGIN DESCRIPTION:
Stream0278
END DESCRIPTION:
DSS Export Rating Curves= 0
DSS Export Rating Curve Sorted= 0
DSS Export Volume Flow Curves= 0
DXF OffsetX= 0
DXF OffsetY= 0
DXF ScaleX= 1
DXF ScaleY= 10

--- Stream0278.p01 (plan) ---

Plan Title=Multiple Run
Short Identifier=Multiple
Geom File=g01
Flow File=f01
Subcritical Flow
K Sum by GR= 0
Std Step Tol= 0.01
Critical Tol= 0.01
Num of Std Step Trials= 20
Max Error Tol= 0.3
Flow Tol Ratio= 0.001
Split Flow NTrial= 30
Split Flow Tol= 0.02
Split Flow Ratio= 0.02
Log Output Level= 0
Friction Slope Method= 1
Unsteady Friction Slope Method= 2
Unsteady Bridges Friction Slope Method= 1
Parabolic Critical Depth
Global Vel Dist=  1 , 1 , 1
Global Log Level= 0
CheckData=True
Encroach Param= -1, 0, 0, 0
BEGIN DESCRIPTION:
Multiple Run
END DESCRIPTION:

--- Stream0278.f01 (steady flow) ---

Flow Title=Multiple
Number of Profiles=7
Profile Names=10-year,25-year,50-year,1pct_min,100-year,1pct_plu,500-year
River Rch & RM= Stream0278,Reach-1,35173
     834    1367    1856    1220    2434    4856    4146
River Rch & RM= Stream0278,Reach-1,32305
    1041    1723    2355    1557    3106    6197    5354
River Rch & RM= Stream0278,Reach-1,28726
    1343    2250    3100    2062    4115    8211    7191
River Rch & RM= Stream0278,Reach-1,25172
    1515    2544    3510    2337    4664    9305    8165
River Rch & RM= Stream0278,Reach-1,20686
    1733    2920    4037    2693    5373   10721    9437
River Rch & RM= Stream0278,Reach-1,17164
    2608    4469    6249    4210    8399   16759   15050
River Rch & RM= Stream0278,Reach-1,11032
    2677    4585    6410    4317    8613   17185   15422
River Rch & RM= Stream0278,Reach-1,7479
    2754    4709    6575    4421    8821   17599   15745
River Rch & RM= Stream0278,Reach-1,2458
    2931    5022    7021    4726    9430   18815   16871
Boundary for River Rch & Prof#=Stream0278,Reach-1,1
Up Type=0
Dn Type=3
Dn Slope=0.005
Boundary for River Rch & Prof#=Stream0278,Reach-1,2
Up Type=0
Dn Type=3
Dn Slope=0.005
Boundary for River Rch & Prof#=Stream0278,Reach-1,3
Up Type=0
Dn Type=3
Dn Slope=0.005
Boundary for River Rch & Prof#=Stream0278,Reach-1,4
Up Type=0
Dn Type=3
Dn Slope=0.005
Boundary for River Rch & Prof#=Stream0278,Reach-1,5
Up Type=0
Dn Type=3
Dn Slope=0.005
Boundary for River Rch & Prof#=Stream0278,Reach-1,6
Up Type=0
Dn Type=3
Dn Slope=0.005
Boundary for River Rch & Prof#=Stream0278,Reach-1,7
Up Type=0
Dn Type=3
Dn Slope=0.005

--- Stream0278.g01 (geometry) ---

Geom Title=Existing Conditions
Program Version=4.10

River Reach=Stream0278      ,Reach-1
Reach XY= 30
        2396825.       13750775.      2397130.46     13749821.99
      2397794.63     13749054.52       2399317.3     13748081.48
      2399684.15     13746368.27      2400957.87      13745091.3
      2401441.67     13745008.37      2401885.31     13744275.86
      2402835.17     13744764.18      2403668.66     13743833.02
      2404658.77     13743542.11      2404332.77     13743228.41
      2404464.88     13742985.34      2404978.42     13743117.24
      2405531.19     13742767.19      2408411.77     13740438.67
       2408224.8     13738749.92      2408525.55     13738245.13
      2408278.76     13737826.56        2409567.     13737481.38
      2409780.46     13735672.55      2410498.97     13735302.19
      2411280.61     13734030.59      2411671.54      13733873.5
      2411350.85     13733297.72      2411869.16     13733177.05
      2412614.94     13733635.12      2412874.14     13732885.31
      2412215.17     13733164.54        2412375.       13732475.

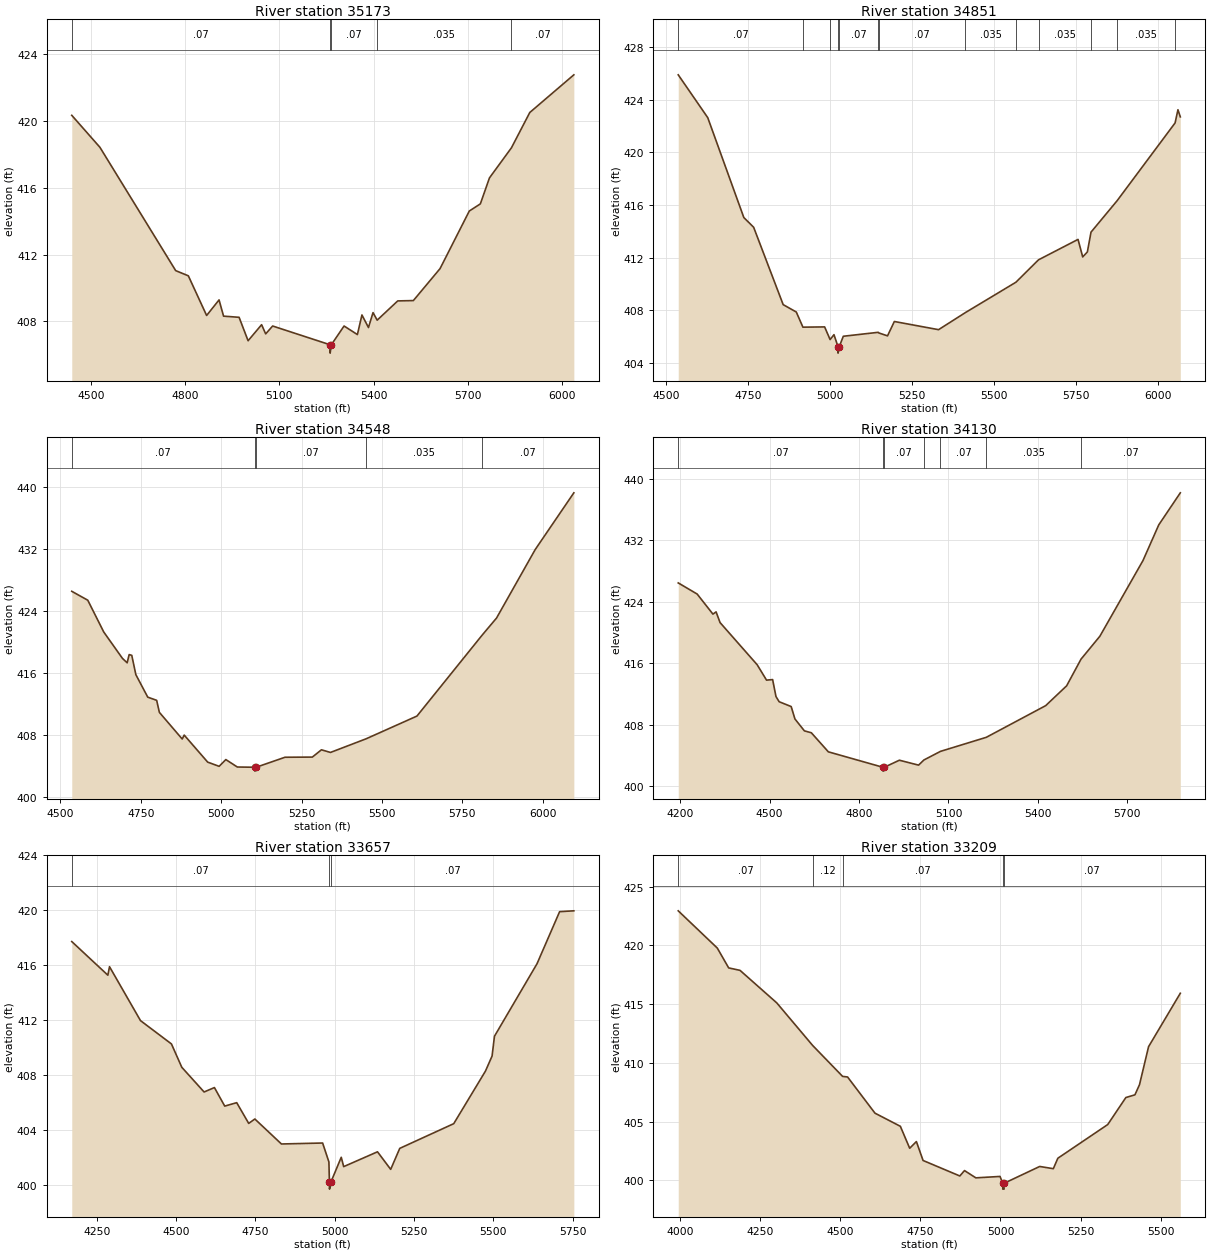
Type RM Length L Ch R = 1 ,35173   ,322,322,322
BEGIN DESCRIPTION:
XS6321
END DESCRIPTION:
XS GIS Cut Line= 4
      2396979.24     13751274.16      2396927.16     13750819.35
       2396760.5     13750614.49      2396066.02     13750076.27
#Sta/Elev= 30
  4438.1  420.32  4527.8  418.41  4769.4  411.04  4809.7  410.73    4868  408.36
  4907.6  409.29    4922  408.32  4971.5  408.25  5000.2  406.85  5043.3  407.81
  5056.2  407.26  5078.5  407.73  5261.5  406.61  5261.8  406.11  5265.5  406.61
  5306.1  407.73  5348.6  407.22  5363.1  408.39  5383.9  407.64  5398.4  408.53
  5411.7  408.08  5477.2  409.23    5527  409.25  5612.1  411.16  5705.3   414.6
  5740.6  415.03  5769.6  416.58  5839.7  418.38  5898.2  420.49  6038.6  422.74
#Mann= 5 ,-1 , 0
  4438.1     .07       0  5261.5     .05       0  5265.5     .07       0
  5411.7    .035       0  5839.7     .07       0
Bank Sta=5261.5,5265.5
XS Rating Curve= 0 ,0
Exp/Cntr=0.3,0.1

Type RM Length L Ch R = 1 ,34851   ,303,303,303
BEGIN DESCRIPTION:
Stream0278 70.0
END DESCRIPTION:
XS GIS Cut Line= 3
      2397474.99       13750525.      2397083.41     13750524.21
      2396224.97     13749774.97
#Sta/Elev= 30
  4536.4  425.88  4626.4  422.63  4736.4  415.05  4766.4  414.31  4856.4  408.44
  4896.4  407.88  4916.6  406.73  4982.8  406.75  4999.5  405.79  5011.3  406.16
  5023.5  405.26  5023.7  404.76  5027.6  405.26  5039.8  406.04  5146.5  406.34
  5148.3  406.29  5174.6  406.07  5195.4  407.16  5330.2  406.54  5412.3  407.84
  5566.1  410.14    5635  411.84  5755.5  413.39  5769.8  412.06    5784  412.44
  5795.1  413.94  5874.5  416.32  6051.5  422.23  6060.2  423.23  6067.4  422.69
#Mann= 13 ,-1 , 0
  4536.4     .07       0  4916.6     .12       0  4999.5     .07       0
  5023.5     .05       0  5027.6     .07       0  5146.5     .12       0
  5148.3     .07       0  5412.3    .035       0  5566.1     .07       0
    5635    .035       0  5795.1     .07       0  5874.5    .035       0
  6051.5     .07       0
Bank Sta=5023.5,5027.6
XS Rating Curve= 0 ,0
Exp/Cntr=0.3,0.1

Type RM Length L Ch R = 1 ,34548   ,418,418,418
BEGIN DESCRIPTION:
Stream0278 69.0
END DESCRIPTION:
XS GIS Cut Line= 3
        2397475.       13750475.      2397063.45     13750170.56
      2396324.98     13749424.98
#Sta/Elev= 30
  4535.4  426.55  4585.2   425.4  4634.9   421.3    4693   417.9  4707.6  417.33
  4713.9  418.39    4722  418.29  4734.7   415.8  4771.7   412.9  4799.4  412.49
  4807.8  410.94  4878.8   407.5    4885  408.01  4958.1  404.52  4993.6  403.98
  5014.5  404.85  5050.2  403.89  5104.6  403.86  5104.9  403.36  5108.8  403.86
  5198.6  405.15  5283.5  405.17  5311.8  406.11    5340  405.77  5450.2  407.52
  5608.8  410.46  5811.2  420.88  5856.3   423.1  5976.5  431.93  6096.7  439.25
#Mann= 5 ,-1 , 0
  4535.4     .07       0  5104.6     .05       0  5108.8     .07       0
  5450.2    .035       0  5811.2     .07       0
Bank Sta=5104.6,5108.8
XS Rating Curve= 0 ,0
Exp/Cntr=0.3,0.1

Type RM Length L Ch R = 1 ,34130   ,473,473,473
BEGIN DESCRIPTION:
Stream0278 68.0
END DESCRIPTION:
XS GIS Cut Line= 3
      2397525.01     13750475.02      2397339.49     13749938.79
        2396375.       13749375.
#Sta/Elev= 30
  4193.3  426.46  4256.8  425.01  4309.7   422.4  4320.3  422.69  4333.6   421.3
  4458.2  415.81  4489.6  413.81    4510  413.88  4521.3  411.67  4531.9     411
  4572.3  410.37  4584.8  408.76  4616.6  407.21  4639.9  406.96    4697  404.48
  4880.2  402.47  4880.5  401.97  4884.5  402.47  4935.3  403.39  4999.7  402.75
  5017.6  403.42  5073.2  404.54    5227  406.37  5426.2  410.49  5496.5  413.07
  5544.8  416.54    5608  419.52  5752.7  429.37  5805.6  434.01  5877.9  438.18
#Mann= 7 ,-1 , 0
  4193.3     .07       0  4880.2     .05       0  4884.5     .07       0
  5017.6    .035       0  5073.2     .07       0    5227    .035       0
  5544.8     .07       0
Bank Sta=4880.2,4884.5
XS Rating Curve= 0 ,0
Exp/Cntr=0.3,0.1

Type RM Length L Ch R = 1 ,33657   ,448,448,448
BEGIN DESCRIPTION:
Stream0278 67.0
END DESCRIPTION:
XS GIS Cut Line= 3
      2397714.49     13750376.29      2397474.91     13749605.46
      2396972.32     13749014.34
#Sta/Elev= 30
    4171  417.72  4284.8  415.27    4290  415.89  4387.7  411.96  4485.3  410.26
  4517.9  408.56  4588.2  406.76  4620.8  407.08  4653.3  405.73  4691.1  405.98
  4728.9  404.47  4748.3  404.79  4832.1  402.97    4962  403.04  4981.8  401.66
  4983.4  400.18  4983.7  399.68  4987.8  400.18  5020.7     402  5028.4  401.32
    5135   402.4  5176.6  401.12  5205.2  402.65  5375.4  404.45  5475.4  408.28
  5496.3  409.38  5503.8  410.82  5637.9   416.1  5709.3   419.9  5754.1  419.96
#Mann= 3 ,-1 , 0
    4171     .07       0  4983.4     .05       0  4987.8     .07       0
Bank Sta=4983.4,4987.8
XS Rating Curve= 0 ,0
Exp/Cntr=0.3,0.1

Type RM Length L Ch R = 1 ,33209   ,462,462,462
BEGIN DESCRIPTION:
Stream0278 66.0
END DESCRIPTION:
XS GIS Cut Line= 3
      2398474.97     13749874.98        2397675.       13749275.
      2397274.97     13748874.97
#Sta/Elev= 30
  3995.2  422.95    4117  419.78  4152.5  418.09  4187.9  417.88  4302.5  415.11
  4414.2  411.49  4507.8  408.85  4523.3   408.8  4608.7  405.72  4687.9   404.6
    4717  402.73  4737.9   403.3  4758.7  401.69  4873.3  400.37  4887.9  400.83
  4923.3  400.21  4998.7  400.33    5007  399.75  5007.4  399.25  5011.3  399.25
  5011.6  399.75  5122.4  401.18  5164.9  400.99    5179  401.88  5334.6  404.75
  5391.1  407.05  5419.4  407.28  5433.6  408.14  5461.9  411.38  5560.9  415.93
#Mann= 5 ,-1 , 0
  3995.2     .07       0  4414.2     .12       0  4507.8     .07       0
    5007     .05       0  5011.6     .07       0
Bank Sta=5007,5011.6
XS Rating Curve= 0 ,0
Exp/Cntr=0.3,0.1

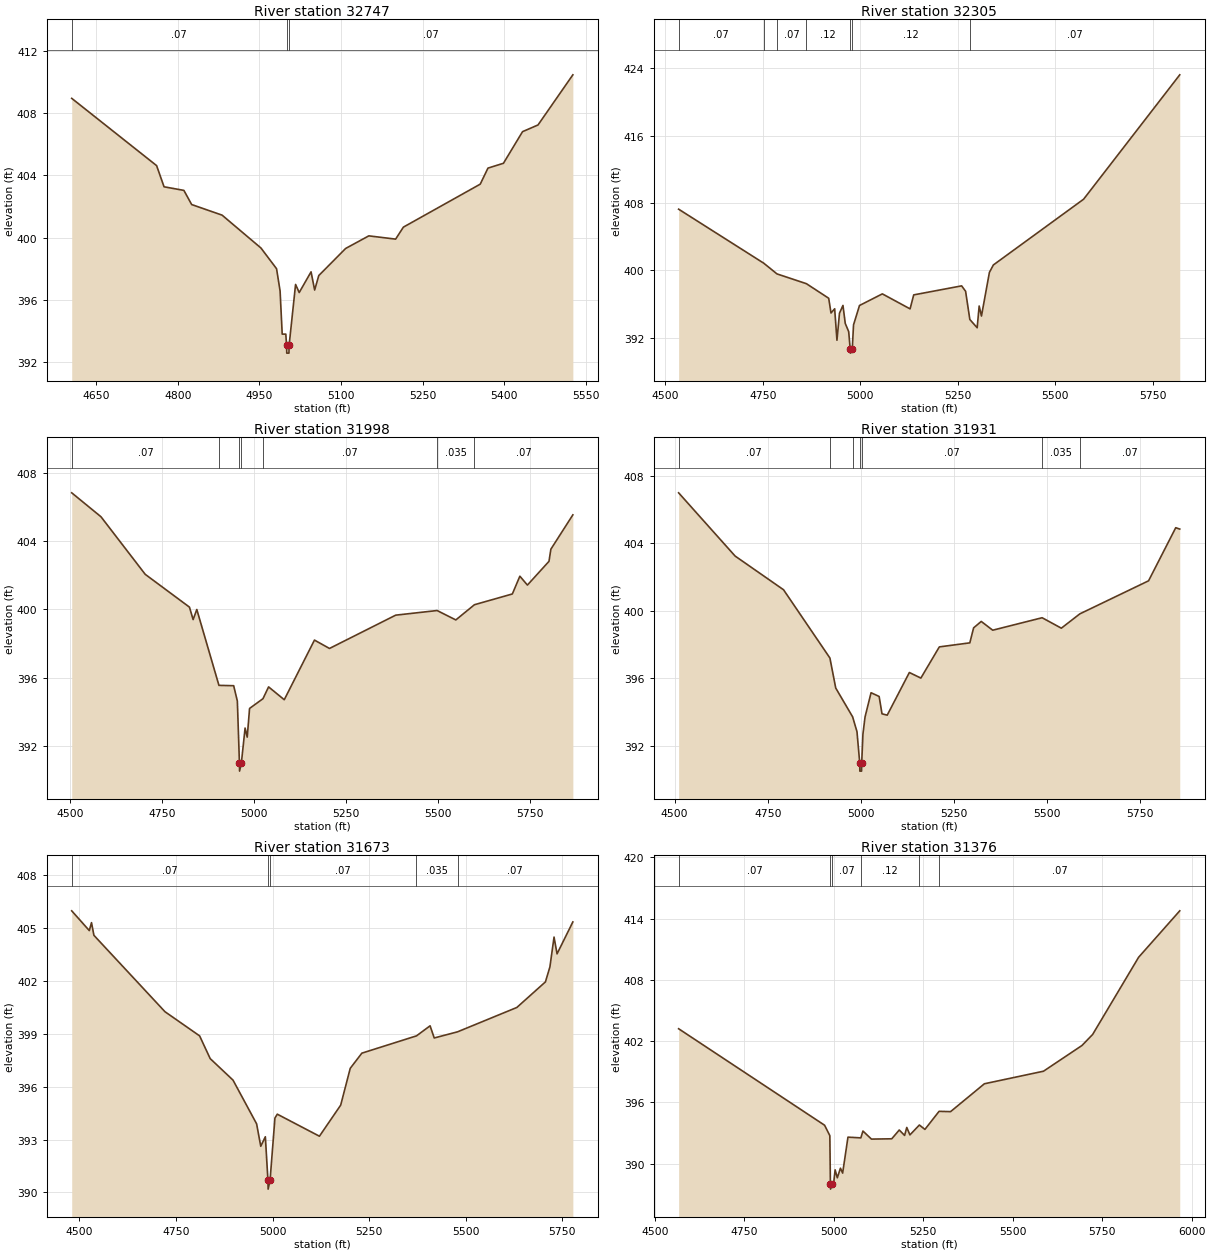
Type RM Length L Ch R = 1 ,32747   ,442,442,442
BEGIN DESCRIPTION:
Stream0278 65.0
END DESCRIPTION:
XS GIS Cut Line= 3
      2398225.02     13749275.03        2397975.       13748975.
      2397574.97     13748624.97
#Sta/Elev= 30
  4604.5  408.94  4760.7  404.62  4774.4  403.26  4810.9  403.03  4825.2  402.12
  4881.2  401.44  4952.7  399.33  4981.4     398  4987.9  396.57  4991.8   393.8
  4998.4   393.8  4999.9  393.08  5000.2  392.58  5004.2  392.58  5004.5  393.08
  5016.4  396.99  5023.1  396.47  5044.9   397.8  5051.5  396.63  5059.1  397.56
  5108.5   399.3  5151.2  400.11  5200.5   399.9  5214.8  400.67  5356.2  403.43
  5370.4  404.46  5398.9  404.77    5434   406.8  5462.5  407.23  5526.6  410.45
#Mann= 3 ,-1 , 0
  4604.5     .07       0  4999.9     .05       0  5004.5     .07       0
Bank Sta=4999.9,5004.5
XS Rating Curve= 0 ,0
Exp/Cntr=0.3,0.1

Type RM Length L Ch R = 1 ,32305   ,307,307,307
BEGIN DESCRIPTION:
Stream0278 64.0
END DESCRIPTION:
XS GIS Cut Line= 3
      2398474.99     13749024.98        2398225.       13748625.
      2397425.02       13748475.
#Sta/Elev= 30
  4533.9  407.26  4752.3  400.85  4786.2  399.58  4861.7  398.42  4918.9  396.69
  4924.8  394.94  4934.2  395.44  4940.1  391.71  4946.6  394.92  4955.5  395.84
  4961.4   393.7  4970.2  392.73    4974  390.68  4974.4  390.18  4979.4  390.68
  4982.6  393.53  4997.9  395.83  5056.5  397.21  5127.7  395.43    5137  397.09
  5259.9  398.16  5270.1  397.52    5281  394.17  5299.8  393.19  5304.9  395.77
  5310.8  394.58  5331.2  399.76  5341.3  400.64  5572.8  408.44  5819.5   423.2
#Mann= 7 ,-1 , 0
  4533.9     .07       0  4752.3     .12       0  4786.2     .07       0
  4861.7     .12       0    4974     .05       0  4979.4     .12       0
    5281     .07       0
Bank Sta=4974,4979.4
XS Rating Curve= 0 ,0
Exp/Cntr=0.3,0.1

Type RM Length L Ch R = 1 ,31998   ,67,67,67
BEGIN DESCRIPTION:
XS6320
END DESCRIPTION:
XS GIS Cut Line= 4
      2398493.14     13749014.36       2398472.3     13748553.38
       2398597.3     13748350.25      2398456.68     13747704.44
#Sta/Elev= 30
  4505.4  406.82  4584.8  405.42    4705  402.05  4825.1  400.13  4835.1   399.4
  4845.1  399.99  4905.2  395.55  4945.2  395.53  4955.2  394.63  4960.8  391.03
  4961.2  390.53  4966.2  391.03  4976.2  393.05    4982  392.52  4988.4   394.2
  5024.8  394.77    5040  395.46  5082.6  394.71  5164.6   398.2  5205.4  397.71
  5385.3  399.66  5497.7  399.93  5548.5  399.38    5599  400.27    5702   400.9
  5722.4  401.94  5742.9  401.42  5801.5  402.81  5806.6  403.52  5866.3  405.53
#Mann= 7 ,-1 , 0
  4505.4     .07       0  4905.2     .12       0  4960.8     .05       0
  4966.2     .12       0  5024.8     .07       0  5497.7    .035       0
    5599     .07       0
Bank Sta=4960.8,4966.2
XS Rating Curve= 0 ,0
Exp/Cntr=0.3,0.1

Type RM Length L Ch R = 1 ,31931   ,258,258,258
BEGIN DESCRIPTION:
XS6319
END DESCRIPTION:
XS GIS Cut Line= 4
      2398508.76     13749006.52      2398529.59     13748574.21
      2398633.76     13748386.71      2398482.72     13747704.43
#Sta/Elev= 30
  4510.6     407  4662.3  403.25  4792.4  401.25    4917   397.2  4932.6  395.42
    4978  393.71  4989.7  392.83    4997  390.99  4997.4  390.49    5002  390.49
  5002.4  390.99  5005.7  392.69  5011.4  393.71  5027.5  395.14  5049.2  394.92
  5056.9  393.89  5070.9  393.81  5130.4  396.34  5161.3  396.01  5210.9  397.86
  5292.8   398.1    5303  398.99  5323.5  399.37  5354.3  398.85    5487  399.59
  5538.6  398.97  5588.4  399.82  5772.9  401.78  5845.9  404.93  5856.7  404.85
#Mann= 7 ,-1 , 0
  4510.6     .07       0    4917     .12       0    4978     .07       0
    4997     .05       0  5002.4     .07       0    5487    .035       0
  5588.4     .07       0
Bank Sta=4997,5002.4
XS Rating Curve= 0 ,0
Exp/Cntr=0.3,0.1

Type RM Length L Ch R = 1 ,31673   ,297,297,297
BEGIN DESCRIPTION:
Stream0278 63.0
END DESCRIPTION:
XS GIS Cut Line= 3
        2399025.       13748875.      2398816.05      13748506.5
       2398506.4     13747689.42
#Sta/Elev= 30
  4479.9  405.97  4525.4  404.85  4531.1   405.3  4537.4  404.58  4721.3  400.25
    4811  398.88  4838.4  397.59  4897.5  396.37  4958.6  393.89  4969.3  392.62
  4981.2  393.16  4987.9  390.69  4988.4  390.19  4993.4  390.69    5006  394.22
  5012.1  394.44  5121.2  393.19  5176.2  394.95    5201  397.04  5231.1   397.9
  5372.5  398.88  5407.7  399.45  5418.4  398.76  5478.9  399.11  5632.3  400.49
  5706.3  401.94  5717.9  402.79  5728.6  404.48  5736.4  403.53  5777.3  405.34
#Mann= 5 ,-1 , 0
  4479.9     .07       0  4987.9     .05       0  4993.4     .07       0
  5372.5    .035       0  5478.9     .07       0
Bank Sta=4987.9,4993.4
XS Rating Curve= 0 ,0
Exp/Cntr=0.3,0.1

Type RM Length L Ch R = 1 ,31376   ,427,427,427
BEGIN DESCRIPTION:
Stream0278 62.0
END DESCRIPTION:
XS GIS Cut Line= 3
      2399274.98     13748624.98        2399025.       13748275.
      2398475.01     13747475.01
#Sta/Elev= 30
    4566  403.22    4974  393.77  4988.7  392.75  4990.3  388.01  4990.7  387.51
  4995.8  388.01  4999.1  388.01  5003.5   389.4  5009.6  388.62  5018.4  389.56
  5024.5  389.08  5039.4   392.6  5075.4  392.53  5081.3   393.2    5105  392.41
  5161.8  392.44  5182.8   393.3  5197.7  392.77  5203.8  393.55  5212.6  392.82
    5239  393.79  5254.5  393.36  5294.1  395.13  5326.2   395.1  5420.8  397.83
    5586  399.06  5693.6  401.58  5723.4  402.66  5851.9  410.22  5966.9  414.77
#Mann= 6 ,-1 , 0
    4566     .07       0  4990.3     .05       0  4995.8     .07       0
  5075.4     .12       0    5239    .035       0  5294.1     .07       0
Bank Sta=4990.3,4995.8
XS Rating Curve= 0 ,0
Exp/Cntr=0.3,0.1

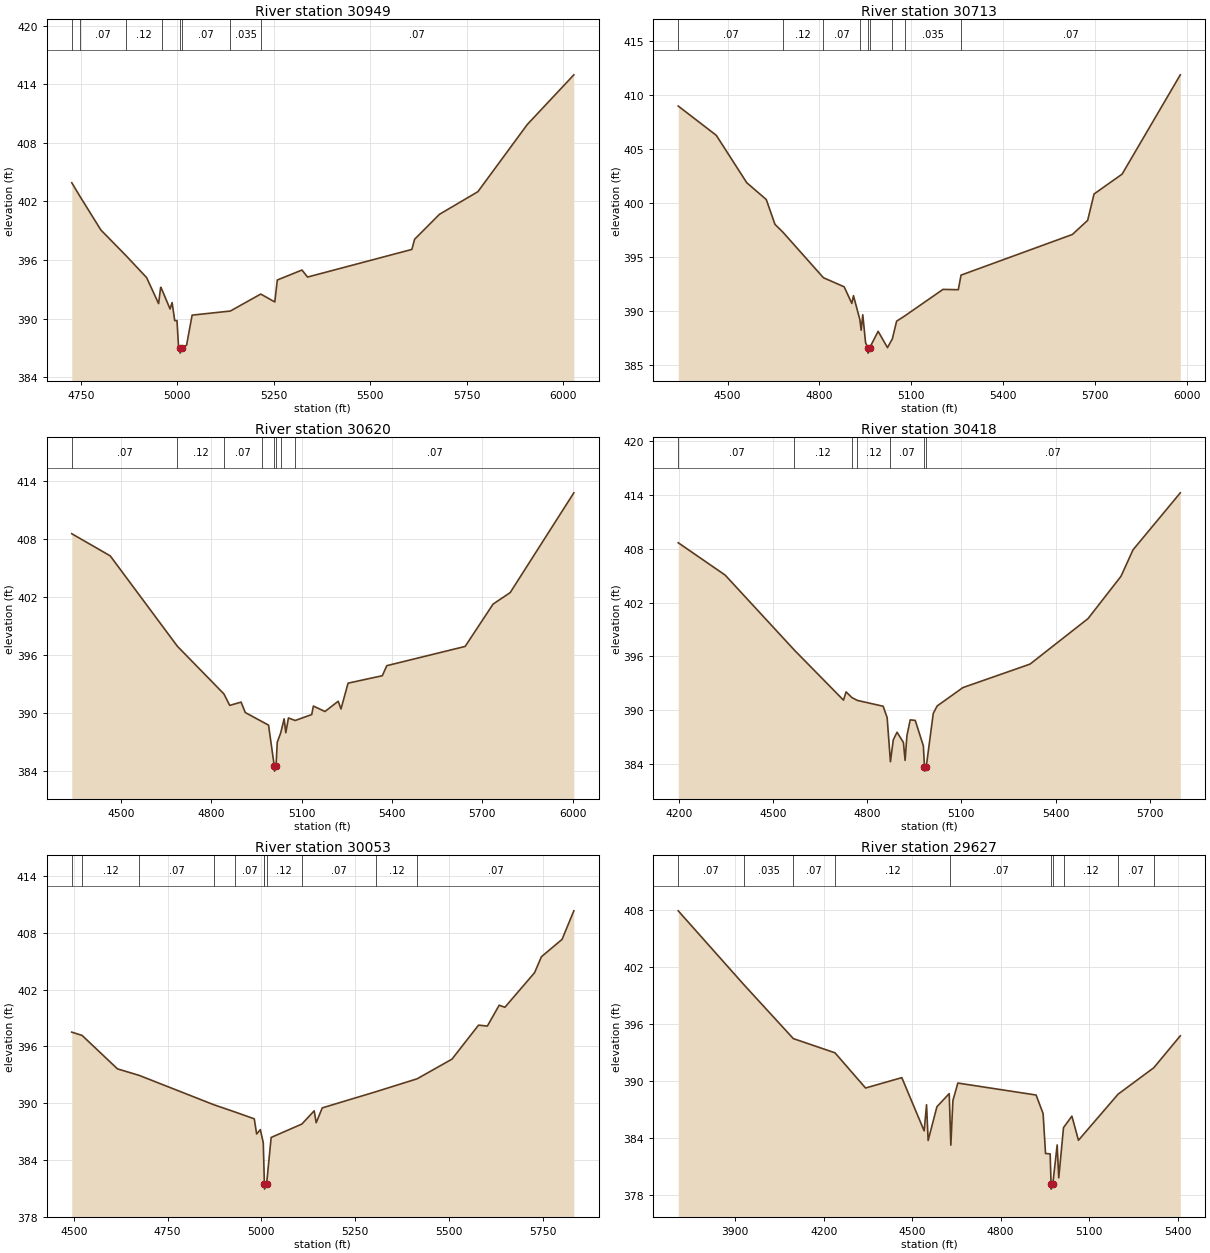
Type RM Length L Ch R = 1 ,30949   ,236,236,236
BEGIN DESCRIPTION:
Stream0278 61.0
END DESCRIPTION:
XS GIS Cut Line= 3
      2399575.01       13748175.        2399325.       13748075.
      2398525.04     13747425.03
#Sta/Elev= 30
  4726.8  403.91  4748.4  402.49  4802.2  399.07  4867.6  396.43  4920.7  394.19
  4951.6  391.53    4957   393.2  4959.9     393  4981.3  390.98  4986.6  391.64
  4993.4  389.79  4999.3  389.79  5003.3  387.08  5006.9  386.96  5007.3  386.46
  5012.5  386.96  5024.1  387.28  5038.4  390.35  5137.4  390.77  5216.1  392.51
  5252.5   391.7    5259  393.95  5322.9  394.97  5337.3  394.25  5607.4  397.08
  5614.5  398.12    5679  400.68  5778.3  402.99  5906.2  409.87  6026.8  414.96
#Mann= 8 ,-1 , 0
  4726.8     .12       0  4748.4     .07       0  4867.6     .12       0
  4959.9     .07       0  5006.9     .05       0  5012.5     .07       0
  5137.4    .035       0  5216.1     .07       0
Bank Sta=5006.9,5012.5
XS Rating Curve= 0 ,0
Exp/Cntr=0.3,0.1

Type RM Length L Ch R = 1 ,30713   ,93,93,93
BEGIN DESCRIPTION:
XS6318
END DESCRIPTION:
XS GIS Cut Line= 5
      2399878.57     13748147.47      2399569.31     13747794.96
      2399346.55     13747877.14      2399212.47     13747935.53
      2398583.11     13747461.88
#Sta/Elev= 30
  4338.8  409.01  4463.2   406.3  4562.8  401.91  4626.4  400.36  4654.9  398.06
    4681  397.33  4813.1  393.12  4880.9  392.28    4906  390.74  4911.3  391.46
  4932.2  389.24  4936.4  388.26  4941.7  389.69  4950.9   387.1  4958.7  386.64
  4959.1  386.14  4964.3  386.64  4991.9  388.16  5022.4  386.65  5038.3  387.46
  5052.3   389.1  5078.2  389.57  5203.8  392.04  5253.8  392.01  5262.7  393.36
  5626.3  397.12  5676.4  398.43  5697.3  400.87    5789  402.71  5979.1   411.9
#Mann= 9 ,-1 , 0
  4338.8     .07       0    4681     .12       0  4813.1     .07       0
  4932.2    .035       0  4958.7    .035       0  4964.3    .035       0
  5038.3     .07       0  5078.2    .035       0  5262.7     .07       0
Bank Sta=4958.7,4964.3
XS Rating Curve= 0 ,0
Exp/Cntr=0.3,0.1

Type RM Length L Ch R = 1 ,30620   ,202,202,202
BEGIN DESCRIPTION:
XS6317
END DESCRIPTION:
XS GIS Cut Line= 4
      2399891.56     13748138.84      2399536.87     13747730.08
      2399210.31     13747881.46      2398577.43     13747449.47
#Sta/Elev= 30
  4336.4   408.5  4464.1  406.21  4687.1  396.86  4841.6  391.93    4861  390.74
  4898.7  391.08  4912.7     390  4968.4  389.06  4989.9   388.7  5009.1  384.44
  5009.6  383.94  5014.7  384.44  5018.8  386.93  5030.2  387.89  5041.7  389.35
  5047.2  387.91    5056  389.44  5078.4  389.18  5133.2  389.79  5138.8  390.67
  5177.3  390.11  5221.3  391.17  5230.5  390.37    5254  393.04  5367.7  393.81
  5382.6  394.85  5642.8  396.84  5735.6  401.22  5792.4  402.41  6003.8  412.73
#Mann= 8 ,-1 , 0
  4336.4     .07       0  4687.1     .12       0  4841.6     .07       0
  4968.4     .12       0  5009.1     .05       0  5014.7     .12       0
  5030.2    .035       0  5078.4     .07       0
Bank Sta=5009.1,5014.7
XS Rating Curve= 0 ,0
Exp/Cntr=0.3,0.1

Type RM Length L Ch R = 1 ,30418   ,365,365,365
BEGIN DESCRIPTION:
Stream0278 60.0
END DESCRIPTION:
XS GIS Cut Line= 3
      2399903.45     13748134.72      2399568.15      13747689.8
      2398574.96     13747374.99
#Sta/Elev= 30
  4198.4  408.67  4347.9  405.06  4568.6  396.68  4724.7  391.11    4733  392.03
  4751.4   391.4  4768.9  391.08  4851.1  390.43  4863.7  389.16  4871.3   385.6
  4874.2  384.24  4883.3  386.68  4895.2  387.53  4915.6  386.39  4920.9  384.39
  4926.7  387.14  4937.2  388.91  4953.2  388.85  4979.1  386.01  4982.6  383.69
  4983.1  383.19  4988.3  383.69  5010.6  389.63    5023  390.46    5105  392.51
  5318.8  395.13  5503.6  400.21  5608.5  404.93  5646.8  407.88  5797.4  414.24
#Mann= 7 ,-1 , 0
  4198.4     .07       0  4568.6     .12       0  4751.4     .07       0
  4768.9     .12       0  4871.3     .07       0  4982.6     .05       0
  4988.3     .07       0
Bank Sta=4982.6,4988.3
XS Rating Curve= 0 ,0
Exp/Cntr=0.3,0.1

Type RM Length L Ch R = 1 ,30053   ,426,426,426
BEGIN DESCRIPTION:
Stream0278 59.0
END DESCRIPTION:
XS GIS Cut Line= 3
      2399874.98     13747774.97        2399575.       13747375.
      2398775.02     13747125.01
#Sta/Elev= 30
  4494.8  397.52  4522.4  397.17  4616.6  393.63  4674.5  392.94    4873  389.84
  4930.3  389.06  4981.2  388.34  4987.5  386.74  4997.4   387.2  5005.2   385.8
  5005.8  384.92  5008.2   381.4  5008.6   380.9  5013.9   381.4  5026.2  386.37
  5108.1  387.79  5140.9  389.19  5146.2  387.93  5162.4   389.5  5305.3  391.21
  5415.3  392.58  5508.1  394.66  5578.9  398.26  5602.4  398.16  5633.9  400.37
  5649.1  400.15  5728.2  403.81  5746.5   405.5  5801.5  407.34  5832.9  410.36
#Mann= 11 ,-1 , 0
  4494.8     .07       0  4522.4     .12       0  4674.5     .07       0
    4873     .12       0  4930.3     .07       0  5005.8     .12       0
  5008.2     .05       0  5013.9     .12       0  5108.1     .07       0
  5305.3     .12       0  5415.3     .07       0
Bank Sta=5008.2,5013.9
XS Rating Curve= 0 ,0
Exp/Cntr=0.3,0.1

Type RM Length L Ch R = 1 ,29627   ,489,489,489
BEGIN DESCRIPTION:
Stream0278 58.0
END DESCRIPTION:
XS GIS Cut Line= 3
      2400725.02     13747525.01        2399525.       13747025.
      2399175.03     13746825.02
#Sta/Elev= 30
  3706.3   407.9    3929  400.13  4096.6  394.46  4238.1  392.96  4341.7  389.26
  4464.7  390.35  4540.5  384.75  4548.6   387.5    4554  383.74  4583.8  387.29
  4625.5  388.67  4627.8   386.4    4631  383.25    4638  387.94  4654.8  389.78
  4920.2  388.52    4944  386.57  4952.2  382.37  4967.9  382.33    4971  379.12
  4971.4  378.62  4976.7  379.12  4991.7  383.27  4997.1  379.81  5013.2  385.09
  5041.6   386.3  5063.9  383.76  5198.3  388.61  5319.4  391.39  5409.4  394.75
#Mann= 10 ,-1 , 0
  3706.3     .07       0    3929    .035       0  4096.6     .07       0
  4238.1     .12       0  4627.8     .07       0    4971     .05       0
  4976.7     .07       0  5013.2     .12       0  5198.3     .07       0
  5319.4     .12       0
Bank Sta=4971,4976.7
XS Rating Curve= 0 ,0
Exp/Cntr=0.3,0.1

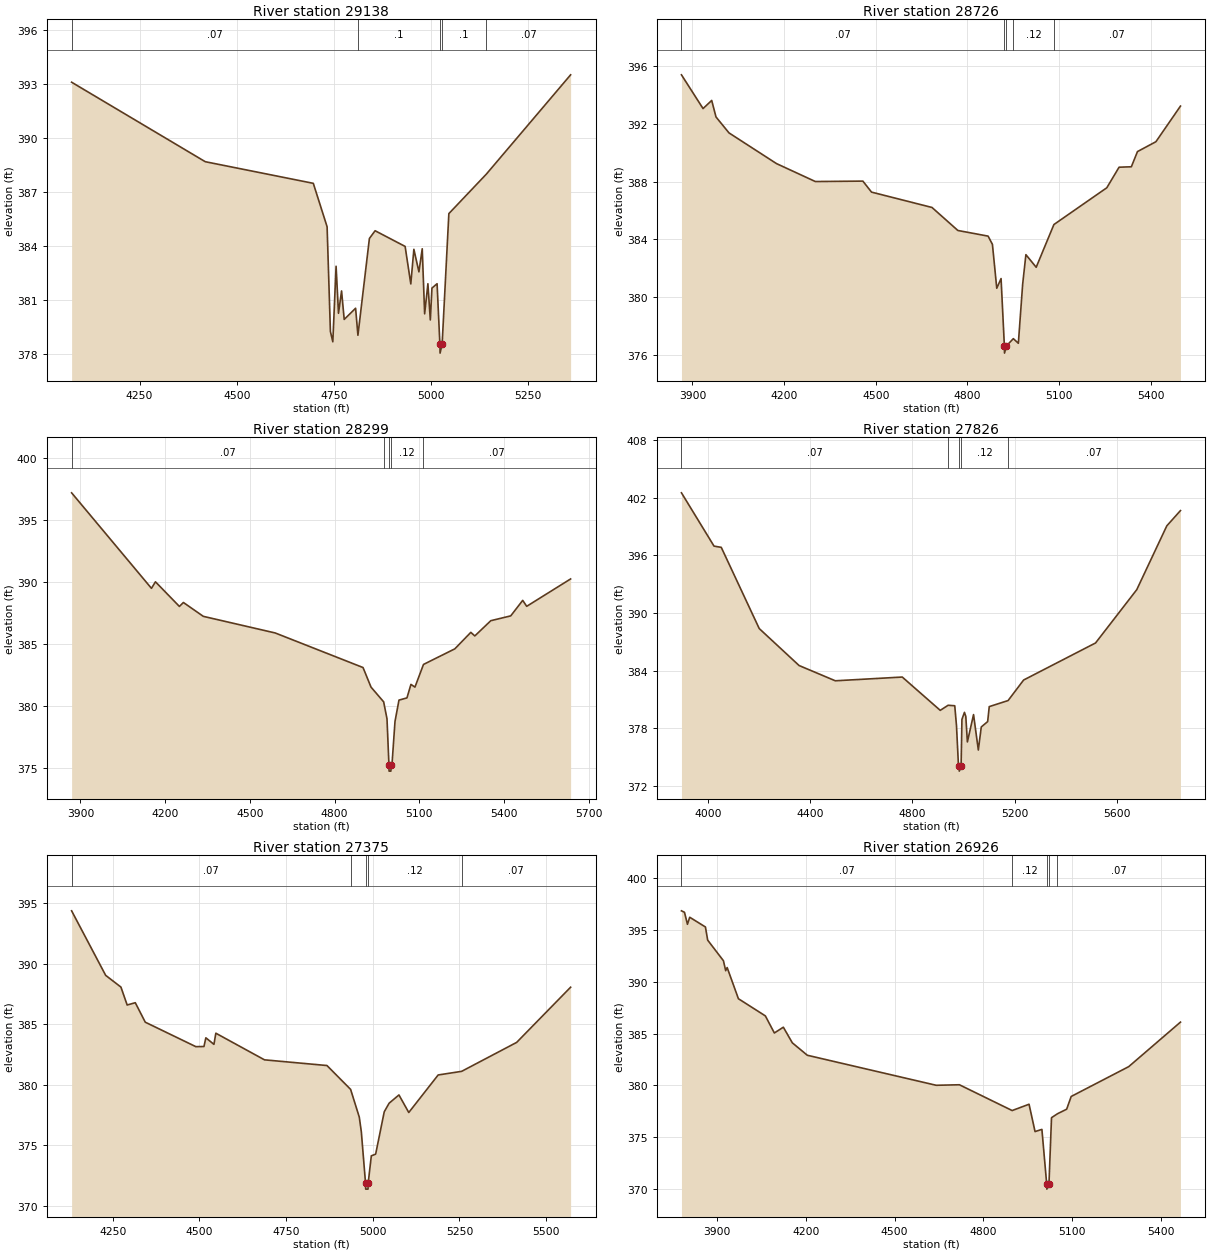
Type RM Length L Ch R = 1 ,29138   ,412,412,412
BEGIN DESCRIPTION:
Stream0278 57.0
END DESCRIPTION:
XS GIS Cut Line= 3
      2400374.99     13747124.99        2399625.       13746575.
        2399275.       13746525.
#Sta/Elev= 30
  4075.1   393.1  4418.9  388.69  4696.8  387.49  4732.3  385.08  4740.8  379.27
    4747   378.7  4755.4  382.89  4761.6  380.28  4769.5  381.52  4776.3  379.94
  4805.6  380.56  4811.6  379.06  4841.1  384.43  4855.8  384.86    4933  383.99
  4947.6  381.91  4955.5  383.83  4968.5  382.58    4977  383.86  4983.2  380.25
  4991.6  381.92  4997.8  379.91    5002  381.68  5015.2  381.92  5022.4  378.57
  5022.9  378.07  5028.2  378.57  5045.5  385.81  5141.9     388  5358.7  393.51
#Mann= 5 ,-1 , 0
  4075.1     .07       0  4811.6      .1       0  5022.4     .05       0
  5028.2      .1       0  5141.9     .07       0
Bank Sta=5022.4,5028.2
XS Rating Curve= 0 ,0
Exp/Cntr=0.3,0.1

Type RM Length L Ch R = 1 ,28726   ,427,427,427
BEGIN DESCRIPTION:
Stream0278 56.0
END DESCRIPTION:
XS GIS Cut Line= 3
      2400575.01     13747075.01        2399775.       13746275.
      2399274.98       13746225.
#Sta/Elev= 30
    3864  395.37  3934.7  393.04    3963   393.6  3977.1  392.46  4019.6  391.36
  4175.1  389.24  4302.4     388    4458  388.03  4486.3  387.27  4684.3  386.21
  4769.1  384.62  4868.1  384.23  4882.2  383.66  4896.4  380.63  4910.5   381.3
  4921.3  376.65  4921.8  376.15    4928  376.65  4950.7  377.15  4967.1  376.83
  4981.2  380.91  4991.8  382.95  5025.5  382.08  5083.5  385.03  5256.7  387.57
  5296.9  388.99  5337.1  389.02  5357.2  390.07  5417.5  390.75  5497.9  393.21
#Mann= 5 ,-1 , 0
    3864     .07       0  4921.3     .05       0    4928     .07       0
  4950.7     .12       0  5083.5     .07       0
Bank Sta=4921.3,4928
XS Rating Curve= 0 ,0
Exp/Cntr=0.3,0.1

Type RM Length L Ch R = 1 ,28299   ,473,473,473
BEGIN DESCRIPTION:
Stream0278 55.0
END DESCRIPTION:
XS GIS Cut Line= 3
      2400875.03     13746825.03        2400075.       13746025.
        2399625.       13745575.
#Sta/Elev= 30
  3868.6   397.2  4151.5  389.49  4165.6  390.02  4250.5  388.03  4264.6  388.35
  4335.3  387.23  4589.9  385.89    4901   383.1  4929.3  381.52  4974.1  380.33
  4985.9  378.96  4992.8  375.24  4993.3  374.74  4999.7  374.74  5000.2  375.24
  5003.5  375.24  5014.2  378.74  5028.3  380.47  5056.6  380.65  5070.7  381.74
  5084.9  381.52  5115.2  383.35  5226.3  384.61  5282.9  385.94    5297  385.65
  5353.6  386.88  5424.3  387.27  5466.7  388.52  5480.8  388.04  5636.4  390.25
#Mann= 5 ,-1 , 0
  3868.6     .07       0  4974.1     .12       0  4992.8     .05       0
  5000.2     .12       0  5115.2     .07       0
Bank Sta=4992.8,5000.2
XS Rating Curve= 0 ,0
Exp/Cntr=0.3,0.1

Type RM Length L Ch R = 1 ,27826   ,451,451,451
BEGIN DESCRIPTION:
Stream0278 54.0
END DESCRIPTION:
XS GIS Cut Line= 3
        2401175.       13746525.        2400425.       13745725.
        2400125.     13744924.99
#Sta/Elev= 30
  3897.2  402.51  4024.5  396.96  4052.8  396.83  4201.3  388.37  4357.1  384.52
  4498.7  382.93  4760.5  383.32    4909  379.85  4939.8  380.38  4965.7  380.33
  4972.5  378.26  4979.9  374.28  4982.9  374.02  4983.4  373.52  4990.5  374.02
  4993.8  378.91  5003.6  379.64  5008.9  379.22  5015.1  376.56  5039.2  379.41
  5057.9  375.72  5069.4  378.12  5094.4  378.68  5100.6  380.24  5174.2  380.87
    5235  383.01  5516.2  386.87  5677.3  392.42  5794.8  399.07  5848.2  400.66
#Mann= 5 ,-1 , 0
  3897.2     .07       0  4939.8     .12       0  4982.9     .05       0
  4990.5     .12       0  5174.2     .07       0
Bank Sta=4982.9,4990.5
XS Rating Curve= 0 ,0
Exp/Cntr=0.3,0.1

Type RM Length L Ch R = 1 ,27375   ,449,449,449
BEGIN DESCRIPTION:
Stream0278 53.0
END DESCRIPTION:
XS GIS Cut Line= 3
      2401074.98     13746324.96        2400725.       13745525.
      2400324.97     13745124.97
#Sta/Elev= 30
  4131.6  394.38  4229.8  389.05  4273.8  388.08  4291.8   386.6  4315.2  386.79
    4344  385.18  4489.8  383.16  4513.2  383.17  4518.7  383.89    4542  383.35
  4547.5  384.27  4687.8  382.07  4867.9   381.6  4936.1  379.63  4961.1  377.34
    4967  376.13  4979.1  371.89  4979.6  371.39  4986.3  371.39  4986.8  371.89
  4995.8  374.14  5008.3  374.28  5033.1  377.78  5047.2  378.49  5075.5  379.17
  5103.8  377.72  5188.6  380.82  5256.3  381.12  5414.9  383.51  5570.5  388.07
#Mann= 5 ,-1 , 0
  4131.6     .07       0  4936.1     .12       0  4979.1     .05       0
  4986.8     .12       0  5256.3     .07       0
Bank Sta=4979.1,4986.8
XS Rating Curve= 0 ,0
Exp/Cntr=0.3,0.1

Type RM Length L Ch R = 1 ,26926   ,458,458,458
BEGIN DESCRIPTION:
Stream0278 52.0
END DESCRIPTION:
XS GIS Cut Line= 3
      2401125.01     13746375.04        2400925.       13745175.
      2400524.99     13744924.99
#Sta/Elev= 30
  3778.7  396.86  3788.9  396.72    3799  395.56  3806.6  396.24  3859.8   395.3
  3867.4  394.03  3920.7  392.04  3928.3  391.08  3933.3  391.38  3971.4  388.37
  4062.6  386.71    4093  385.06  4123.4  385.62  4153.8  384.11  4204.5  382.91
  4640.5  380.01    4719  380.06  4897.6  377.57  4954.7  378.18    4975  375.54
  4998.2  375.75  5014.4  370.48  5014.9  369.98  5022.1  370.48  5030.7  376.88
  5050.9  377.26    5082   377.7  5097.3  378.93  5291.9  381.81    5467  386.11
#Mann= 5 ,-1 , 0
  3778.7     .07       0  4897.6     .12       0  5014.4     .05       0
  5022.1     .12       0  5050.9     .07       0
Bank Sta=5014.4,5022.1
XS Rating Curve= 0 ,0
Exp/Cntr=0.3,0.1

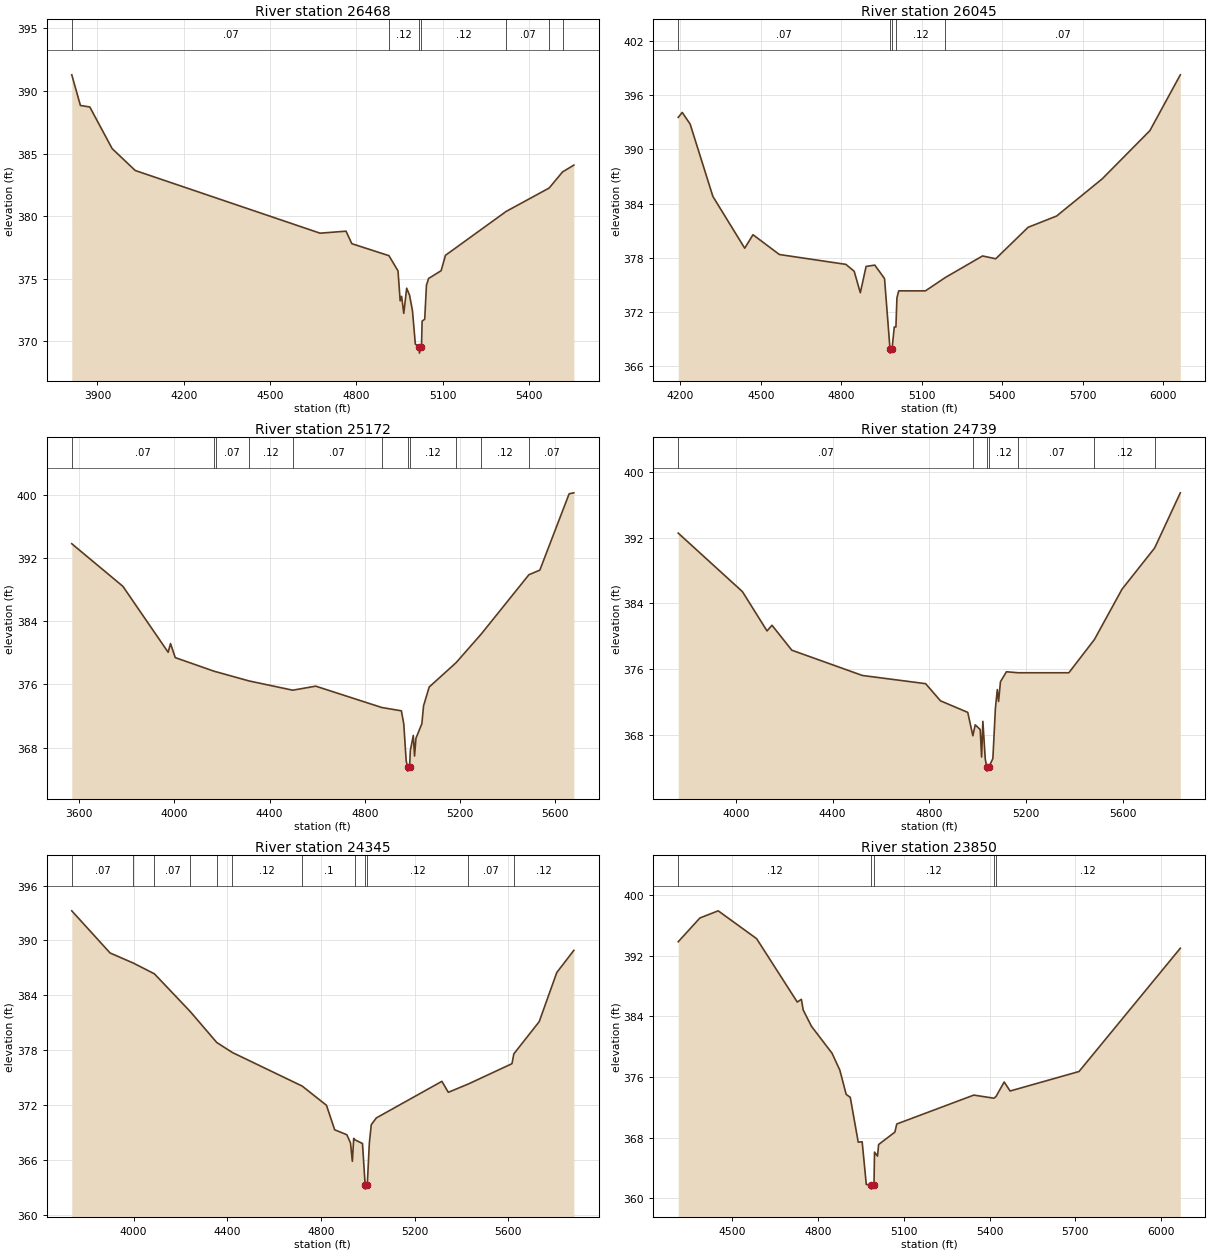
Type RM Length L Ch R = 1 ,26468   ,423,423,423
BEGIN DESCRIPTION:
Stream0278 51.0
END DESCRIPTION:
XS GIS Cut Line= 3
        2401175.     13746174.96        2401275.       13744975.
      2400824.96     13744674.97
#Sta/Elev= 30
  3810.9  391.29    3841  388.84  3873.6  388.72  3951.3  385.39  4031.6  383.64
  4673.8  378.63  4764.2  378.79  4784.2  377.79  4913.4  376.83  4944.8  375.61
  4952.3  373.22  4957.3  373.58  4964.8  372.22  4974.9  374.23  4984.9  373.67
    4995  372.44    5005  369.76  5018.6  369.54  5019.1  369.04  5026.4  369.54
  5028.5   371.6  5037.6  371.75  5043.6  374.47  5051.1  375.01  5094.6  375.63
  5109.7  376.86  5320.7  380.37  5470.1  382.24  5516.7  383.53  5555.9  384.07
#Mann= 7 ,-1 , 0
  3810.9     .07       0  4913.4     .12       0  5018.6     .05       0
  5026.4     .12       0  5320.7     .07       0  5470.1     .12       0
  5516.7     .07       0
Bank Sta=5018.6,5026.4
XS Rating Curve= 0 ,0
Exp/Cntr=0.3,0.1

Type RM Length L Ch R = 1 ,26045   ,873,873,873
BEGIN DESCRIPTION:
Stream0278 50.0
END DESCRIPTION:
XS GIS Cut Line= 3
      2401874.99     13745624.97        2401575.       13744875.
      2400874.97     13744074.96
#Sta/Elev= 30
  4192.3  393.53  4207.1  394.08  4236.7  392.79  4321.5  384.78    4440  379.06
  4470.9  380.55  4569.2  378.36  4816.9  377.27  4847.9  376.51  4870.8  374.13
  4892.3  377.04  4924.6  377.19    4961   375.7  4981.3  367.95  4981.8  367.45
  4989.2  367.95  4997.3  370.34  5003.4  370.34  5005.4  372.04  5007.2  373.57
  5013.8  374.34  5113.5  374.34  5187.7  375.82  5326.1   378.2  5375.4  377.89
    5496  381.37  5602.3  382.62  5772.1  386.73  5949.6  392.06  6063.1  398.24
#Mann= 5 ,-1 , 0
  4192.3     .07       0  4981.3     .05       0  4989.2     .07       0
  5005.4     .12       0  5187.7     .07       0
Bank Sta=4981.3,4989.2
XS Rating Curve= 0 ,0
Exp/Cntr=0.3,0.1

Type RM Length L Ch R = 1 ,25172   ,433,433,433
BEGIN DESCRIPTION:
Stream0278 49.0
END DESCRIPTION:
XS GIS Cut Line= 3
      2401997.74      13745749.9        2402025.       13744325.
      2401793.57     13743680.55
#Sta/Elev= 30
  3568.9   393.8  3783.8  388.41  3973.9  380.07  3983.9  381.17  4003.9  379.39
  4167.9  377.66  4173.1  377.62  4313.9  376.44  4497.5  375.27    4594  375.78
  4871.7  373.08    4954  372.66  4964.1     371  4974.1  366.39  4979.8  365.53
  4980.3  365.03  4988.4  365.53  4991.6  367.62  5004.1  369.55  5009.4  366.94
  5015.3  369.19  5040.2  371.04  5047.2  373.29  5070.9  375.67  5183.6  378.74
  5289.5  382.37    5490  389.88  5535.9  390.46    5659  400.12  5678.8  400.24
#Mann= 11 ,-1 , 0
  3568.9     .07       0  4167.9     .12       0  4173.1     .07       0
  4313.9     .12       0  4497.5     .07       0  4871.7     .12       0
  4979.8     .05       0  4988.4     .12       0  5183.6     .07       0
  5289.5     .12       0    5490     .07       0
Bank Sta=4979.8,4988.4
XS Rating Curve= 0 ,0
Exp/Cntr=0.3,0.1

Type RM Length L Ch R = 1 ,24739   ,394,394,394
BEGIN DESCRIPTION:
Stream0278 48.0
END DESCRIPTION:
XS GIS Cut Line= 3
       2402102.6     13745733.29        2402375.       13744525.
      2402124.99     13743724.97
#Sta/Elev= 30
  3761.4  392.56  4026.9  385.43  4128.7  380.64  4149.2  381.33  4231.2  378.29
    4523  375.21  4784.7  374.21  4846.2  372.12    4959  370.71  4980.1  367.86
  4989.8  369.19  5010.5  368.62  5016.3  365.27  5021.5  369.62  5031.4  365.02
  5037.6  364.05  5038.1  363.55  5046.3  364.05  5062.9  365.09  5073.4  371.23
  5081.2  373.49  5086.4  372.04  5094.3  374.45  5118.9  375.66  5168.1  375.54
  5377.2  375.54  5482.9  379.59  5597.2  385.73  5732.1  390.75  5838.2  397.47
#Mann= 7 ,-1 , 0
  3761.4     .07       0  4980.1     .12       0  5037.6     .05       0
  5046.3     .12       0  5168.1     .07       0  5482.9     .12       0
  5732.1     .07       0
Bank Sta=5037.6,5046.3
XS Rating Curve= 0 ,0
Exp/Cntr=0.3,0.1

Type RM Length L Ch R = 1 ,24345   ,495,495,495
BEGIN DESCRIPTION:
Stream0278 47.0
END DESCRIPTION:
XS GIS Cut Line= 3
      2403233.81     13745766.44       2402701.9     13744717.25
      2402225.01     13743875.01
#Sta/Elev= 30
    3736  393.24  3899.7  388.63  3999.4  387.52  4088.9  386.35  4242.1  382.22
  4355.2  378.84  4422.2  377.74  4720.1  374.07  4823.8  371.97  4858.8  369.29
  4910.8  368.75  4926.4  367.85  4934.3  365.84  4940.1  368.35  4944.9   368.2
  4977.6  367.79  4988.8   363.3  4989.3   362.8  4998.1   363.3  5006.8  367.83
  5015.1  369.85  5036.8  370.59  5316.7  374.59  5344.1  373.39  5429.6   374.3
  5615.9  376.52  5624.1   377.6  5732.3  381.12  5807.3  386.49  5880.2  388.92
#Mann= 12 ,-1 , 0
    3736     .07       0  3999.4     .12       0  4088.9     .07       0
  4242.1     .12       0  4355.2     .07       0  4422.2     .12       0
  4720.1      .1       0  4944.9     .12       0  4988.8     .05       0
  4998.1     .12       0  5429.6     .07       0  5624.1     .12       0
Bank Sta=4988.8,4998.1
XS Rating Curve= 0 ,0
Exp/Cntr=0.3,0.1

Type RM Length L Ch R = 1 ,23850   ,446,446,446
BEGIN DESCRIPTION:
Stream0278 46.0
END DESCRIPTION:
XS GIS Cut Line= 3
      2403360.73      13745115.3        2402925.       13744575.
      2402225.01     13743775.01
#Sta/Elev= 30
  4310.4  393.82  4386.3  396.96  4450.3   397.9  4584.7  394.23    4727  385.87
  4741.4  386.23  4747.8  384.82  4776.6  382.68  4848.5  379.13    4876  376.89
  4898.1   373.7  4912.5   373.3  4940.3   367.4  4954.1  367.44  4968.5  361.82
  4986.2   361.7  4986.7   361.2  4995.5   361.7  4997.3  366.08  5007.8  365.55
  5011.6  367.08  5068.6  368.72  5075.2  369.79  5344.8   373.6  5415.1  373.19
  5422.6  373.42  5451.1  375.33  5471.9  374.14    5713  376.71  6067.5  392.97
#Mann= 5 ,-1 , 0
  4310.4     .12       0  4986.2     .05       0  4995.5     .12       0
  5415.1     .07       0  5422.6     .12       0
Bank Sta=4986.2,4995.5
XS Rating Curve= 0 ,0
Exp/Cntr=0.3,0.1