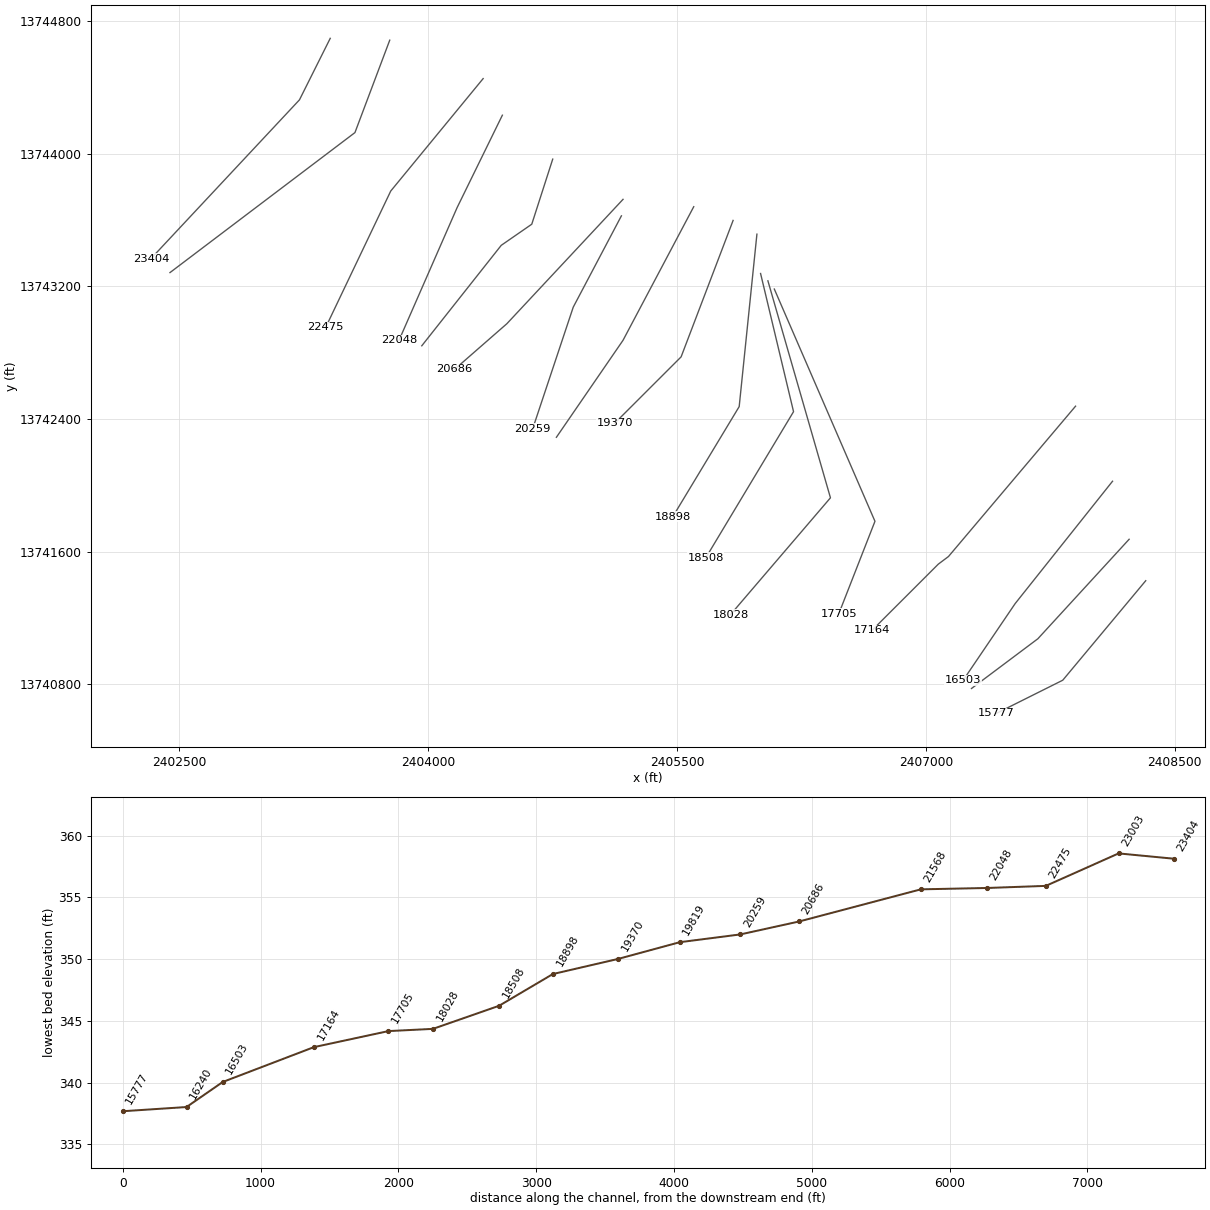
HEC-RAS study Stream0278.prj: Stream0278 Base Level Engineering

--- Stream0278.g01 (geometry) --- (continued)

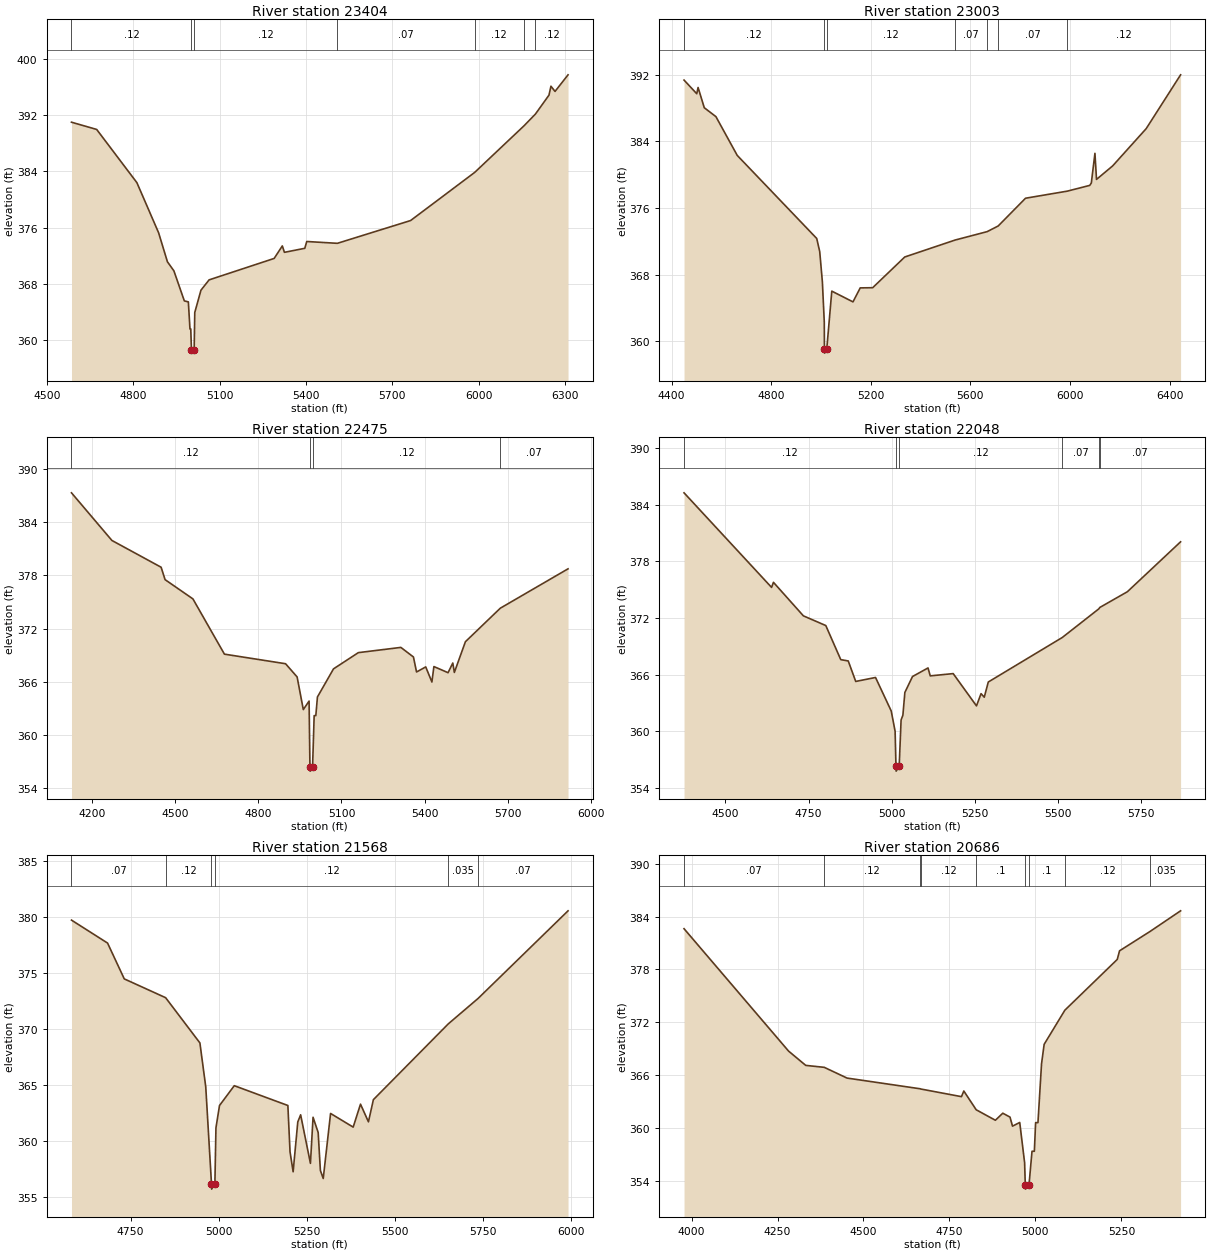
Type RM Length L Ch R = 1 ,23404   ,401,401,401
BEGIN DESCRIPTION:
Stream0278 45.0
END DESCRIPTION:
XS GIS Cut Line= 3
       2403410.4     13744695.94        2403225.       13744325.
      2402329.39     13743366.64
#Sta/Elev= 30
  4584.8  390.99  4672.4  389.96  4812.2  382.39  4887.7  375.26  4918.4  371.13
  4940.8  369.85  4977.1  365.57  4991.1  365.43  4996.7  361.58  4999.5  361.58
  5001.9  358.64  5002.4  358.14  5011.3  358.64  5013.4  363.92  5034.9  367.09
  5063.2  368.56  5289.4  371.61  5317.8  373.39  5325.1  372.48  5395.9  373.05
  5402.8  374.02  5509.1  373.76  5763.8     377  5986.4  383.84  6158.2  390.48
  6197.8  392.15  6244.9  394.84  6251.8  396.11    6266  395.37  6311.2  397.73
#Mann= 7 ,-1 , 0
  4584.8     .12       0  5001.9     .05       0  5011.3     .12       0
  5509.1     .07       0  5986.4     .12       0  6158.2     .07       0
  6197.8     .12       0
Bank Sta=5001.9,5011.3
XS Rating Curve= 0 ,0
Exp/Cntr=0.3,0.1

Type RM Length L Ch R = 1 ,23003   ,528,528,528
BEGIN DESCRIPTION:
Stream0278 44.0
END DESCRIPTION:
XS GIS Cut Line= 3
      2403769.07     13744684.88      2403559.38     13744127.54
      2402444.71     13743283.26
#Sta/Elev= 30
  4450.2  391.34  4501.3   389.7  4506.6  390.45  4531.5  388.02  4578.3  386.95
  4663.8   382.3    4983  372.33    4995  370.76  5005.7  367.12  5013.3  362.31
  5013.9  359.07  5014.4  358.57  5023.3  359.07  5043.5  366.01  5128.6  364.72
  5157.7   366.4  5207.6  366.42  5336.6  370.11  5538.5  372.14  5667.3  373.15
  5711.7  373.83  5821.4  377.16    5989  378.01  6079.3   378.7  6085.6  378.99
  6100.1  382.55  6106.4  379.42  6170.9  381.03  6306.1  385.52    6444  391.97
#Mann= 7 ,-1 , 0
  4450.2     .12       0  5013.9     .05       0  5023.3     .12       0
  5538.5     .07       0  5667.3     .12       0  5711.7     .07       0
    5989     .12       0
Bank Sta=5013.9,5023.3
XS Rating Curve= 0 ,0
Exp/Cntr=0.3,0.1

Type RM Length L Ch R = 1 ,22475   ,427,427,427
BEGIN DESCRIPTION:
Stream0278 43.0
END DESCRIPTION:
XS GIS Cut Line= 3
      2404331.92     13744453.12        2403775.       13743775.
       2403382.8      13742952.2
#Sta/Elev= 30
  4127.3  387.32  4272.9  381.95  4450.2  378.93  4464.5  377.53  4564.8  375.36
  4678.3  369.13  4898.6  368.05  4940.2  366.56  4962.5  362.88  4983.3  363.84
  4986.4  356.44  4986.9  355.94  4995.9  356.44  5001.6   362.2  5007.6   362.2
  5013.4   364.3  5071.3  367.47  5160.7   369.3    5314  369.89  5359.3  368.81
  5370.5  367.12  5403.6  367.69  5425.8  365.99    5433  367.73    5484  367.04
  5501.1  368.13  5506.7  367.07  5546.5  370.53  5672.2  374.31  5916.3  378.75
#Mann= 4 ,-1 , 0
  4127.3     .12       0  4986.4     .05       0  4995.9     .12       0
  5672.2     .07       0
Bank Sta=4986.4,4995.9
XS Rating Curve= 0 ,0
Exp/Cntr=0.3,0.1

Type RM Length L Ch R = 1 ,22048   ,480,480,480
BEGIN DESCRIPTION:
Stream0278 42.0
END DESCRIPTION:
XS GIS Cut Line= 3
      2404447.81     13744232.42        2404175.       13743675.
      2403825.01     13742875.01
#Sta/Elev= 30
  4375.3  385.25  4638.7  375.23  4644.3  375.77  4734.3  372.22  4801.8  371.19
  4846.8  367.58  4869.3  367.44  4891.8  365.27  4951.4  365.69  4998.6  362.14
  5010.3  359.99  5012.9  356.27  5013.4  355.77  5022.5  356.27  5028.3  361.19
  5033.7   361.7  5039.6   364.1  5062.6  365.79  5109.3   366.7    5116  365.86
    5185   366.1  5255.1  362.68  5268.8  363.98  5278.5   363.6  5290.6  365.21
  5513.4  369.93  5623.1  372.96  5626.2  373.11  5708.9  374.77  5869.1  380.06
#Mann= 6 ,-1 , 0
  4375.3     .12       0  5012.9     .05       0  5022.5     .12       0
  5513.4     .07       0  5623.1     .12       0  5626.2     .07       0
Bank Sta=5012.9,5022.5
XS Rating Curve= 0 ,0
Exp/Cntr=0.3,0.1

Type RM Length L Ch R = 1 ,21568   ,882,882,882
BEGIN DESCRIPTION:
Stream0278 41.0
END DESCRIPTION:
XS GIS Cut Line= 4
       2404751.3     13743967.54        2404625.       13743575.
      2404440.99     13743447.61      2403962.21     13742841.83
#Sta/Elev= 30
  4582.5  379.69  4684.8  377.64  4732.2  374.44  4849.5  372.76  4946.7  368.72
  4963.3  364.79  4979.5  356.16    4980  355.66  4989.2  356.16  4992.2  361.13
  5002.3  363.13  5044.2   364.9  5196.2  363.13  5202.3     359  5211.1  357.21
  5224.3  361.66  5232.4   362.3  5260.2  357.96  5267.6  362.08  5282.1  360.72
  5288.4  357.33  5296.5  356.61  5317.3  362.42  5381.4   361.2  5402.2  363.25
  5424.7  361.67  5438.7  363.65  5651.1  370.42  5735.9   372.7  5990.8  380.52
#Mann= 6 ,-1 , 0
  4582.5     .07       0  4849.5     .12       0  4979.5     .05       0
  4989.2     .12       0  5651.1    .035       0  5735.9     .07       0
Bank Sta=4979.5,4989.2
XS Rating Curve= 0 ,0
Exp/Cntr=0.3,0.1

Type RM Length L Ch R = 1 ,20686   ,427,427,427
BEGIN DESCRIPTION:
Stream0278 40.0
END DESCRIPTION:
XS GIS Cut Line= 3
      2405175.01     13743725.01        2404475.       13742975.
      2404160.11     13742699.84
#Sta/Elev= 30
  3978.1  382.63  4282.2  368.73  4332.1  367.11  4385.8  366.89  4452.2  365.67
  4665.6  364.45  4666.3  364.43  4784.9  363.56  4791.8   364.2  4827.8  362.07
  4883.6  360.88  4905.1  361.68  4926.1  361.24  4933.4  360.21  4954.4  360.63
  4968.6  356.06  4970.5  353.56    4971  353.06  4981.4  353.56  4990.1  357.36
  4996.9  357.36  5000.6  360.61  5007.4  360.61  5017.8  367.29  5025.4   369.5
  5085.7  373.38    5238  379.14  5244.7  380.12  5333.5  382.32  5422.2  384.66
#Mann= 9 ,-1 , 0
  3978.1     .07       0  4385.8     .12       0  4665.6      .1       0
  4666.3     .12       0  4827.8      .1       0  4970.5     .05       0
  4981.4      .1       0  5085.7     .12       0  5333.5    .035       0
Bank Sta=4970.5,4981.4
XS Rating Curve= 0 ,0
Exp/Cntr=0.3,0.1

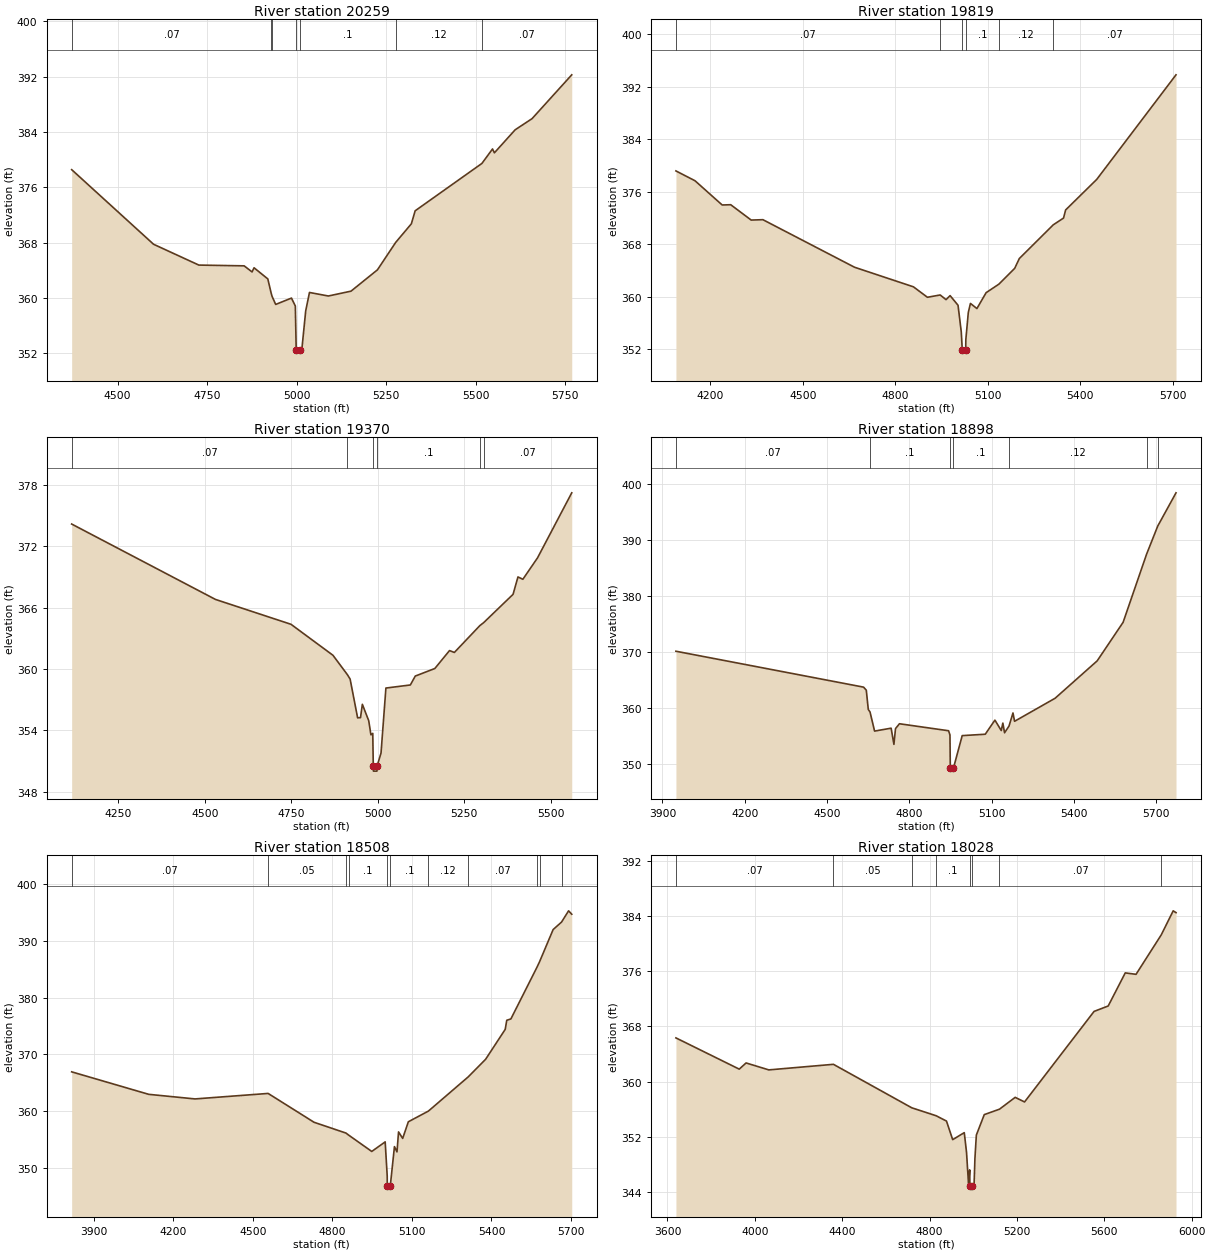
Type RM Length L Ch R = 1 ,20259   ,440,440,440
BEGIN DESCRIPTION:
Stream0278 39.0
END DESCRIPTION:
XS GIS Cut Line= 3
      2405165.14     13743625.38        2404875.       13743075.
      2404630.01     13742340.03
#Sta/Elev= 30
  4371.5  378.54  4600.3  367.75  4726.8  364.74  4853.3  364.63  4875.4  363.75
    4881  364.35  4919.4  362.74  4928.6  360.72  4931.3  360.22  4941.4  359.05
  4985.5  359.97  4996.3  358.82  4998.7  352.51  4999.2  352.01  5009.7  352.51
  5014.8  352.71  5025.3  358.14  5035.8  360.78  5088.5  360.27  5151.8  360.97
  5225.6  364.05  5276.5  368.01  5320.4  370.71    5331  372.59  5517.5  379.44
  5547.1  381.53  5552.3  380.97  5610.3   384.3  5657.7  385.92  5768.4  392.25
#Mann= 7 ,-1 , 0
  4371.5     .07       0  4928.6     .12       0  4931.3      .1       0
  4998.7     .05       0  5009.7      .1       0  5276.5     .12       0
  5517.5     .07       0
Bank Sta=4998.7,5009.7
XS Rating Curve= 0 ,0
Exp/Cntr=0.3,0.1

Type RM Length L Ch R = 1 ,19819   ,449,449,449
BEGIN DESCRIPTION:
Stream0278 38.0
END DESCRIPTION:
XS GIS Cut Line= 3
      2405601.09     13743680.59        2405175.       13742875.
      2404773.39     13742290.03
#Sta/Elev= 30
  4088.9  379.14  4150.8  377.64  4238.8  373.95  4266.5  373.99  4332.8  371.65
  4370.8  371.71  4667.6  364.47  4858.8  361.48    4904  359.89  4945.4  360.24
  4964.4  359.53  4977.6  360.14  5003.3  358.67  5013.8   354.6    5017  351.88
  5017.5  351.38  5028.1  351.88  5028.6  353.46  5036.6  357.58  5043.5  358.95
  5064.5  358.17  5094.3  360.59    5136   361.9    5187   364.3  5201.9  365.79
    5312  370.93  5345.3  371.96    5352  373.19  5452.9  377.85  5709.8  393.78
#Mann= 6 ,-1 , 0
  4088.9     .07       0  4945.4      .1       0    5017     .05       0
  5028.1      .1       0    5136     .12       0    5312     .07       0
Bank Sta=5017,5028.1
XS Rating Curve= 0 ,0
Exp/Cntr=0.3,0.1

Type RM Length L Ch R = 1 ,19370   ,472,472,472
BEGIN DESCRIPTION:
Stream0278 37.0
END DESCRIPTION:
XS GIS Cut Line= 3
      2405838.36     13743597.79        2405525.       13742775.
      2405125.02     13742375.02
#Sta/Elev= 30
  4115.3  374.17  4531.2   366.8  4749.6  364.37    4871  361.34  4912.6  359.45
  4920.5  359.02  4942.2  355.23  4950.6  355.25  4955.9  356.55  4974.3  354.95
  4980.7  353.57    4986  353.71  4987.5  350.52    4988  350.02  4998.1  350.02
  4998.6  350.52  5009.9  351.79    5024  358.14  5094.7  358.44  5108.9  359.31
  5165.5  360.05  5207.9   361.8    5222  361.62  5295.9  364.25  5306.3  364.52
  5391.7   367.3  5405.9     369    5420  368.77  5462.4  370.86  5561.4  377.22
#Mann= 6 ,-1 , 0
  4115.3     .07       0  4912.6      .1       0  4987.5     .05       0
  4998.6      .1       0  5295.9     .12       0  5306.3     .07       0
Bank Sta=4987.5,4998.6
XS Rating Curve= 0 ,0
Exp/Cntr=0.3,0.1

Type RM Length L Ch R = 1 ,18898   ,390,390,390
BEGIN DESCRIPTION:
Stream0278 36.0
END DESCRIPTION:
XS GIS Cut Line= 3
      2405981.83     13743515.01        2405875.       13742475.
      2405474.17     13741809.93
#Sta/Elev= 30
  3949.4  370.21    4633   363.8    4643  363.25  4650.2  359.82  4656.6  359.36
  4673.2  355.95  4733.5  356.47  4743.6  353.58  4749.4  356.39  4763.7  357.26
  4942.8  356.01  4947.8  355.26  4949.1   349.3  4949.6   348.8  4960.3   349.3
  4992.4  355.14  5076.4  355.39  5111.6  357.91  5134.7  356.05  5140.5  357.38
  5146.7  355.65    5163  356.85  5177.4  359.19  5183.2   357.7  5330.8  361.81
  5484.2  368.49  5578.7  375.38  5664.1  387.53  5704.9  392.57  5771.4   398.5
#Mann= 7 ,-1 , 0
  3949.4     .07       0  4656.6      .1       0  4949.1     .05       0
  4960.3      .1       0    5163     .12       0  5664.1     .07       0
  5704.9     .12       0
Bank Sta=4949.1,4960.3
XS Rating Curve= 0 ,0
Exp/Cntr=0.3,0.1

Type RM Length L Ch R = 1 ,18508   ,480,480,480
BEGIN DESCRIPTION:
Stream0278 35.0
END DESCRIPTION:
XS GIS Cut Line= 3
      2406003.91     13743277.74      2406202.56     13742444.51
      2405672.83     13741561.62
#Sta/Elev= 30
  3816.7  366.93  4107.4  362.96  4282.1  362.15  4557.7  363.12  4730.9  358.03
    4851  356.13  4862.2  355.74  4948.6  352.88  4999.2  354.57  5006.9  348.54
  5007.1  346.73  5007.6  346.23  5018.3  346.73  5034.2  353.73  5043.8   352.8
  5049.6  356.33  5065.2  355.18  5086.6  358.12  5162.2     360  5312.4  366.04
  5378.1  369.15    5452  374.43  5457.8  376.03  5473.4  376.27    5571  385.32
  5581.4  386.35  5632.7  392.04  5664.5  393.37    5691  395.35  5702.9  394.75
#Mann= 11 ,-1 , 0
  3816.7     .07       0  4557.7     .05       0    4851     .07       0
  4862.2      .1       0  5007.1     .05       0  5018.3      .1       0
  5162.2     .12       0  5312.4     .07       0    5571     .12       0
  5581.4     .07       0  5664.5     .12       0
Bank Sta=5007.1,5018.3
XS Rating Curve= 0 ,0
Exp/Cntr=0.3,0.1

Type RM Length L Ch R = 1 ,18028   ,323,323,323
BEGIN DESCRIPTION:
Stream0278 34.0
END DESCRIPTION:
XS GIS Cut Line= 3
      2406048.05     13743233.61        2406425.       13741925.
      2405822.03     13741219.74
#Sta/Elev= 30
  3638.7  366.34  3928.6   361.8  3959.9   362.7  4063.9  361.69  4359.8   362.5
  4718.6  356.18  4829.7  355.03  4877.5  354.25  4905.9  351.55  4958.9  352.57
  4969.3   349.7  4978.5  345.05  4983.7  347.16  4984.5  344.86    4985  344.36
  4995.8  344.86  5003.8  345.02  5007.7  348.81  5014.2  352.21  5050.5  355.19
  5120.2  355.98  5192.1   357.7  5234.9  357.03  5553.2  370.19    5618  370.98
    5696  375.79  5745.4  375.58  5860.9  381.32  5915.5  384.81  5928.4  384.55
#Mann= 8 ,-1 , 0
  3638.7     .07       0  4359.8     .05       0  4718.6     .07       0
  4829.7      .1       0  4984.5     .05       0  4995.8      .1       0
  5120.2     .07       0  5860.9     .12       0
Bank Sta=4984.5,4995.8
XS Rating Curve= 0 ,0
Exp/Cntr=0.3,0.1

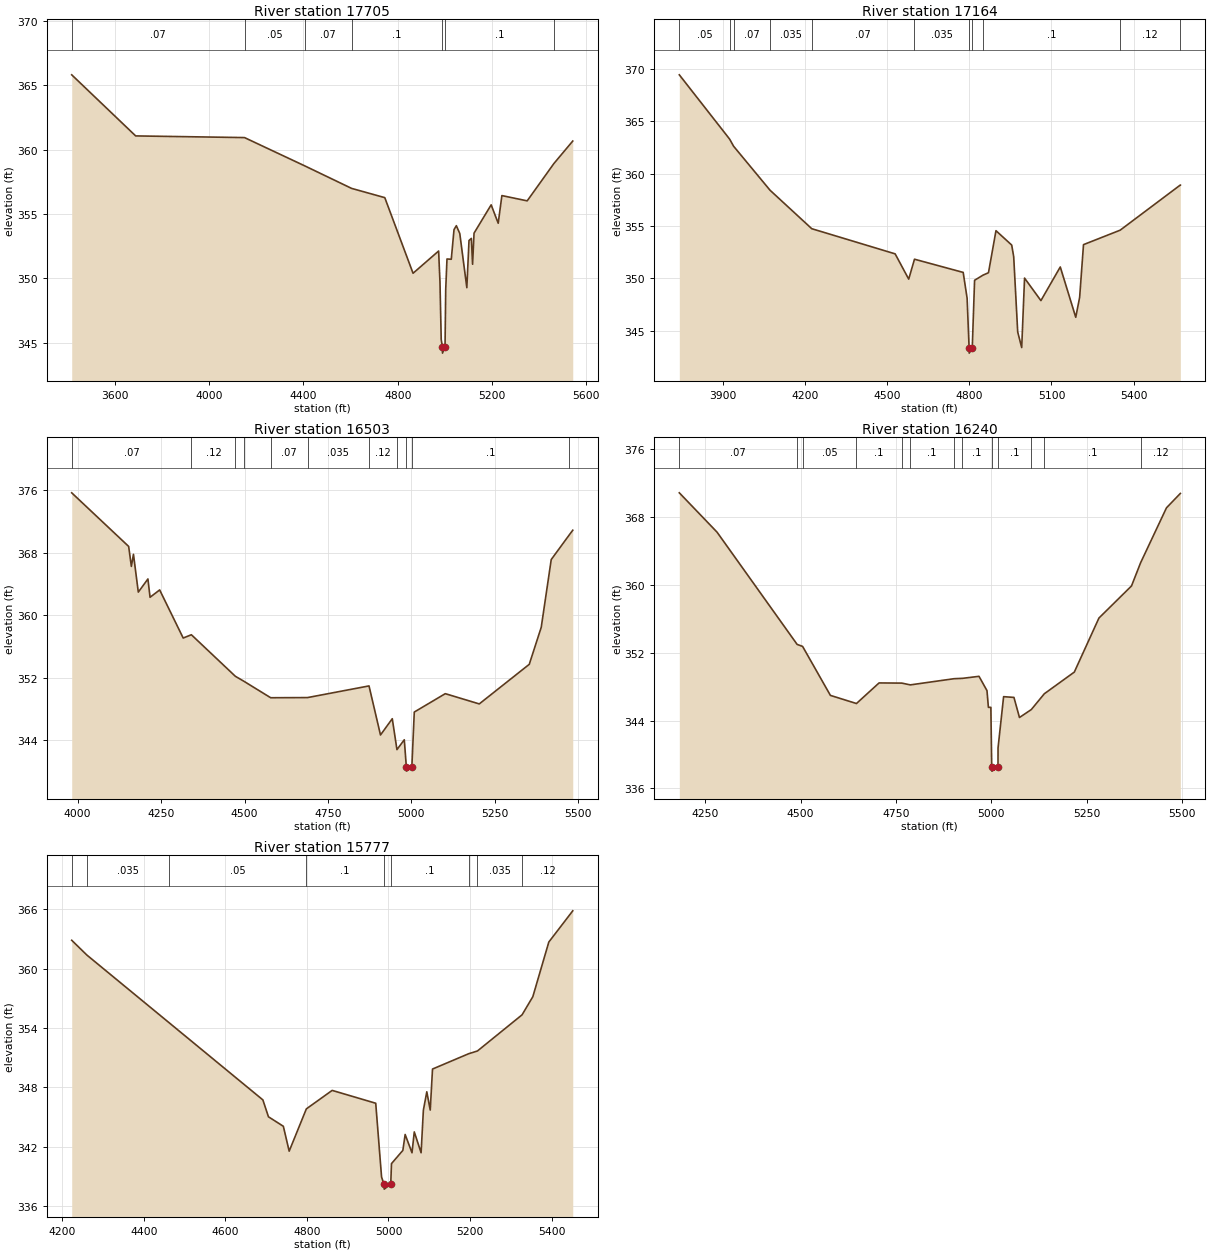
Type RM Length L Ch R = 1 ,17705   ,541,541,541
BEGIN DESCRIPTION:
Stream0278 33.0
END DESCRIPTION:
XS GIS Cut Line= 3
      2406086.69     13743183.93      2406693.24     13741783.39
      2406474.99     13741224.98
#Sta/Elev= 30
  3416.7  365.82    3688  361.07  4149.8  360.94  4406.6  358.73  4604.1  356.99
    4745  356.27  4864.9  350.39  4973.4  352.12  4979.1  349.72  4984.4  345.24
  4989.3  344.68  4989.8  344.18  5000.6  344.68  5003.5  349.13  5008.9   351.5
  5027.1  351.48  5038.7  353.78  5048.6  354.09  5063.2  353.48  5093.1  349.27
  5102.3  352.94  5112.2   353.1  5117.5  351.09  5123.7  353.51  5196.3  355.71
  5226.2  354.28  5241.8  356.43  5349.2  356.02  5462.8  358.93  5542.5  360.67
#Mann= 7 ,-1 , 0
  3416.7     .07       0  4149.8     .05       0  4406.6     .07       0
  4604.1      .1       0  4989.3     .05       0  5000.6      .1       0
  5462.8     .12       0
Bank Sta=4989.3,5000.6
XS Rating Curve= 0 ,0
Exp/Cntr=0.3,0.1

Type RM Length L Ch R = 1 ,17164   ,661,661,661
BEGIN DESCRIPTION:
Stream0278 32.0
END DESCRIPTION:
XS GIS Cut Line= 4
      2407902.12     13742477.59      2407136.28     13741570.96
        2407075.       13741525.      2406674.99     13741124.99
#Sta/Elev= 30
  3741.4  369.43    3925   363.3  3939.5  362.62  4072.6  358.42  4224.9  354.75
  4529.3  352.35  4578.8  349.94  4599.9  351.84  4777.7  350.58    4792  348.12
  4799.3  343.38  4799.8  342.88  4810.8  343.38  4819.3  349.83  4850.1  350.32
    4870  350.55  4897.4  354.56  4954.8  353.19  4962.1  352.08  4976.7   344.9
  4991.3  343.41  5001.7  350.04  5061.4  347.89  5132.1   351.1  5188.6   346.3
  5202.8   348.2  5216.9  353.23  5350.8  354.61    5570  358.91  5570.5  358.91
#Mann= 11 ,-1 , 0
  3741.4     .05       0    3925    .035       0  3939.5     .07       0
  4072.6    .035       0  4224.9     .07       0  4599.9    .035       0
  4799.3     .05       0  4810.8    .035       0  4850.1      .1       0
  5350.8     .12       0    5570     .07       0
Bank Sta=4799.3,4810.8
XS Rating Curve= 0 ,0
Exp/Cntr=0.3,0.1

Type RM Length L Ch R = 1 ,16503   ,263,263,263
BEGIN DESCRIPTION:
Stream0278 31.0
END DESCRIPTION:
XS GIS Cut Line= 3
      2408125.02     13742025.03      2407537.94     13741286.89
      2407224.98     13740824.96
#Sta/Elev= 30
  3982.3  375.63  4152.9  368.78    4161  366.23  4167.3  367.77  4181.8  362.94
  4210.6  364.62    4217  362.28  4245.8  363.22  4316.3  357.07  4340.8  357.49
  4472.6  352.18  4497.6  351.56  4578.4  349.44  4688.9  349.46    4873  350.95
  4907.4  344.68  4942.7  346.76  4956.7  342.81  4978.7  344.07  4984.9  340.56
  4985.4  340.06  5001.3  340.56  5008.6  347.61  5101.5  349.96  5203.3  348.65
  5353.1  353.71    5389  358.45  5418.9   367.1  5472.6  370.23  5483.4  370.85
#Mann= 11 ,-1 , 0
  3982.3     .07       0  4340.8     .12       0  4472.6     .07       0
  4497.6     .12       0  4578.4     .07       0  4688.9    .035       0
    4873     .12       0  4956.7      .1       0  4984.9     .05       0
  5001.3      .1       0  5472.6     .12       0
Bank Sta=4984.9,5001.3
XS Rating Curve= 0 ,0
Exp/Cntr=0.3,0.1

Type RM Length L Ch R = 1 ,16240   ,463,463,463
BEGIN DESCRIPTION:
Stream0278 30.0
END DESCRIPTION:
XS GIS Cut Line= 3
      2408224.98     13741674.98        2407675.       13741075.
      2407275.01     13740775.01
#Sta/Elev= 30
  4181.9  370.88  4280.8  366.24  4490.8  352.99  4505.2  352.75  4578.1  346.97
  4646.4  346.01  4705.7  348.44  4765.2  348.42  4787.7  348.21  4902.4  348.94
  4924.1  348.98  4967.8  349.22  4988.7  347.53  4992.4  345.56  4998.9  345.56
  5001.1  338.53  5001.6  338.03  5017.6  338.53  5017.7  340.77  5032.3  346.82
  5059.4  346.73  5073.9  344.36    5105   345.3    5139  347.16  5217.7  349.72
  5282.3   356.1  5367.7  359.89  5391.5  362.62  5459.4  369.11  5495.8  370.81
#Mann= 13 ,-1 , 0
  4181.9     .07       0  4490.8    .035       0  4505.2     .05       0
  4646.4      .1       0  4765.2     .05       0  4787.7      .1       0
  4902.4     .05       0  4924.1      .1       0  5001.1     .05       0
  5017.6      .1       0    5105    .035       0    5139      .1       0
  5391.5     .12       0
Bank Sta=5001.1,5017.6
XS Rating Curve= 0 ,0
Exp/Cntr=0.3,0.1

Type RM Length L Ch R = 1 ,15777   ,899,899,899
BEGIN DESCRIPTION:
Stream0278 29.0
END DESCRIPTION:
XS GIS Cut Line= 3
      2408325.02     13741425.02        2407825.       13740825.
      2407424.97     13740624.99
#Sta/Elev= 30
  4223.5  362.87  4260.8  361.37  4461.3  354.56  4692.1  346.72  4705.8  345.01
  4742.3  344.05  4756.6  341.53  4798.7  345.81    4862  347.68  4968.8  346.38
  4983.1  338.91  4989.1  338.19  4989.6  337.69  5005.6  338.19  5007.4  340.27
  5035.3  341.61  5040.9  343.22  5057.7  341.37  5063.3  343.48    5080  341.37
  5085.6  345.68    5094  347.54  5102.4  345.69    5108  349.84  5196.6  351.39
  5218.2  351.67  5327.6  355.33  5353.9  357.16  5393.1  362.69  5451.8  365.85
#Mann= 9 ,-1 , 0
  4223.5     .07       0  4260.8    .035       0  4461.3     .05       0
  4798.7      .1       0  4989.1     .05       0  5005.6      .1       0
  5196.6    .045       0  5218.2    .035       0  5327.6     .12       0
Bank Sta=4989.1,5005.6
XS Rating Curve= 0 ,0
Exp/Cntr=0.3,0.1