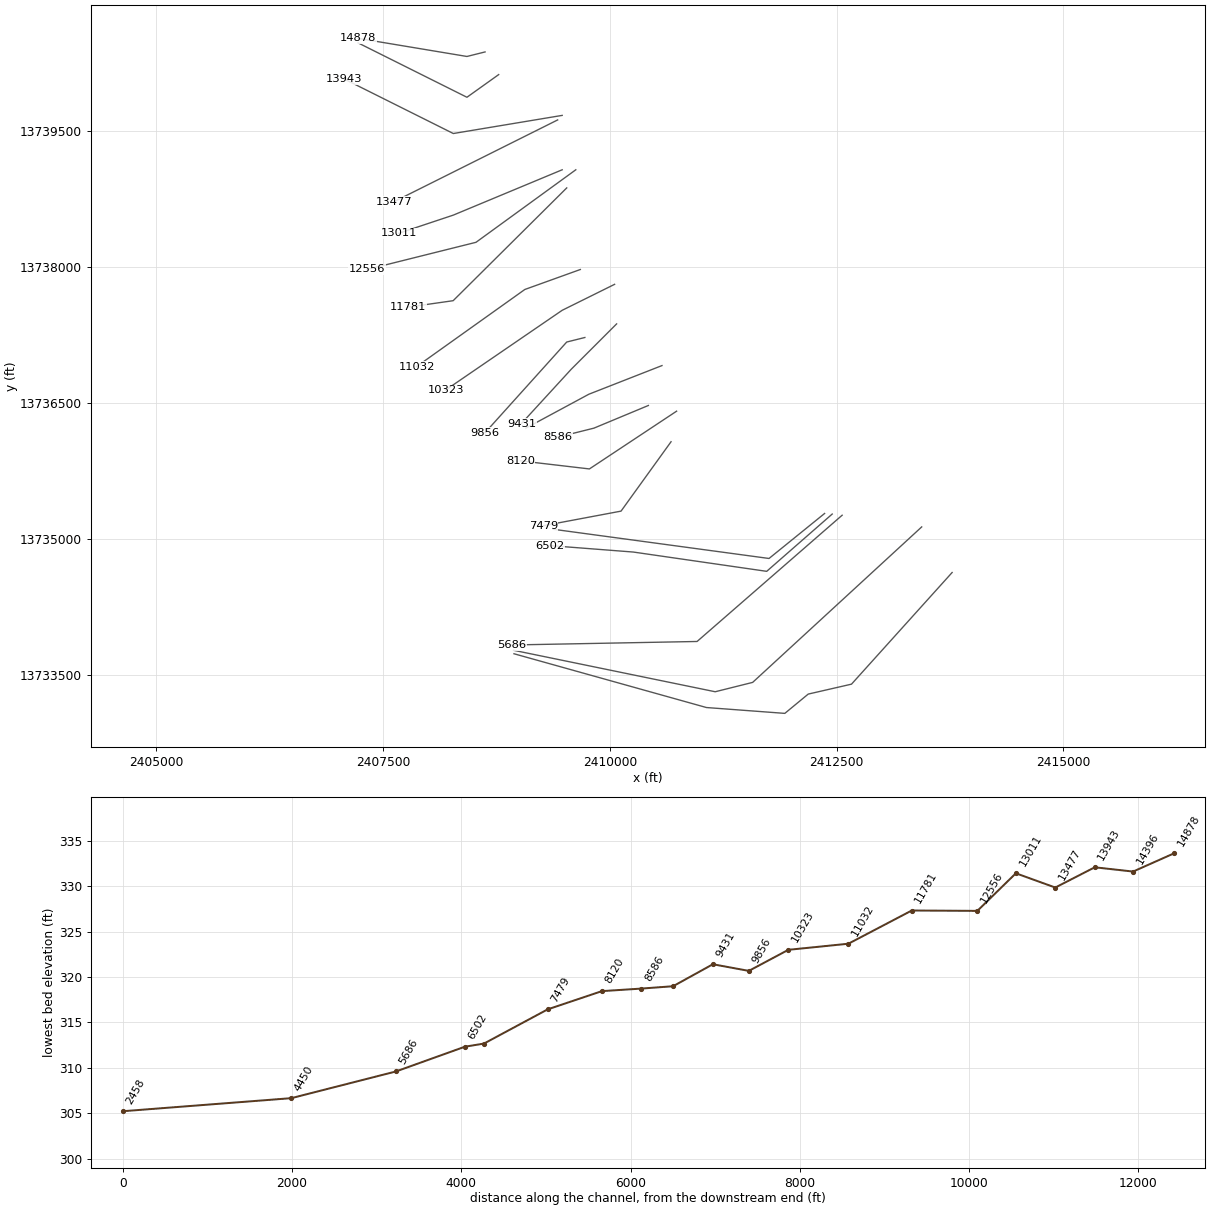
HEC-RAS study Stream0278.prj: Stream0278 Base Level Engineering

--- Stream0278.g01 (geometry) --- (continued)

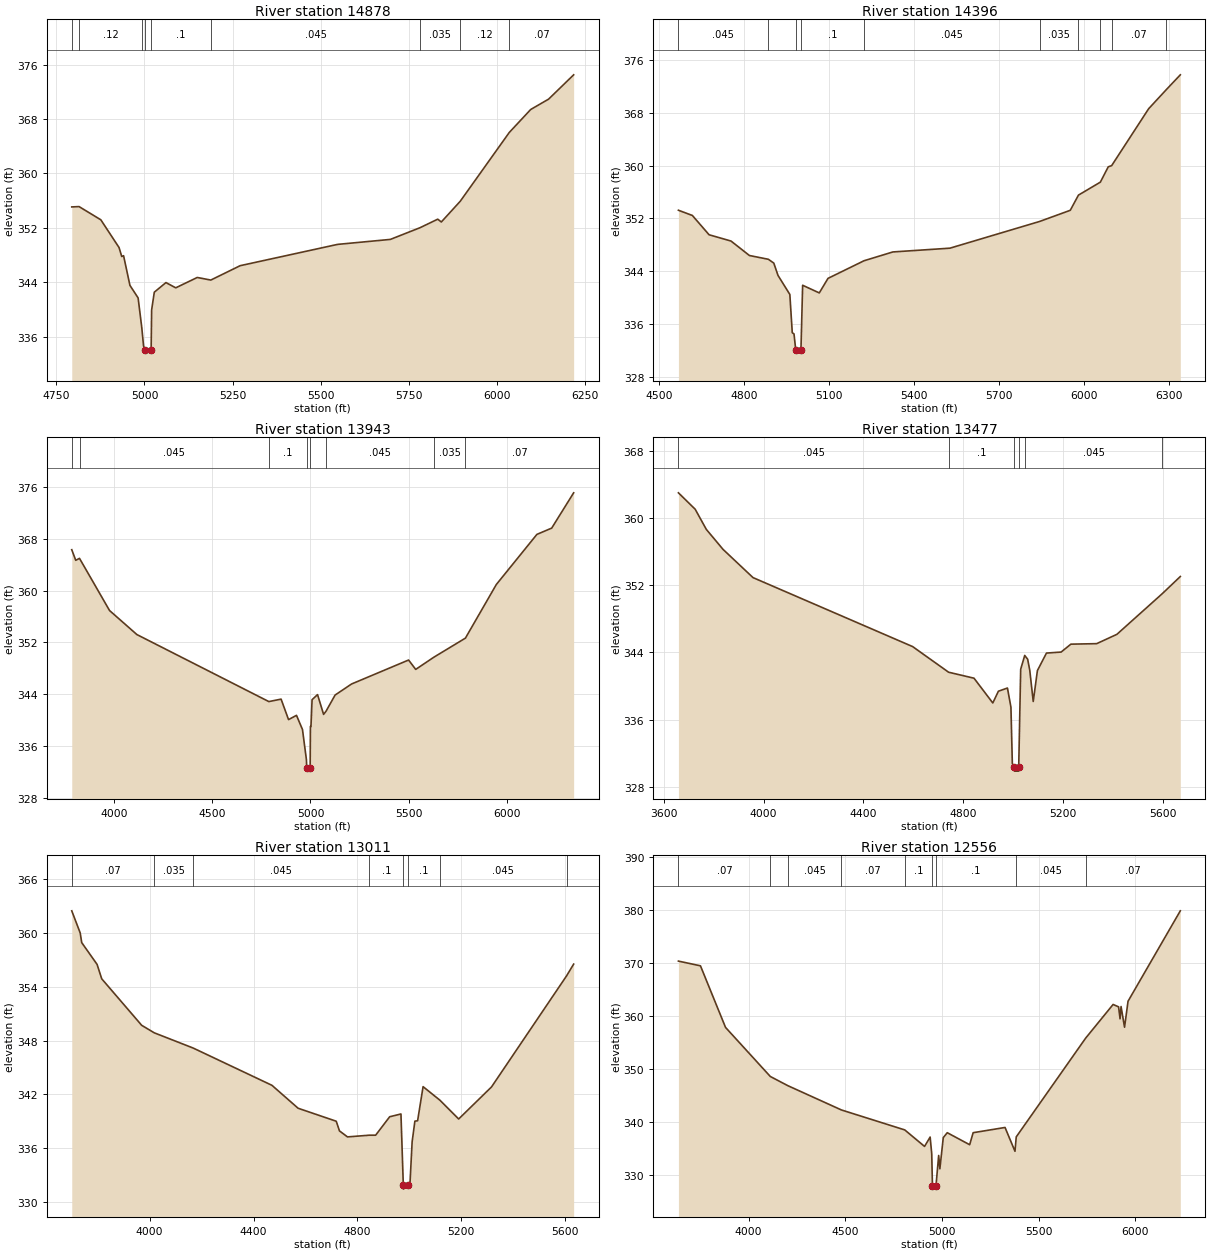
Type RM Length L Ch R = 1 ,14878   ,482,482,482
BEGIN DESCRIPTION:
Stream0278 28.0
END DESCRIPTION:
XS GIS Cut Line= 3
      2408624.97     13740374.99        2408425.       13740325.
      2407224.98       13740525.
#Sta/Elev= 30
  4793.9  355.09  4814.6  355.14  4876.3   353.2  4927.9  349.13  4935.6  347.81
  4940.8  347.93  4958.8  343.57    4982  341.73  4992.4  337.36  4997.4  334.68
  5001.5  334.12    5002  333.62  5018.9  334.12  5020.3  339.96  5027.9  342.57
  5060.9  343.98  5088.7  343.21  5149.6  344.73  5188.1  344.35  5271.2  346.46
  5547.5  349.59    5697  350.32  5781.2  352.04  5831.3  353.29  5841.5  352.88
  5895.1  355.92  6034.2  366.03  6094.9   369.4  6145.6  370.92  6216.6  374.49
#Mann= 9 ,-1 , 0
  4793.9    .045       0  4814.6     .12       0  4992.4      .1       0
  5001.5     .05       0  5018.9      .1       0  5188.1    .045       0
  5781.2    .035       0  5895.1     .12       0  6034.2     .07       0
Bank Sta=5001.5,5018.9
XS Rating Curve= 0 ,0
Exp/Cntr=0.3,0.1

Type RM Length L Ch R = 1 ,14396   ,453,453,453
BEGIN DESCRIPTION:
Stream0278 27.0
END DESCRIPTION:
XS GIS Cut Line= 3
      2408775.01     13740125.01        2408425.       13739875.
      2407224.97     13740475.01
#Sta/Elev= 30
  4569.5  353.24  4618.7  352.45  4677.7  349.53  4755.1  348.58  4820.2  346.39
    4887  345.82  4906.2  345.24    4921  343.38  4962.8   340.5  4971.4   334.7
  4977.5  334.53  4983.6  332.12  4984.1  331.62    5001  332.12  5002.4  332.75
    5008  341.89  5066.7  340.73  5097.5  342.93  5224.8   345.6  5326.7  346.93
  5527.9   347.5  5844.4  351.54  5952.8  353.23  5981.7  355.53    6059  357.49
  6086.9  359.81  6098.9  359.99  6229.5   368.6    6291  371.45  6341.3  373.73
#Mann= 10 ,-1 , 0
  4569.5    .045       0    4887      .1       0  4983.6     .05       0
    5001      .1       0  5224.8    .045       0  5844.4    .035       0
  5981.7     .07       0    6059     .12       0  6098.9     .07       0
    6291     .12       0
Bank Sta=4983.6,5001
XS Rating Curve= 0 ,0
Exp/Cntr=0.3,0.1

Type RM Length L Ch R = 1 ,13943   ,466,466,466
BEGIN DESCRIPTION:
Stream0278 26.0
END DESCRIPTION:
XS GIS Cut Line= 3
      2409474.96     13739674.99        2408275.       13739475.
      2407074.96     13740075.02
#Sta/Elev= 30
  3783.4  366.35  3803.6  364.71  3822.9  365.01    3976  356.94  4115.4  353.22
    4788  342.85  4850.4  343.23  4888.4  340.06  4928.9  340.72  4959.4  338.53
  4979.6  333.84    4981  332.59  4981.5  332.09  4998.6  332.59  4999.9     339
  5002.7     339  5008.3  343.14  5036.2  343.93    5067  340.87  5079.1  341.34
  5125.7  343.86  5209.5  345.57  5500.2  349.28  5536.6  347.83  5628.8  349.71
    5790  352.67  5947.4  360.96  6154.3  368.72  6229.7  369.69  6341.6  375.15
#Mann= 8 ,-1 , 0
  3783.4     .07       0  3822.9    .045       0    4788      .1       0
    4981     .05       0  4998.6      .1       0  5079.1    .045       0
  5628.8    .035       0    5790     .07       0
Bank Sta=4981,4998.6
XS Rating Curve= 0 ,0
Exp/Cntr=0.3,0.1

Type RM Length L Ch R = 1 ,13477   ,466,466,466
BEGIN DESCRIPTION:
Stream0278 25.0
END DESCRIPTION:
XS GIS Cut Line= 3
      2409425.04     13739625.02        2408225.       13739025.
        2407625.       13738725.
#Sta/Elev= 30
  3658.3  362.98  3725.4  361.03  3770.1  358.63  3837.2  356.25  3957.4  352.89
  4597.5  344.68  4741.7  341.63  4843.5  340.92  4918.9  337.97  4941.3  339.37
  4977.6  339.75  4991.6  337.47  4997.2  330.76  5005.1  330.36  5005.6  329.86
  5022.3  329.86  5022.8  330.36  5030.7  341.98  5046.9  343.63  5058.7  343.17
  5067.1  341.86    5081  338.15  5097.8  341.83  5134.1  343.91  5192.8  344.03
    5232  344.97  5335.4  345.03  5416.5  346.14  5598.1  350.97  5670.8  353.02
#Mann= 6 ,-1 , 0
  3658.3    .045       0  4741.7      .1       0  5005.1     .05       0
  5022.8      .1       0  5046.9    .045       0  5598.1     .05       0
Bank Sta=5005.1,5022.8
XS Rating Curve= 0 ,0
Exp/Cntr=0.3,0.1

Type RM Length L Ch R = 1 ,13011   ,455,455,455
BEGIN DESCRIPTION:
Stream0278 24.0
END DESCRIPTION:
XS GIS Cut Line= 3
      2409474.98     13739074.99        2408275.       13738575.
      2407675.03     13738375.01
#Sta/Elev= 30
  3700.1   362.5  3732.6  360.03  3738.5  358.95  3797.6  356.52  3815.5  354.91
  3969.3  349.72  4017.8  348.88  4167.6  347.18  4470.9  343.02  4571.6  340.46
  4718.4  339.01  4730.9  337.93  4761.7  337.26  4845.6  337.45  4870.1  337.45
  4924.2  339.51  4967.6  339.82  4976.6  331.93  4977.1  331.43  4994.4  331.93
  5002.7  332.26  5010.6   336.7  5021.2  339.02  5031.7  339.06  5052.8  342.87
  5117.5  341.36  5189.8  339.26  5316.3  342.84  5605.3  355.24  5632.5  356.55
#Mann= 8 ,-1 , 0
  3700.1     .07       0  4017.8    .035       0  4167.6    .045       0
  4845.6      .1       0  4976.6     .05       0  4994.4      .1       0
  5117.5    .045       0  5605.3     .05       0
Bank Sta=4976.6,4994.4
XS Rating Curve= 0 ,0
Exp/Cntr=0.3,0.1

Type RM Length L Ch R = 1 ,12556   ,775,775,775
BEGIN DESCRIPTION:
Stream0278 23.0
END DESCRIPTION:
XS GIS Cut Line= 3
      2409624.97     13739074.98        2408525.       13738275.
      2407325.05     13737975.01
#Sta/Elev= 30
  3636.5  370.37  3750.5  369.48  3880.3  357.84    4112  348.57  4202.4  346.84
  4479.7  342.25  4807.4  338.48  4910.1  335.36    4939  337.13  4947.2  333.96
    4951  327.79  4951.5  327.29  4968.9  327.79  4983.1  333.65  4989.3  331.13
  5006.9  337.02  5027.5  337.95  5143.5  335.68  5161.5  337.95  5326.5  338.94
    5378  334.44  5384.5  337.16  5743.9  355.83  5885.7  362.18    5914  361.73
  5921.7  359.47  5926.9  361.79  5944.9  357.88    5963  362.79  6233.5  379.87
#Mann= 9 ,-1 , 0
  3636.5     .07       0    4112    .035       0  4202.4    .045       0
  4479.7     .07       0  4807.4      .1       0    4951     .05       0
  4968.9      .1       0  5384.5    .045       0  5743.9     .07       0
Bank Sta=4951,4968.9
XS Rating Curve= 0 ,0
Exp/Cntr=0.3,0.1

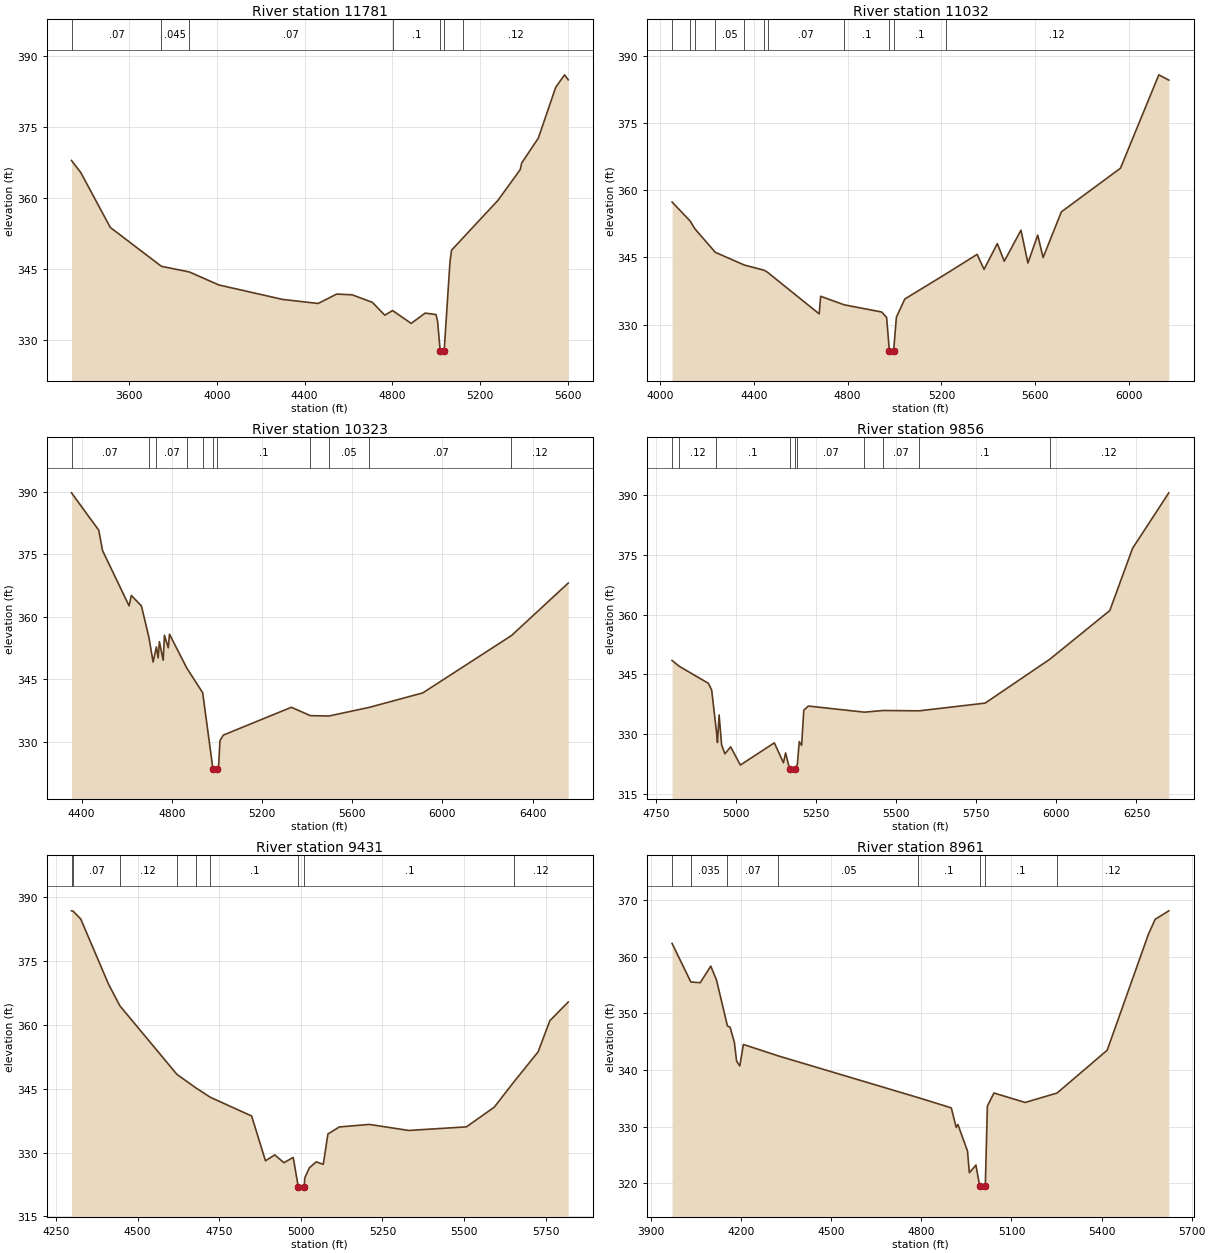
Type RM Length L Ch R = 1 ,11781   ,749,749,749
BEGIN DESCRIPTION:
Stream0278 22.0
END DESCRIPTION:
XS GIS Cut Line= 3
      2409525.03     13738875.03      2408273.02     13737630.84
      2407778.52      13737560.2
#Sta/Elev= 30
  3337.5  367.91  3379.9  365.36  3514.3  353.81  3747.3  345.62  3875.2  344.42
  4009.3  341.69  4299.2  338.65  4461.9  337.79  4546.7  339.77  4617.4  339.61
  4709.3  338.02  4765.9  335.32  4801.4   336.3  4886.1  333.59  4949.7  335.76
  4999.3  335.46  5006.3  334.09  5018.5  327.83    5019  327.33  5036.5  327.83
  5062.9  346.48    5070     349  5122.5  351.61  5282.4  359.55  5383.4     366
  5389.9  367.38  5465.7  372.61    5545  383.32  5585.5  385.95  5602.1   384.9
#Mann= 7 ,-1 , 0
  3337.5     .07       0  3747.3    .045       0  3875.2     .07       0
  4801.4      .1       0  5018.5     .05       0  5036.5      .1       0
  5122.5     .12       0
Bank Sta=5018.5,5036.5
XS Rating Curve= 0 ,0
Exp/Cntr=0.3,0.1

Type RM Length L Ch R = 1 ,11032   ,709,709,709
BEGIN DESCRIPTION:
Stream0278 21.0
END DESCRIPTION:
XS GIS Cut Line= 3
        2409675.       13737975.      2409063.27     13737754.65
      2407868.78     13736902.85
#Sta/Elev= 30
  4051.8  357.36  4128.9  353.13  4148.3  351.44    4236  346.15    4360  343.31
  4444.7  342.15    4459  341.69  4678.9  332.42  4685.2  336.35  4785.5  334.44
  4945.3  332.84  4966.2  331.63    4978  324.17  4978.5  323.67  4996.1  324.17
  5007.9  331.69  5043.8  335.74  5217.6  341.29  5352.1  345.69  5381.6  342.35
  5438.2  348.09  5467.7  344.16    5539  351.08  5568.5  343.76  5610.3  349.99
  5633.3  344.98  5711.1  355.17  5963.1  364.91  6126.5  385.73  6169.1  384.55
#Mann= 11 ,-1 , 0
  4051.8     .07       0  4128.9     .12       0  4148.3     .07       0
    4236     .05       0    4360     .07       0  4444.7     .05       0
    4459     .07       0  4785.5      .1       0    4978     .05       0
  4996.1      .1       0  5217.6     .12       0
Bank Sta=4978,4996.1
XS Rating Curve= 0 ,0
Exp/Cntr=0.3,0.1

Type RM Length L Ch R = 1 ,10323   ,467,467,467
BEGIN DESCRIPTION:
Stream0278 20.0
END DESCRIPTION:
XS GIS Cut Line= 3
       2410052.7      13737811.4        2409475.       13737525.
      2408189.61     13736644.58
#Sta/Elev= 30
  4355.2  389.73    4476  380.78  4492.8  375.89  4610.5  362.64  4620.5  365.12
  4665.2  362.62  4698.7  355.04    4717  349.16  4731.7  352.78  4739.4  350.14
    4745  354.04  4761.8  349.59  4767.4  355.58  4784.2  352.58  4789.8  355.82
  4866.6   347.7  4936.9  341.81  4982.5   323.5    4983     323  5000.7   323.5
  5007.5  324.13  5013.5  330.28  5028.4  331.64  5330.3  338.31  5414.8   336.3
  5496.9  336.22  5675.1  338.28  5913.2  341.76  6306.4  355.51    6558  368.09
#Mann= 11 ,-1 , 0
  4355.2     .07       0  4698.7     .12       0  4731.7     .07       0
  4866.6     .12       0  4936.9      .1       0  4982.5     .05       0
  5000.7      .1       0  5414.8     .07       0  5496.9     .05       0
  5675.1     .07       0  6306.4     .12       0
Bank Sta=4982.5,5000.7
XS Rating Curve= 0 ,0
Exp/Cntr=0.3,0.1

Type RM Length L Ch R = 1 ,9856    ,425,425,425
BEGIN DESCRIPTION:
Stream0278 19.0
END DESCRIPTION:
XS GIS Cut Line= 3
      2409725.04     13737225.01        2409525.       13737175.
      2408624.97     13736174.97
#Sta/Elev= 30
  4799.4   348.5  4821.6  347.04  4912.8  342.76  4923.1  341.04  4938.1  330.57
  4941.2  327.88  4946.3  334.81  4954.1   327.3  4964.4  325.03  4982.4  326.78
  5012.7  322.21  5118.8  327.79  5147.2  322.78    5154  325.26  5166.5  321.18
    5167  320.68  5184.7  321.18  5190.9  322.47  5196.6  328.09    5204  327.15
  5210.8  335.99    5225  337.04  5400.1   335.5  5458.2  335.92  5571.6  335.84
  5777.3  337.78  5979.5  348.82  6166.7  361.05  6237.7  376.68    6351  390.64
#Mann= 10 ,-1 , 0
  4799.4     .07       0  4821.6     .12       0  4938.1      .1       0
  5166.5     .05       0  5184.7      .1       0  5190.9     .07       0
  5400.1      .1       0  5458.2     .07       0  5571.6      .1       0
  5979.5     .12       0
Bank Sta=5166.5,5184.7
XS Rating Curve= 0 ,0
Exp/Cntr=0.3,0.1

Type RM Length L Ch R = 1 ,9431    ,470,470,470
BEGIN DESCRIPTION:
Stream0278 18.0
END DESCRIPTION:
XS GIS Cut Line= 3
      2410075.03     13737375.03        2409575.       13736875.
        2409025.     13736274.99
#Sta/Elev= 30
  4297.9  386.83  4302.6  386.77  4326.2  384.91  4411.1  369.62    4446  364.51
  4620.4  348.41  4679.4  345.17  4723.3  342.99  4849.5   338.6  4891.9  328.07
  4920.2  329.46  4948.5  327.62  4976.8  328.87  4992.4  321.91  4992.9  321.41
  5010.6  321.91  5012.1  324.03  5026.3  326.42  5047.3  327.82  5068.9  327.24
  5083.1  334.37  5118.2  336.03  5210.1  336.62  5330.6   335.2  5507.3  336.05
  5592.4  340.67    5654  346.75  5726.8  353.68  5762.6  360.99    5819   365.4
#Mann= 9 ,-1 , 0
  4297.9     .12       0  4302.6     .07       0    4446     .12       0
  4620.4     .07       0  4679.4     .12       0  4723.3      .1       0
  4992.4     .05       0  5010.6      .1       0    5654     .12       0
Bank Sta=4992.4,5010.6
XS Rating Curve= 0 ,0
Exp/Cntr=0.3,0.1

Type RM Length L Ch R = 1 ,8961    ,375,375,375
BEGIN DESCRIPTION:
Stream0278 17.0
END DESCRIPTION:
XS GIS Cut Line= 3
      2410574.95      13736915.1      2409768.96     13736599.15
        2409075.       13736225.
#Sta/Elev= 30
  3969.8  362.36  4032.3  355.56  4063.5  355.43  4098.7  358.36  4117.8  355.89
  4154.1   347.8  4163.1  347.57  4177.4  344.85  4184.6   341.6  4195.3  340.73
  4207.2  344.53  4323.5  342.51  4790.3  335.13  4899.7  333.33  4915.9  329.89
  4921.6   330.4  4953.6   325.7  4959.7  321.88  4981.6  323.23  4994.3  319.49
  4994.8  318.99  5012.8  319.49  5019.7  333.64  5041.6  335.96  5145.4  334.29
  5251.7  335.95  5418.7  343.51  5555.8  363.96  5578.5  366.63  5623.9  368.12
#Mann= 8 ,-1 , 0
  3969.8     .07       0  4032.3    .035       0  4154.1     .07       0
  4323.5     .05       0  4790.3      .1       0  4994.3     .05       0
  5012.8      .1       0  5251.7     .12       0
Bank Sta=4994.3,5012.8
XS Rating Curve= 0 ,0
Exp/Cntr=0.3,0.1

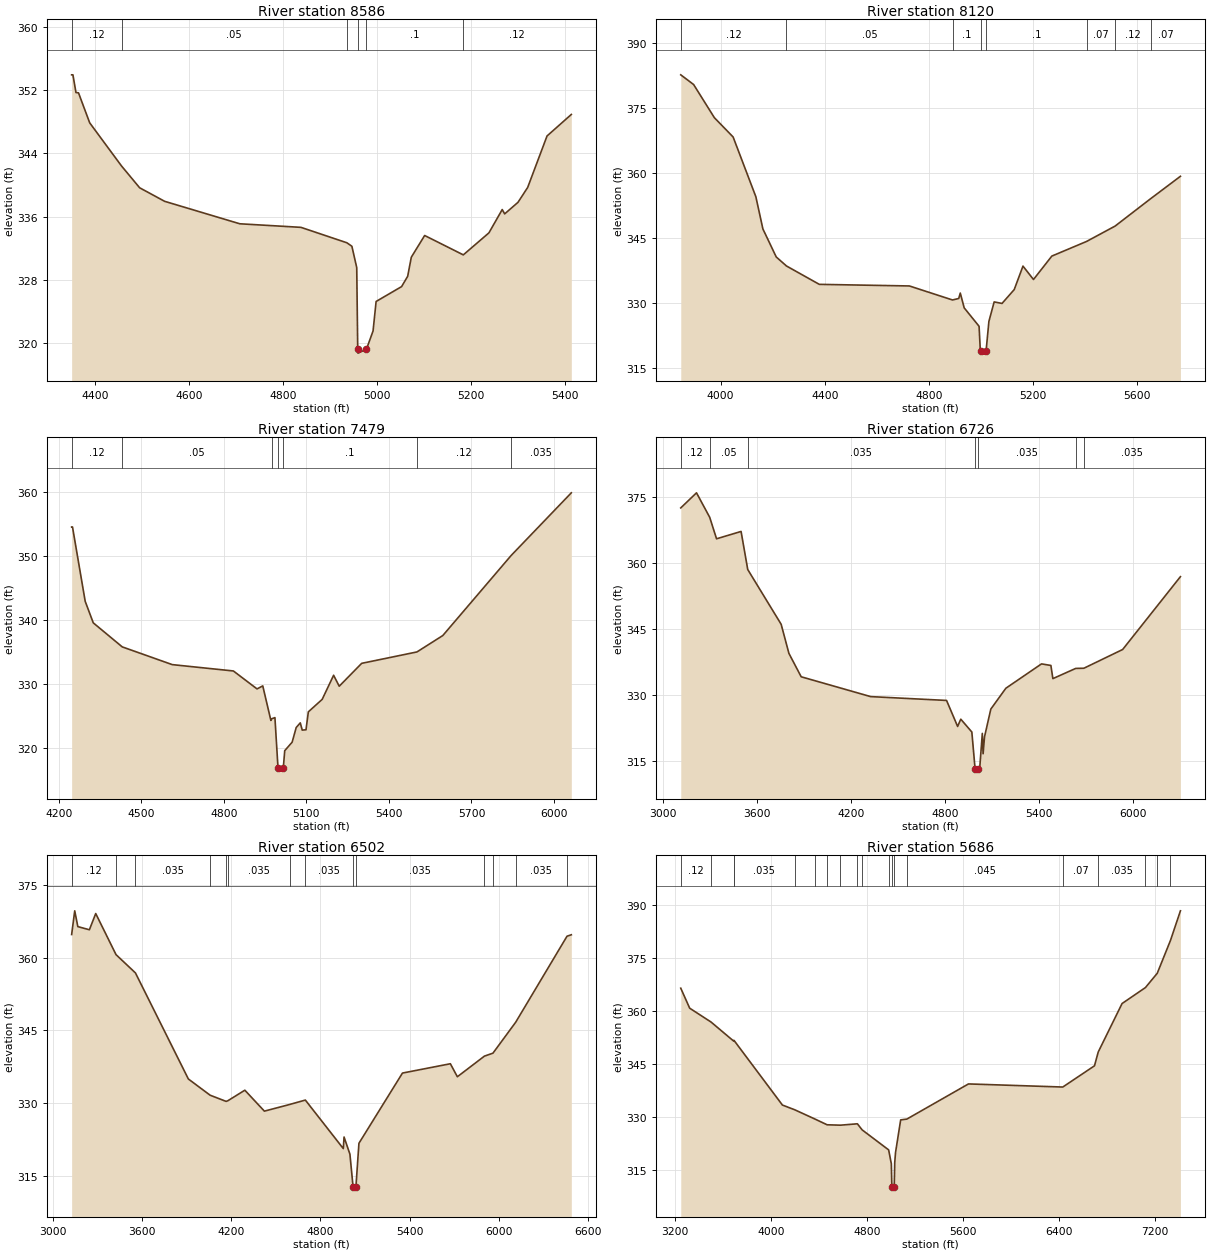
Type RM Length L Ch R = 1 ,8586    ,466,466,466
BEGIN DESCRIPTION:
Stream0278 16.0
END DESCRIPTION:
XS GIS Cut Line= 3
      2410424.98     13736474.99        2409825.       13736225.
      2409424.99       13736125.
#Sta/Elev= 30
  4350.5  353.91  4353.2  353.91  4359.7  351.67  4365.1  351.63  4388.9  347.84
  4456.5  342.39  4495.1  339.63  4548.2  337.92    4708  335.08    4838  334.63
  4935.6  332.68  4946.3  332.24  4956.6  329.54  4958.7  319.23  4959.2  318.73
  4977.3  319.23  4991.3  321.53  4997.8  325.26    5052  327.14  5064.9  328.44
  5072.6  330.85    5101   333.6  5183.2  331.15  5237.6  333.93  5265.9  336.88
  5271.1  336.33  5299.4  337.79    5320  339.67  5361.2  346.18  5412.8   348.9
#Mann= 6 ,-1 , 0
  4350.5     .12       0  4456.5     .05       0  4935.6      .1       0
  4958.7     .05       0  4977.3      .1       0  5183.2     .12       0
Bank Sta=4958.7,4977.3
XS Rating Curve= 0 ,0
Exp/Cntr=0.3,0.1

Type RM Length L Ch R = 1 ,8120    ,641,641,641
BEGIN DESCRIPTION:
Stream0278 15.0
END DESCRIPTION:
XS GIS Cut Line= 3
      2410736.14     13736412.14        2409775.       13735775.
      2409014.54     13735864.08
#Sta/Elev= 30
  3846.7  382.63  3896.1  380.39  3975.7  372.75  4047.8  368.29  4135.1  354.51
  4162.1  347.09  4213.3  340.63  4252.5  338.55  4378.7  334.31  4724.6  333.94
  4890.2  330.71  4914.1  331.05  4920.1   332.3  4935.2  328.88  4992.3  324.64
  4996.8  319.26  5000.6  318.95  5001.1  318.45  5019.2  318.95    5030  325.77
  5050.2  330.26  5080.4  329.91  5127.2   333.1  5160.9  338.52  5201.2  335.43
  5271.7  340.83  5404.9   344.2  5514.7  347.75  5652.1  354.11  5765.5  359.23
#Mann= 8 ,-1 , 0
  3846.7     .12       0  4252.5     .05       0  4890.2      .1       0
  5000.6     .05       0  5019.2      .1       0  5404.9     .07       0
  5514.7     .12       0  5652.1     .07       0
Bank Sta=5000.6,5019.2
XS Rating Curve= 0 ,0
Exp/Cntr=0.3,0.1

Type RM Length L Ch R = 1 ,7479    ,753,753,753
BEGIN DESCRIPTION:
Stream0278 14.0
END DESCRIPTION:
XS GIS Cut Line= 3
      2410675.01     13736075.01      2410123.61     13735309.54
      2409266.01     13735148.34
#Sta/Elev= 30
    4247  354.54  4250.1  354.54  4296.3  342.93  4325.6  339.58  4430.8  335.83
  4612.7  333.06  4834.8  332.07  4920.8  329.27  4941.6  329.74  4971.1  324.35
  4974.1  324.61  4985.8  324.79    4997  316.94  4997.5  316.44  5016.3  316.94
  5021.4  319.63  5048.4  320.96  5063.1  323.24  5077.9  323.97  5085.1  322.84
  5098.7  322.89  5107.3  325.69  5157.6  327.64  5199.1   331.4  5219.5  329.69
  5301.1  333.26    5502  335.04    5596   337.6  5844.3  350.09    6063  359.87
#Mann= 7 ,-1 , 0
    4247     .12       0  4430.8     .05       0  4974.1      .1       0
    4997     .05       0  5016.3      .1       0    5502     .12       0
  5844.3    .035       0
Bank Sta=4997,5016.3
XS Rating Curve= 0 ,0
Exp/Cntr=0.3,0.1

Type RM Length L Ch R = 1 ,6726    ,224,224,224
BEGIN DESCRIPTION:
XS6316
END DESCRIPTION:
XS GIS Cut Line= 3
      2412367.52     13735283.74      2411754.96     13734787.25
       2409375.6     13735109.66
#Sta/Elev= 30
  3111.6  372.51  3212.1  375.94  3296.3  370.38    3340  365.49  3496.6  367.16
  3539.2   358.5  3752.4  346.06    3802  339.44  3880.3  334.12  4323.9  329.61
  4808.3  328.74  4878.9  322.83  4899.1  324.48  4969.7  321.56  4990.4  313.17
  4990.9  312.67  5009.7  313.17  5020.2  313.46  5036.5  321.25  5041.6  316.62
  5050.5  320.44  5090.8  326.77  5186.7  331.51  5414.4  337.05  5474.3  336.69
    5487   333.7  5632.7  336.02  5684.9  336.06  5932.4  340.32  6301.2  356.88
#Mann= 7 ,-1 , 0
  3111.6     .12       0  3296.3     .05       0  3539.2    .035       0
  4990.4    .035       0  5009.7    .035       0  5632.7      .1       0
  5684.9    .035       0
Bank Sta=4990.4,5009.7
XS Rating Curve= 0 ,0
Exp/Cntr=0.3,0.1

Type RM Length L Ch R = 1 ,6502    ,816,816,816
BEGIN DESCRIPTION:
XS6315
END DESCRIPTION:
XS GIS Cut Line= 4
      2412451.38     13735277.33      2411729.17      13734645.4
      2410259.02     13734858.18      2409343.38     13734929.11
#Sta/Elev= 30
  3125.3  364.76    3146  369.64  3166.9  366.39  3244.7  365.74  3287.4  369.08
    3424  360.62  3554.8  356.85    3911  335.01  4057.5  331.67    4165   330.4
  4176.1  330.52  4291.2   332.7  4422.6  328.39  4592.7  329.76  4698.4  330.67
  4953.9  320.68    4959  323.06  4998.5  319.53  5019.6  312.83  5020.1  312.33
    5039  312.83  5059.2  321.77  5352.2  336.23  5674.7  338.15  5721.7  335.47
    5904  339.72  5961.4  340.33  6114.4   346.7  6459.9  364.41  6488.8  364.71
#Mann= 14 ,-1 , 0
  3125.3     .12       0    3424     .05       0  3554.8    .035       0
  4057.5     .07       0    4165     .05       0  4176.1    .035       0
  4592.7      .1       0  4698.4    .035       0  5019.6    .035       0
    5039    .035       0    5904     .07       0  5961.4     .12       0
  6114.4    .035       0  6459.9     .12       0
Bank Sta=5019.6,5039
XS Rating Curve= 0 ,0
Exp/Cntr=0.3,0.1

Type RM Length L Ch R = 1 ,5686    ,1236,1236,1236
BEGIN DESCRIPTION:
XS6314
END DESCRIPTION:
XS GIS Cut Line= 3
        2412561.     13735264.43      2410961.85     13733871.63
      2408918.87     13733832.96
#Sta/Elev= 30
  3245.6   366.5  3319.9  360.84  3497.5  356.93  3685.1  351.56  3688.9  351.74
  4092.7  333.41  4194.6  332.08  4363.6  329.45  4465.2  327.82  4576.6  327.71
  4717.4   328.1  4757.1  326.38    4978  320.71  5000.4  316.77  5004.9   310.1
  5005.4   309.6  5024.3   310.1  5028.8  317.17  5035.5  319.99  5078.2  329.21
  5129.6  329.43  5643.2  339.39  6429.2  338.51  6693.3  344.52  6724.5  348.42
  6923.4  362.16  7118.1  366.68  7216.5  370.73  7326.8  380.04  7409.6  388.41
#Mann= 19 ,-1 , 0
  3245.6     .12       0  3497.5    .035       0  3685.1     .05       0
  3688.9    .035       0  4194.6     .07       0  4363.6     .05       0
  4465.2     .07       0  4576.6     .05       0  4717.4     .07       0
  4757.1     .05       0    4978      .1       0  5004.9     .05       0
  5024.3      .1       0  5129.6    .045       0  6429.2     .07       0
  6724.5    .035       0  7118.1     .07       0  7216.5     .12       0
  7326.8     .07       0
Bank Sta=5004.9,5024.3
XS Rating Curve= 0 ,0
Exp/Cntr=0.3,0.1

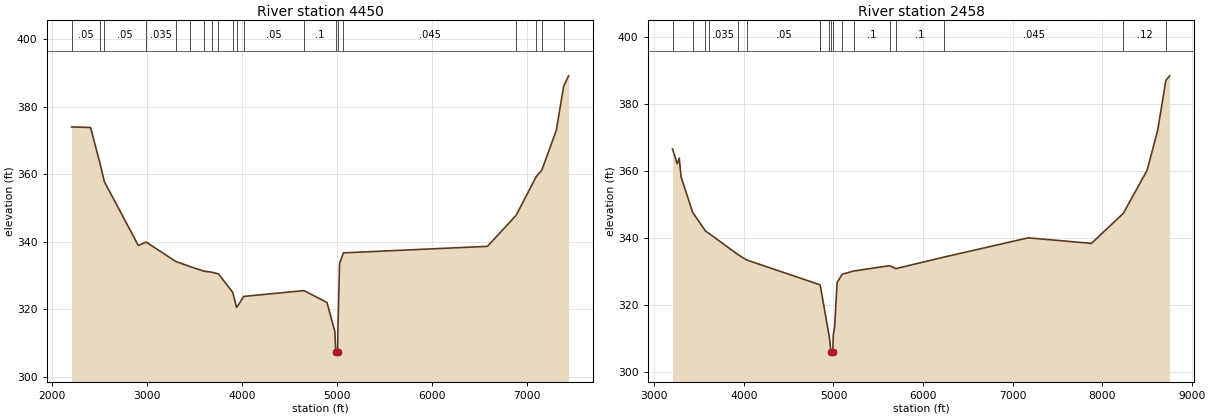
Type RM Length L Ch R = 1 ,4450    ,1992,1992,1992
BEGIN DESCRIPTION:
XS6313
END DESCRIPTION:
XS GIS Cut Line= 4
      2413437.87     13735135.42      2411574.42     13733420.27
      2411161.74      13733317.1      2408938.54     13733774.63
#Sta/Elev= 30
    2210  374.04  2410.5  373.87  2512.3  362.91  2555.1  357.82  2912.9  338.87
  2994.4   339.9  3305.5  334.15  3455.6  332.64  3605.6  331.25  3685.5  330.95
  3755.7  330.46  3905.8  324.97  3946.2  320.46  4021.9  323.78  4654.5   325.5
  4896.6  321.98  4979.1  313.37    4990  307.16  4990.5  306.66  5009.4  307.16
    5010  312.64  5028.9  333.47  5069.4  336.69  6583.8  338.62  6885.3  347.79
  7097.1  359.29  7156.8  361.28  7308.7  373.04  7385.3  386.07  7437.8  389.19
#Mann= 20 ,-1 , 0
    2210     .05       0  2512.3    .035       0  2555.1     .05       0
  2994.4    .035       0  3305.5     .07       0  3455.6     .05       0
  3605.6    .035       0  3685.5     .07       0  3755.7    .035       0
  3905.8     .05       0  3946.2      .1       0  4021.9     .05       0
  4654.5      .1       0    4990     .05       0  5009.4      .1       0
  5069.4    .045       0  6885.3     .12       0  7097.1     .07       0
  7156.8     .12       0  7385.3     .07       0
Bank Sta=4990,5009.4
XS Rating Curve= 0 ,0
Exp/Cntr=0.3,0.1

Type RM Length L Ch R = 1 ,2458    ,0,0,0
BEGIN DESCRIPTION:
XS6312
END DESCRIPTION:
XS GIS Cut Line= 6
      2413773.19     13734632.48      2412664.14     13733400.92
      2412186.98      13733291.3      2411929.06     13733078.52
      2411065.02       13733143.      2408943.62     13733736.22
#Sta/Elev= 30
  3202.3  366.61  3255.7  362.17  3277.4  363.86  3298.3  358.26  3427.3  347.64
  3569.8  342.08  3611.8  341.29  3928.5  335.09    4031  333.38  4849.4  325.96
  4852.9  325.67  4955.2  310.05    4972  305.72  4972.5  305.22  4991.7  305.72
  4997.5  310.99  5012.6  313.29  5040.3  326.64  5097.1  329.11  5223.8  330.08
    5626  331.68  5696.1   330.8  6238.3  334.28  7174.2  340.01    7880  338.35
    8237  347.36  8501.9  360.22  8619.9  372.19  8711.4  387.13  8752.8  388.48
#Mann= 18 ,-1 , 0
  3202.3     .05       0  3427.3    .035       0  3569.8     .05       0
  3611.8    .035       0  3928.5     .07       0    4031     .05       0
  4849.4    .035       0  4852.9     .12       0  4955.2      .1       0
    4972     .05       0  4991.7      .1       0  5097.1     .12       0
  5223.8      .1       0    5626     .12       0  5696.1      .1       0
  6238.3    .045       0    8237     .12       0  8711.4     .07       0
Bank Sta=4972,4991.7
XS Rating Curve= 0 ,0
Exp/Cntr=0.3,0.1

Chan Stop Cuts=-1
Use User Specified Reach Order=0
Composite Channel Slope=5