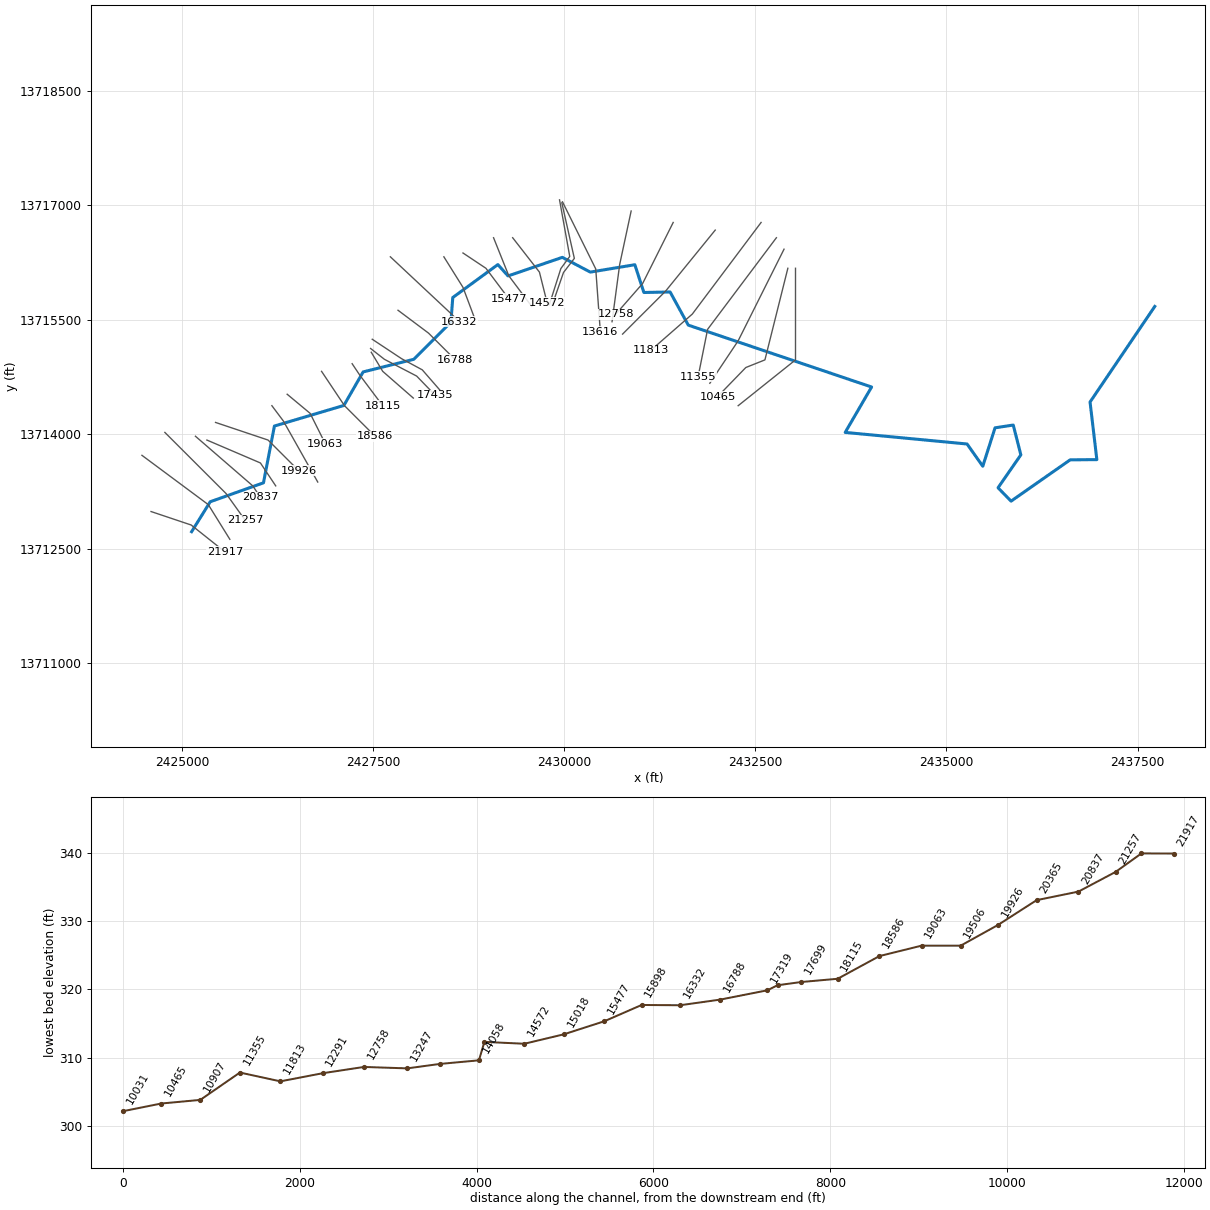
--- Stream0280.prj (project) ---

Proj Title=Stream0280 Base Level Engineering
Current Plan=p01
Default Exp/Contr=0.3,0.1
English Units
Geom File=g01
Flow File=f01
Plan File=p01
Y Axis Title=Elevation
X Axis Title(PF)=Main Channel Distance
X Axis Title(XS)=Station
BEGIN DESCRIPTION:
Stream0280
END DESCRIPTION:
DSS Export Rating Curves= 0
DSS Export Rating Curve Sorted= 0
DSS Export Volume Flow Curves= 0
DXF OffsetX= 0
DXF OffsetY= 0
DXF ScaleX= 1
DXF ScaleY= 10

--- Stream0280.p01 (plan) ---

Plan Title=Multiple Run
Short Identifier=Multiple
Geom File=g01
Flow File=f01
Subcritical Flow
K Sum by GR= 0
Std Step Tol= 0.01
Critical Tol= 0.01
Num of Std Step Trials= 20
Max Error Tol= 0.3
Flow Tol Ratio= 0.001
Split Flow NTrial= 30
Split Flow Tol= 0.02
Split Flow Ratio= 0.02
Log Output Level= 0
Friction Slope Method= 1
Unsteady Friction Slope Method= 2
Unsteady Bridges Friction Slope Method= 1
Parabolic Critical Depth
Global Vel Dist=  1 , 1 , 1
Global Log Level= 0
CheckData=True
Encroach Param= -1, 0, 0, 0
BEGIN DESCRIPTION:
Multiple Run
END DESCRIPTION:

--- Stream0280.f01 (steady flow) ---

Flow Title=Multiple
Number of Profiles=7
Profile Names=10-year,25-year,50-year,1pct_min,100-year,1pct_plu,500-year
River Rch & RM= Stream0280,Reach-1,21917
     669    1077    1444     938    1871    3733    3109
River Rch & RM= Stream0280,Reach-1,19926
     849    1386    1876    1228    2451    4890    4145
River Rch & RM= Stream0280,Reach-1,19506
    1602    2691    3713    2472    4932    9840    8628
River Rch & RM= Stream0280,Reach-1,9116
    1631    2739    3778    2515    5017   10011    8773
River Rch & RM= Stream0280,Reach-1,7324
    2302    3924    5466    3670    7323   14612   13037
River Rch & RM= Stream0280,Reach-1,1542
    2422    4120    5733    3844    7670   15304   13612
Boundary for River Rch & Prof#=Stream0280,Reach-1,1
Up Type=0
Dn Type=3
Dn Slope=0.005
Boundary for River Rch & Prof#=Stream0280,Reach-1,2
Up Type=0
Dn Type=3
Dn Slope=0.005
Boundary for River Rch & Prof#=Stream0280,Reach-1,3
Up Type=0
Dn Type=3
Dn Slope=0.005
Boundary for River Rch & Prof#=Stream0280,Reach-1,4
Up Type=0
Dn Type=3
Dn Slope=0.005
Boundary for River Rch & Prof#=Stream0280,Reach-1,5
Up Type=0
Dn Type=3
Dn Slope=0.005
Boundary for River Rch & Prof#=Stream0280,Reach-1,6
Up Type=0
Dn Type=3
Dn Slope=0.005
Boundary for River Rch & Prof#=Stream0280,Reach-1,7
Up Type=0
Dn Type=3
Dn Slope=0.005

--- Stream0280.g01 (geometry) ---

Geom Title=Existing Conditions
Program Version=4.10

River Reach=Stream0280      ,Reach-1
Reach XY= 30
        2425125.       13712725.      2425368.81     13713117.14
      2426064.98     13713364.95      2426208.08     13714108.61
      2427116.66     13714378.16      2427368.81     13714817.25
      2428031.19     13714982.86       2428517.2     13715468.79
      2428541.39     13715791.67      2429131.21     13716223.22
       2429264.7     13716074.49        2429975.     13716317.93
      2430340.71     13716124.76      2430923.55     13716221.47
      2431041.27     13715857.68      2431384.79     13715864.48
      2431621.98     13715430.46      2434020.41     13714619.84
        2433675.       13714025.      2435269.17     13713873.47
      2435475.01     13713582.07      2435635.32     13714085.18
      2435873.78     13714121.57      2435972.86     13713730.97
      2435674.49     13713299.96      2435844.98     13713124.96
      2436618.27     13713665.89       2436967.2     13713668.79
      2436878.34     13714423.28        2437725.       13715675.

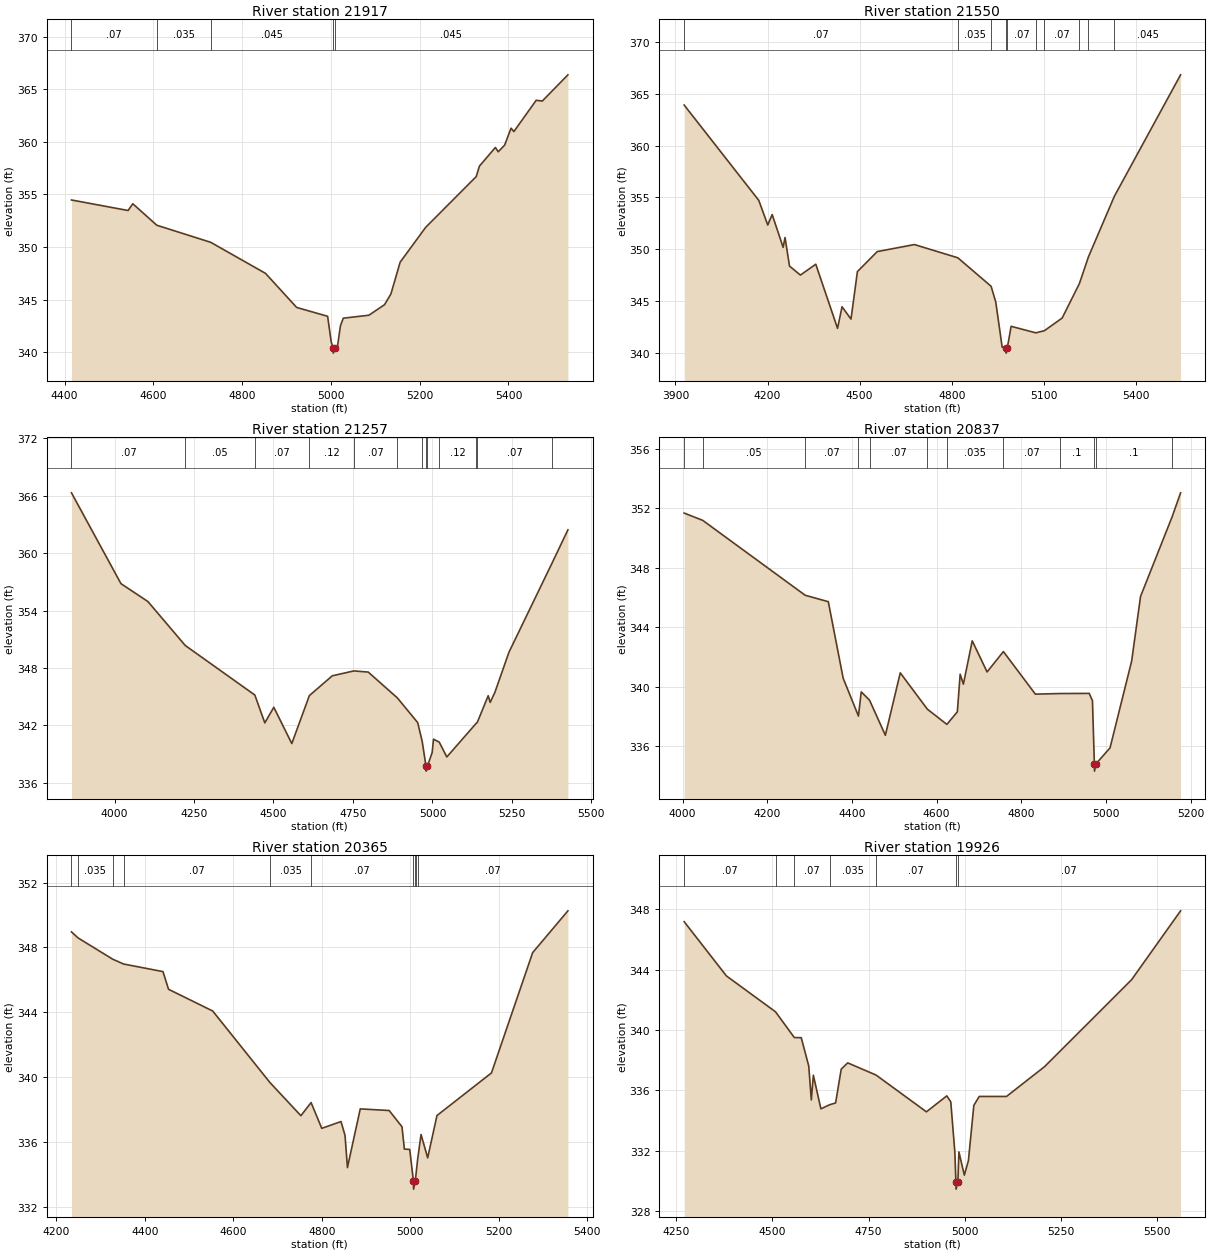
Type RM Length L Ch R = 1 ,21917   ,367,367,367
BEGIN DESCRIPTION:
XS6331
END DESCRIPTION:
XS GIS Cut Line= 3
      2424594.11     13712988.74      2425119.44      13712812.2
      2425560.92     13712460.73
#Sta/Elev= 30
  4415.5  354.47    4543  353.47  4553.6  354.11  4607.8  352.07  4729.1  350.45
  4852.6   347.5  4922.8  344.26  4992.6  343.42  5000.7  340.99    5005  340.42
  5005.2  339.92  5009.1  340.42  5015.1  340.64  5021.5  342.52  5027.9  343.24
  5085.5  343.52  5120.8  344.52  5135.2  345.54    5156  348.56  5213.7  351.88
  5327.4  356.69  5334.7  357.69  5370.6  359.46    5377  359.05  5391.4  359.68
  5405.9  361.29  5412.3  360.97  5462.5  363.94  5476.3  363.87    5534  366.36
#Mann= 5 ,-1 , 0
  4415.5     .07       0  4607.8    .035       0  4729.1    .045       0
    5005    .045       0  5009.1    .045       0
Bank Sta=5005,5009.1
XS Rating Curve= 0 ,0
Exp/Cntr=0.3,0.1

Type RM Length L Ch R = 1 ,21550   ,293,293,293
BEGIN DESCRIPTION:
Stream0280 35.0
END DESCRIPTION:
XS GIS Cut Line= 3
      2424475.02     13713724.99      2425343.36     13713079.18
      2425625.01     13712624.98
#Sta/Elev= 30
  3928.5  363.91  4171.5   354.7  4200.7  352.32  4215.1  353.33  4250.8  350.16
    4257  351.11  4271.6  348.35    4307  347.48  4357.1  348.53    4428  342.33
  4442.6  344.42  4471.8  343.23  4492.7  347.82  4557.3  349.75  4678.3  350.43
  4819.8  349.15    4928   346.4  4943.2  344.88  4964.1  340.51  4976.6  340.44
  4976.9  339.94  4980.7  340.44  4993.3  342.53  5073.5   341.9  5101.8  342.11
  5159.4  343.33  5215.7  346.67    5245  349.24  5329.5   355.1  5545.1  366.83
#Mann= 10 ,-1 , 0
  3928.5     .07       0  4819.8    .035       0    4928     .07       0
  4976.6     .05       0  4980.7     .07       0  5073.5     .12       0
  5101.8     .07       0  5215.7    .045       0    5245     .12       0
  5329.5    .045       0
Bank Sta=4976.6,4980.7
XS Rating Curve= 0 ,0
Exp/Cntr=0.3,0.1

Type RM Length L Ch R = 1 ,21257   ,420,420,420
BEGIN DESCRIPTION:
Stream0280 34.0
END DESCRIPTION:
XS GIS Cut Line= 3
      2424774.98     13714025.02        2425575.       13713225.
      2425824.99     13712875.02
#Sta/Elev= 30
  3864.6   366.3  4020.2  356.81    4105  354.94  4222.4  350.35  4441.4  345.17
  4472.7  342.26    4501  343.89  4557.6   340.1  4612.8  345.11  4684.9  347.18
  4752.8  347.69    4798  347.57  4889.7  344.87  4953.6  342.29  4967.5  340.37
  4979.8  337.72  4980.1  337.22  4983.9  337.72  4999.1  339.16  5003.4  340.56
  5021.4  340.25  5045.2   338.7  5137.3   342.2    5141  342.31  5175.4   345.1
  5181.6   344.4  5196.3  345.44  5240.6  349.64  5377.1  359.02  5426.1  362.43
#Mann= 13 ,-1 , 0
  3864.6     .07       0  4222.4     .05       0  4441.4     .07       0
  4612.8     .12       0  4752.8     .07       0  4889.7    .035       0
  4967.5     .07       0  4979.8     .05       0  4983.9     .07       0
  5021.4     .12       0  5137.3      .1       0    5141     .07       0
  5377.1     .12       0
Bank Sta=4979.8,4983.9
XS Rating Curve= 0 ,0
Exp/Cntr=0.3,0.1

Type RM Length L Ch R = 1 ,20837   ,472,472,472
BEGIN DESCRIPTION:
Stream0280 33.0
END DESCRIPTION:
XS GIS Cut Line= 3
      2425175.02     13713974.99        2425925.       13713325.
      2426024.98     13713175.02
#Sta/Elev= 30
  4003.5  351.67  4047.4  351.18  4289.4  346.15    4344  345.72  4379.1  340.58
  4415.2  338.04  4421.8  339.66  4441.5   339.1  4478.8  336.75    4514  340.94
    4578   338.5  4624.1  337.48  4648.8  338.32  4655.5  340.85  4663.1  340.18
    4684  343.09  4719.1     341  4757.6  342.37  4833.1  339.51  4891.2  339.55
  4960.3  339.56    4968  339.07  4972.5  334.84  4972.8  334.34  4976.6  334.84
  5009.5   335.9  5060.6  341.73  5081.6  346.07  5156.2  351.42  5176.2  353.03
#Mann= 12 ,-1 , 0
  4003.5     .07       0  4047.4     .05       0  4289.4     .07       0
  4415.2     .12       0  4441.5     .07       0    4578     .12       0
  4624.1    .035       0  4757.6     .07       0  4891.2      .1       0
  4972.5     .05       0  4976.6      .1       0  5156.2     .07       0
Bank Sta=4972.5,4976.6
XS Rating Curve= 0 ,0
Exp/Cntr=0.3,0.1

Type RM Length L Ch R = 1 ,20365   ,439,439,439
BEGIN DESCRIPTION:
Stream0280 32.0
END DESCRIPTION:
XS GIS Cut Line= 3
      2425324.96     13713925.02        2426025.       13713625.
      2426225.02     13713324.98
#Sta/Elev= 30
  4234.1  348.96  4248.9  348.59    4327  347.28  4351.7  346.98  4440.9  346.51
  4453.5  345.42  4553.3  344.08  4682.6  339.67  4752.7  337.62  4775.7  338.43
  4799.9  336.84  4843.4  337.26  4852.5   336.4  4857.9  334.42  4886.9  338.04
  4952.2  337.94  4981.2  336.94  4986.6  335.56  4998.7  335.54  5007.1  333.59
  5007.4  333.09  5011.3  333.59  5012.6  333.92  5016.6  334.93  5024.3  336.46
  5039.3  335.02  5060.3  337.63  5183.5  340.26  5276.6  347.68  5356.3  350.26
#Mann= 10 ,-1 , 0
  4234.1     .05       0  4248.9    .035       0    4327     .05       0
  4351.7     .07       0  4682.6    .035       0  4775.7     .07       0
  5007.1     .05       0  5011.3     .07       0  5012.6     .12       0
  5016.6     .07       0
Bank Sta=5007.1,5011.3
XS Rating Curve= 0 ,0
Exp/Cntr=0.3,0.1

Type RM Length L Ch R = 1 ,19926   ,420,420,420
BEGIN DESCRIPTION:
Stream0280 31.0
END DESCRIPTION:
XS GIS Cut Line= 3
      2425438.09     13714155.72        2426125.       13713925.
      2426524.99     13713525.01
#Sta/Elev= 30
  4270.7  347.19  4380.5  343.59  4508.1  341.21    4557   339.5    4575  339.49
  4594.5  337.61  4601.2  335.36  4606.5     337  4626.1  334.77  4648.8  335.04
  4664.3  335.16  4678.9   337.4  4695.8  337.82  4769.5  337.01  4900.4  334.57
  4953.3  335.63  4963.7  335.23  4974.2  331.91    4977  329.94  4977.4  329.44
  4982.1  329.94  4984.8  331.91  4998.9  330.37  5009.5  331.33  5023.6     335
  5037.7  335.59  5108.5  335.59  5207.5  337.57  5433.7  343.34    5561  347.91
#Mann= 7 ,-1 , 0
  4270.7     .07       0  4508.1     .12       0    4557     .07       0
  4648.8    .035       0  4769.5     .07       0    4977     .05       0
  4982.1     .07       0
Bank Sta=4977,4982.1
XS Rating Curve= 0 ,0
Exp/Cntr=0.3,0.1

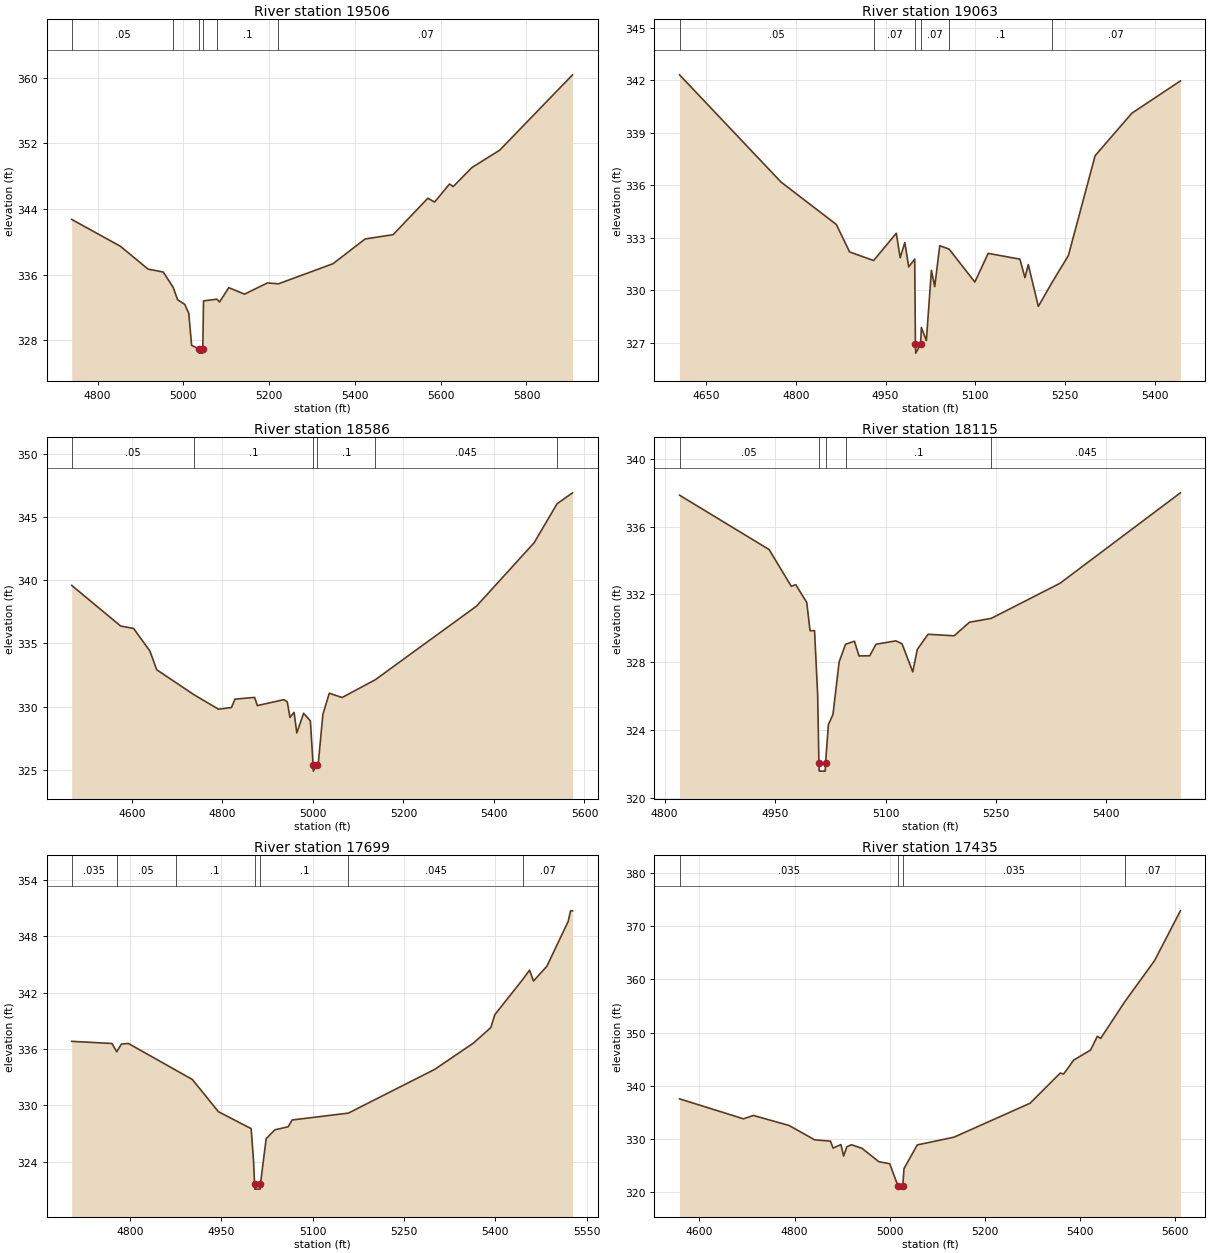
Type RM Length L Ch R = 1 ,19506   ,443,443,443
BEGIN DESCRIPTION:
Stream0280 30.0
END DESCRIPTION:
XS GIS Cut Line= 3
        2426175.       13714375.        2426325.       13714175.
      2426775.01     13713374.99
#Sta/Elev= 30
  4739.6  342.72  4853.1  339.45  4917.7  336.66  4953.1  336.31  4976.3  334.43
  4986.5  332.93  5003.3  332.36  5012.6  331.27  5019.2  327.37  5036.6  326.92
  5037.1  326.42  5044.8  326.42  5045.3  326.92    5047  332.79  5078.4     333
  5084.3  332.65  5105.9   334.4  5142.6  333.61  5196.1  334.98  5221.7  334.87
  5348.8  337.32    5424  340.34    5489  340.86    5570   345.3  5585.9  344.84
  5620.6  347.04  5629.3  346.73  5672.6  349.04  5737.6  351.16  5907.5  360.35
#Mann= 6 ,-1 , 0
  4739.6     .05       0  4976.3     .07       0  5036.6     .05       0
  5045.3     .07       0  5078.4      .1       0  5221.7     .07       0
Bank Sta=5036.6,5045.3
XS Rating Curve= 0 ,0
Exp/Cntr=0.3,0.1

Type RM Length L Ch R = 1 ,19063   ,477,477,477
BEGIN DESCRIPTION:
Stream0280 29.0
END DESCRIPTION:
XS GIS Cut Line= 3
      2426374.97     13714525.03        2426675.       13714275.
      2426875.01     13713874.97
#Sta/Elev= 30
  4605.3  342.32  4775.2  336.19  4867.6  333.77  4889.8   332.2    4930  331.71
  4967.9  333.27  4974.4  331.87  4982.2  332.74  4988.7  331.35  4998.7  331.79
  4999.9  326.92  5000.4  326.42  5008.6  326.92  5009.8  327.89  5018.2  327.14
  5026.6  331.15  5032.2  330.22  5040.6  332.56  5056.3  332.36  5099.3  330.48
  5121.6  332.12  5174.7  331.79  5183.1  330.73  5188.7  331.48  5205.5  329.09
  5228.7  330.47  5255.8     332  5300.5   337.7    5362  340.13  5443.1  341.97
#Mann= 6 ,-1 , 0
  4605.3     .05       0    4930     .07       0  4999.9     .05       0
  5008.6     .07       0  5056.3      .1       0  5228.7     .07       0
Bank Sta=4999.9,5008.6
XS Rating Curve= 0 ,0
Exp/Cntr=0.3,0.1

Type RM Length L Ch R = 1 ,18586   ,471,471,471
BEGIN DESCRIPTION:
Stream0280 28.0
END DESCRIPTION:
XS GIS Cut Line= 3
        2426825.       13714825.        2427125.       13714375.
      2427524.98     13713975.02
#Sta/Elev= 30
  4467.2   339.6  4575.4  336.38  4603.9  336.19    4640   334.4    4655  332.92
  4737.9  330.93  4791.7  329.79  4820.2  329.93  4827.8  330.59  4871.3  330.73
  4877.3  330.08  4935.9  330.55  4943.4  330.38  4949.4  329.14  4958.5  329.55
  4964.5  327.91  4979.5  329.47  4994.5  328.87  5000.5  325.39    5001  324.89
  5009.5  325.39  5011.6  325.39  5022.2  329.39  5036.3  331.06  5064.6  330.72
    5138  332.13  5361.6  337.96  5488.9  342.98  5539.7  346.07  5573.7  346.93
#Mann= 6 ,-1 , 0
  4467.2     .05       0  4737.9      .1       0  5000.5     .05       0
  5009.5      .1       0    5138    .045       0  5539.7     .07       0
Bank Sta=5000.5,5009.5
XS Rating Curve= 0 ,0
Exp/Cntr=0.3,0.1

Type RM Length L Ch R = 1 ,18115   ,416,416,416
BEGIN DESCRIPTION:
Stream0280 27.0
END DESCRIPTION:
XS GIS Cut Line= 3
      2427224.99     13714925.02        2427325.       13714775.
        2427625.       13714375.
#Sta/Elev= 30
  4820.2  337.86  4941.9  334.65    4972  332.48    4978  332.58    4993  331.53
  4997.5  329.86  5003.6  329.86  5007.8   326.1  5009.5  322.07    5010  321.57
  5018.1  321.57  5018.6  322.07  5022.4  324.32  5028.6  324.91    5037  328.02
  5045.7  329.06  5057.8  329.24    5064  328.37  5078.6  328.38    5087  329.06
    5114  329.26  5122.4  329.09    5137  327.43  5143.2  328.76  5157.8  329.65
  5193.2  329.56    5214  330.36  5243.7  330.59    5337  332.66  5500.5     338
#Mann= 5 ,-1 , 0
  4820.2     .05       0  5009.5     .05       0  5018.6     .05       0
  5045.7      .1       0  5243.7    .045       0
Bank Sta=5009.5,5018.6
XS Rating Curve= 0 ,0
Exp/Cntr=0.3,0.1

Type RM Length L Ch R = 1 ,17699   ,264,264,264
BEGIN DESCRIPTION:
Stream0280 26.0
END DESCRIPTION:
XS GIS Cut Line= 3
      2427474.98     13715075.03        2427625.       13714825.
        2428025.       13714475.
#Sta/Elev= 30
  4703.9  336.82    4770  336.59  4777.9  335.71  4785.6  336.53  4797.2  336.59
    4875  333.75  4902.2  332.76    4945  329.33  4998.8  327.53  5002.6  324.24
  5004.5  321.59    5005  321.09  5013.5  321.09    5014  321.59  5023.5  326.46
  5037.7   327.4  5059.6  327.73  5066.2  328.45  5158.6  329.18  5300.6  333.84
  5364.2  336.64  5392.7  338.29  5399.3  339.66  5445.8  343.46  5456.3   344.4
  5462.9  343.24  5484.8  344.81  5519.9  349.59  5523.7  350.71    5527  350.71
#Mann= 7 ,-1 , 0
  4703.9    .035       0  4777.9     .05       0    4875      .1       0
  5004.5     .05       0    5014      .1       0  5158.6    .045       0
  5445.8     .07       0
Bank Sta=5004.5,5014
XS Rating Curve= 0 ,0
Exp/Cntr=0.3,0.1

Type RM Length L Ch R = 1 ,17435   ,116,116,116
BEGIN DESCRIPTION:
XS6330
END DESCRIPTION:
XS GIS Cut Line= 4
      2427466.28     13715124.62      2427647.16      13714982.5
      2428069.16     13714762.89      2428310.14      13714513.3
#Sta/Elev= 30
  4558.2  337.56  4692.6  333.81  4713.4  334.44  4788.2  332.57  4842.4  329.86
  4875.3  329.63    4881  328.32  4897.4  328.98  4903.1  326.83  4909.8  328.57
  4919.5  328.95  4941.6  328.28  4977.4  325.75    5000  325.39  5017.7  321.12
  5018.2  320.62  5027.3  321.12    5030  324.46  5057.8  328.91  5134.9  330.36
  5294.9  336.73  5358.4  342.39  5365.6  342.22  5386.7  344.83  5422.2  346.71
  5436.4   349.3  5443.3  348.89  5494.3  355.81  5556.5  363.47  5610.9  372.83
#Mann= 4 ,-1 , 0
  4558.2    .035       0  5017.7    .035       0  5027.3    .035       0
  5494.3     .07       0
Bank Sta=5017.7,5027.3
XS Rating Curve= 0 ,0
Exp/Cntr=0.3,0.1

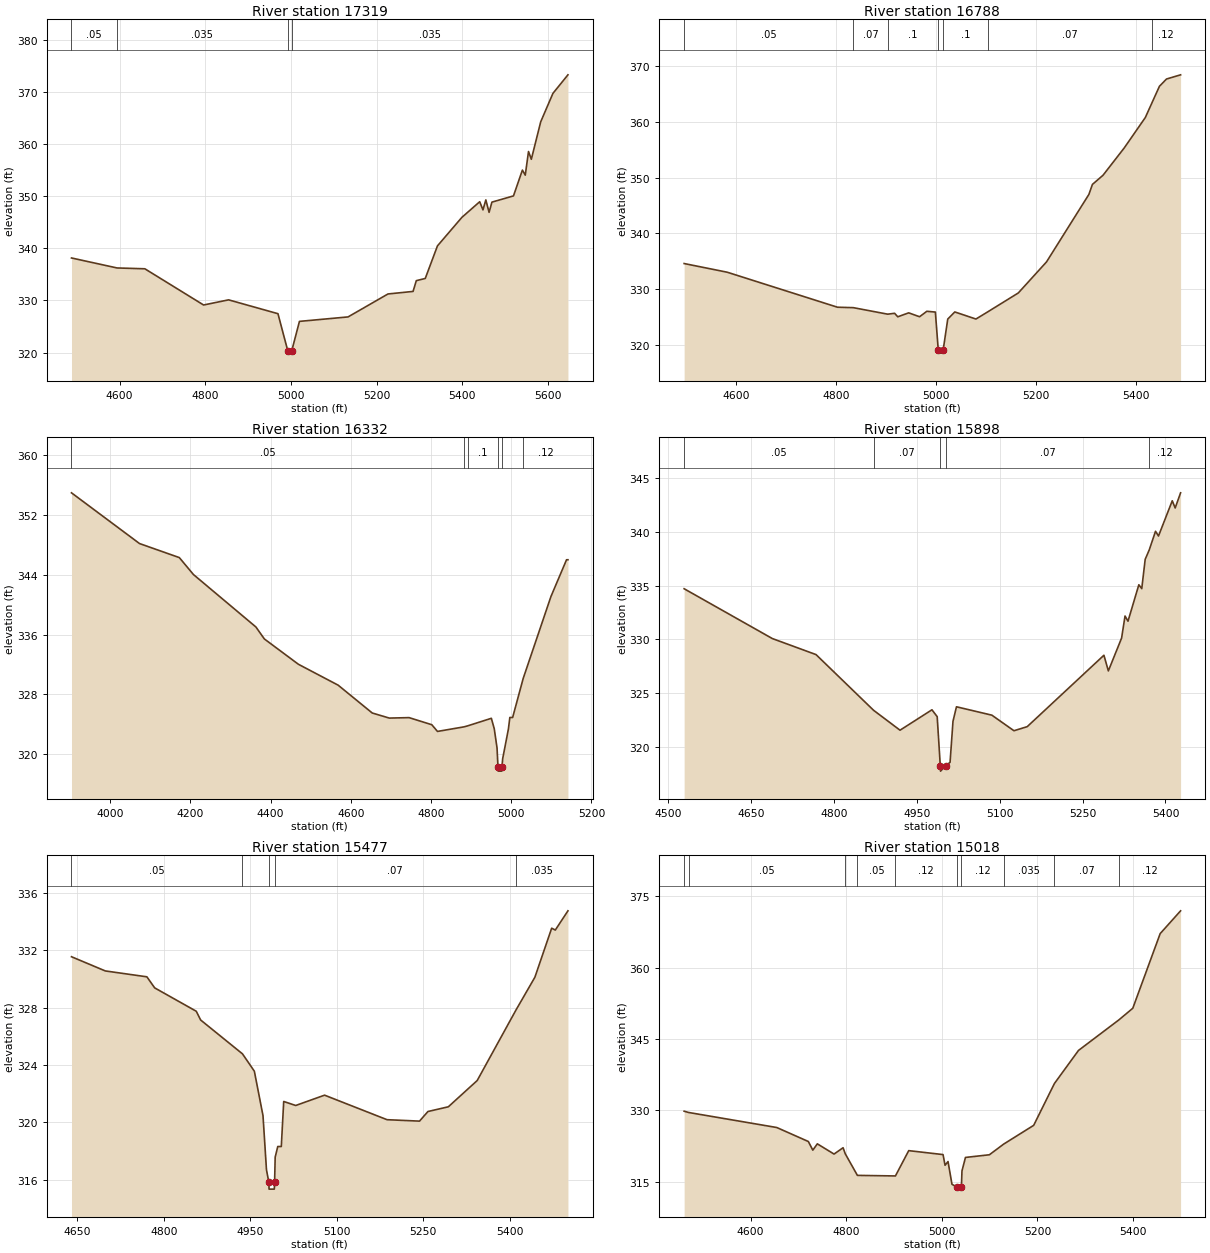
Type RM Length L Ch R = 1 ,17319   ,531,531,531
BEGIN DESCRIPTION:
Stream0280 25.0
END DESCRIPTION:
XS GIS Cut Line= 4
      2427487.81     13715245.19      2427871.08     13714991.11
      2428142.36      13714844.7      2428399.32     13714549.21
#Sta/Elev= 30
  4487.5  338.17  4593.9  336.25  4658.9  336.09  4796.1  329.13  4854.5  330.12
  4969.8  327.46  4992.6  320.38  4993.1  319.88  5002.2  320.38    5020  325.98
  5133.6  326.84  5226.8  331.25  5285.4  331.74    5293  333.81  5313.9  334.23
  5342.4  340.49  5399.4  345.97  5441.1  348.98  5448.7  347.41  5455.4  349.33
    5463  346.94  5469.6   348.9    5520   350.1  5540.8  355.06  5547.5  354.09
  5555.1  358.63  5561.7  357.14  5583.6  364.34  5612.1   369.8  5647.2  373.37
#Mann= 4 ,-1 , 0
  4487.5     .05       0  4593.9    .035       0  4992.6    .035       0
  5002.2    .035       0
Bank Sta=4992.6,5002.2
XS Rating Curve= 0 ,0
Exp/Cntr=0.3,0.1

Type RM Length L Ch R = 1 ,16788   ,456,456,456
BEGIN DESCRIPTION:
Stream0280 24.0
END DESCRIPTION:
XS GIS Cut Line= 3
      2427825.02     13715624.98        2428225.       13715325.
      2428574.97     13714975.03
#Sta/Elev= 30
  4495.4   334.6  4581.8  333.04  4802.7  326.76  4834.5  326.68  4903.4  325.51
  4917.2  325.67  4923.5  325.04  4945.4  325.75  4967.2  325.05  4981.8  326.03
  4998.9  325.89  5004.7  319.02  5005.2  318.52  5013.9  318.52  5014.4  319.02
  5023.7  324.63  5037.8  325.91  5080.2  324.64  5103.9  325.93  5165.1  329.32
  5221.6  334.89  5306.5     347  5313.6   348.8  5334.8  350.44  5377.2  355.33
  5419.6   360.8    5433  363.46  5447.9  366.41  5462.1  367.72  5490.3  368.47
#Mann= 7 ,-1 , 0
  4495.4     .05       0  4834.5     .07       0  4903.4      .1       0
  5004.7     .05       0  5014.4      .1       0  5103.9     .07       0
    5433     .12       0
Bank Sta=5004.7,5014.4
XS Rating Curve= 0 ,0
Exp/Cntr=0.3,0.1

Type RM Length L Ch R = 1 ,16332   ,434,434,434
BEGIN DESCRIPTION:
Stream0280 23.0
END DESCRIPTION:
XS GIS Cut Line= 3
      2427725.01     13716324.99        2428525.       13715575.
      2428625.01     13715474.99
#Sta/Elev= 30
  3903.4  354.99  4073.1  348.19  4172.3  346.31  4207.5  344.04  4363.3  337.01
  4384.3  335.41  4469.3  332.01  4568.4  329.21  4653.4  325.48  4695.9   324.8
  4745.2  324.86  4801.9  323.91  4816.1  323.01  4881.8  323.62    4891  323.75
  4950.4  324.77  4957.7  323.36  4964.6  320.79    4967  318.19  4967.5  317.69
  4976.2  317.69  4976.7  318.19  4978.7  319.37  4992.9  323.32  4996.5  324.88
  5003.5  324.88  5029.8  330.11    5099  341.09  5137.9  346.02  5141.4  346.02
#Mann= 6 ,-1 , 0
  3903.4     .05       0  4881.8     .07       0    4891      .1       0
    4967     .05       0  4976.7      .1       0  5029.8     .12       0
Bank Sta=4967,4976.7
XS Rating Curve= 0 ,0
Exp/Cntr=0.3,0.1

Type RM Length L Ch R = 1 ,15898   ,421,421,421
BEGIN DESCRIPTION:
Stream0280 22.0
END DESCRIPTION:
XS GIS Cut Line= 3
      2428424.99     13716325.02        2428675.       13715925.
      2428824.99     13715525.02
#Sta/Elev= 30
  4528.5  334.71  4688.3  330.07  4767.3  328.58  4871.4   323.4  4919.4  321.54
  4977.2  323.44  4986.7   322.8  4992.3  318.23  4992.8  317.73  5002.3  318.23
    5010  318.55  5015.3  322.37  5021.6  323.72  5085.7  322.94  5125.7  321.49
  5149.7  321.87  5288.6  328.52  5296.6  327.06  5320.6  330.12  5326.8  332.17
  5332.2  331.69  5351.8  335.08  5357.1  334.72  5363.3  337.45  5370.6  338.32
    5382  340.06  5387.4  339.62  5412.3   342.9  5417.6  342.23  5427.4  343.64
#Mann= 5 ,-1 , 0
  4528.5     .05       0  4871.4     .07       0  4992.3     .05       0
  5002.3     .07       0  5370.6     .12       0
Bank Sta=4992.3,5002.3
XS Rating Curve= 0 ,0
Exp/Cntr=0.3,0.1

Type RM Length L Ch R = 1 ,15477   ,459,459,459
BEGIN DESCRIPTION:
Stream0280 21.0
END DESCRIPTION:
XS GIS Cut Line= 3
      2428674.99     13716375.01        2428975.       13716175.
      2429275.02     13715774.97
#Sta/Elev= 30
  4640.1  331.55  4698.7  330.56  4770.8  330.15  4784.3  329.38  4856.4  327.75
    4864  327.14  4936.5  324.78  4957.1  323.57  4972.1  320.47  4978.1   316.7
  4982.1  315.85  4982.6  315.35  4991.7  315.35  4992.2  315.85  4993.2  317.58
  4997.7  318.32  5003.8  318.32    5008  321.46  5028.8  321.18  5078.8   321.9
  5187.1  320.19  5243.4  320.09    5258  320.76  5293.4  321.09  5343.4  322.92
  5410.4  327.82  5443.4  330.12  5472.5  333.54  5478.8  333.41  5500.7  334.75
#Mann= 5 ,-1 , 0
  4640.1     .05       0  4936.5     .07       0  4982.1     .05       0
  4992.2     .07       0  5410.4    .035       0
Bank Sta=4982.1,4992.2
XS Rating Curve= 0 ,0
Exp/Cntr=0.3,0.1

Type RM Length L Ch R = 1 ,15018   ,446,446,446
BEGIN DESCRIPTION:
Stream0280 20.0
END DESCRIPTION:
XS GIS Cut Line= 3
      2429075.02     13716574.96        2429275.       13716075.
      2429575.02     13715674.98
#Sta/Elev= 30
    4461  329.81  4470.5  329.54  4654.8  326.38  4720.8  323.44  4730.2  321.62
  4739.6  322.95  4774.6   320.8  4793.5  322.13  4798.1  320.85  4823.4  316.32
    4903   316.2  4930.8  321.52  5002.6  320.69  5006.8  318.45    5013  319.23
  5021.3  314.44  5030.8  313.93  5031.3  313.43    5041  313.93  5042.2  317.26
  5049.5  320.09  5099.5  320.65  5129.5   322.9  5192.2  326.84  5235.5  335.62
  5285.9  342.58  5370.5  349.01  5399.5  351.45  5456.8  367.14  5499.5  371.93
#Mann= 10 ,-1 , 0
    4461     .07       0  4470.5     .05       0  4798.1     .12       0
  4823.4     .05       0    4903     .12       0  5030.8     .05       0
    5041     .12       0  5129.5    .035       0  5235.5     .07       0
  5370.5     .12       0
Bank Sta=5030.8,5041
XS Rating Curve= 0 ,0
Exp/Cntr=0.3,0.1

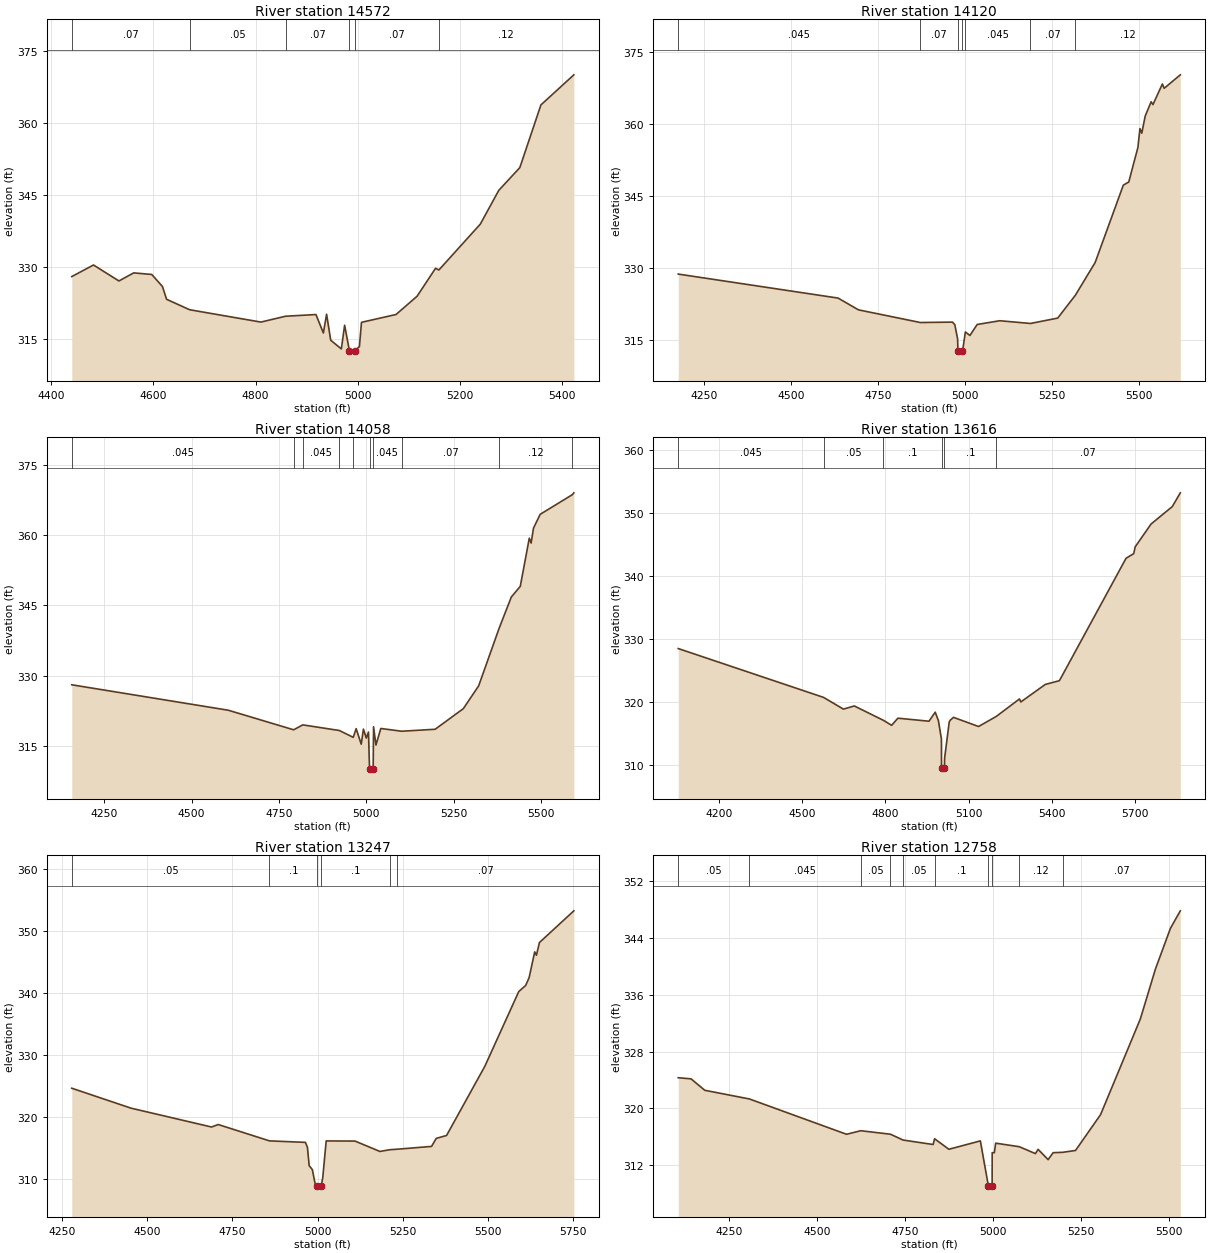
Type RM Length L Ch R = 1 ,14572   ,452,452,452
BEGIN DESCRIPTION:
Stream0280 19.0
END DESCRIPTION:
XS GIS Cut Line= 3
      2429325.01     13716574.99        2429675.       13716125.
        2429775.     13715724.99
#Sta/Elev= 30
  4440.2  327.98  4482.7  330.39  4532.5  327.07  4561.4  328.75  4596.7  328.42
  4617.6  325.92  4625.7  323.26  4670.8  321.08  4810.3  318.51  4858.6  319.73
    4918  320.08  4932.5  316.25  4938.8  320.15  4946.9  314.73  4967.7  312.93
  4974.1  317.86  4983.5  312.55    4984  312.05  4993.7  312.55    5003   313.4
  5007.1  318.46  5074.7  320.09  5115.9  323.89    5152  329.71  5158.5  329.35
  5239.6   338.9  5275.7  345.92  5316.9  350.66  5358.2  363.71  5422.6  369.97
#Mann= 6 ,-1 , 0
  4440.2     .07       0  4670.8     .05       0  4858.6     .07       0
  4983.5     .05       0  4993.7     .07       0  5158.5     .12       0
Bank Sta=4983.5,4993.7
XS Rating Curve= 0 ,0
Exp/Cntr=0.3,0.1

Type RM Length L Ch R = 1 ,14120   ,62,62,62
BEGIN DESCRIPTION:
Stream0280 18.0
END DESCRIPTION:
XS GIS Cut Line= 4
      2429938.04     13717070.98      2430071.53     13716330.33
      2429955.26       13716171.      2429804.97     13715698.66
#Sta/Elev= 30
  4174.8  328.79    4635  323.79  4693.6  321.34  4871.7   318.7  4964.4  318.78
  4971.1  318.24  4979.1   315.3  4980.1  312.82  4980.6  312.32  4990.5  312.82
  4993.8  312.95  5001.5  316.73  5014.6     316  5035.5  318.29  5100.4  319.07
  5188.9   318.5  5267.3  319.62  5318.2  324.39  5375.2  331.21  5456.2  347.32
  5471.9  347.98  5498.2  355.18  5504.1  359.11  5509.4  358.15  5519.2  361.71
  5536.3  364.69  5541.6  364.11  5568.6   368.4  5573.8   367.5  5620.3  370.31
#Mann= 7 ,-1 , 0
  4174.8    .045       0  4871.7     .07       0  4980.1     .05       0
  4990.5     .07       0  5001.5    .045       0  5188.9     .07       0
  5318.2     .12       0
Bank Sta=4980.1,4990.5
XS Rating Curve= 0 ,0
Exp/Cntr=0.3,0.1

Type RM Length L Ch R = 1 ,14058   ,442,442,442
BEGIN DESCRIPTION:
XS6329
END DESCRIPTION:
XS GIS Cut Line= 4
      2429968.18     13717032.21      2430131.81     13716304.49
      2429989.71     13716119.33      2429839.48     13715685.81
#Sta/Elev= 30
  4156.6  328.06  4604.7  322.63  4792.1  318.45  4818.3   319.5  4922.8   318.3
  4962.8  316.84  4971.2  318.69  4985.7  315.38    4992  318.59  5000.2  316.68
  5006.5  317.97  5009.5  310.12    5010  309.62  5019.9  310.12    5021   319.1
  5027.9   315.2  5041.8  318.73  5101.4  318.14  5197.4  318.56  5278.1  322.96
    5322  327.82  5380.6  340.11  5415.6   346.8  5441.3  349.09  5467.1  359.37
  5472.4  358.33  5479.1  361.51  5498.3  364.47  5590.7  368.68  5594.7  369.06
#Mann= 10 ,-1 , 0
  4156.6    .045       0  4792.1     .05       0  4818.3    .045       0
  4922.8      .1       0  4962.8    .045       0  5009.5    .045       0
  5019.9    .045       0  5101.4     .07       0  5380.6     .12       0
  5590.7     .07       0
Bank Sta=5009.5,5019.9
XS Rating Curve= 0 ,0
Exp/Cntr=0.3,0.1

Type RM Length L Ch R = 1 ,13616   ,369,369,369
BEGIN DESCRIPTION:
Stream0280 17.0
END DESCRIPTION:
XS GIS Cut Line= 3
      2429976.79     13717045.15      2430411.71      13716166.7
        2430472.     13715339.91
#Sta/Elev= 30
    4054  328.54  4577.6  320.79  4649.2  318.93  4688.5  319.43  4793.4  317.15
    4823  316.36  4845.5  317.49  4957.6  317.01    4980  318.44  4991.5  317.11
  5002.4  314.18  5002.8  309.59  5003.3  309.09  5013.3  309.59  5013.8  311.13
  5030.5  316.89  5034.2  317.17    5046  317.62  5136.2  316.17  5199.7  317.76
  5283.6  320.54  5288.6  320.07  5376.8  322.85  5427.6  323.44  5667.6  342.86
  5695.4  343.61  5700.5  344.67  5757.8   348.3  5834.4  351.07  5863.2  353.25
#Mann= 6 ,-1 , 0
    4054    .045       0  4577.6     .05       0  4793.4      .1       0
  5002.8     .05       0  5013.3      .1       0  5199.7     .07       0
Bank Sta=5002.8,5013.3
XS Rating Curve= 0 ,0
Exp/Cntr=0.3,0.1

Type RM Length L Ch R = 1 ,13247   ,489,489,489
BEGIN DESCRIPTION:
Stream0280 16.0
END DESCRIPTION:
XS GIS Cut Line= 3
      2430875.01     13716925.04        2430725.       13716225.
        2430625.     13715474.97
#Sta/Elev= 30
  4279.1  324.67    4453  321.46  4689.1  318.43  4708.7  318.83    4859   316.2
  4964.3  315.96  4970.3  315.18  4975.4  312.22  4984.8  311.57  4992.5   309.4
  4999.8  308.94  5000.3  308.44  5010.5  308.94  5015.2  310.25  5025.3  316.19
  5109.8  316.17  5182.9   314.5  5212.4  314.78  5233.9  314.86  5334.3  315.31
  5348.1   316.6  5378.4  317.07  5490.6  328.19  5590.2  340.22  5610.4   341.2
  5620.5  342.45  5636.9   346.6    5642  346.06  5650.8   348.1  5751.7   353.2
#Mann= 6 ,-1 , 0
  4279.1     .05       0    4859      .1       0  4999.8     .05       0
  5010.5      .1       0  5212.4     .12       0  5233.9     .07       0
Bank Sta=4999.8,5010.5
XS Rating Curve= 0 ,0
Exp/Cntr=0.3,0.1

Type RM Length L Ch R = 1 ,12758   ,467,467,467
BEGIN DESCRIPTION:
Stream0280 15.0
END DESCRIPTION:
XS GIS Cut Line= 3
      2431425.01     13716775.03        2431025.       13715975.
      2430674.98     13715574.98
#Sta/Elev= 30
  4105.4  324.33  4141.8  324.17  4180.9  322.56  4307.6  321.34  4583.4  316.37
  4623.8  316.87  4708.1  316.38  4743.9  315.56  4829.4  314.93  4833.5  315.74
  4874.1  314.26  4963.5  315.44  4986.1  309.15  4986.6  308.65  4996.9  309.15
  4997.1  313.78  5003.2  313.78    5007  315.12  5074.1  314.62  5119.9  313.65
  5127.5  314.25    5156   312.8  5170.2  313.78  5197.3  313.83  5233.8  314.09
    5305  319.14  5417.9   332.6  5460.7  339.62  5503.4  345.36  5531.4  347.82
#Mann= 10 ,-1 , 0
  4105.4     .05       0  4307.6    .045       0  4623.8     .05       0
  4708.1    .045       0  4743.9     .05       0  4833.5      .1       0
  4986.1     .05       0  4996.9      .1       0  5074.1     .12       0
  5197.3     .07       0
Bank Sta=4986.1,4996.9
XS Rating Curve= 0 ,0
Exp/Cntr=0.3,0.1

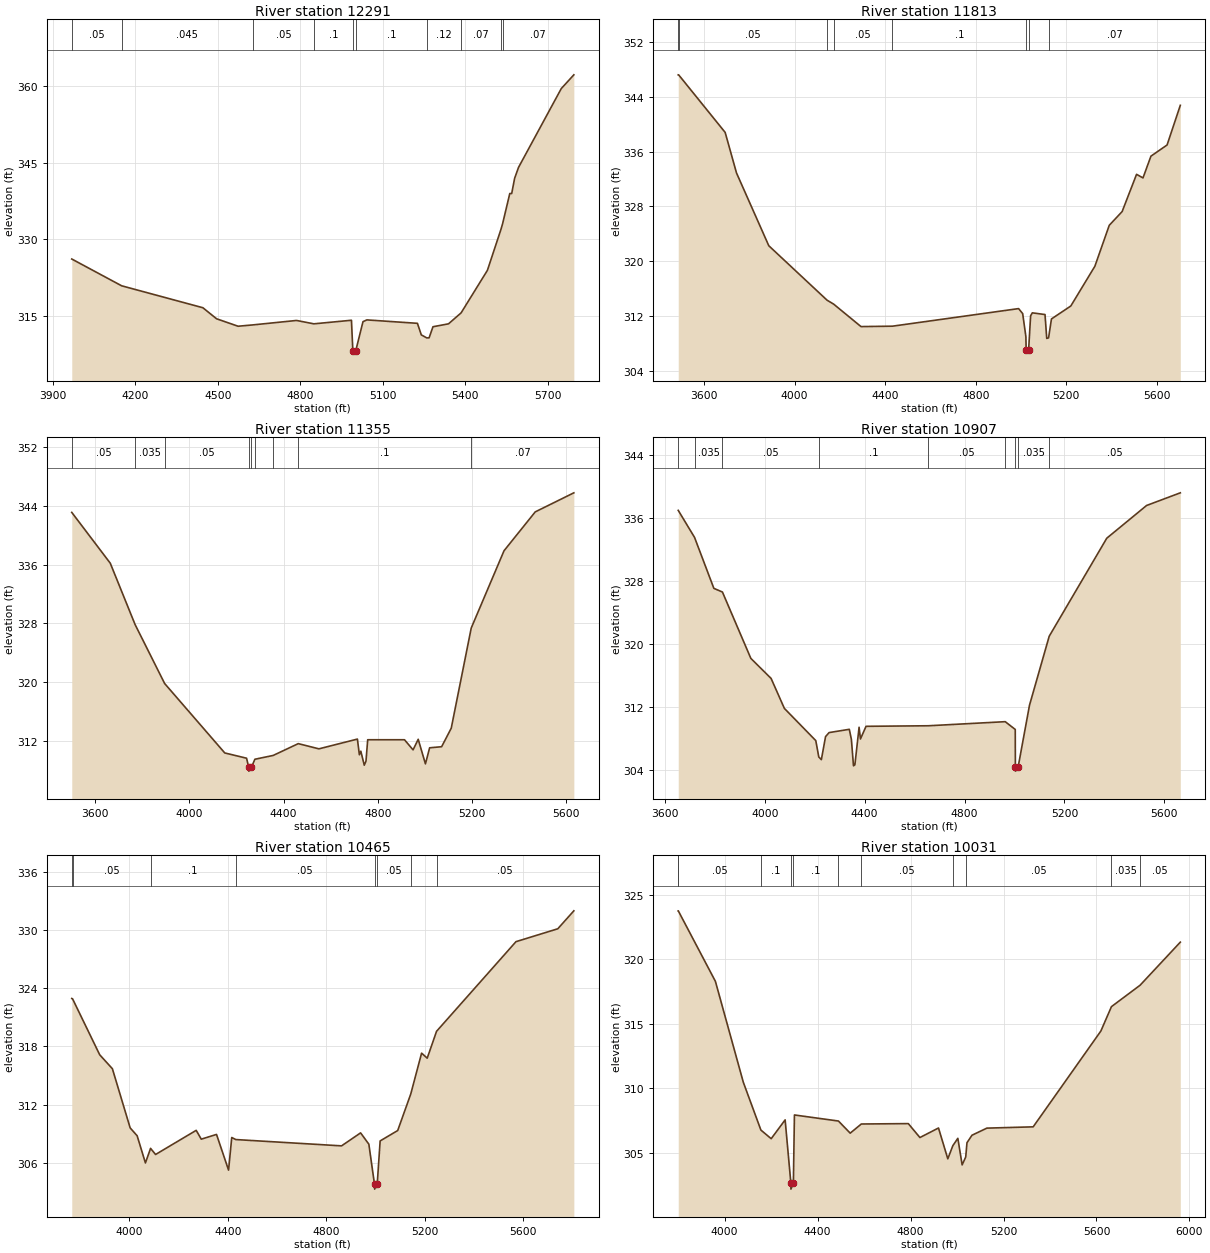
Type RM Length L Ch R = 1 ,12291   ,478,478,478
BEGIN DESCRIPTION:
Stream0280 14.0
END DESCRIPTION:
XS GIS Cut Line= 4
      2431975.02     13716675.03        2431325.       13715875.
        2430925.       13715475.      2430762.72     13715312.72
#Sta/Elev= 30
  3969.3  326.14  4150.7   320.9  4446.1  316.61  4495.9  314.45  4574.2  312.99
  4627.7  313.25  4786.8  314.12  4849.8  313.46  4986.5  314.16  4991.5  308.23
    4992  307.73  5002.3  308.23  5028.4  313.88  5042.5  314.23  5226.4  313.56
  5240.5   311.3  5260.4  310.71  5268.8  310.72    5283  312.89  5339.5  313.46
  5385.2   315.6  5480.9  323.92    5530   331.9  5536.1  333.02  5562.3  338.95
  5569.3  338.95  5579.9  341.92  5594.1  344.06  5749.6  359.48  5795.3  362.17
#Mann= 10 ,-1 , 0
  3969.3     .05       0  4150.7    .045       0  4627.7     .05       0
  4849.8      .1       0  4991.5     .05       0  5002.3      .1       0
  5260.4     .12       0  5385.2     .07       0    5530     .12       0
  5536.1     .07       0
Bank Sta=4991.5,5002.3
XS Rating Curve= 0 ,0
Exp/Cntr=0.3,0.1

Type RM Length L Ch R = 1 ,11813   ,458,458,458
BEGIN DESCRIPTION:
Stream0280 13.0
END DESCRIPTION:
XS GIS Cut Line= 4
      2432575.01     13716775.02        2431675.       13715575.
        2431275.       13715225.      2431134.89     13715102.41
#Sta/Elev= 30
    3486  347.23    3488  347.22  3693.3  338.81  3743.3  332.89    3886  322.24
  4143.4  314.28  4172.3  313.71  4293.3  310.42  4432.4  310.48  4989.3  313.05
  5007.4  312.32  5021.6  308.95  5022.8  307.04  5023.3  306.54  5033.7  307.04
  5042.5     312  5050.1  312.43  5106.1  312.18  5113.7  308.69  5121.8  308.77
  5134.6  311.54    5220  313.43  5326.3  319.24  5389.9  325.23  5446.8  327.24
  5510.4  332.68  5538.9  332.16    5574  335.34  5645.2  336.97  5703.7  342.77
#Mann= 8 ,-1 , 0
    3486     .07       0    3488     .05       0  4143.4    .035       0
  4172.3     .05       0  4432.4      .1       0  5022.8     .05       0
  5033.7      .1       0  5121.8     .07       0
Bank Sta=5022.8,5033.7
XS Rating Curve= 0 ,0
Exp/Cntr=0.3,0.1

Type RM Length L Ch R = 1 ,11355   ,448,448,448
BEGIN DESCRIPTION:
Stream0280 12.0
END DESCRIPTION:
XS GIS Cut Line= 4
      2432775.01     13716575.01        2431875.       13715375.
        2431825.       13715125.      2431750.84     13714754.21
#Sta/Elev= 30
    3500  343.12  3663.6  336.19  3768.8  327.84  3894.6  319.78    4150  310.31
  4242.7  309.59  4251.9  308.33  4252.4  307.83  4262.8  308.33  4278.1  309.45
  4355.8  309.97  4462.3  311.58    4550  310.87  4713.6   312.2  4721.9  310.06
  4728.1  310.55  4742.7  308.64    4750  309.19  4757.3  312.11  4913.6  312.11
    4950  310.73  4971.9  312.17  5002.6  308.82  5020.4  311.01  5071.4  311.16
  5112.2  313.68  5197.2  327.35  5336.5  337.89  5469.1  343.19  5633.1  345.79
#Mann= 9 ,-1 , 0
    3500     .05       0  3768.8    .035       0  3894.6     .05       0
  4251.9     .05       0  4262.8     .05       0  4278.1      .1       0
  4355.8    .035       0  4462.3      .1       0  5197.2     .07       0
Bank Sta=4251.9,4262.8
XS Rating Curve= 0 ,0
Exp/Cntr=0.3,0.1

Type RM Length L Ch R = 1 ,10907   ,442,442,442
BEGIN DESCRIPTION:
Stream0280 11.0
END DESCRIPTION:
XS GIS Cut Line= 4
      2432875.01     13716425.03        2432275.       13715225.
        2432175.       13715075.      2431904.28     13714668.92
#Sta/Elev= 30
  3653.9  336.99  3719.2  333.55  3796.5  327.07  3830.9   326.6  3944.6  318.16
  4025.7  315.61  4078.8   311.8  4204.6   307.7  4216.6  305.62  4226.9  305.28
  4243.7  308.21  4257.7  308.72  4338.7  309.14  4347.1  307.86  4355.5   304.5
  4361.1  304.62  4377.9   309.4  4383.4  307.91  4405.8  309.52  4655.5  309.59
    4963  310.11  5003.1  309.12  5003.6  304.32  5004.1  303.82  5014.5  304.32
  5060.2  312.21  5139.1  320.98  5369.6  333.45  5528.9  337.61  5663.9  339.22
#Mann= 9 ,-1 , 0
  3653.9     .05       0  3719.2    .035       0  3830.9     .05       0
  4216.6      .1       0  4655.5     .05       0    4963    .035       0
  5003.6    .035       0  5014.5    .035       0  5139.1     .05       0
Bank Sta=5003.6,5014.5
XS Rating Curve= 0 ,0
Exp/Cntr=0.3,0.1

Type RM Length L Ch R = 1 ,10465   ,434,434,434
BEGIN DESCRIPTION:
Stream0280 10.0
END DESCRIPTION:
XS GIS Cut Line= 4
      2432925.01     13716175.02        2432625.       13714975.
        2432375.       13714875.      2432004.88     13714493.02
#Sta/Elev= 30
  3766.9  322.94  3770.1  322.91  3880.3  317.14  3931.8   315.7    4004   309.6
  4032.3  308.79  4065.9  305.99  4086.8  307.49  4107.1  306.86    4272  309.35
  4292.6  308.44  4354.5  308.93  4403.4  305.25  4416.3  308.61  4432.8   308.4
  4862.1  307.75  4939.4  309.09  4972.9  307.92  4995.8  303.79  4996.3  303.29
  5006.8  303.79  5018.7  308.26    5090  309.33  5142.8  313.08    5187  317.31
  5209.8  316.79  5247.7  319.56  5570.1   328.8  5739.9  330.13    5805  331.98
#Mann= 8 ,-1 , 0
  3766.9    .035       0  3770.1     .05       0  4086.8      .1       0
  4432.8     .05       0  4995.8     .05       0  5006.8     .05       0
  5142.8    .035       0  5247.7     .05       0
Bank Sta=4995.8,5006.8
XS Rating Curve= 0 ,0
Exp/Cntr=0.3,0.1

Type RM Length L Ch R = 1 ,10031   ,467,467,467
BEGIN DESCRIPTION:
Stream0280 9.0
END DESCRIPTION:
XS GIS Cut Line= 3
        2433025.     13716175.04        2433025.       13714975.
      2432275.01     13714375.01
#Sta/Elev= 30
  3800.3  323.74  3800.5  323.74  3960.3  318.27  4080.3  310.45    4156  306.74
  4200.3  306.07  4260.3  307.53  4284.8  302.66  4285.3  302.16  4295.8  302.66
  4300.3  307.91  4489.7  307.44  4540.3   306.5  4588.2  307.21  4790.3  307.24
  4840.3  306.16  4920.3   306.9  4960.3  304.51    4982  305.53  5003.5   306.1
    5022  304.04  5037.4  304.65  5042.8  305.76  5064.4  306.34  5128.4  306.89
  5327.7  306.99    5619  314.42  5664.5  316.31  5787.7  317.97  5960.8  321.31
#Mann= 11 ,-1 , 0
  3800.3    .035       0  3800.5     .05       0    4156      .1       0
  4284.8     .05       0  4295.8      .1       0  4489.7     .07       0
  4588.2     .05       0    4982     .07       0  5037.4     .05       0
  5664.5    .035       0  5787.7     .05       0
Bank Sta=4284.8,4295.8
XS Rating Curve= 0 ,0
Exp/Cntr=0.3,0.1