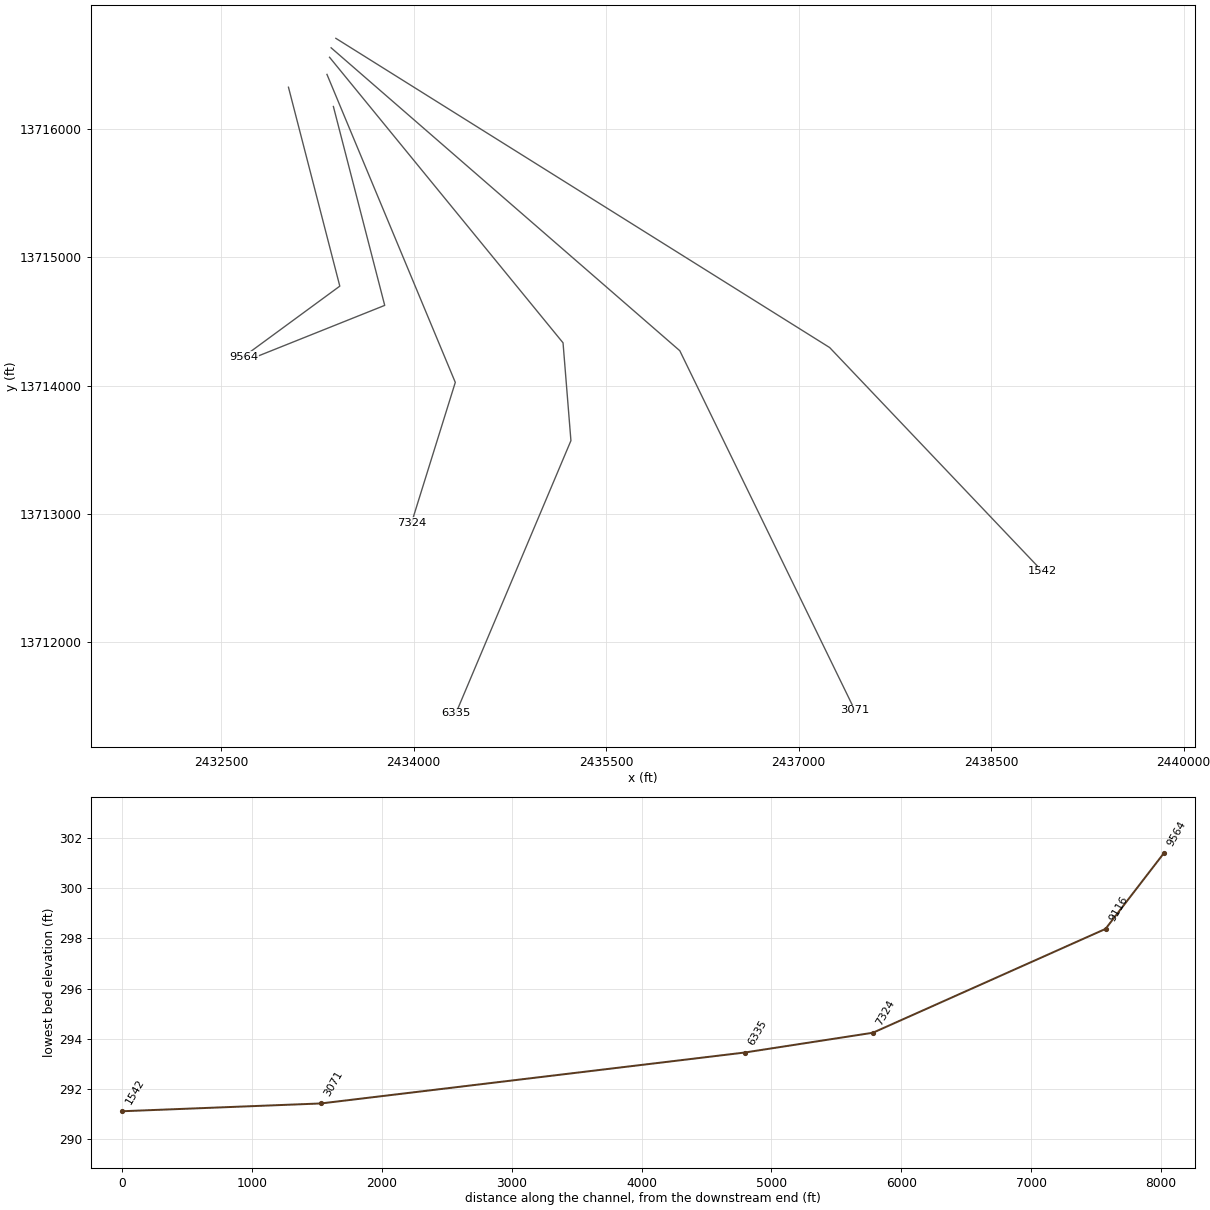
HEC-RAS study Stream0280.prj: Stream0280 Base Level Engineering

--- Stream0280.g01 (geometry) --- (continued)

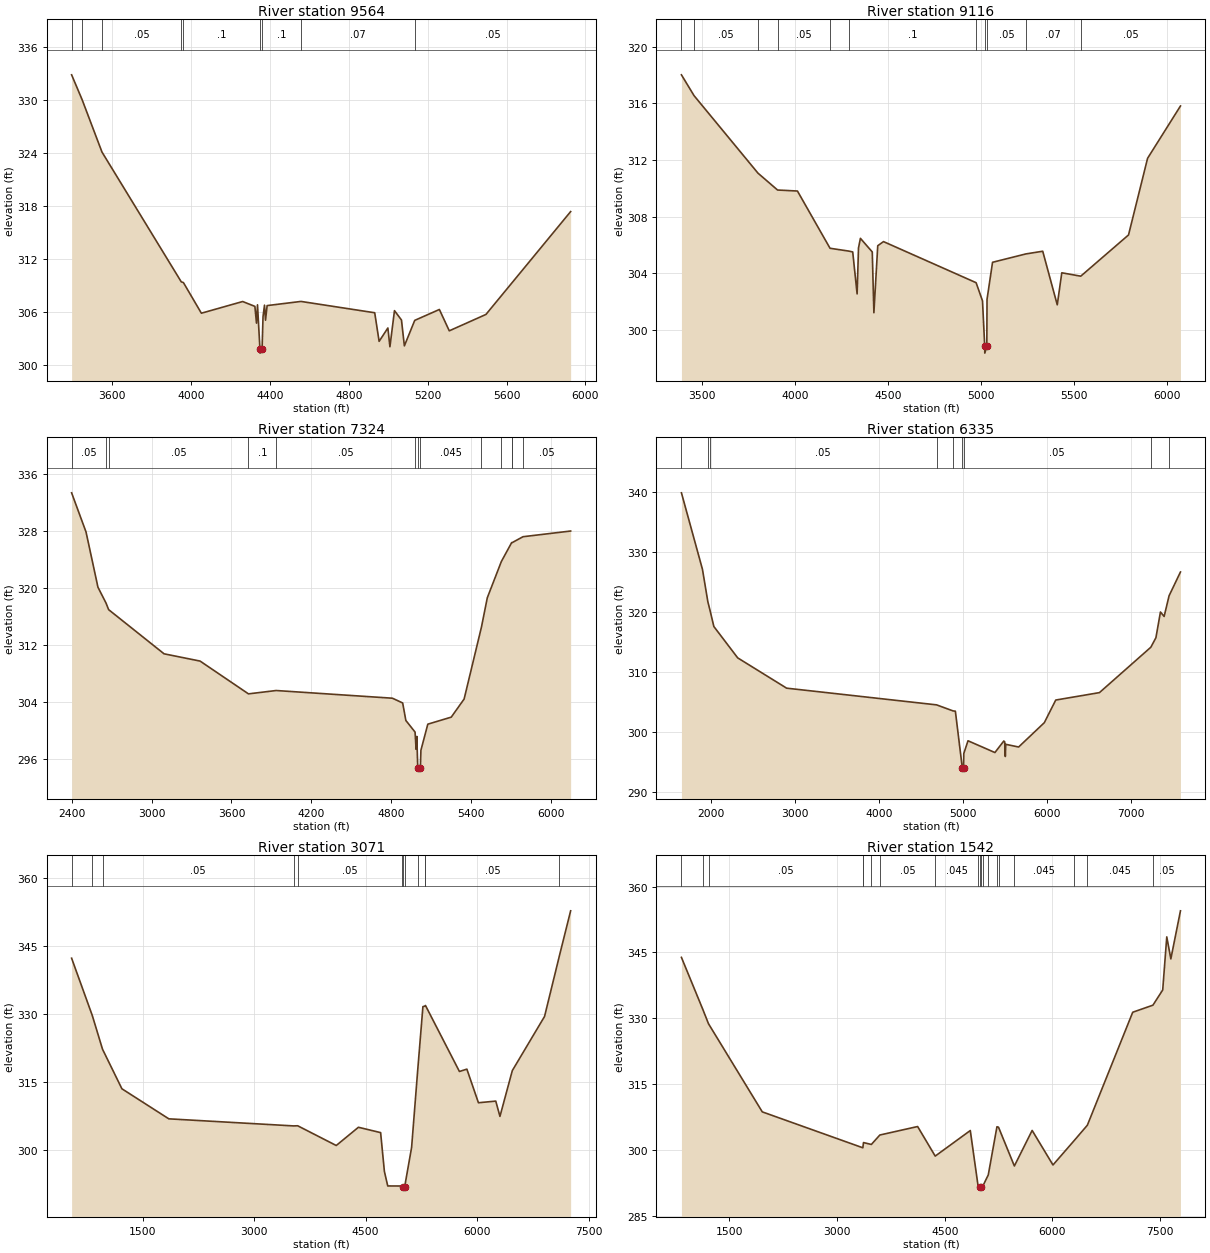
Type RM Length L Ch R = 1 ,9564    ,448,448,448
BEGIN DESCRIPTION:
Stream0280 8.0
END DESCRIPTION:
XS GIS Cut Line= 3
        2433025.       13716325.        2433425.       13714775.
      2432675.03     13714225.02
#Sta/Elev= 30
  3394.2  332.83  3447.2  330.04  3548.1  324.11  3950.4  309.44  3961.2  309.36
  4052.3   305.9  4261.7  307.22  4323.7  306.67  4331.8  304.78  4336.9  306.85
  4349.2  301.89  4349.7  301.39  4360.2  301.89    4365  305.52  4372.4  306.81
  4377.6  305.11  4385.7  306.76  4557.5  307.23  4931.4  305.95  4953.7  302.72
  4998.1  304.23  5008.5  302.11  5031.6  306.19  5067.1  305.13  5081.8  302.21
  5134.3  305.09  5259.3  306.32  5309.5  303.91  5495.5  305.76    5925  317.38
#Mann= 9 ,-1 , 0
  3394.2     .05       0  3447.2    .035       0  3548.1     .05       0
  3950.4     .12       0  3961.2      .1       0  4349.2     .05       0
  4360.2      .1       0  4557.5     .07       0  5134.3     .05       0
Bank Sta=4349.2,4360.2
XS Rating Curve= 0 ,0
Exp/Cntr=0.3,0.1

Type RM Length L Ch R = 1 ,9116    ,1792,1792,1792
BEGIN DESCRIPTION:
Stream0280 7.0
END DESCRIPTION:
XS GIS Cut Line= 3
      2433375.01     13716174.96        2433775.       13714625.
      2432774.97     13714224.99
#Sta/Elev= 30
    3392  318.02  3459.7  316.55  3802.8  311.08  3907.8  309.89  4014.5  309.82
  4189.3  305.78  4290.3  305.58  4311.1  305.52  4334.7  302.56  4342.1   305.8
  4352.4  306.48    4416  305.52  4424.7  301.23  4445.4  305.96  4476.4  306.25
  4973.2  303.35  5007.5  302.07  5019.4  298.88  5019.9  298.38  5030.7  298.88
  5031.8  302.17  5061.4  304.79  5239.9  305.38  5330.7  305.57  5408.7  301.79
    5433  304.05  5534.8  303.81  5791.1  306.72  5893.4  312.13  6069.8  315.82
#Mann= 11 ,-1 , 0
    3392    .035       0  3459.7     .05       0  3802.8     .12       0
  3907.8     .05       0  4189.3     .12       0  4290.3      .1       0
  4973.2     .05       0  5019.4     .05       0  5030.7     .05       0
  5239.9     .07       0  5534.8     .05       0
Bank Sta=5019.4,5030.7
XS Rating Curve= 0 ,0
Exp/Cntr=0.3,0.1

Type RM Length L Ch R = 1 ,7324    ,989,989,989
BEGIN DESCRIPTION:
Stream0280 6.0
END DESCRIPTION:
XS GIS Cut Line= 3
      2433324.99     13716425.01        2434325.       13714025.
      2433984.35     13712931.65
#Sta/Elev= 30
  2400.4  333.36  2508.7  327.85  2598.1  320.09    2659  317.85  2678.2  316.94
  3094.3  310.73  3364.6  309.71  3727.7   305.1  3935.3  305.57  4808.1  304.49
    4885  303.82  4908.9  301.36    4978  299.73  4985.8  297.31  4991.2  299.12
  4997.7  294.97  5003.7  294.74  5004.2  294.24    5018  294.74  5021.9  297.17
  5073.7  300.84  5249.6  301.83  5346.1  304.37  5476.4   314.5  5520.2  318.61
  5625.5   323.7  5702.9  326.36  5706.7  326.36  5788.2  327.19  6145.6  327.99
#Mann= 13 ,-1 , 0
  2400.4     .05       0    2659    .035       0  2678.2     .05       0
  3727.7      .1       0  3935.3     .05       0    4978    .045       0
  5003.7    .045       0    5018    .045       0  5476.4     .05       0
  5625.5    .035       0  5702.9     .05       0  5706.7    .035       0
  5788.2     .05       0
Bank Sta=5003.7,5018
XS Rating Curve= 0 ,0
Exp/Cntr=0.3,0.1

Type RM Length L Ch R = 1 ,6335    ,3264,3264,3264
BEGIN DESCRIPTION:
XS6328
END DESCRIPTION:
XS GIS Cut Line= 4
      2433345.03     13716558.52      2435164.62     13714333.21
      2435226.09     13713570.95       2434329.3     13711445.68
#Sta/Elev= 30
    1644  339.85  1894.6  327.09  1958.8  321.68  1980.5  320.49  2030.3  317.56
  2314.6  312.33  2897.5  307.28  4683.4   304.5  4880.5  303.49    4908  303.44
  4991.1  293.95  4991.6  293.45  5005.5  293.95  5008.3  296.39  5058.5  298.51
    5379  296.55  5485.1  298.47  5495.9  298.32    5503  295.89  5508.5  297.92
  5661.6  297.47  5967.9  301.53  6103.8   305.3  6624.7  306.54  7237.2  314.11
  7297.7   315.7  7351.6  319.98  7395.4  319.24  7454.2  322.68    7590  326.65
#Mann= 9 ,-1 , 0
    1644     .05       0  1958.8    .035       0  1980.5     .05       0
  4683.4    .035       0  4880.5     .05       0  4991.1     .05       0
  5005.5     .05       0  7237.2    .035       0  7454.2     .05       0
Bank Sta=4991.1,5005.5
XS Rating Curve= 0 ,0
Exp/Cntr=0.3,0.1

Type RM Length L Ch R = 1 ,3071    ,1529,1529,1529
BEGIN DESCRIPTION:
XS6327
END DESCRIPTION:
XS GIS Cut Line= 3
       2433357.3     13716632.32      2436074.42     13714271.74
      2437438.76     13711469.33
#Sta/Elev= 30
   542.8  342.34   821.2   329.7   958.8  322.27  1219.6  313.55  1851.1  306.92
  3529.3  305.36  3585.6  305.39  4104.4  301.04    4403  305.06  4701.7  303.88
  4752.3  295.33  4797.4  292.12  4990.1  292.11  5009.2  291.92  5009.7  291.42
    5025  291.92  5118.6  300.61  5198.8  317.24  5270.8  331.66  5298.4  331.77
  5305.2  331.92  5762.3  317.36  5862.4  317.88  6018.1  310.47  6251.4  310.83
  6307.6  307.46  6474.1  317.56  6907.9   329.5  7107.7  342.86    7259  352.79
#Mann= 12 ,-1 , 0
   542.8     .05       0   821.2    .035       0   958.8     .05       0
  3529.3    .035       0  3585.6     .05       0  4990.1      .1       0
  5009.2     .05       0    5025      .1       0  5198.8     .12       0
  5298.4      .1       0  5305.2     .05       0  7107.7     .07       0
Bank Sta=5009.2,5025
XS Rating Curve= 0 ,0
Exp/Cntr=0.3,0.1

Type RM Length L Ch R = 1 ,1542    ,0,0,0
BEGIN DESCRIPTION:
XS6326
END DESCRIPTION:
XS GIS Cut Line= 3
      2433394.23     13716706.05      2437242.41     13714296.33
      2438901.08     13712551.66
#Sta/Elev= 30
   834.7  343.87  1135.8  331.89  1211.6  328.76  1960.1   308.7  3360.5  300.52
  3369.2  301.71  3478.8  301.28  3597.1  303.43  4123.1  305.36  4367.9  298.63
  4856.3  304.45  4965.8   291.7  4984.9  291.61  4985.4  291.11  5001.2  291.61
    5028   291.7  5106.9  294.36  5227.4  305.31  5249.2  305.21  5469.9  296.38
  5717.5  304.47  6007.5  296.61  6301.3  302.14  6486.1  305.66  7117.8  331.38
    7399  332.99  7535.2  336.45  7591.8  348.54  7648.5  343.53  7782.4  354.47
#Mann= 19 ,-1 , 0
   834.7     .05       0  1135.8    .035       0  1211.6     .05       0
  3360.5    .035       0  3369.2     .05       0  3478.8    .035       0
  3597.1     .05       0  4367.9    .045       0  4965.8      .1       0
  4984.9     .05       0  5001.2      .1       0    5028    .045       0
  5106.9      .1       0  5227.4    .035       0  5249.2      .1       0
  5469.9    .045       0  6301.3     .05       0  6486.1    .045       0
    7399     .05       0
Bank Sta=4984.9,5001.2
XS Rating Curve= 0 ,0
Exp/Cntr=0.3,0.1

Chan Stop Cuts=-1
Use User Specified Reach Order=0
Composite Channel Slope=5