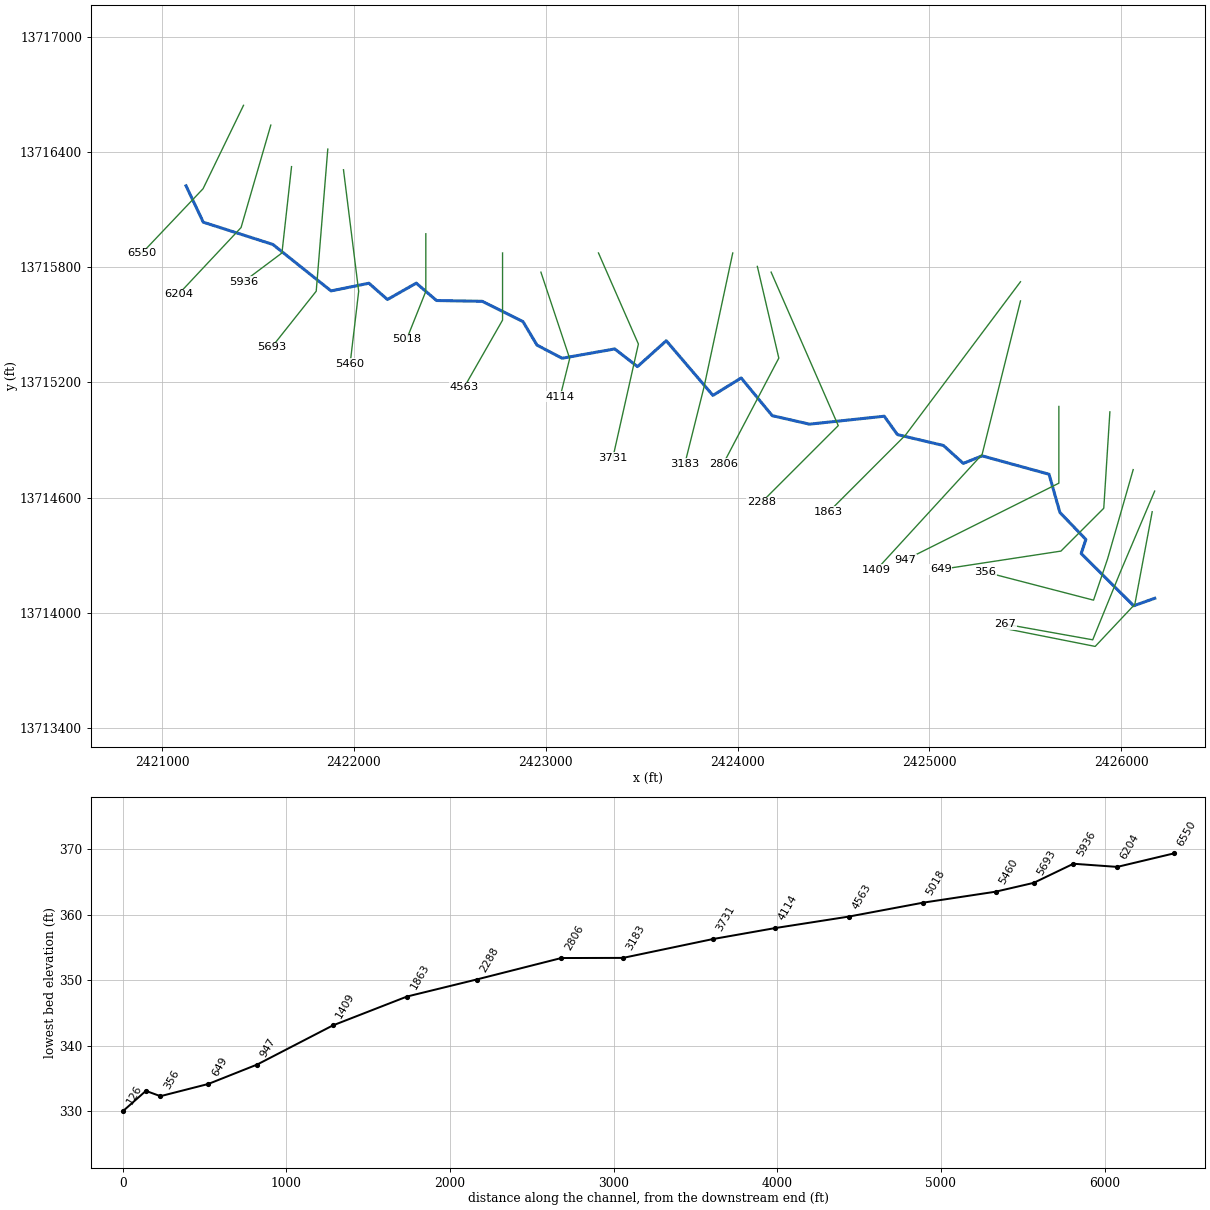
--- Stream0281.prj (project) ---

Proj Title=Stream0281 Base Level Engineering
Current Plan=p01
Default Exp/Contr=0.3,0.1
English Units
Geom File=g01
Flow File=f01
Plan File=p01
BEGIN DESCRIPTION:
Stream0281
END DESCRIPTION:

--- Stream0281.p01 (plan) ---

Plan Title=Multiple Run
Short Identifier=Multiple
Geom File=g01
Flow File=f01
Subcritical Flow
K Sum by GR= 0
Std Step Tol= 0.01
Critical Tol= 0.01
Num of Std Step Trials= 20
Max Error Tol= 0.3
Flow Tol Ratio= 0.001
Split Flow NTrial= 30
Split Flow Tol= 0.02
Split Flow Ratio= 0.02
Log Output Level= 0
Friction Slope Method= 1
Unsteady Friction Slope Method= 2
Unsteady Bridges Friction Slope Method= 1
Parabolic Critical Depth
Global Vel Dist=  1 , 1 , 1
Global Log Level= 0
CheckData=True
Encroach Param= -1, 0, 0, 0
BEGIN DESCRIPTION:
Multiple Run
END DESCRIPTION:

--- Stream0281.f01 (steady flow) ---

Flow Title=Multiple
Number of Profiles=7
Profile Names=10-year,25-year,50-year,1pct_min,100-year,1pct_plu,500-year
River Rch & RM= Stream0281,Reach-1,6550
     655    1047    1398     903    1801    3594    2963
River Rch & RM= Stream0281,Reach-1,2288
     762    1230    1653    1074    2143    4276    3570
Boundary for River Rch & Prof#=Stream0281,Reach-1,1
Up Type=0
Dn Type=3
Dn Slope=0.005
Boundary for River Rch & Prof#=Stream0281,Reach-1,2
Up Type=0
Dn Type=3
Dn Slope=0.005
Boundary for River Rch & Prof#=Stream0281,Reach-1,3
Up Type=0
Dn Type=3
Dn Slope=0.005
Boundary for River Rch & Prof#=Stream0281,Reach-1,4
Up Type=0
Dn Type=3
Dn Slope=0.005
Boundary for River Rch & Prof#=Stream0281,Reach-1,5
Up Type=0
Dn Type=3
Dn Slope=0.005
Boundary for River Rch & Prof#=Stream0281,Reach-1,6
Up Type=0
Dn Type=3
Dn Slope=0.005
Boundary for River Rch & Prof#=Stream0281,Reach-1,7
Up Type=0
Dn Type=3
Dn Slope=0.005

--- Stream0281.g01 (geometry) ---

Geom Title=Existing Conditions

River Reach=Stream0281,Reach-1
Reach XY= 30
      2421125.00     13716225.00      2421214.83     13716035.32
      2421577.43     13715919.48      2421880.93     13715677.23
      2422078.42     13715717.18      2422174.91     13715632.31
      2422325.08     13715717.70      2422430.85     13715627.08
      2422669.14     13715622.93      2422881.45     13715517.25
      2422954.53     13715394.63      2423085.50     13715326.19
      2423359.78     13715374.75      2423478.34     13715282.60
      2423628.35     13715417.42      2423871.66     13715132.60
      2424018.96     13715223.42      2424180.68     13715026.99
      2424375.01     13714982.59      2424764.71     13715024.00
      2424833.35     13714928.19      2425073.50     13714871.38
      2425176.65     13714778.17      2425274.99     13714817.41
      2425623.78     13714721.56      2425680.47     13714522.55
      2425815.70     13714381.67      2425791.39     13714308.33
      2426064.96     13714035.99      2426175.00     13714075.00

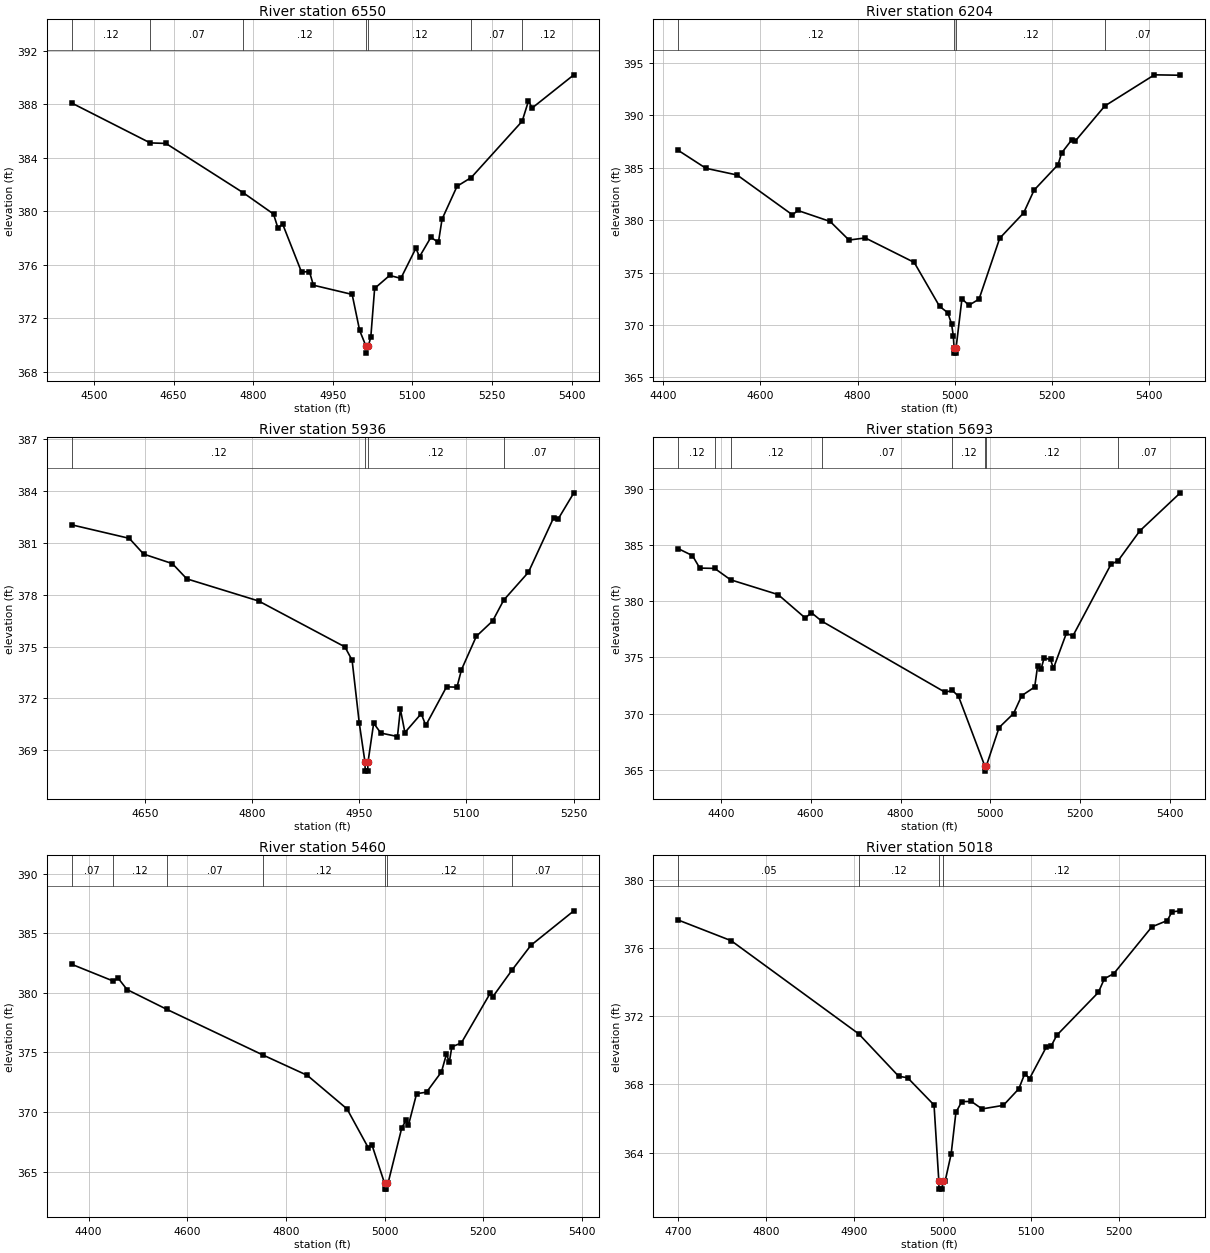
Type RM Length L Ch R = 1,6550,346,346,346
BEGIN DESCRIPTION:
Stream0281 13.0
END DESCRIPTION:
XS GIS Cut Line= 3
      2421424.76     13716644.70      2421213.75     13716209.76
      2420895.10     13715873.89
#Sta/Elev= 30
  4457.9  388.08  4605.7  385.10  4635.4  385.06  4781.2  381.37  4838.2  379.78
  4846.6  378.72  4855.2  379.05  4891.0  375.44  4905.9  375.48  4913.3  374.46
  4986.4  373.77  5000.5  371.08  5012.7  369.88  5012.9  369.38  5016.7  369.88
  5021.6  370.59  5028.8  374.22  5057.1  375.19  5078.2  374.97  5106.5  377.22
  5113.4  376.59  5134.8  378.04  5149.0  377.66  5155.9  379.40  5184.2  381.86
  5210.9  382.51  5306.9  386.72  5318.8  388.24  5325.7  387.71  5404.3  390.19
#Mann=7,-1,0
  4457.9    0.12       0  4605.7    0.07       0  4781.2    0.12       0
  5012.7    0.05       0  5016.7    0.12       0  5210.9    0.07       0
  5306.9    0.12       0
Bank Sta=5012.7,5016.7
Exp/Cntr=0.3,0.1

Type RM Length L Ch R = 1,6204,268,268,268
BEGIN DESCRIPTION:
XS6336
END DESCRIPTION:
XS GIS Cut Line= 3
      2421566.86     13716541.35      2421411.83     13716007.37
      2421085.26     13715659.32
#Sta/Elev= 30
  4430.8  386.65  4487.8  384.94  4552.0  384.30  4665.9  380.50  4676.9  380.92
  4743.5  379.87  4782.2  378.10  4815.8  378.30  4916.4  375.97  4968.5  371.79
  4985.5  371.17  4993.2  370.13  4996.9  368.98  4998.5  367.82  4998.7  367.32
  5002.3  367.32  5002.6  367.82  5014.7  372.50  5028.9  371.88  5049.9  372.47
  5092.4  378.27  5141.7  380.69  5163.2  382.86  5212.5  385.29  5219.8  386.40
  5240.9  387.67  5248.2  387.55  5308.7  390.88  5410.8  393.85  5464.1  393.81
#Mann=4,-1,0
  4430.8    0.12       0  4998.5    0.05       0  5002.6    0.12       0
  5308.7    0.07       0
Bank Sta=4998.5,5002.6
Exp/Cntr=0.3,0.1

Type RM Length L Ch R = 1,5936,243,243,243
BEGIN DESCRIPTION:
Stream0281 12.0
END DESCRIPTION:
XS GIS Cut Line= 3
      2421675.00     13716324.99      2421625.00     13715875.00
      2421424.96     13715724.97
#Sta/Elev= 30
  4547.6  382.03  4628.1  381.25  4648.2  380.34  4688.4  379.79  4708.6  378.91
  4809.2  377.63  4929.9  374.98  4940.0  374.21  4950.0  370.59  4958.1  368.30
  4958.3  367.80  4961.9  367.80  4962.2  368.30  4970.2  370.57  4980.2  370.00
  5003.5  369.80  5007.6  371.38  5013.9  370.03  5036.8  371.12  5043.1  370.44
  5072.2  372.67  5086.8  372.65  5093.1  373.66  5113.9  375.59  5136.8  376.48
  5152.2  377.68  5186.8  379.29  5222.2  382.45  5228.5  382.37  5250.4  383.88
#Mann=4,-1,0
  4547.6    0.12       0  4958.1    0.05       0  4962.2    0.12       0
  5152.2    0.07       0
Bank Sta=4958.1,4962.2
Exp/Cntr=0.3,0.1

Type RM Length L Ch R = 1,5693,233,233,233
BEGIN DESCRIPTION:
XS6335
END DESCRIPTION:
XS GIS Cut Line= 3
      2421863.98     13716416.50      2421803.69     13715675.79
      2421571.14     13715382.96
#Sta/Elev= 30
  4305.4  384.69  4337.0  384.07  4353.3  382.96  4386.5  382.93  4421.7  381.92
  4527.6  380.60  4587.8  378.52  4601.9  378.98  4624.5  378.24  4898.9  371.91
  4915.6  372.06  4929.0  371.54  4987.1  365.38  4987.4  364.88  4991.2  365.38
  5019.3  368.76  5051.5  370.01  5069.7  371.60  5098.5  372.37  5104.9  374.22
  5112.9  374.00  5119.3  374.93  5133.7  374.83  5140.1  374.02  5169.0  377.15
  5183.4  376.91  5268.3  383.30  5284.0  383.61  5332.4  386.27  5422.5  389.66
#Mann=8,-1,0
  4305.4    0.12       0  4386.5    0.07       0  4421.7    0.12       0
  4624.5    0.07       0  4915.6    0.12       0  4987.1    0.05       0
  4991.2    0.12       0  5284.0    0.07       0
Bank Sta=4987.1,4991.2
Exp/Cntr=0.3,0.1

Type RM Length L Ch R = 1,5460,442,442,442
BEGIN DESCRIPTION:
Stream0281 11.0
END DESCRIPTION:
XS GIS Cut Line= 3
      2421945.80     13716308.79      2422025.00     13715675.00
      2421980.43     13715298.45
#Sta/Elev= 30
  4365.8  382.40  4448.4  381.02  4460.3  381.21  4477.9  380.28  4558.5  378.62
  4753.8  374.78  4843.3  373.08  4923.9  370.26  4966.7  367.02  4974.3  367.25
  4999.9  364.03  5000.2  363.53  5003.8  363.53  5004.0  364.03  5007.0  364.03
  5034.7  368.65  5043.4  369.31  5048.4  368.90  5064.9  371.54  5085.1  371.67
  5115.3  373.37  5125.4  374.86  5131.3  374.19  5136.3  375.47  5155.6  375.80
  5214.1  379.97  5219.1  379.66  5258.4  381.92  5296.5  383.99  5383.7  386.89
#Mann=7,-1,0
  4365.8    0.07       0  4448.4    0.12       0  4558.5    0.07       0
  4753.8    0.12       0  4999.9    0.05       0  5004.0    0.12       0
  5258.4    0.07       0
Bank Sta=4999.9,5004
Exp/Cntr=0.3,0.1

Type RM Length L Ch R = 1,5018,455,455,455
BEGIN DESCRIPTION:
Stream0281 10.0
END DESCRIPTION:
XS GIS Cut Line= 3
      2422375.00     13715974.98      2422375.00     13715675.00
      2422275.01     13715425.03
#Sta/Elev= 30
  4700.2  377.63  4760.2  376.42  4904.8  370.96  4950.2  368.47  4960.2  368.39
  4990.2  366.79  4995.6  362.36  4995.8  361.86  4999.5  361.86  4999.8  362.36
  5002.9  362.36  5009.6  363.92  5015.0  366.36  5021.7  366.99  5032.5  367.00
  5044.6  366.56  5068.8  366.77  5086.3  367.74  5093.1  368.63  5098.5  368.34
  5117.3  370.17  5122.7  370.22  5129.4  370.88  5176.5  373.39  5183.3  374.19
  5194.0  374.49  5237.1  377.23  5254.6  377.60  5260.0  378.11  5269.4  378.17
#Mann=4,-1,0
  4700.2    0.05       0  4904.8    0.12       0  4995.6    0.05       0
  4999.8    0.12       0
Bank Sta=4995.6,4999.8
Exp/Cntr=0.3,0.1

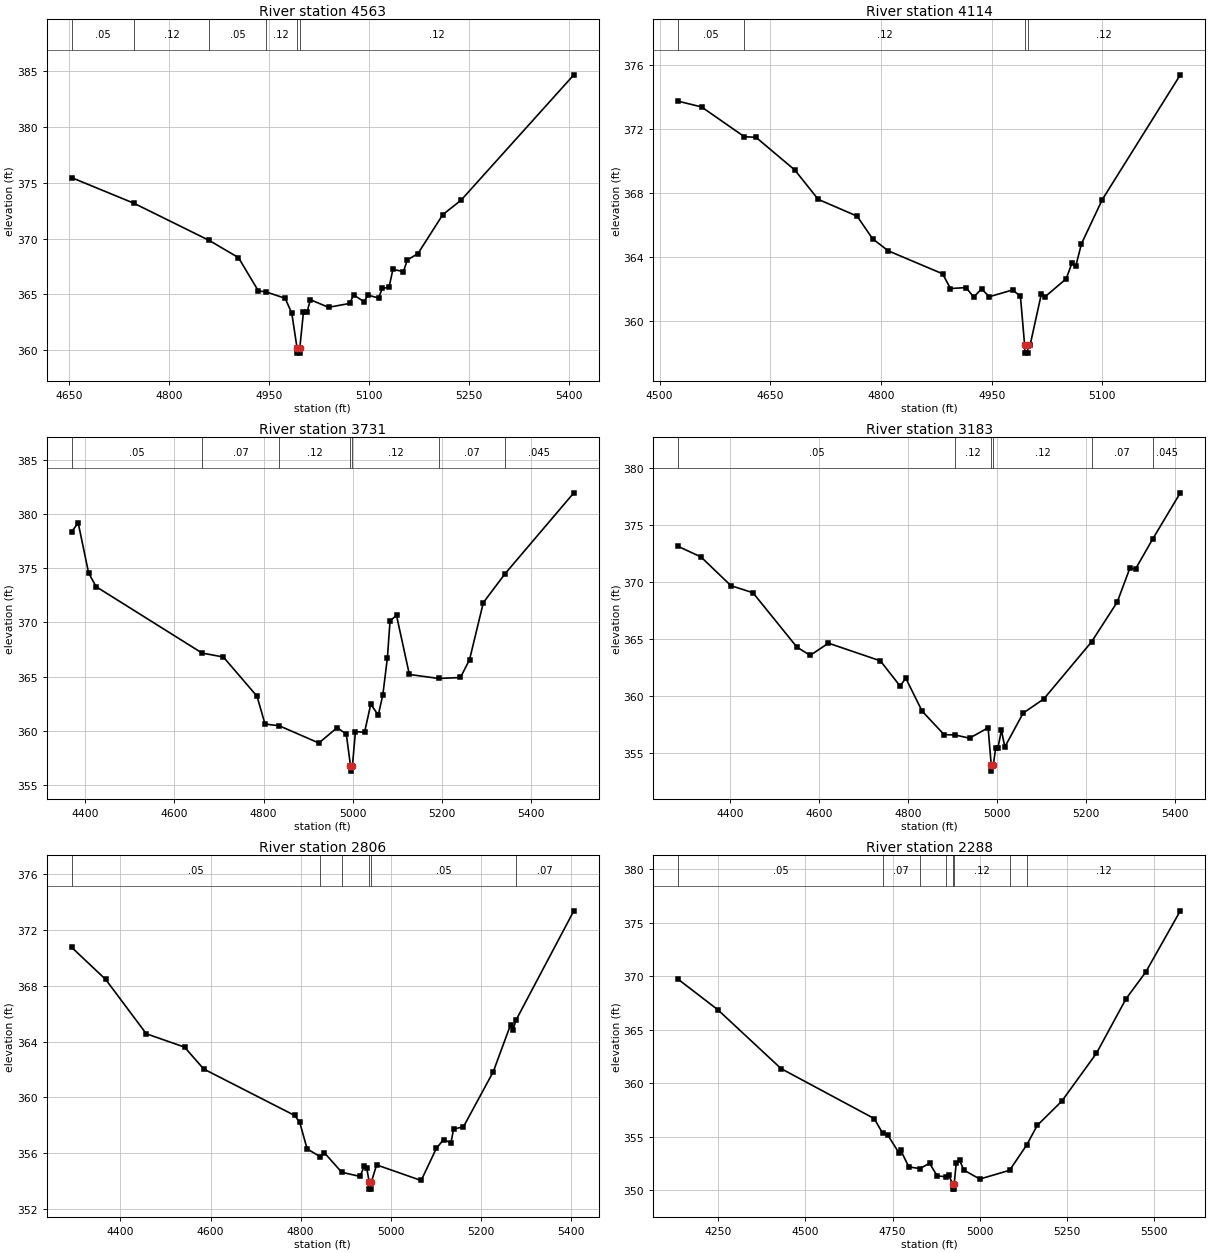
Type RM Length L Ch R = 1,4563,449,449,449
BEGIN DESCRIPTION:
Stream0281 9.0
END DESCRIPTION:
XS GIS Cut Line= 3
      2422775.00     13715874.96      2422775.00     13715525.00
      2422574.99     13715174.98
#Sta/Elev= 30
  4654.4  375.47  4747.5  373.18  4860.6  369.84  4904.4  368.30  4934.4  365.30
  4945.1  365.24  4974.4  364.65  4984.4  363.32  4992.2  360.23  4992.5  359.73
  4996.2  359.73  4996.5  360.23  5001.9  363.40  5007.2  363.40  5012.3  364.52
  5039.6  363.84  5071.3  364.19  5077.1  364.96  5092.9  364.34  5098.7  364.93
  5114.5  364.68  5120.3  365.54  5130.3  365.64  5136.1  367.24  5151.9  367.05
  5157.7  368.09  5173.5  368.65  5211.0  372.16  5238.3  373.45  5407.5  384.70
#Mann=6,-1,0
  4654.4    0.05       0  4747.5    0.12       0  4860.6    0.05       0
  4945.1    0.12       0  4992.2    0.05       0  4996.5    0.12       0
Bank Sta=4992.2,4996.5
Exp/Cntr=0.3,0.1

Type RM Length L Ch R = 1,4114,383,383,383
BEGIN DESCRIPTION:
Stream0281 8.0
END DESCRIPTION:
XS GIS Cut Line= 3
      2422975.01     13715774.97      2423125.00     13715325.00
      2423074.99     13715124.97
#Sta/Elev= 30
  4525.2  373.74  4556.8  373.38  4614.8  371.52  4630.6  371.48  4683.3  369.43
  4714.9  367.60  4767.6  366.55  4788.7  365.13  4809.8  364.38  4883.6  362.94
  4894.1  362.02  4915.2  362.08  4925.7  361.49  4936.3  362.00  4946.8  361.51
  4978.4  361.93  4989.0  361.54  4994.7  358.48  4995.0  357.98  4998.8  357.98
  4999.0  358.48  5002.1  358.48  5017.5  361.71  5022.7  361.52  5051.0  362.63
  5058.8  363.61  5063.9  363.40  5071.7  364.82  5100.0  367.59  5205.7  375.39
#Mann=4,-1,0
  4525.2    0.05       0  4614.8    0.12       0  4994.7    0.05       0
  4999.0    0.12       0
Bank Sta=4994.7,4999
Exp/Cntr=0.3,0.1

Type RM Length L Ch R = 1,3731,548,548,548
BEGIN DESCRIPTION:
Stream0281 7.0
END DESCRIPTION:
XS GIS Cut Line= 3
      2423274.99     13715875.02      2423483.10     13715400.20
      2423349.80     13714806.81
#Sta/Elev= 30
  4369.7  378.37  4384.1  379.17  4407.5  374.55  4424.3  373.29  4662.2  367.17
  4709.8  366.81  4785.4  363.19  4803.3  360.63  4835.2  360.47  4924.2  358.88
  4965.2  360.30  4985.7  359.70  4995.1  356.79  4995.4  356.29  4999.5  356.79
  5006.2  359.93  5026.7  359.87  5040.6  362.46  5057.4  361.45  5067.7  363.32
  5077.9  366.72  5083.9  370.15  5098.4  370.64  5127.2  365.20  5192.9  364.83
  5241.9  364.92  5262.3  366.57  5293.2  371.82  5341.3  374.45  5496.3  381.94
#Mann=7,-1,0
  4369.7    0.05       0  4662.2    0.07       0  4835.2    0.12       0
  4995.1    0.05       0  4999.5    0.12       0  5192.9    0.07       0
  5341.3   0.045       0
Bank Sta=4995.1,4999.5
Exp/Cntr=0.3,0.1

Type RM Length L Ch R = 1,3183,377,377,377
BEGIN DESCRIPTION:
Stream0281 6.0
END DESCRIPTION:
XS GIS Cut Line= 3
      2423974.99     13715874.98      2423825.00     13715175.00
      2423724.99     13714774.98
#Sta/Elev= 30
  4283.7  373.12  4334.8  372.20  4402.1  369.68  4451.6  369.06  4550.4  364.29
  4580.3  363.57  4621.2  364.64  4737.9  363.09  4782.2  360.88  4795.0  361.57
  4831.7  358.68  4881.1  356.62  4905.6  356.59  4938.2  356.31  4980.0  357.22
  4987.1  353.92  4987.4  353.42  4991.6  353.92  4997.0  355.46  5002.1  355.46
  5009.9  357.00  5017.6  355.54  5058.8  358.51  5105.2  359.75  5212.4  364.75
  5270.1  368.24  5298.5  371.21  5311.4  371.15  5349.7  373.76  5411.9  377.82
#Mann=6,-1,0
  4283.7    0.05       0  4905.6    0.12       0  4987.1    0.05       0
  4991.6    0.12       0  5212.4    0.07       0  5349.7   0.045       0
Bank Sta=4987.1,4991.6
Exp/Cntr=0.3,0.1

Type RM Length L Ch R = 1,2806,518,518,518
BEGIN DESCRIPTION:
Stream0281 5.0
END DESCRIPTION:
XS GIS Cut Line= 3
      2424103.19     13715804.94      2424215.14     13715327.00
      2423924.99     13714774.99
#Sta/Elev= 30
  4292.0  370.76  4367.3  368.46  4457.4  364.56  4542.3  363.60  4584.8  362.03
  4786.8  358.69  4798.0  358.20  4814.4  356.29  4843.5  355.73  4852.8  356.01
  4891.3  354.61  4932.0  354.31  4941.0  355.04  4946.7  354.92  4952.3  353.90
  4952.6  353.40  4956.5  353.40  4956.8  353.90  4968.7  355.14  5067.6  354.02
  5101.5  356.34  5117.4  356.96  5133.8  356.72  5139.4  357.71  5161.5  357.88
  5227.6  361.83  5266.0  365.20  5271.7  364.86  5277.8  365.52  5406.5  373.39
#Mann=6,-1,0
  4292.0    0.05       0  4843.5    0.07       0  4891.3    0.05       0
  4952.3    0.05       0  4956.8    0.05       0  5277.8    0.07       0
Bank Sta=4952.3,4956.8
Exp/Cntr=0.3,0.1

Type RM Length L Ch R = 1,2288,425,425,425
BEGIN DESCRIPTION:
Stream0281 4.0
END DESCRIPTION:
XS GIS Cut Line= 3
      2424175.01     13715774.98      2424525.00     13714975.00
      2424124.98     13714574.98
#Sta/Elev= 30
  4135.8  369.72  4249.2  366.88  4430.5  361.38  4697.5  356.71  4721.8  355.33
  4736.1  355.18  4767.7  353.54  4773.1  353.77  4796.5  352.20  4827.9  352.04
  4856.2  352.53  4878.0  351.35  4903.7  351.28  4910.8  351.44  4922.1  350.62
  4922.5  350.12  4926.4  350.12  4926.7  350.62  4932.6  352.59  4942.3  352.80
  4954.4  351.90  5000.0  351.06  5085.5  351.88  5134.4  354.24  5164.6  356.07
  5235.3  358.35  5334.3  362.81  5419.1  367.90  5475.7  370.40  5574.7  376.12
#Mann=8,-1,0
  4135.8    0.05       0  4721.8    0.07       0  4827.9    0.05       0
  4903.7    0.12       0  4922.1    0.05       0  4926.7    0.12       0
  5085.5    0.05       0  5134.4    0.12       0
Bank Sta=4922.1,4926.7
Exp/Cntr=0.3,0.1

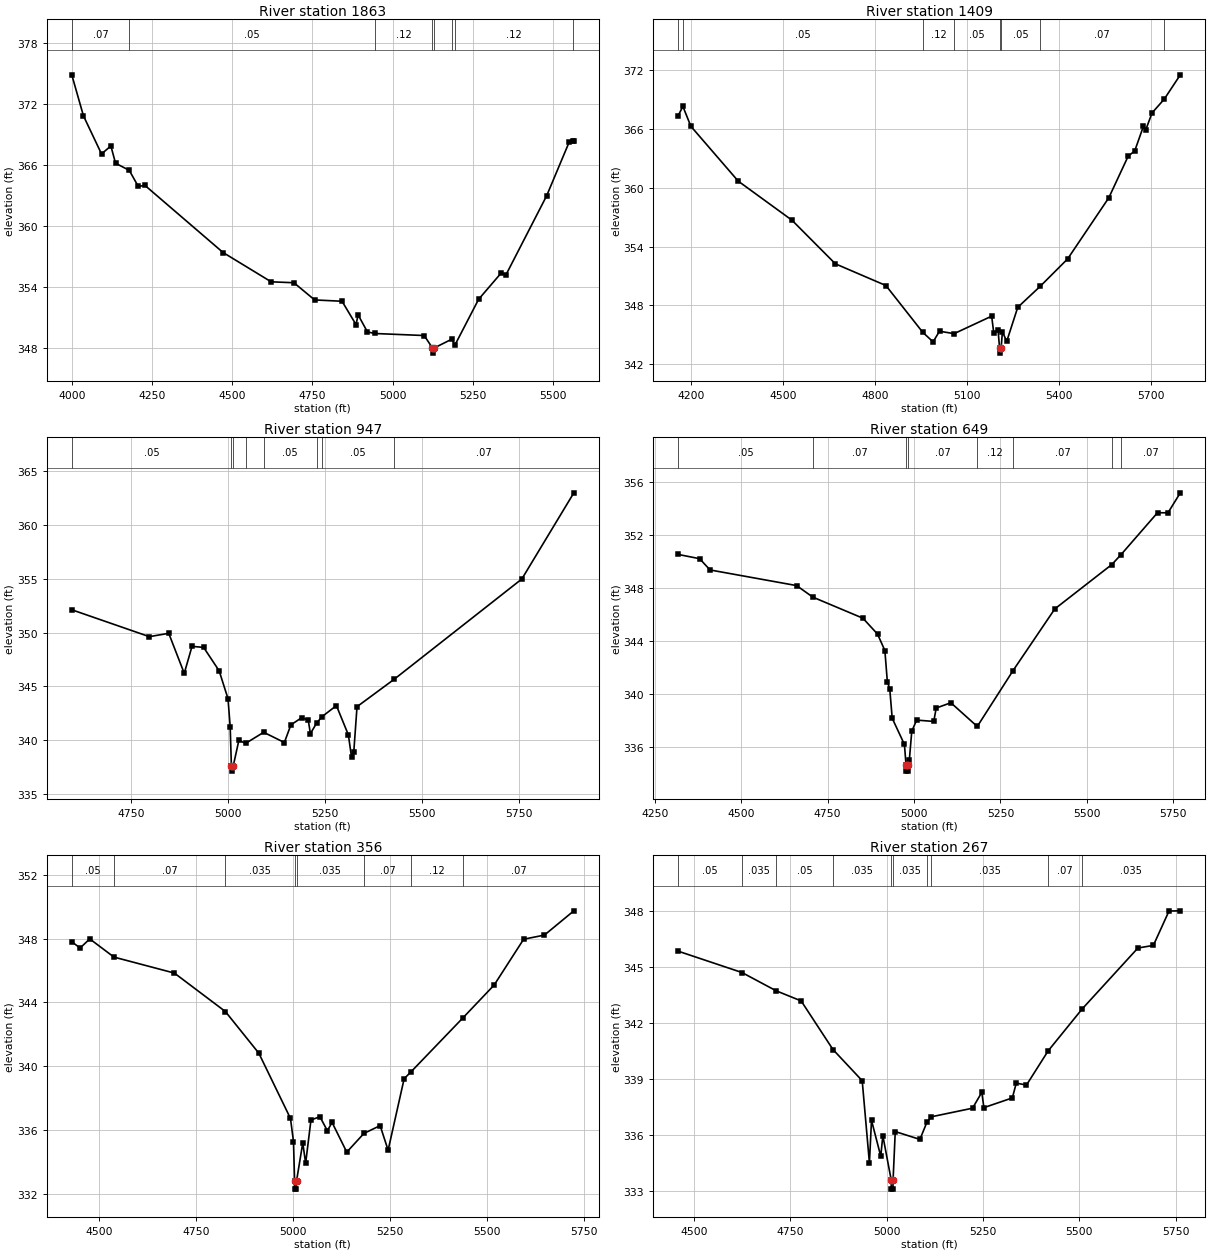
Type RM Length L Ch R = 1,1863,454,454,454
BEGIN DESCRIPTION:
Stream0281 3.0
END DESCRIPTION:
XS GIS Cut Line= 3
      2425475.03     13715725.04      2424875.00     13714925.00
      2424475.02     13714525.02
#Sta/Elev= 30
  3999.7  374.88  4036.2  370.84  4092.5  367.10  4121.6  367.89  4136.2  366.19
  4179.0  365.49  4207.0  363.91  4227.9  364.01  4471.6  357.41  4621.6  354.53
  4692.5  354.44  4757.0  352.75  4842.5  352.62  4886.2  350.32  4892.5  351.29
  4921.6  349.61  4944.2  349.45  5098.7  349.25  5124.6  348.02  5125.0  347.52
  5129.4  348.02  5185.4  348.90  5194.2  348.29  5268.4  352.81  5339.2  355.41
  5353.3  355.19  5480.6  362.99  5551.3  368.30  5563.8  368.37  5565.4  368.38
#Mann=8,-1,0
  3999.7    0.07       0  4179.0    0.05       0  4944.2    0.12       0
  5124.6    0.05       0  5129.4    0.12       0  5185.4    0.05       0
  5194.2    0.12       0  5563.8    0.07       0
Bank Sta=5124.6,5129.4
Exp/Cntr=0.3,0.1

Type RM Length L Ch R = 1,1409,462,462,462
BEGIN DESCRIPTION:
Stream0281 2.0
END DESCRIPTION:
XS GIS Cut Line= 3
      2425475.00     13715625.01      2425275.00     13714825.00
      2424724.98     13714224.98
#Sta/Elev= 30
  4157.6  367.39  4172.8  368.32  4198.8  366.29  4353.5  360.68  4528.7  356.69
  4670.4  352.23  4835.4  350.01  4955.3  345.24  4989.3  344.25  5010.3  345.34
  5057.9  345.09  5180.5  346.88  5187.3  345.18  5201.4  345.44  5206.4  343.60
  5206.7  343.10  5211.3  343.60  5215.6  345.27  5229.8  344.31  5265.6  347.78
  5338.6  349.92  5428.4  352.73  5562.8  358.98  5626.3  363.25  5647.3  363.76
  5675.6  366.27  5683.0  365.89  5704.0  367.66  5743.9  369.07  5796.2  371.55
#Mann=8,-1,0
  4157.6    0.07       0  4172.8    0.05       0  4955.3    0.12       0
  5057.9    0.05       0  5206.4    0.05       0  5211.3    0.05       0
  5338.6    0.07       0  5743.9   0.035       0
Bank Sta=5206.4,5211.3
Exp/Cntr=0.3,0.1

Type RM Length L Ch R = 1,947,298,298,298
BEGIN DESCRIPTION:
Stream0281 1.0
END DESCRIPTION:
XS GIS Cut Line= 3
      2425675.00     13715075.01      2425675.00     13714675.00
      2424875.03     13714275.02
#Sta/Elev= 30
  4596.3  352.13  4796.3  349.63  4846.3  349.94  4886.3  346.22  4906.3  348.73
  4936.3  348.63  4976.3  346.45  4999.1  343.86  5004.7  341.27  5007.8  337.63
  5008.2  337.13  5012.7  337.63  5027.1  339.99  5044.5  339.71  5091.1  340.74
  5144.4  339.79  5161.2  341.43  5189.2  342.10  5205.9  341.88  5211.5  340.62
  5228.2  341.63  5241.7  342.20  5278.6  343.22  5309.4  340.50  5317.7  338.40
  5323.3  338.89  5331.7  343.12  5427.2  345.66  5756.6  354.99  5890.7  363.00
#Mann=8,-1,0
  4596.3    0.05       0  5007.8    0.05       0  5012.7    0.05       0
  5044.5    0.07       0  5091.1    0.05       0  5228.2    0.12       0
  5241.7    0.05       0  5427.2    0.07       0
Bank Sta=5007.8,5012.7
Exp/Cntr=0.3,0.1

Type RM Length L Ch R = 1,649,293,293,293
BEGIN DESCRIPTION:
E20860
END DESCRIPTION:
XS GIS Cut Line= 4
      2425940.99     13715046.77      2425909.09     13714544.31
      2425685.77     13714320.99      2425059.83     13714225.31
#Sta/Elev= 30
  4317.8  350.52  4379.7  350.20  4409.8  349.35  4660.3  348.17  4707.1  347.30
  4852.0  345.71  4894.4  344.51  4915.6  343.27  4922.7  340.93  4929.7  340.38
  4936.8  338.16  4972.2  336.18  4976.7  334.67  4977.1  334.17  4981.3  334.17
  4981.7  334.67  4986.3  334.98  4993.4  337.18  5007.5  338.02  5057.0  337.92
  5064.1  338.93  5106.5  339.33  5182.9  337.54  5286.5  341.76  5407.2  346.41
  5572.2  349.76  5598.9  350.51  5704.4  353.67  5734.5  353.66  5770.3  355.17
#Mann=8,-1,0
  4317.8    0.05       0  4707.1    0.07       0  4976.7    0.05       0
  4981.7    0.07       0  5182.9    0.12       0  5286.5    0.07       0
  5572.2    0.12       0  5598.9    0.07       0
Bank Sta=4976.7,4981.7
Exp/Cntr=0.3,0.1

Type RM Length L Ch R = 1,356,89,89,89
BEGIN DESCRIPTION:
XS6334
END DESCRIPTION:
XS GIS Cut Line= 4
      2426062.49     13714745.69      2425929.00     13714280.60
      2425855.79     13714065.29      2425291.66     13714211.70
#Sta/Elev= 30
  4429.7  347.80  4451.2  347.41  4476.1  347.98  4538.5  346.84  4694.1  345.84
  4825.6  343.43  4911.8  340.82  4993.4  336.73  5001.2  335.28  5004.0  332.80
  5004.3  332.30  5008.6  332.30  5009.0  332.80  5025.1  335.20  5032.5  333.92
  5046.2  336.63  5069.2  336.84  5088.5  335.96  5100.6  336.48  5138.5  334.62
  5182.7  335.79  5224.5  336.28  5245.1  334.74  5286.4  339.22  5304.1  339.65
  5438.6  343.05  5518.4  345.09  5594.4  347.96  5648.0  348.22  5723.8  349.74
#Mann=8,-1,0
  4429.7    0.05       0  4538.5    0.07       0  4825.6   0.035       0
  5004.0   0.035       0  5009.0   0.035       0  5182.7    0.07       0
  5304.1    0.12       0  5438.6    0.07       0
Bank Sta=5004,5009
Exp/Cntr=0.3,0.1

Type RM Length L Ch R = 1,267,141,141,141
BEGIN DESCRIPTION:
XS6333
END DESCRIPTION:
XS GIS Cut Line= 4
      2426174.45     13714633.71      2425993.59     13714207.39
      2425851.49     13713858.59      2425396.17     13713940.21
#Sta/Elev= 30
  4459.4  345.84  4624.6  344.70  4713.5  343.72  4778.2  343.18  4860.7  340.58
  4936.6  338.91  4955.3  334.51  4960.7  336.79  4984.7  334.87  4990.1  335.97
  5011.7  333.61  5012.0  333.11  5016.3  333.11  5016.7  333.61  5022.3  336.19
  5086.3  335.77  5104.4  336.69  5115.9  336.98  5222.8  337.44  5246.8  338.29
  5252.2  337.47  5326.0  337.99  5336.2  338.78  5362.7  338.68  5419.0  340.51
  5506.7  342.74  5651.7  346.01  5691.8  346.15  5732.4  347.99  5761.7  348.00
#Mann=10,-1,0
  4459.4    0.05       0  4624.6   0.035       0  4713.5    0.05       0
  4860.7   0.035       0  5011.7   0.035       0  5016.7   0.035       0
  5104.4    0.07       0  5115.9   0.035       0  5419.0    0.07       0
  5506.7   0.035       0
Bank Sta=5011.7,5016.7
Exp/Cntr=0.3,0.1

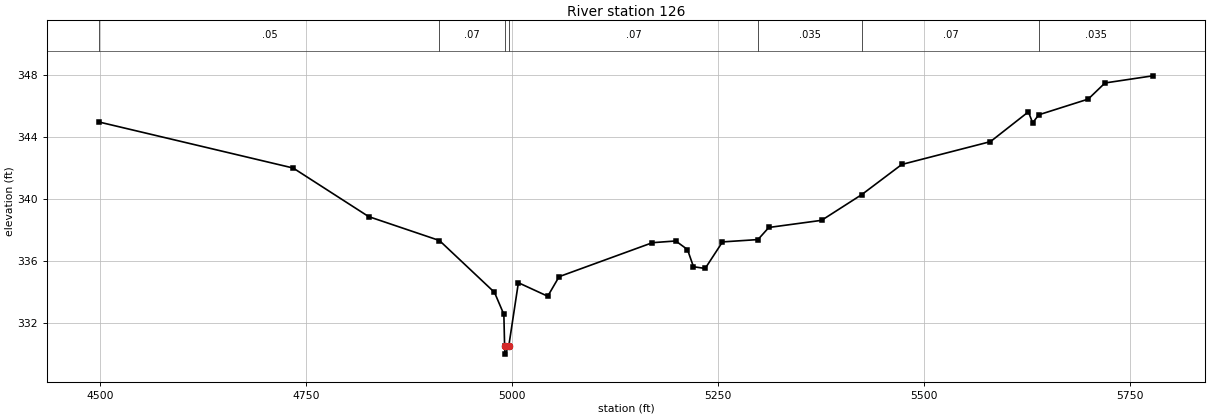
Type RM Length L Ch R = 1,126,0,0,0
BEGIN DESCRIPTION:
XS6332
END DESCRIPTION:
XS GIS Cut Line= 4
      2426161.54     13714526.09      2426071.10     13714043.76
      2425864.40     13713824.14      2425388.19     13713918.53
#Sta/Elev= 30
  4499.3  344.95  4734.4  341.99  4826.0  338.86  4911.8  337.32  4978.6  333.98
  4990.0  332.56  4990.9  330.50  4991.3  330.00  4995.9  330.50  5007.6  334.60
  5043.2  333.73  5057.0  334.99  5170.2  337.18  5198.5  337.29  5212.7  336.74
  5220.0  335.63  5234.2  335.52  5255.2  337.23  5298.2  337.38  5311.4  338.16
  5375.4  338.62  5424.2  340.28  5472.7  342.22  5580.2  343.69  5626.3  345.61
  5631.4  344.90  5638.9  345.42  5698.8  346.43  5719.2  347.47  5777.1  347.93
#Mann=7,-1,0
  4499.3    0.05       0  4911.8    0.07       0  4990.9    0.05       0
  4995.9    0.07       0  5298.2   0.035       0  5424.2    0.07       0
  5638.9   0.035       0
Bank Sta=4990.9,4995.9
Exp/Cntr=0.3,0.1

Chan Stop Cuts=-1