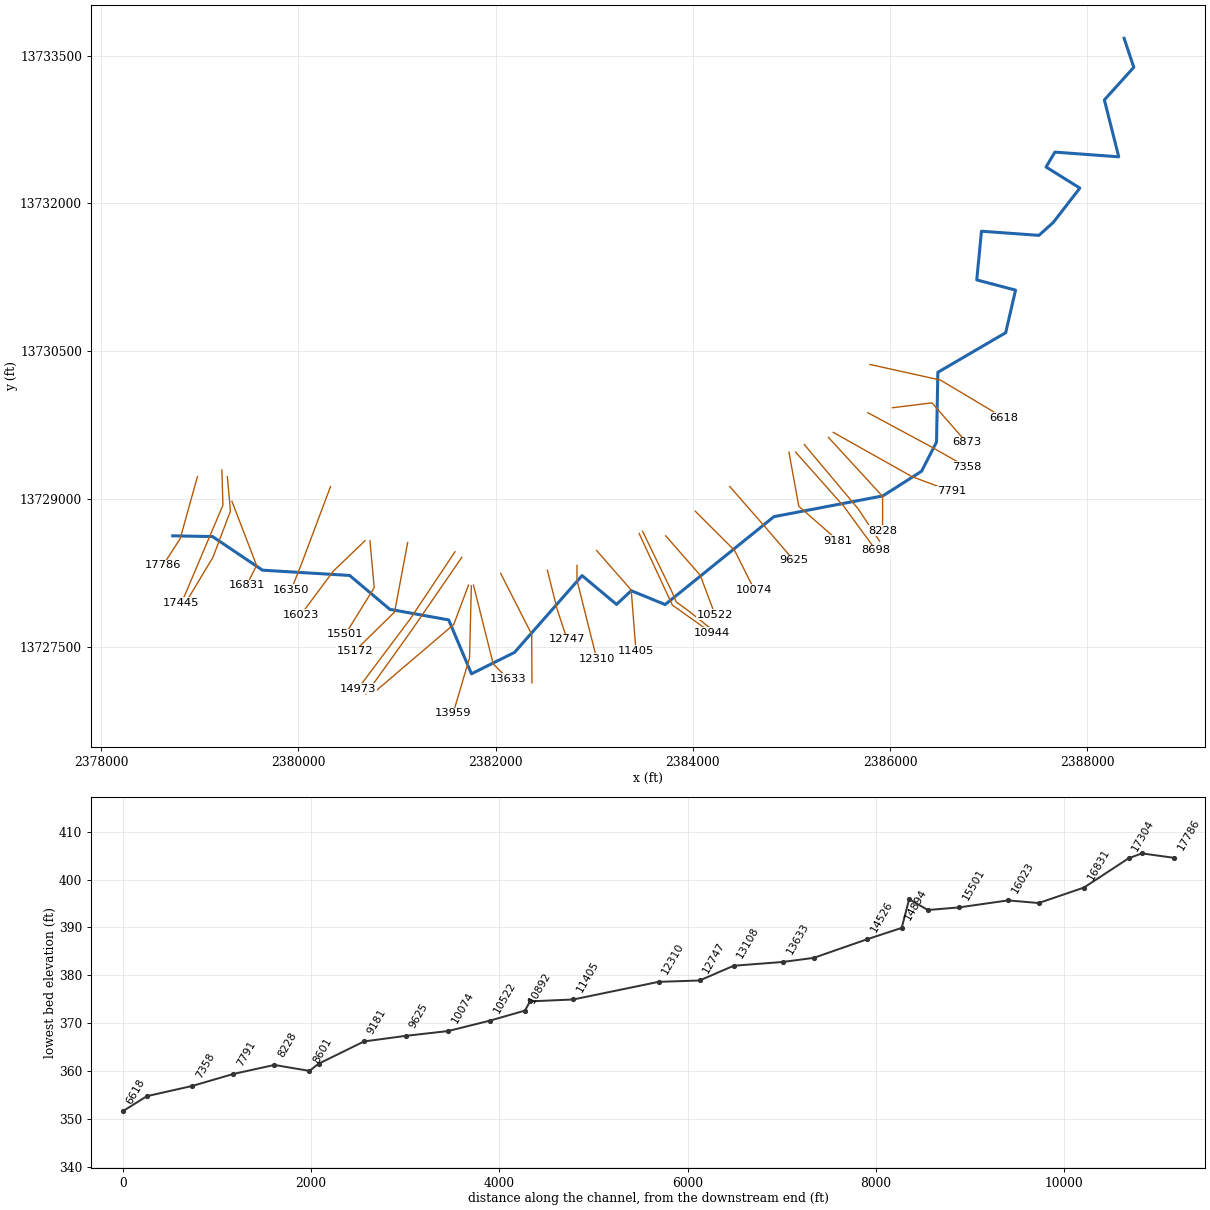
--- Stream0283.prj (project) ---

Proj Title=Stream0283 Base Level Engineering
Current Plan=p01
Default Exp/Contr=0.3,0.1
English Units
Geom File=g01
Flow File=f01
Plan File=p01
Y Axis Title=Elevation
X Axis Title(PF)=Main Channel Distance
X Axis Title(XS)=Station
BEGIN DESCRIPTION:
Stream0283
END DESCRIPTION:
DSS Export Rating Curves= 0
DSS Export Rating Curve Sorted= 0
DSS Export Volume Flow Curves= 0
DXF OffsetX= 0
DXF OffsetY= 0
DXF ScaleX= 1
DXF ScaleY= 10

--- Stream0283.p01 (plan) ---

Plan Title=Multiple Run
Short Identifier=Multiple
Geom File=g01
Flow File=f01
Subcritical Flow
K Sum by GR= 0
Std Step Tol= 0.01
Critical Tol= 0.01
Num of Std Step Trials= 20
Max Error Tol= 0.3
Flow Tol Ratio= 0.001
Split Flow NTrial= 30
Split Flow Tol= 0.02
Split Flow Ratio= 0.02
Log Output Level= 0
Friction Slope Method= 1
Unsteady Friction Slope Method= 2
Unsteady Bridges Friction Slope Method= 1
Parabolic Critical Depth
Global Vel Dist=  1 , 1 , 1
Global Log Level= 0
CheckData=True
Encroach Param= -1, 0, 0, 0
BEGIN DESCRIPTION:
Multiple Run
END DESCRIPTION:

--- Stream0283.f01 (steady flow) ---

Flow Title=Multiple
Number of Profiles=7
Profile Names=10-year,25-year,50-year,1pct_min,100-year,1pct_plu,500-year
River Rch & RM= Stream0283,Reach-1,17786
     792    1297    1759    1155    2304    4598    3920
River Rch & RM= Stream0283,Reach-1,16831
     912    1503    2047    1349    2691    5369    4610
River Rch & RM= Stream0283,Reach-1,13959
    1316    2213    3057    2040    4069    8119    7153
River Rch & RM= Stream0283,Reach-1,12747
    1545    2610    3615    2417    4822    9620    8510
River Rch & RM= Stream0283,Reach-1,3872
    1623    2736    3783    2524    5037   10049    8854
River Rch & RM= Stream0283,Reach-1,2213
    2009    3419    4758    3194    6373   12715   11338
Boundary for River Rch & Prof#=Stream0283,Reach-1,1
Up Type=0
Dn Type=3
Dn Slope=0.005
Boundary for River Rch & Prof#=Stream0283,Reach-1,2
Up Type=0
Dn Type=3
Dn Slope=0.005
Boundary for River Rch & Prof#=Stream0283,Reach-1,3
Up Type=0
Dn Type=3
Dn Slope=0.005
Boundary for River Rch & Prof#=Stream0283,Reach-1,4
Up Type=0
Dn Type=3
Dn Slope=0.005
Boundary for River Rch & Prof#=Stream0283,Reach-1,5
Up Type=0
Dn Type=3
Dn Slope=0.005
Boundary for River Rch & Prof#=Stream0283,Reach-1,6
Up Type=0
Dn Type=3
Dn Slope=0.005
Boundary for River Rch & Prof#=Stream0283,Reach-1,7
Up Type=0
Dn Type=3
Dn Slope=0.005

--- Stream0283.g01 (geometry) ---

Geom Title=Existing Conditions
Program Version=4.10

River Reach=Stream0283      ,Reach-1
Reach XY= 30
        2378725.       13728625.      2379128.33     13728617.39
       2379635.5      13728276.2      2380519.07     13728222.77
      2380926.58     13727878.82      2381523.55     13727771.47
      2381754.76      13727224.5      2382191.68     13727441.64
      2382876.47     13728221.46      2383226.58     13727928.42
      2383374.75     13728068.02      2383719.07     13727927.23
      2384822.58     13728819.46      2385927.44     13729030.39
      2386320.19     13729280.62      2386471.87     13729576.63
      2386485.51     13730284.81      2387173.38     13730686.81
      2387273.47     13731119.17      2386880.11     13731222.68
      2386927.84     13731716.99      2387509.66     13731674.95
      2387655.21     13731804.91      2387925.68     13732154.93
      2387582.76     13732368.79      2387672.68     13732519.99
      2388320.05     13732472.42      2388174.67     13733050.21
      2388472.86     13733380.97        2388375.       13733675.

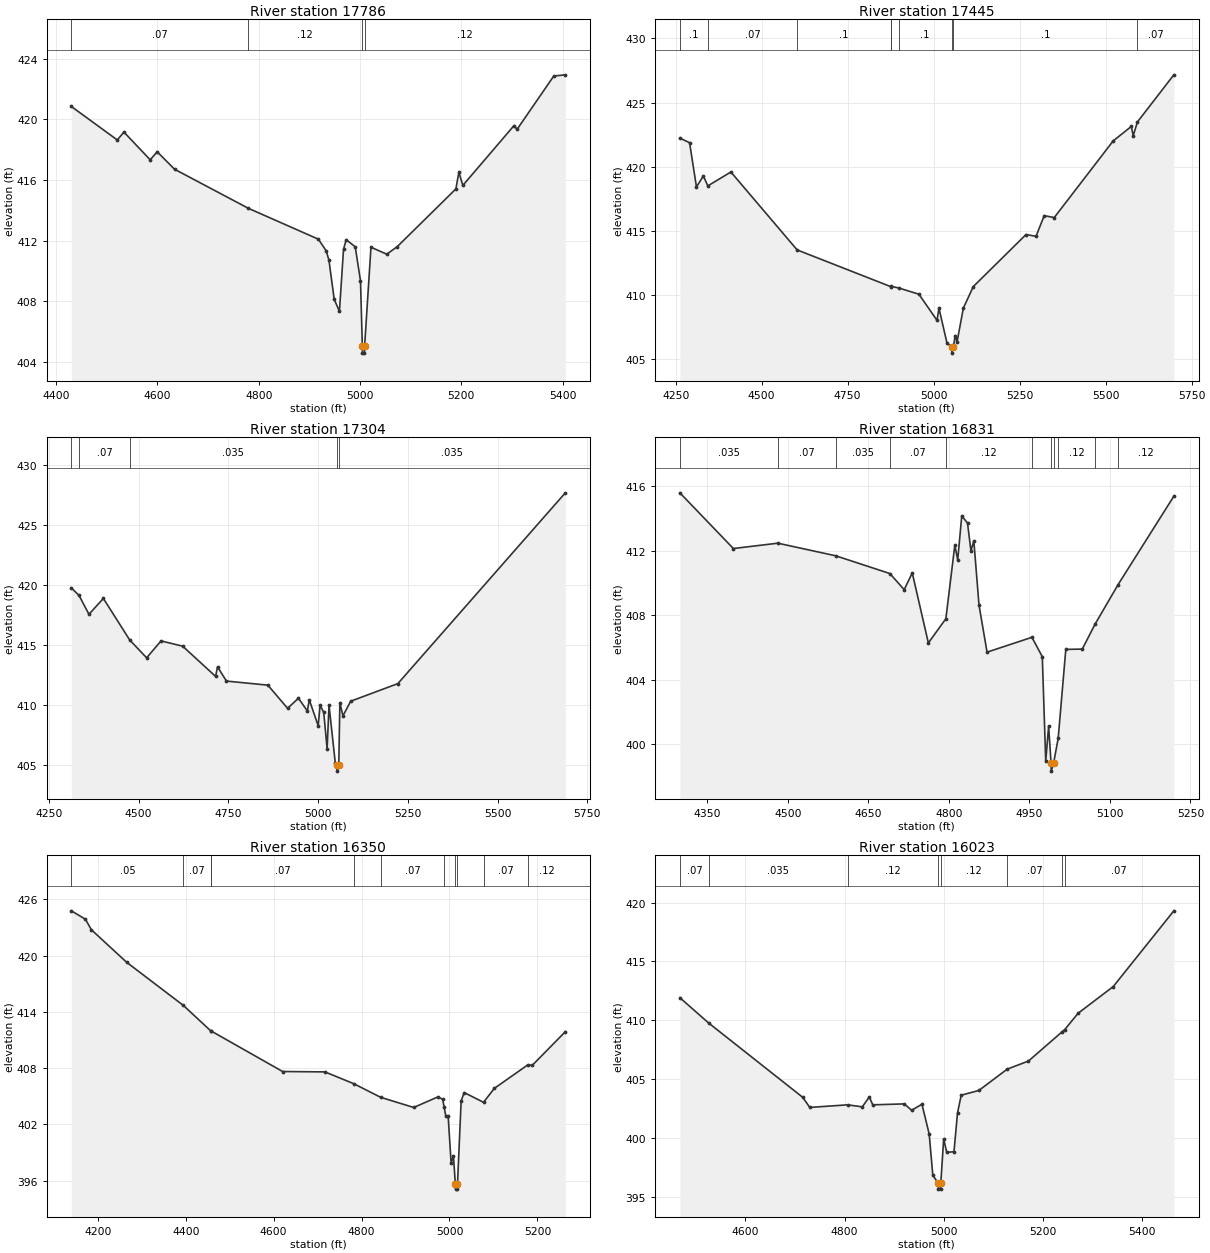
Type RM Length L Ch R = 1 ,17786   ,341,341,341
BEGIN DESCRIPTION:
Stream0283 33.0
END DESCRIPTION:
XS GIS Cut Line= 3
      2378975.01     13729225.02      2378799.58     13728595.33
      2378624.99     13728324.98
#Sta/Elev= 30
  4429.9  420.85  4520.6  418.64  4533.7  419.16  4585.6  417.33  4599.4  417.86
  4633.6  416.71  4779.4  414.13  4917.8  412.09  4933.2  411.32  4938.6   410.7
    4949  408.12  4959.3  407.33  4967.4  411.42  4972.6  412.06  4990.5  411.59
  5000.9  409.34  5004.5  405.07  5004.8  404.57  5008.8  404.57  5009.1  405.07
  5021.6  411.56  5052.8   411.1  5073.5   411.6  5189.3  415.41  5195.2  416.51
    5203  415.64  5304.1  419.59  5310.1  419.34  5382.6  422.86  5405.4  422.94
#Mann= 4 ,-1 , 0
  4429.9     .07       0  4779.4     .12       0  5004.5     .05       0
  5009.1     .12       0
Bank Sta=5004.5,5009.1
XS Rating Curve= 0 ,0
Exp/Cntr=0.3,0.1

Type RM Length L Ch R = 1 ,17445   ,141,141,141
BEGIN DESCRIPTION:
XS6360
END DESCRIPTION:
XS GIS Cut Line= 4
      2379223.19     13729293.21       2379233.6     13728935.61
      2379049.58     13728501.58      2378813.48     13727942.58
#Sta/Elev= 30
  4262.2  422.24  4290.4  421.88  4310.4  418.44  4330.4  419.29  4343.5  418.52
  4410.5   419.6  4603.1  413.53  4875.3  410.67  4876.8  410.69  4897.9  410.57
  4957.1  410.08  5009.8  408.04  5015.3     409  5038.9  406.25  5052.7  405.99
  5053.1  405.49  5057.4  405.99  5062.6  406.86    5068  406.36  5086.3     409
  5115.4  410.68  5268.5  414.73  5297.6  414.59  5321.3   416.2  5350.5  416.05
  5521.8  422.02  5574.7  423.15  5580.1  422.43  5592.4   423.5  5698.2  427.17
#Mann= 9 ,-1 , 0
  4262.2      .1       0  4343.5     .07       0  4603.1      .1       0
  4875.3     .07       0  4876.8     .12       0  4897.9      .1       0
  5052.7     .05       0  5057.4      .1       0  5592.4     .07       0
Bank Sta=5052.7,5057.4
XS Rating Curve= 0 ,0
Exp/Cntr=0.3,0.1

Type RM Length L Ch R = 1 ,17304   ,473,473,473
BEGIN DESCRIPTION:
Stream0283 32.0
END DESCRIPTION:
XS GIS Cut Line= 4
      2379278.74     13729223.83      2379309.99     13728876.58
      2379132.91     13728407.83       2378862.1     13727956.48
#Sta/Elev= 30
  4312.8  419.74  4334.2  419.11  4361.8  417.54    4402  418.86  4475.5  415.39
  4522.5  413.91  4562.6  415.32  4622.9  414.88  4714.6  412.36    4720  413.16
  4744.8  411.97  4860.2  411.63  4915.2   409.7  4945.4  410.54  4970.2  409.48
  4975.6  410.41  5000.4  408.25  5005.8  409.97  5015.9  409.35  5025.3  406.32
  5030.6  409.95    5048  405.16  5053.1  404.96  5053.4  404.46  5057.8  404.96
  5060.8  410.17  5069.4  409.07    5091  410.29  5222.4  411.76  5688.9  427.67
#Mann= 5 ,-1 , 0
  4312.8    .035       0  4334.2     .07       0  4475.5    .035       0
  5053.1    .035       0  5057.8    .035       0
Bank Sta=5053.1,5057.8
XS Rating Curve= 0 ,0
Exp/Cntr=0.3,0.1

Type RM Length L Ch R = 1 ,16831   ,481,481,481
BEGIN DESCRIPTION:
Stream0283 31.0
END DESCRIPTION:
XS GIS Cut Line= 3
      2379325.01     13728974.98        2379575.       13728325.
        2379475.     13728125.01
#Sta/Elev= 30
    4299  415.59  4398.6  412.14  4481.4  412.47  4589.2  411.69  4690.1  410.59
  4716.8  409.59  4731.8  410.63  4761.8  406.29  4794.4  407.79  4811.1  412.35
  4816.5  411.44    4824  414.16  4834.7  413.72  4841.1     412  4846.5  412.61
  4856.1  408.64  4871.1  405.72  4954.7  406.64    4974  405.44  4980.4  398.96
  4985.8  401.14  4990.3  398.85  4990.7  398.35  4995.1  398.85  5003.6  400.38
  5017.8  405.89  5048.5  405.91  5072.2  407.45  5115.3  409.91    5219  415.38
#Mann= 11 ,-1 , 0
    4299    .035       0  4481.4     .07       0  4589.2    .035       0
  4690.1     .07       0  4794.4     .12       0  4954.7     .07       0
  4990.3     .05       0  4995.1     .07       0  5003.6     .12       0
  5072.2     .07       0  5115.3     .12       0
Bank Sta=4990.3,4995.1
XS Rating Curve= 0 ,0
Exp/Cntr=0.3,0.1

Type RM Length L Ch R = 1 ,16350   ,327,327,327
BEGIN DESCRIPTION:
Stream0283 30.0
END DESCRIPTION:
XS GIS Cut Line= 3
      2380325.01     13729125.03        2380025.       13728325.
        2379925.     13728074.99
#Sta/Elev= 30
  4139.8  424.76  4171.9  423.86  4185.2  422.75  4265.3  419.29  4394.6  414.68
  4456.7  411.98  4457.7  411.96  4620.4  407.64  4716.6   407.6  4781.9  406.35
  4843.5  404.89  4918.6  403.81  4972.9  404.92  4984.4   404.7  4987.9  403.83
  4991.6  402.91  4996.9  402.91  5003.7  397.91    5009  398.63  5013.4  395.61
  5013.7  395.11  5017.8  395.11  5018.2  395.61  5026.5  404.49  5033.3   405.4
  5077.5  404.36  5101.9  405.84  5178.2  408.35  5188.1  408.29  5263.5  411.88
#Mann= 11 ,-1 , 0
  4139.8     .05       0  4394.6     .07       0  4456.7     .05       0
  4457.7     .07       0  4781.9     .05       0  4843.5     .07       0
  4987.9     .12       0  5013.4     .05       0  5018.2     .12       0
  5077.5     .07       0  5178.2     .12       0
Bank Sta=5013.4,5018.2
XS Rating Curve= 0 ,0
Exp/Cntr=0.3,0.1

Type RM Length L Ch R = 1 ,16023   ,522,522,522
BEGIN DESCRIPTION:
Stream0283 29.0
END DESCRIPTION:
XS GIS Cut Line= 3
      2380675.02     13728575.02      2380355.13     13728268.94
      2380024.98     13727824.98
#Sta/Elev= 30
    4468  411.92  4526.3  409.76  4715.7  403.46  4729.9   402.6  4806.1  402.82
  4835.8  402.65    4850  403.49  4856.9  402.82  4920.6   402.9  4935.2  402.36
  4956.1  402.87  4970.7  400.34    4978  396.84    4989  396.16  4989.4  395.66
  4993.7  395.66  4994.1  396.16  4999.9  399.93  5006.1  398.78  5020.7  398.84
  5027.8  402.13  5035.3  403.64  5070.8  404.04  5127.9  405.85  5170.9  406.54
  5238.6  409.02    5244  409.21    5271   410.6  5341.9  412.87    5464   419.3
#Mann= 8 ,-1 , 0
    4468     .07       0  4526.3    .035       0  4806.1     .12       0
    4989     .05       0  4994.1     .12       0  5127.9     .07       0
  5238.6     .12       0    5244     .07       0
Bank Sta=4989,4994.1
XS Rating Curve= 0 ,0
Exp/Cntr=0.3,0.1

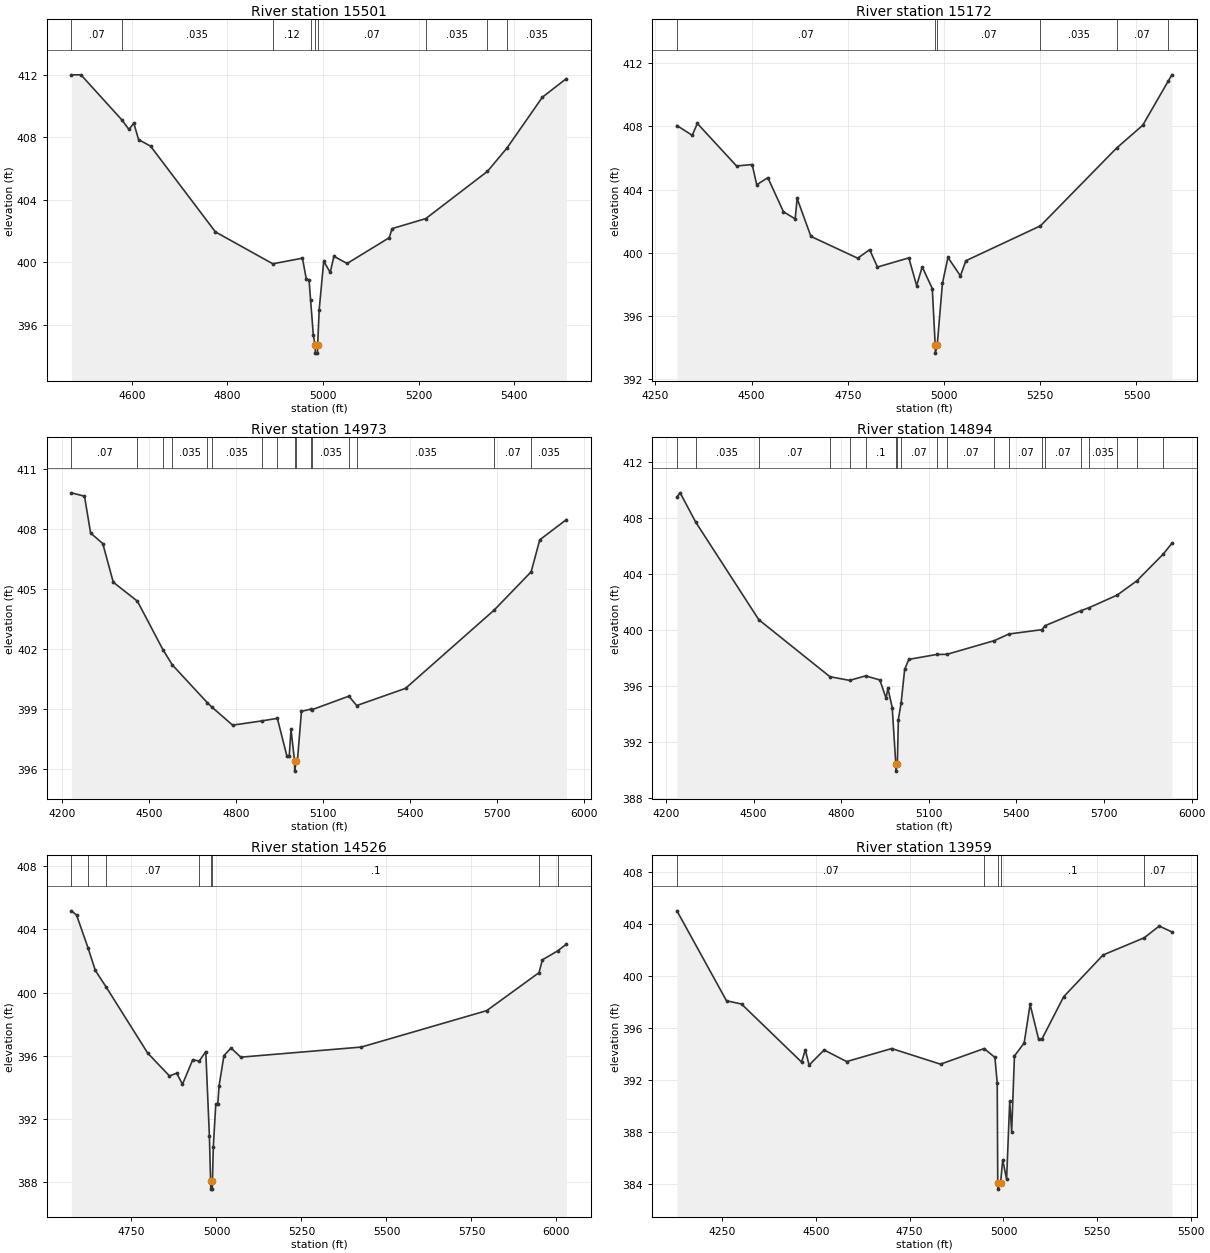
Type RM Length L Ch R = 1 ,15501   ,329,329,329
BEGIN DESCRIPTION:
Stream0283 28.0
END DESCRIPTION:
XS GIS Cut Line= 3
        2380725.     13728574.95      2380768.33      13728098.8
      2380474.98     13727624.97
#Sta/Elev= 30
  4473.5  411.98  4493.5  411.98  4578.4  409.12  4593.9  408.49    4604  408.89
    4614  407.84  4639.1  407.42  4774.7  401.94  4894.8   399.9  4956.8  400.26
  4964.7  398.95  4970.6  398.86  4973.9  397.56  4979.6  395.32  4983.4  394.69
  4983.8  394.19  4988.2  394.19  4988.6  394.69  4991.8  396.97  5001.3  400.06
  5014.9  399.35  5022.6  400.38  5050.2  399.92  5138.4  401.57  5144.3  402.15
  5214.8  402.79  5343.8  405.81  5384.6   407.3  5458.7  410.55  5508.9  411.74
#Mann= 9 ,-1 , 0
  4473.5     .07       0  4578.4    .035       0  4894.8     .12       0
  4973.9     .07       0  4983.4     .05       0  4988.6     .07       0
  5214.8    .035       0  5343.8     .07       0  5384.6    .035       0
Bank Sta=4983.4,4988.6
XS Rating Curve= 0 ,0
Exp/Cntr=0.3,0.1

Type RM Length L Ch R = 1 ,15172   ,199,199,199
BEGIN DESCRIPTION:
Stream0283 27.0
END DESCRIPTION:
XS GIS Cut Line= 3
      2381107.74     13728557.17      2380974.92     13727851.41
      2380569.37     13727453.65
#Sta/Elev= 30
  4305.9  408.06  4345.7  407.44    4359  408.19  4460.9   405.5  4501.4  405.59
  4513.3  404.31  4542.1  404.76  4582.8   402.6  4613.2  402.15  4618.3  403.44
  4654.1  401.04  4775.7  399.66  4806.7   400.2  4827.1   399.1  4908.5  399.68
  4928.8  397.93  4943.3  399.11  4969.5  397.74  4977.1  394.15  4977.5  393.65
  4982.3  394.15  4995.8  398.06  5010.2  399.71  5042.6  398.54  5056.8   399.5
  5250.6  401.71  5448.3  406.63  5516.4  408.08    5582  410.85  5592.1  411.27
#Mann= 6 ,-1 , 0
  4305.9     .07       0  4977.1     .05       0  4982.3     .07       0
  5250.6    .035       0  5448.3     .07       0    5582     .05       0
Bank Sta=4977.1,4982.3
XS Rating Curve= 0 ,0
Exp/Cntr=0.3,0.1

Type RM Length L Ch R = 1 ,14973   ,79,79,79
BEGIN DESCRIPTION:
XS6358
END DESCRIPTION:
XS GIS Cut Line= 3
       2381587.8     13728463.42      2381129.44     13727775.89
      2380601.64       13727071.
#Sta/Elev= 30
  4231.6  409.83  4276.7  409.66  4297.8  407.82  4339.8  407.29  4375.9  405.36
  4459.2  404.41    4547  401.99  4579.8  401.22  4700.5  399.33  4717.1   399.1
  4787.5  398.21  4887.2  398.42  4941.8  398.55  4974.9  396.65  4982.8  396.67
  4988.8     398  5001.2  396.41  5001.6  395.91  5006.5  396.41  5010.9  396.42
  5024.9   398.9  5057.3  399.01  5062.7  398.99  5188.4  399.66  5215.5  399.19
  5383.8  400.05  5689.8  403.97    5817  405.88  5846.7  407.48  5938.5  408.49
#Mann= 16 ,-1 , 0
  4231.6     .07       0  4459.2    .035       0    4547     .07       0
  4579.8    .035       0  4700.5     .07       0  4717.1    .035       0
  4887.2     .07       0  4941.8    .035       0  5001.2    .035       0
  5006.5    .035       0  5057.3     .07       0  5062.7    .035       0
  5188.4     .07       0  5215.5    .035       0  5689.8     .07       0
    5817    .035       0
Bank Sta=5001.2,5006.5
XS Rating Curve= 0 ,0
Exp/Cntr=0.3,0.1

Type RM Length L Ch R = 1 ,14894   ,368,368,368
BEGIN DESCRIPTION:
XS6359
END DESCRIPTION:
XS GIS Cut Line= 3
      2381657.22     13728407.84      2381139.85     13727654.36
      2380685.37     13727019.47
#Sta/Elev= 30
  4237.5  409.49  4248.6  409.78  4302.1  407.68  4517.9  400.72  4761.6  396.65
  4828.8  396.39  4883.5  396.71  4932.4  396.42  4953.7  395.11  4959.8  395.84
  4974.7  394.45    4987  390.41  4987.4  389.91  4992.3  390.41  4995.7  393.59
  5005.3  394.79  5017.3  397.17  5031.5  397.89  5127.2  398.24  5162.3  398.25
  5324.8  399.23  5374.1   399.7  5487.4  400.01  5497.8  400.29  5621.4  401.37
  5649.9  401.59  5745.1  402.48  5812.5   403.5  5903.3  405.42  5932.3  406.18
#Mann= 20 ,-1 , 0
  4237.5     .07       0  4302.1    .035       0  4517.9     .07       0
  4761.6      .1       0  4828.8    .035       0  4883.5      .1       0
    4987    .035       0  4992.3      .1       0  5005.3     .07       0
  5127.2      .1       0  5162.3     .07       0  5324.8    .035       0
  5374.1     .07       0  5487.4    .035       0  5497.8     .07       0
  5621.4      .1       0  5649.9    .035       0  5745.1     .07       0
  5812.5    .035       0  5903.3     .07       0
Bank Sta=4987,4992.3
XS Rating Curve= 0 ,0
Exp/Cntr=0.3,0.1

Type RM Length L Ch R = 1 ,14526   ,567,567,567
BEGIN DESCRIPTION:
Stream0283 26.0
END DESCRIPTION:
XS GIS Cut Line= 3
      2381725.01     13728125.04        2381575.       13727725.
      2380792.63     13727057.14
#Sta/Elev= 30
  4573.3  405.18  4588.5  404.91  4622.5  402.81  4643.6   401.4  4675.1  400.36
  4797.6  396.16  4861.7  394.71  4883.1  394.88    4900  394.18  4930.2  395.74
  4949.1  395.65  4968.5  396.25  4979.2  390.89  4982.7  388.03  4983.2  387.53
  4987.7  387.53  4988.1  388.03  4990.7  390.23  4997.9   392.9  5003.8   392.9
  5007.7   394.1    5022     396  5042.8  396.48  5071.4   395.9    5426  396.54
  5794.9  398.85  5948.8  401.26  5958.5  402.07  6003.6  402.64  6029.2  403.07
#Mann= 8 ,-1 , 0
  4573.3     .07       0  4622.5    .035       0  4675.1     .07       0
  4949.1      .1       0  4982.7     .05       0  4988.1      .1       0
  5948.8     .07       0  6003.6      .1       0
Bank Sta=4982.7,4988.1
XS Rating Curve= 0 ,0
Exp/Cntr=0.3,0.1

Type RM Length L Ch R = 1 ,13959   ,326,326,326
BEGIN DESCRIPTION:
XS6357
END DESCRIPTION:
XS GIS Cut Line= 3
      2381753.57     13728117.03      2381735.34     13727387.87
      2381568.66     13726822.72
#Sta/Elev= 30
  4130.1  405.02  4262.2  398.11  4302.2  397.86  4462.2   393.4  4472.2  394.34
  4482.2  393.17  4522.3  394.33  4582.3  393.44  4702.3  394.44  4832.3  393.24
  4948.6  394.44  4977.2  393.76  4983.4  391.81  4984.8  384.14  4985.3  383.64
  4992.4  384.14    4998  385.89  5008.4  384.41  5016.7   390.4  5021.9  388.06
  5029.3  393.87  5055.2  394.87    5071  397.83  5093.8  395.14  5102.3  395.16
  5160.4  398.42  5265.5  401.63  5375.1  402.95    5415  403.85  5448.7   403.4
#Mann= 5 ,-1 , 0
  4130.1     .07       0  4948.6      .1       0  4984.8     .05       0
  4992.4      .1       0  5375.1     .07       0
Bank Sta=4984.8,4992.4
XS Rating Curve= 0 ,0
Exp/Cntr=0.3,0.1

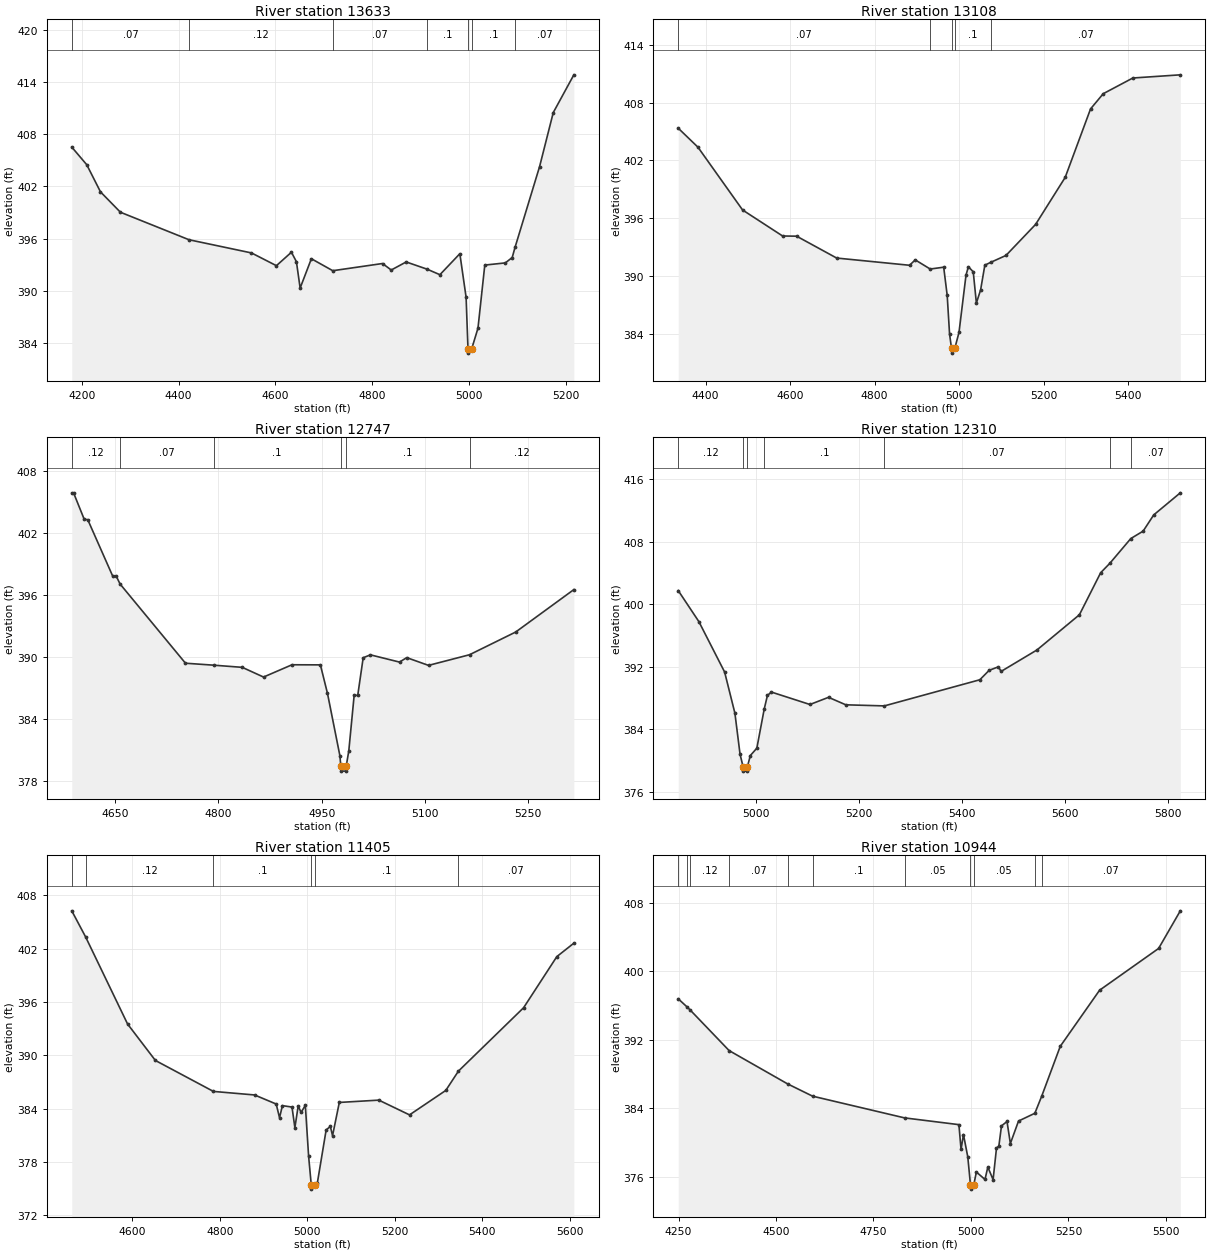
Type RM Length L Ch R = 1 ,13633   ,525,525,525
BEGIN DESCRIPTION:
Stream0283 25.0
END DESCRIPTION:
XS GIS Cut Line= 3
        2381775.     13728125.01        2381975.       13727325.
      2382125.02     13727174.98
#Sta/Elev= 30
  4179.6  406.54  4210.5  404.51  4238.9  401.38  4280.1  399.03  4421.7  395.86
  4550.7  394.34  4602.2  392.87  4633.2  394.42  4643.5  393.33  4651.2  390.29
  4674.4  393.67  4718.6  392.29  4821.3  393.12  4839.3  392.37  4870.2   393.3
  4913.7  392.46  4939.8  391.83    4981  394.25  4993.9  389.23  4997.8  383.29
  4998.3  382.79  5005.5  383.29  5018.4  385.66  5032.5  392.94  5074.9  393.19
  5089.1  393.81  5094.9  394.97  5145.7   404.3  5173.9  410.52  5216.4  414.87
#Mann= 7 ,-1 , 0
  4179.6     .07       0  4421.7     .12       0  4718.6     .07       0
  4913.7      .1       0  4997.8     .05       0  5005.5      .1       0
  5094.9     .07       0
Bank Sta=4997.8,5005.5
XS Rating Curve= 0 ,0
Exp/Cntr=0.3,0.1

Type RM Length L Ch R = 1 ,13108   ,361,361,361
BEGIN DESCRIPTION:
Stream0283 24.0
END DESCRIPTION:
XS GIS Cut Line= 3
      2382050.47     13728244.59      2382365.55     13727624.85
      2382368.15      13727132.7
#Sta/Elev= 30
  4335.4  405.34    4382  403.37  4487.6  396.85  4582.2  394.15  4615.4  394.13
  4710.1  391.86  4882.5  391.11  4895.9  391.67  4931.3  390.72  4963.2  390.91
  4971.5  387.98  4977.1  383.96  4981.7  382.49  4982.2  381.99  4989.5  382.49
  4999.4  384.14    5016  390.09  5021.6  390.96  5033.1  390.43  5040.5  387.19
  5050.5  388.55  5060.5  391.12  5074.2  391.41  5110.5  392.13  5180.5  395.35
  5250.5  400.23  5310.5  407.34  5340.5  408.92  5410.5  410.55  5522.8  410.88
#Mann= 5 ,-1 , 0
  4335.4     .07       0  4931.3      .1       0  4981.7     .05       0
  4989.5      .1       0  5074.2     .07       0
Bank Sta=4981.7,4989.5
XS Rating Curve= 0 ,0
Exp/Cntr=0.3,0.1

Type RM Length L Ch R = 1 ,12747   ,437,437,437
BEGIN DESCRIPTION:
Stream0283 23.0
END DESCRIPTION:
XS GIS Cut Line= 3
      2382524.99     13728275.03        2382625.       13727875.
      2382725.01     13727574.97
#Sta/Elev= 30
  4587.4  405.86    4590  405.86  4605.5  403.29  4610.6  403.26  4646.7  397.81
  4651.9  397.79  4657.5  397.03  4752.4  389.36  4793.3  389.17  4834.8  388.96
  4865.7  388.02    4907  389.21  4948.2   389.2  4958.5  386.43  4976.5   380.4
  4977.8  379.41  4978.3  378.91  4985.2  378.91  4985.7  379.41  4989.4  380.86
  4997.2  386.25  5002.4  386.25  5010.3  389.89  5020.8  390.17    5063  389.47
  5073.5   389.9  5105.1  389.15  5164.6  390.18  5231.6  392.38    5316  396.49
#Mann= 6 ,-1 , 0
  4587.4     .12       0  4657.5     .07       0  4793.3      .1       0
  4977.8     .05       0  4985.7      .1       0  5164.6     .12       0
Bank Sta=4977.8,4985.7
XS Rating Curve= 0 ,0
Exp/Cntr=0.3,0.1

Type RM Length L Ch R = 1 ,12310   ,905,905,905
BEGIN DESCRIPTION:
Stream0283 22.0
END DESCRIPTION:
XS GIS Cut Line= 3
        2382825.     13728325.05        2382825.       13728175.
      2383025.01     13727374.97
#Sta/Elev= 30
    4850  401.76    4890  397.79    4940  391.33    4960  386.05    4970  380.79
  4976.1  379.12  4976.6  378.62  4983.5  378.62    4984  379.12    4990  380.62
  5002.6  381.56    5017   386.6  5023.2  388.33    5031  388.75  5105.7  387.16
  5141.8  388.08  5175.3  387.12  5250.1  386.98  5435.5  390.33  5453.6  391.54
  5471.6  391.99  5476.8   391.4  5546.4  394.15  5628.8  398.66  5670.1  404.05
  5687.8  405.25  5728.6  408.43  5752.5  409.38  5773.1  411.46  5824.7  414.29
#Mann= 7 ,-1 , 0
    4850     .12       0  4976.1     .05       0    4984     .12       0
    5017      .1       0  5250.1     .07       0  5687.8     .12       0
  5728.6     .07       0
Bank Sta=4976.1,4984
XS Rating Curve= 0 ,0
Exp/Cntr=0.3,0.1

Type RM Length L Ch R = 1 ,11405   ,461,461,461
BEGIN DESCRIPTION:
Stream0283 21.0
END DESCRIPTION:
XS GIS Cut Line= 3
      2383025.03     13728474.97        2383375.       13728075.
      2383422.97     13727460.44
#Sta/Elev= 30
  4461.4  406.24  4493.1   403.3    4589  393.51  4652.6  389.41  4785.2  385.93
  4879.4  385.53  4928.8  384.51  4936.4  382.97    4943  384.33  4964.9  384.17
  4971.5  381.85  4979.1   384.3  4985.7  383.56  4995.4  384.37  5002.9  378.64
  5008.9  375.44  5009.4  374.94  5016.9  375.44    5023  375.67    5043   381.6
  5052.6  381.99  5057.6  380.95  5073.1  384.69  5163.4  384.95  5233.6  383.29
  5316.5  386.04  5345.4  388.21  5494.4  395.34  5570.4  401.09  5609.3   402.6
#Mann= 6 ,-1 , 0
  4461.4     .07       0  4493.1     .12       0  4785.2      .1       0
  5008.9     .05       0  5016.9      .1       0  5345.4     .07       0
Bank Sta=5008.9,5016.9
XS Rating Curve= 0 ,0
Exp/Cntr=0.3,0.1

Type RM Length L Ch R = 1 ,10944   ,52,52,52
BEGIN DESCRIPTION:
Stream0283 20.0
END DESCRIPTION:
XS GIS Cut Line= 3
      2383455.27     13728648.81      2383792.18     13727921.93
      2384189.11     13727640.39
#Sta/Elev= 30
  4249.3  396.79  4271.3  395.87  4279.8  395.49  4379.8  390.74  4529.6  386.85
  4593.9  385.41  4829.8  382.87  4969.2  382.08  4974.7  379.19  4980.9  380.92
    4992   378.3  4998.9  375.04  4999.4  374.54  5007.3  375.04    5014  376.54
  5036.1  375.67  5043.4  377.12  5056.9  375.65  5065.6  379.33  5071.7  379.58
  5078.4  381.93  5092.6  382.45  5101.2  379.87  5122.1   382.5    5164  383.41
  5181.6  385.41  5229.2  391.24  5330.1   397.8  5481.4  402.68  5537.1  407.08
#Mann= 11 ,-1 , 0
  4249.3     .12       0  4271.3     .07       0  4279.8     .12       0
  4379.8     .07       0  4529.6     .12       0  4593.9      .1       0
  4829.8     .05       0  4998.9     .05       0  5007.3     .05       0
    5164     .12       0  5181.6     .07       0
Bank Sta=4998.9,5007.3
XS Rating Curve= 0 ,0
Exp/Cntr=0.3,0.1

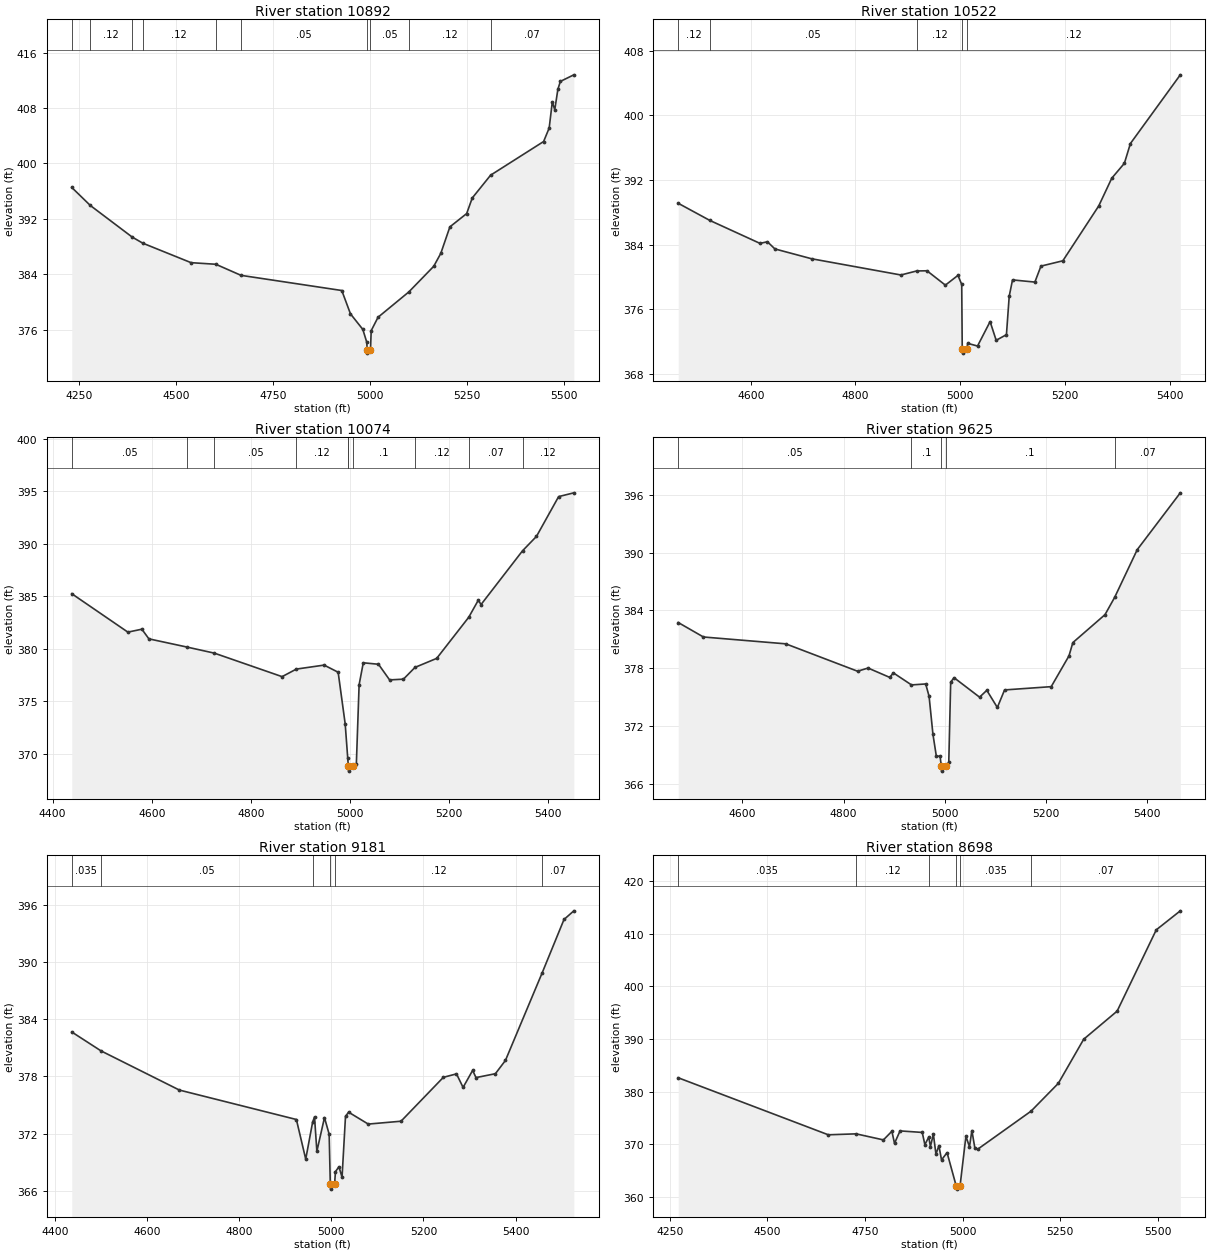
Type RM Length L Ch R = 1 ,10892   ,370,370,370
BEGIN DESCRIPTION:
XS6356
END DESCRIPTION:
XS GIS Cut Line= 5
      2383489.89     13728671.87      2383787.56     13728058.07
       2383831.4     13727954.24      2383958.32     13727861.93
        2384226.     13727647.33
#Sta/Elev= 30
  4231.4  396.54  4279.2  393.94  4387.1  389.38  4414.7  388.49  4539.1  385.68
  4602.9  385.45  4667.9  383.85  4927.8  381.66  4950.2  378.29    4982  376.05
  4992.2   374.2  4993.4  373.12  4993.9  372.62  5001.8  373.12  5003.7  375.87
  5021.3   377.8  5100.8  381.46    5165  385.16  5183.2  387.03  5206.6  390.85
  5249.9  392.77  5264.3  395.02  5311.6  398.31  5448.3  403.17  5462.7  405.12
  5470.7  408.88  5477.1  407.76  5485.1   410.7  5491.5  411.85  5526.3   412.8
#Mann= 10 ,-1 , 0
  4231.4     .07       0  4279.2     .12       0  4387.1     .07       0
  4414.7     .12       0  4602.9      .1       0  4667.9     .05       0
  4993.4     .05       0  5001.8     .05       0  5100.8     .12       0
  5311.6     .07       0
Bank Sta=4993.4,5001.8
XS Rating Curve= 0 ,0
Exp/Cntr=0.3,0.1

Type RM Length L Ch R = 1 ,10522   ,448,448,448
BEGIN DESCRIPTION:
Stream0283 19.0
END DESCRIPTION:
XS GIS Cut Line= 3
      2383725.03     13728624.97        2384075.       13728225.
      2384225.01     13727824.97
#Sta/Elev= 30
  4461.6  389.11  4521.8  386.99  4617.7  384.14  4631.9  384.34  4646.2  383.45
  4716.4  382.23  4886.8  380.22    4917  380.72  4936.6  380.74  4971.7  378.96
  4995.7  380.17  5002.9  379.05  5003.9  371.03  5004.4  370.53  5012.4  371.03
  5014.4  371.74  5033.1  371.41  5057.1  374.44  5068.7  372.12  5088.3  372.82
  5093.6  377.59  5099.9  379.61  5142.6  379.34  5154.2  381.32    5196  381.98
  5264.5  388.78  5289.4  392.22  5313.5  394.07    5325  396.52  5420.3  405.04
#Mann= 5 ,-1 , 0
  4461.6     .12       0  4521.8     .05       0    4917     .12       0
  5003.9     .05       0  5012.4     .12       0
Bank Sta=5003.9,5012.4
XS Rating Curve= 0 ,0
Exp/Cntr=0.3,0.1

Type RM Length L Ch R = 1 ,10074   ,449,449,449
BEGIN DESCRIPTION:
Stream0283 18.0
END DESCRIPTION:
XS GIS Cut Line= 3
      2384024.98     13728875.02        2384425.       13728475.
      2384624.99     13728075.02
#Sta/Elev= 30
  4438.5  385.23  4551.7  381.57  4579.9  381.85  4594.1  380.93  4670.8  380.15
  4726.1  379.57  4862.8  377.33  4891.6  378.05  4947.6  378.43  4975.9  377.75
  4990.1  372.83  4995.2  369.59  4996.4  368.83  4996.9  368.33    5005  368.83
  5012.6  368.97  5018.2  376.56  5026.6  378.65  5057.3  378.51  5079.7  377.02
  5107.6  377.09  5130.9  378.21  5174.7  379.07  5239.4  382.99  5258.6  384.61
  5264.2   384.2  5347.9  389.32    5376  390.69  5420.7  394.48  5451.4  394.84
#Mann= 10 ,-1 , 0
  4438.5     .05       0  4670.8     .07       0  4726.1     .05       0
  4891.6     .12       0  4995.2      .1       0  4996.4     .05       0
    5005      .1       0  5130.9     .12       0  5239.4     .07       0
  5347.9     .12       0
Bank Sta=4996.4,5005
XS Rating Curve= 0 ,0
Exp/Cntr=0.3,0.1

Type RM Length L Ch R = 1 ,9625    ,444,444,444
BEGIN DESCRIPTION:
Stream0283 17.0
END DESCRIPTION:
XS GIS Cut Line= 3
      2384375.02     13729124.98        2384725.       13728725.
      2385025.03     13728374.96
#Sta/Elev= 30
  4473.2  382.74    4523  381.24  4685.8  380.53  4827.7  377.69  4848.5  378.02
  4891.3  377.05  4898.4  377.52  4934.3  376.27  4962.4  376.37  4969.1  375.08
  4976.7  371.15  4983.3  368.92  4990.9  368.85  4993.2  367.83  4993.7  367.33
  5001.9  367.83    5008  368.25  5011.8  376.56  5018.4  377.02  5068.9     375
  5083.2  375.71    5104  373.93  5118.3  375.75  5210.5  376.09  5245.6  379.28
  5253.3  380.66  5316.9  383.56    5336  385.36  5380.6   390.3  5465.7  396.19
#Mann= 5 ,-1 , 0
  4473.2     .05       0  4934.3      .1       0  4993.2     .05       0
  5001.9      .1       0    5336     .07       0
Bank Sta=4993.2,5001.9
XS Rating Curve= 0 ,0
Exp/Cntr=0.3,0.1

Type RM Length L Ch R = 1 ,9181    ,483,483,483
BEGIN DESCRIPTION:
Stream0283 16.0
END DESCRIPTION:
XS GIS Cut Line= 3
      2384974.99     13729475.04        2385075.       13728925.
      2385475.03     13728574.97
#Sta/Elev= 30
  4436.1  382.66  4499.8  380.67  4669.9  376.56    4924  373.47  4944.3  369.31
  4959.3   373.2  4963.4  373.74  4968.5  370.13    4985  373.67  4995.2  371.93
  4997.7  366.66  4998.2  366.16  5006.9  366.66  5008.9     368  5016.5  368.51
  5023.2   367.4  5030.7   373.8  5037.4  374.24  5080.1  372.99  5151.3  373.29
  5243.3   377.9  5271.8  378.26  5286.1  376.84  5306.9  378.63  5314.1  377.87
  5356.3  378.28  5378.1  379.67    5458  388.88  5505.3  394.47  5526.7  395.38
#Mann= 6 ,-1 , 0
  4436.1    .035       0  4499.8     .05       0  4959.3     .12       0
  4997.7     .05       0  5006.9     .12       0    5458     .07       0
Bank Sta=4997.7,5006.9
XS Rating Curve= 0 ,0
Exp/Cntr=0.3,0.1

Type RM Length L Ch R = 1 ,8698    ,97,97,97
BEGIN DESCRIPTION:
Stream0283 15.0
END DESCRIPTION:
XS GIS Cut Line= 3
      2385042.52     13729474.94      2385533.36     13728921.51
      2385856.18      13728480.1
#Sta/Elev= 30
  4271.3  382.64  4655.8  371.81  4727.2  371.99  4797.1  370.84  4818.8  372.48
  4825.5  370.18  4839.7  372.55  4896.6  372.26  4903.3  369.94  4913.3  371.38
  4917.5  369.58  4925.1  371.92  4931.7  368.15  4939.3  369.73    4946  367.04
  4960.2  368.42    4984  361.99  4984.5  361.49  4993.3  361.99  5008.5  371.53
  5017.6  369.55  5023.8  372.61  5031.5  369.26  5038.5  369.06  5175.4   376.3
  5245.4  381.59  5310.3  389.96    5396   395.3  5496.3  410.74  5557.9  414.35
#Mann= 6 ,-1 , 0
  4271.3    .035       0  4727.2     .12       0  4913.3    .035       0
    4984    .035       0  4993.3    .035       0  5175.4     .07       0
Bank Sta=4984,4993.3
XS Rating Curve= 0 ,0
Exp/Cntr=0.3,0.1

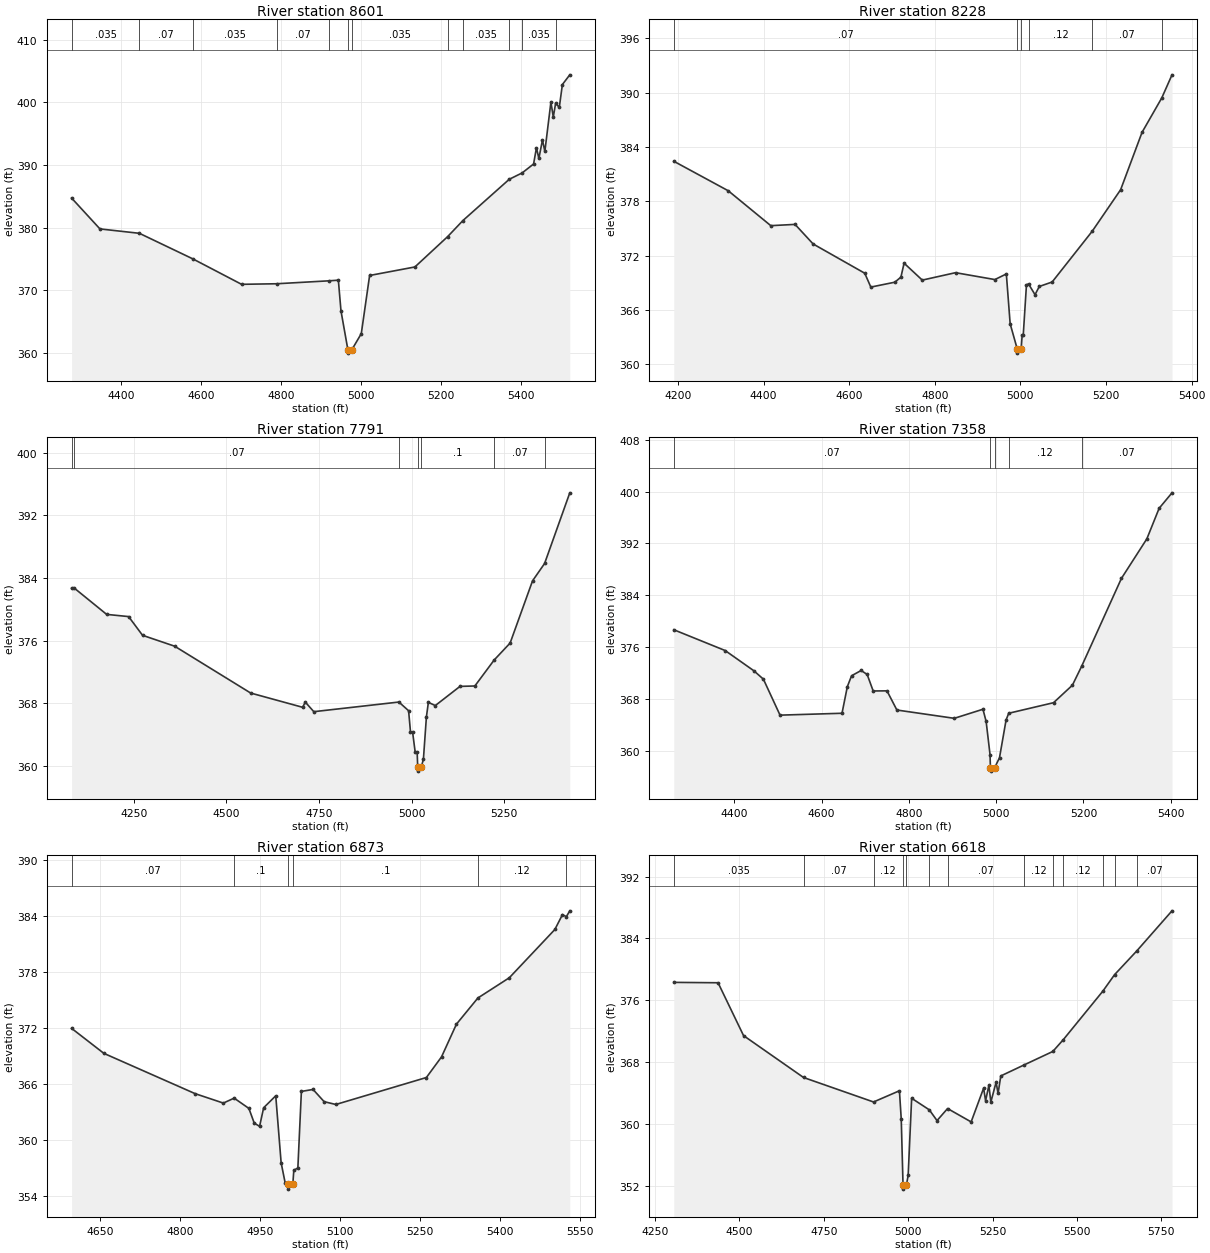
Type RM Length L Ch R = 1 ,8601    ,373,373,373
BEGIN DESCRIPTION:
XS6355
END DESCRIPTION:
XS GIS Cut Line= 3
      2385131.44     13729550.73      2385675.01     13728901.75
      2385895.38     13728569.54
#Sta/Elev= 30
  4276.4  384.75  4347.3  379.82  4445.9  379.12  4579.8  375.03  4701.3  370.98
    4789  371.07  4919.9  371.54  4943.2  371.64  4949.7  366.76  4967.1   360.5
  4967.6     360  4976.5   360.5  5000.5  363.11  5021.3  372.39  5134.5  373.75
  5216.3  378.59  5254.4  381.15  5370.3  387.74  5402.6  388.76  5431.1  390.18
  5438.3  392.77  5444.3  391.06  5453.3  394.01  5459.3  392.19  5474.4  400.05
  5480.4  397.68  5486.2  399.87  5495.4  399.22  5503.1  402.86  5521.6  404.41
#Mann= 12 ,-1 , 0
  4276.4    .035       0  4445.9     .07       0  4579.8    .035       0
    4789     .07       0  4919.9    .035       0  4967.1    .035       0
  4976.5    .035       0  5216.3     .07       0  5254.4    .035       0
  5370.3     .07       0  5402.6    .035       0  5486.2     .07       0
Bank Sta=4967.1,4976.5
XS Rating Curve= 0 ,0
Exp/Cntr=0.3,0.1

Type RM Length L Ch R = 1 ,8228    ,437,437,437
BEGIN DESCRIPTION:
Stream0283 14.0
END DESCRIPTION:
XS GIS Cut Line= 3
      2385375.03     13729624.97        2385925.       13729025.
        2385925.       13728675.
#Sta/Elev= 30
  4190.2  382.42  4317.5  379.16  4416.8  375.31  4473.5  375.45  4515.7  373.29
  4636.3  370.06  4650.5  368.53  4706.6  369.07  4720.8  369.63  4728.2  371.17
  4770.7   369.3  4848.4  370.12  4940.3  369.36  4967.1  369.98    4976  364.48
  4992.3  361.74  4992.8  361.24  5001.7  361.74  5004.1  363.24  5006.6  363.24
  5014.1  368.78  5018.9  368.88  5034.1  367.69  5044.1   368.6  5074.1  369.09
  5167.8   374.7  5234.1  379.28  5284.1  385.61  5330.2  389.41  5354.1  391.96
#Mann= 6 ,-1 , 0
  4190.2     .07       0  4992.3     .05       0  5001.7     .07       0
  5018.9     .12       0  5167.8     .07       0  5330.2    .035       0
Bank Sta=4992.3,5001.7
XS Rating Curve= 0 ,0
Exp/Cntr=0.3,0.1

Type RM Length L Ch R = 1 ,7791    ,433,433,433
BEGIN DESCRIPTION:
Stream0283 13.0
END DESCRIPTION:
XS GIS Cut Line= 3
      2385424.97     13729675.01        2386225.       13729225.
      2386624.99       13729075.
#Sta/Elev= 30
    4082  382.68  4087.9  382.77  4176.7  379.36    4236  379.08  4273.6  376.69
  4360.3   375.3  4565.5  369.32  4705.7   367.5  4713.1  368.16    4736  366.94
  4965.7  368.17  4991.9  367.06    4997  364.37  5002.6  364.37  5009.7  361.77
    5015   361.8  5016.5  359.85    5017  359.35    5026  359.85  5031.9  360.87
    5040  366.27  5045.3  368.13    5064  367.72  5130.7  370.17  5170.8  370.22
    5223  373.54    5266   375.7  5326.5  383.64  5359.1  385.86  5427.1  394.88
#Mann= 7 ,-1 , 0
    4082    .035       0  4087.9     .07       0  4965.7      .1       0
  5016.5     .05       0    5026      .1       0    5223     .07       0
  5359.1     .12       0
Bank Sta=5016.5,5026
XS Rating Curve= 0 ,0
Exp/Cntr=0.3,0.1

Type RM Length L Ch R = 1 ,7358    ,485,485,485
BEGIN DESCRIPTION:
Stream0283 12.0
END DESCRIPTION:
XS GIS Cut Line= 3
      2385774.96     13729875.02        2386425.       13729525.
        2386775.       13729325.
#Sta/Elev= 30
  4261.4  378.68  4379.1  375.47  4444.8  372.35  4466.7  371.05  4504.8   365.5
  4646.8  365.79    4659   369.9  4668.7  371.58  4690.6  372.39  4704.4  371.78
  4718.2  369.23  4749.8  369.25  4772.5  366.29    4904  365.01  4969.7  366.41
    4977  364.52  4985.9  359.42  4986.8  357.36  4987.3  356.86  4996.3  357.36
  5007.6  358.93  5022.7  364.76  5028.7  365.79  5131.4  367.42  5174.6  370.12
  5195.7  373.03  5286.9   386.6  5345.2  392.71  5373.3  397.42  5402.8  399.81
#Mann= 5 ,-1 , 0
  4261.4     .07       0  4986.8     .05       0  4996.3     .07       0
  5028.7     .12       0  5195.7     .07       0
Bank Sta=4986.8,4996.3
XS Rating Curve= 0 ,0
Exp/Cntr=0.3,0.1

Type RM Length L Ch R = 1 ,6873    ,255,255,255
BEGIN DESCRIPTION:
Stream0283 11.0
END DESCRIPTION:
XS GIS Cut Line= 3
      2386024.98       13729925.        2386425.       13729975.
      2386774.98     13729575.03
#Sta/Elev= 30
  4596.9  371.94  4657.4  369.26  4828.7  364.94  4881.6  363.93  4901.9  364.46
  4929.5  363.36  4939.6  361.78  4949.6  361.44  4957.2  363.43  4979.9  364.71
    4990  357.54  4997.5   355.4  5002.3  355.21  5002.8  354.71  5011.9  355.21
  5013.8  356.73  5021.4  356.98    5028  365.18  5049.9  365.39  5070.7  364.08
  5092.6  363.78  5262.5  366.67  5290.9  368.88  5318.9  372.39  5359.1  375.19
  5418.1  377.36  5503.5  382.53  5517.8  384.13    5525   383.9  5531.5  384.53
#Mann= 6 ,-1 , 0
  4596.9     .07       0  4901.9      .1       0  5002.3     .05       0
  5011.9      .1       0  5359.1     .12       0    5525     .07       0
Bank Sta=5002.3,5011.9
XS Rating Curve= 0 ,0
Exp/Cntr=0.3,0.1

Type RM Length L Ch R = 1 ,6618    ,364,364,364
BEGIN DESCRIPTION:
XS6354
END DESCRIPTION:
XS GIS Cut Line= 3
      2385796.87     13730364.35      2386511.72     13730206.23
      2387150.42     13729824.33
#Sta/Elev= 30
  4305.4  378.32  4436.6  378.27  4512.1  371.43  4689.8  366.01  4897.3  362.84
    4974  364.29  4979.4  360.62  4984.7  352.06  4985.2  351.56  4994.6  352.06
  4999.9  353.35  5010.2  363.32  5062.6  361.82  5085.4  360.43  5116.7  361.99
  5186.5  360.26  5223.5  364.63  5229.3     363  5239.1     365  5244.9  362.83
  5260.5   365.4  5266.3  363.94  5274.4  366.21  5343.2  367.63  5428.6  369.38
  5459.9  370.92  5576.7  377.18  5611.6  379.32  5677.1  382.38  5781.7  387.58
#Mann= 13 ,-1 , 0
  4305.4    .035       0  4689.8     .07       0  4897.3     .12       0
  4984.7     .05       0  4994.6     .12       0  5062.6      .1       0
  5116.7     .07       0  5343.2     .12       0  5428.6      .1       0
  5459.9     .12       0  5576.7      .1       0  5611.6     .12       0
  5677.1     .07       0
Bank Sta=4984.7,4994.6
XS Rating Curve= 0 ,0
Exp/Cntr=0.3,0.1