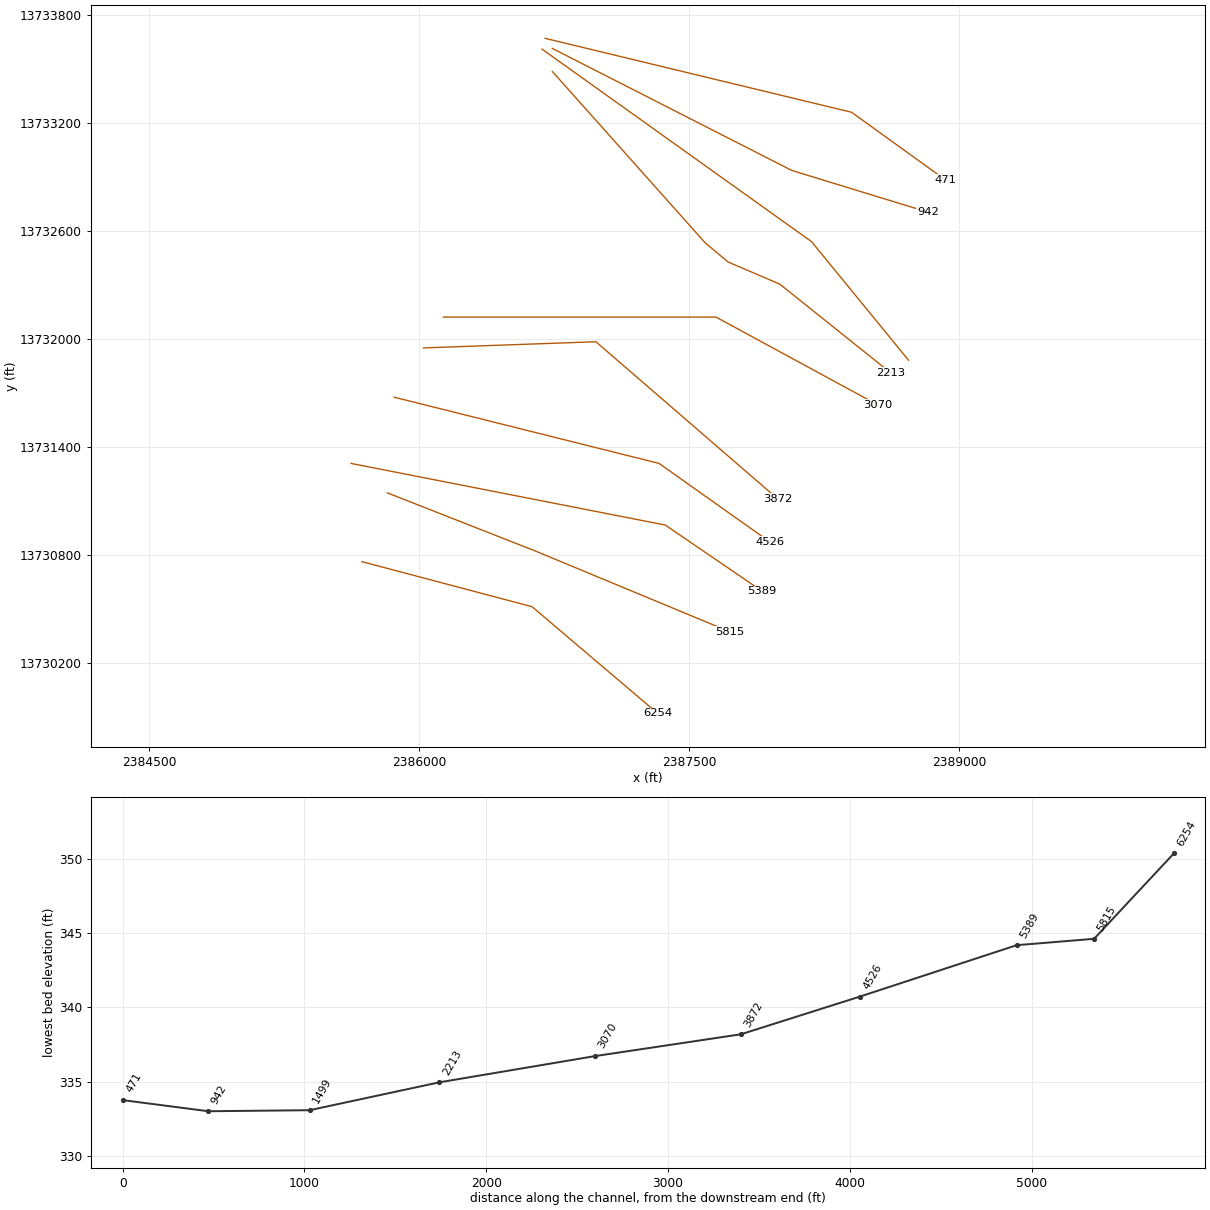
HEC-RAS study Stream0283.prj: Stream0283 Base Level Engineering

--- Stream0283.g01 (geometry) --- (continued)

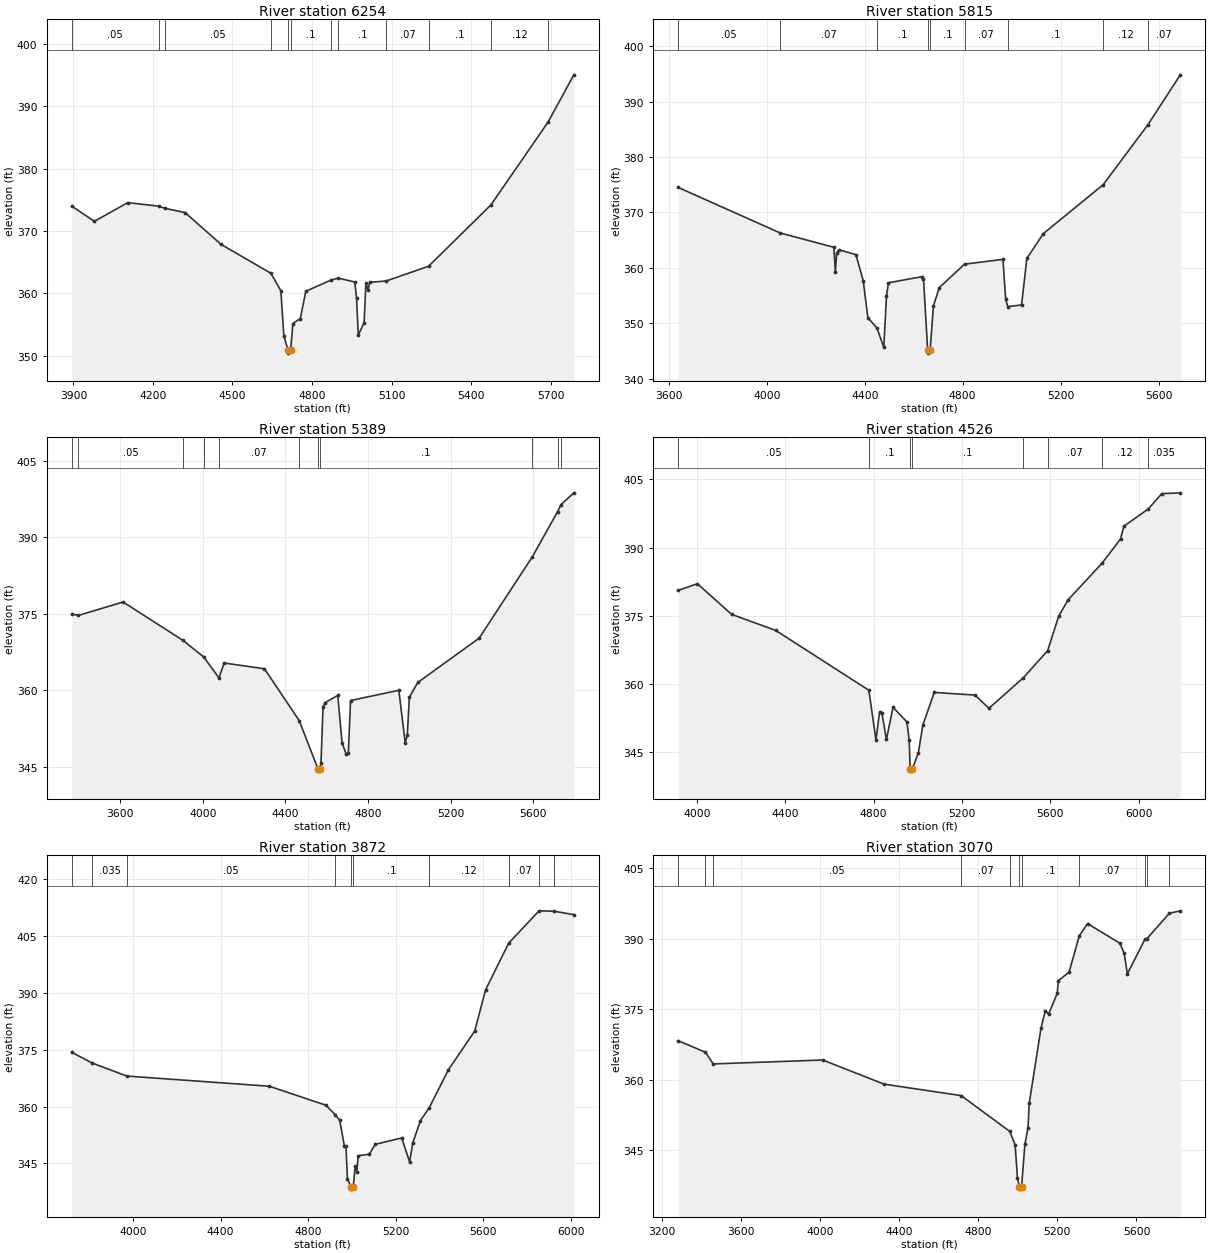
Type RM Length L Ch R = 1 ,6254    ,439,439,439
BEGIN DESCRIPTION:
XS6353
END DESCRIPTION:
XS GIS Cut Line= 3
      2385681.61     13730762.94      2386627.02     13730512.59
      2387325.13     13729919.85
#Sta/Elev= 30
  3893.8  373.97  3979.2  371.53    4105  374.53  4221.5  373.97  4245.4  373.62
  4321.4  372.93  4456.6  367.84  4644.9   363.2  4682.5   360.4  4693.8  353.12
  4709.6  350.89  4710.1  350.39  4719.5  350.89  4727.9  355.13  4755.9  355.94
  4776.6  360.31  4872.4  362.13  4899.6  362.42    4961   361.8    4968  359.25
  4974.6  353.26  4996.6   355.3  5003.1  361.62  5010.9  360.46  5017.4  361.75
  5079.7  361.96  5239.7  364.33  5474.4  374.14  5690.2  387.44  5787.6  395.03
#Mann= 12 ,-1 , 0
  3893.8     .05       0  4221.5    .035       0  4245.4     .05       0
  4644.9      .1       0  4709.6     .05       0  4719.5      .1       0
  4872.4     .12       0  4899.6      .1       0  5079.7     .07       0
  5239.7      .1       0  5474.4     .12       0  5690.2     .07       0
Bank Sta=4709.6,4719.5
XS Rating Curve= 0 ,0
Exp/Cntr=0.3,0.1

Type RM Length L Ch R = 1 ,5815    ,426,426,426
BEGIN DESCRIPTION:
XS6352
END DESCRIPTION:
XS GIS Cut Line= 3
      2385823.25     13731145.06      2386648.16     13730820.94
        2387724.     13730374.22
#Sta/Elev= 30
  3637.9  374.51  4054.8   366.3  4273.7  363.72  4279.9  359.26  4285.2  362.72
  4295.2  363.27  4363.9  362.39  4393.6  357.69  4412.7  351.03  4450.2  349.13
  4477.8  345.66  4488.6  354.91  4496.7  357.32  4632.7  358.41  4639.9  358.01
    4657  345.13  4657.5  344.63    4667  345.13  4680.4  353.13  4704.3  356.44
  4807.6  360.68  4964.6  361.54  4975.6  354.36  4984.1  353.02  5040.5  353.32
  5062.2  361.71  5129.5  366.19  5373.8     375  5557.1  385.85  5689.1  394.83
#Mann= 9 ,-1 , 0
  3637.9     .05       0  4054.8     .07       0  4450.2      .1       0
    4657     .05       0    4667      .1       0  4807.6     .07       0
  4984.1      .1       0  5373.8     .12       0  5557.1     .07       0
Bank Sta=4657,4667
XS Rating Curve= 0 ,0
Exp/Cntr=0.3,0.1

Type RM Length L Ch R = 1 ,5389    ,863,863,863
BEGIN DESCRIPTION:
XS6345
END DESCRIPTION:
XS GIS Cut Line= 3
      2385621.16     13731308.76      2387367.07     13730966.43
      2387905.13     13730599.18
#Sta/Elev= 30
  3365.7  374.95  3398.2   374.7  3614.1  377.32  3904.5  369.79  4005.4  366.52
    4078  362.45  4103.3  365.37  4298.4  364.25  4466.6  354.11  4556.9   344.7
  4557.4   344.2  4566.9   344.7  4572.1  345.72  4582.3  356.84  4592.5  357.62
  4653.5  359.03    4674  349.78  4694.4  347.48  4704.6  347.69  4715.2  358.02
  4949.1  360.03  4979.7  349.77  4989.9  351.18  5000.1  358.69  5040.8  361.56
  5337.9  370.24  5595.6  386.19  5717.2  394.98  5734.5   396.4  5796.3   398.7
#Mann= 11 ,-1 , 0
  3365.7     .07       0  3398.2     .05       0  3904.5     .07       0
  4005.4     .05       0    4078     .07       0  4466.6      .1       0
  4556.9     .05       0  4566.9      .1       0  5595.6     .07       0
  5717.2    .035       0  5734.5     .07       0
Bank Sta=4556.9,4566.9
XS Rating Curve= 0 ,0
Exp/Cntr=0.3,0.1

Type RM Length L Ch R = 1 ,4526    ,654,654,654
BEGIN DESCRIPTION:
XS6344
END DESCRIPTION:
XS GIS Cut Line= 3
      2385860.81     13731676.78      2387332.84     13731308.77
      2387949.07     13730872.27
#Sta/Elev= 30
  3916.1  380.56  4002.9  382.02  4157.5  375.28  4357.4  371.73  4778.9  358.55
    4811  347.62  4827.5  353.83  4837.8  353.58  4858.4   347.7  4888.3  354.81
  4951.2  351.56  4961.5  347.53  4965.7  341.23  4966.2  340.73  4975.8  341.23
  5002.7  344.72  5023.4  350.88  5074.9  358.07  5259.4  357.49  5322.3  354.57
  5477.6  361.27    5588  367.26  5638.6  374.93  5681.2   378.5  5834.1  386.53
  5917.9  391.87  5932.7  394.67  6043.6   398.5    6105  401.87  6188.6  402.05
#Mann= 8 ,-1 , 0
  3916.1     .05       0  4778.9      .1       0  4965.7     .05       0
  4975.8      .1       0  5477.6     .12       0    5588     .07       0
  5834.1     .12       0  6043.6    .035       0
Bank Sta=4965.7,4975.8
XS Rating Curve= 0 ,0
Exp/Cntr=0.3,0.1

Type RM Length L Ch R = 1 ,3872    ,802,802,802
BEGIN DESCRIPTION:
XS6343
END DESCRIPTION:
XS GIS Cut Line= 3
      2386023.43     13731950.65      2386981.94     13731984.89
      2387990.92     13731112.72
#Sta/Elev= 30
  3720.1  374.33  3813.5  371.49  3971.6  368.06  4622.2  365.37  4880.2  360.37
  4923.9   357.8  4943.8  356.35  4964.7  349.69  4972.3  349.47  4978.9  340.97
  4995.2  338.69  4995.7  338.19  5005.7  338.69  5014.1  344.35  5021.7  342.75
  5028.3  347.02  5078.7  347.42  5106.2  350.03  5226.9   351.7    5263  345.36
  5277.3  350.44  5312.4  356.29  5352.9  359.72  5439.6  369.67  5560.3  379.96
  5609.7  390.82  5715.1  403.15    5854  411.71  5923.1   411.6  6012.9   410.7
#Mann= 10 ,-1 , 0
  3720.1     .05       0  3813.5    .035       0  3971.6     .05       0
  4923.9      .1       0  4995.2     .05       0  5005.7      .1       0
  5352.9     .12       0  5715.1     .07       0    5854     .12       0
  5923.1    .035       0
Bank Sta=4995.2,5005.7
XS Rating Curve= 0 ,0
Exp/Cntr=0.3,0.1

Type RM Length L Ch R = 1 ,3070    ,857,857,857
BEGIN DESCRIPTION:
XS6342
END DESCRIPTION:
XS GIS Cut Line= 3
      2386134.67     13732121.82       2387649.5     13732121.82
       2388548.1     13731634.01
#Sta/Elev= 30
  3284.3  368.28    3422  365.82    3461  363.34  4014.6  364.17  4324.6  359.04
  4714.5   356.6  4959.4     349  4986.7  346.17  4998.8  339.01  5008.9  337.22
  5009.4  336.72  5019.5  337.22  5036.1  346.23  5052.2  349.82  5057.9  354.93
  5117.8     371  5139.7  374.68  5155.8  373.92  5199.6  378.33  5205.3  381.05
  5259.5  382.85  5311.1  390.58  5352.6  393.17  5516.1     389  5537.9   386.9
  5554.1  382.49  5642.3  389.82  5652.5  389.95  5766.3  395.36  5821.6  395.89
#Mann= 11 ,-1 , 0
  3284.3     .05       0    3422    .035       0    3461     .05       0
  4714.5     .07       0  4959.4      .1       0  5008.9     .05       0
  5019.5      .1       0  5311.1     .07       0  5642.3    .035       0
  5652.5     .07       0  5766.3     .05       0
Bank Sta=5008.9,5019.5
XS Rating Curve= 0 ,0
Exp/Cntr=0.3,0.1

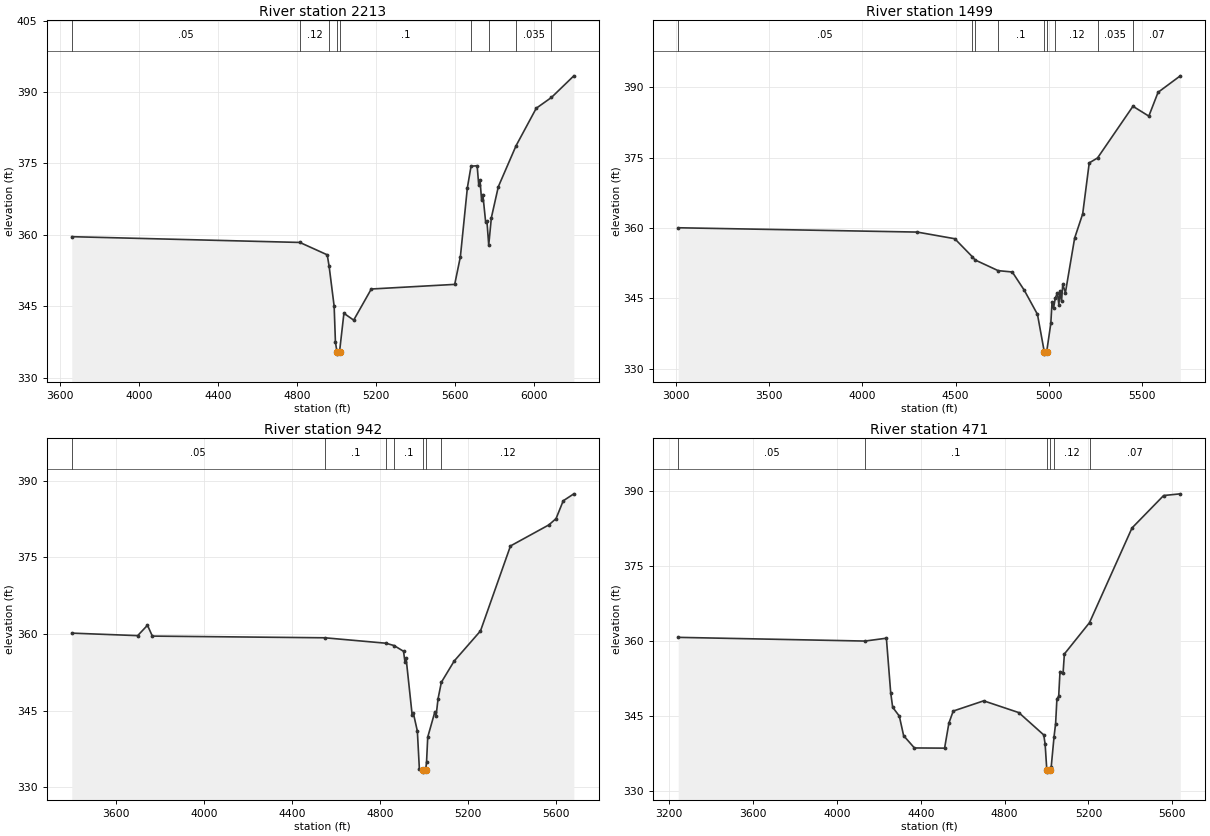
Type RM Length L Ch R = 1 ,2213    ,714,714,714
BEGIN DESCRIPTION:
E20862
END DESCRIPTION:
XS GIS Cut Line= 5
      2386740.18     13733486.27      2387587.57     13732536.17
      2387715.96     13732428.32      2388003.55     13732305.07
      2388619.84     13731812.03
#Sta/Elev= 30
  3657.5  359.62  4812.7  358.41  4951.3  355.81    4961  353.39  4986.4  345.01
  4992.9  337.45  5000.8  335.45  5001.3  334.95  5013.7  335.45  5035.9  343.53
  5085.3  342.09  5174.5  348.63    5597   349.6  5625.8  355.43  5661.1  369.89
  5679.8  374.43  5710.7  374.52  5718.7  370.44  5725.1  371.55  5733.1  367.31
  5739.5  368.48  5753.9  362.63  5760.3  362.84  5769.3  357.86  5782.7  363.62
  5817.9  370.12  5907.8  378.73    6010   386.6  6086.8  388.86  6200.4  393.41
#Mann= 9 ,-1 , 0
  3657.5     .05       0  4812.7     .12       0    4961      .1       0
  5000.8     .05       0  5013.7      .1       0  5679.8     .12       0
  5769.3      .1       0  5907.8    .035       0  6086.8     .07       0
Bank Sta=5000.8,5013.7
XS Rating Curve= 0 ,0
Exp/Cntr=0.3,0.1

Type RM Length L Ch R = 1 ,1499    ,557,557,557
BEGIN DESCRIPTION:
XS6341
END DESCRIPTION:
XS GIS Cut Line= 3
      2386682.38       13733611.      2388180.12     13732541.18
      2388719.28     13731882.22
#Sta/Elev= 30
  3013.2  360.04  4294.5  359.12  4495.9   357.7  4589.7  353.87  4604.8  353.17
  4728.4  350.89  4804.3   350.6  4868.8  346.69  4939.3  341.56  4975.8  333.57
  4976.3  333.07  4988.7  333.57  5010.9  339.62  5017.4  344.22  5025.3  342.82
  5034.8  345.01  5046.1  346.14    5054  343.64  5060.5  346.58  5068.4  344.33
  5074.8  347.94  5089.2  346.21  5138.7  357.85  5181.8  363.01  5216.9  373.89
  5261.4  374.94  5451.3  385.97  5536.4  383.87  5585.9  388.95  5705.2  392.47
#Mann= 9 ,-1 , 0
  3013.2     .05       0  4589.7     .12       0  4604.8     .05       0
  4728.4      .1       0  4975.8     .05       0  4988.7      .1       0
  5034.8     .12       0  5261.4    .035       0  5451.3     .07       0
Bank Sta=4975.8,4988.7
XS Rating Curve= 0 ,0
Exp/Cntr=0.3,0.1

Type RM Length L Ch R = 1 ,942     ,471,471,471
BEGIN DESCRIPTION:
E20861
END DESCRIPTION:
XS GIS Cut Line= 3
      2386740.24     13733614.62      2388070.31     13732936.74
      2388825.28     13732705.63
#Sta/Elev= 30
  3397.7  360.17  3697.3  359.68  3741.8  361.71    3764  359.59  4547.9  359.26
  4825.4   358.2  4862.9  357.74  4905.9  356.62  4912.4  354.51  4917.6  355.24
  4945.1  344.18  4950.4  344.55  4968.7  341.02  4977.9   333.6  4993.5   333.5
    4994     333  5006.5   333.5  5010.5  334.96  5015.9  339.85  5048.7  344.84
  5053.9  344.01  5062.8  347.34  5077.8  350.56    5136  354.71  5255.7   360.6
    5392  377.21  5566.3  381.32  5599.1  382.55  5631.9  386.04  5680.1   387.4
#Mann= 7 ,-1 , 0
  3397.7     .05       0  4547.9      .1       0  4825.4     .05       0
  4862.9      .1       0  4993.5     .05       0  5006.5      .1       0
  5077.8     .12       0
Bank Sta=4993.5,5006.5
XS Rating Curve= 0 ,0
Exp/Cntr=0.3,0.1

Type RM Length L Ch R = 1 ,471     ,0,0,0
BEGIN DESCRIPTION:
XS6340
END DESCRIPTION:
XS GIS Cut Line= 3
      2386699.51      13733670.9      2388402.64     13733260.09
      2388924.73     13732883.51
#Sta/Elev= 30
  3242.6  360.67  4133.7  359.93  4235.8   360.5  4256.3  349.65  4265.7  346.72
  4297.5  344.94  4318.1  341.03  4369.5  338.58  4513.5  338.54  4534.1  343.54
  4554.7  345.95  4700.1  347.99  4867.7  345.64  4986.7  341.18  4993.2  339.37
  5001.2  334.25  5001.7  333.75  5014.2  334.25  5022.1  334.72  5035.9  340.85
  5043.3  343.46  5049.5  348.37    5058  348.91  5064.2  353.84  5078.9  353.52
  5085.1  357.35    5205  363.61  5407.8  382.52  5558.7     389  5638.3  389.34
#Mann= 6 ,-1 , 0
  3242.6     .05       0  4133.7      .1       0  5001.2     .05       0
  5014.2      .1       0  5035.9     .12       0    5205     .07       0
Bank Sta=5001.2,5014.2
XS Rating Curve= 0 ,0
Exp/Cntr=0.3,0.1

Chan Stop Cuts=-1
Use User Specified Reach Order=0
Composite Channel Slope=5