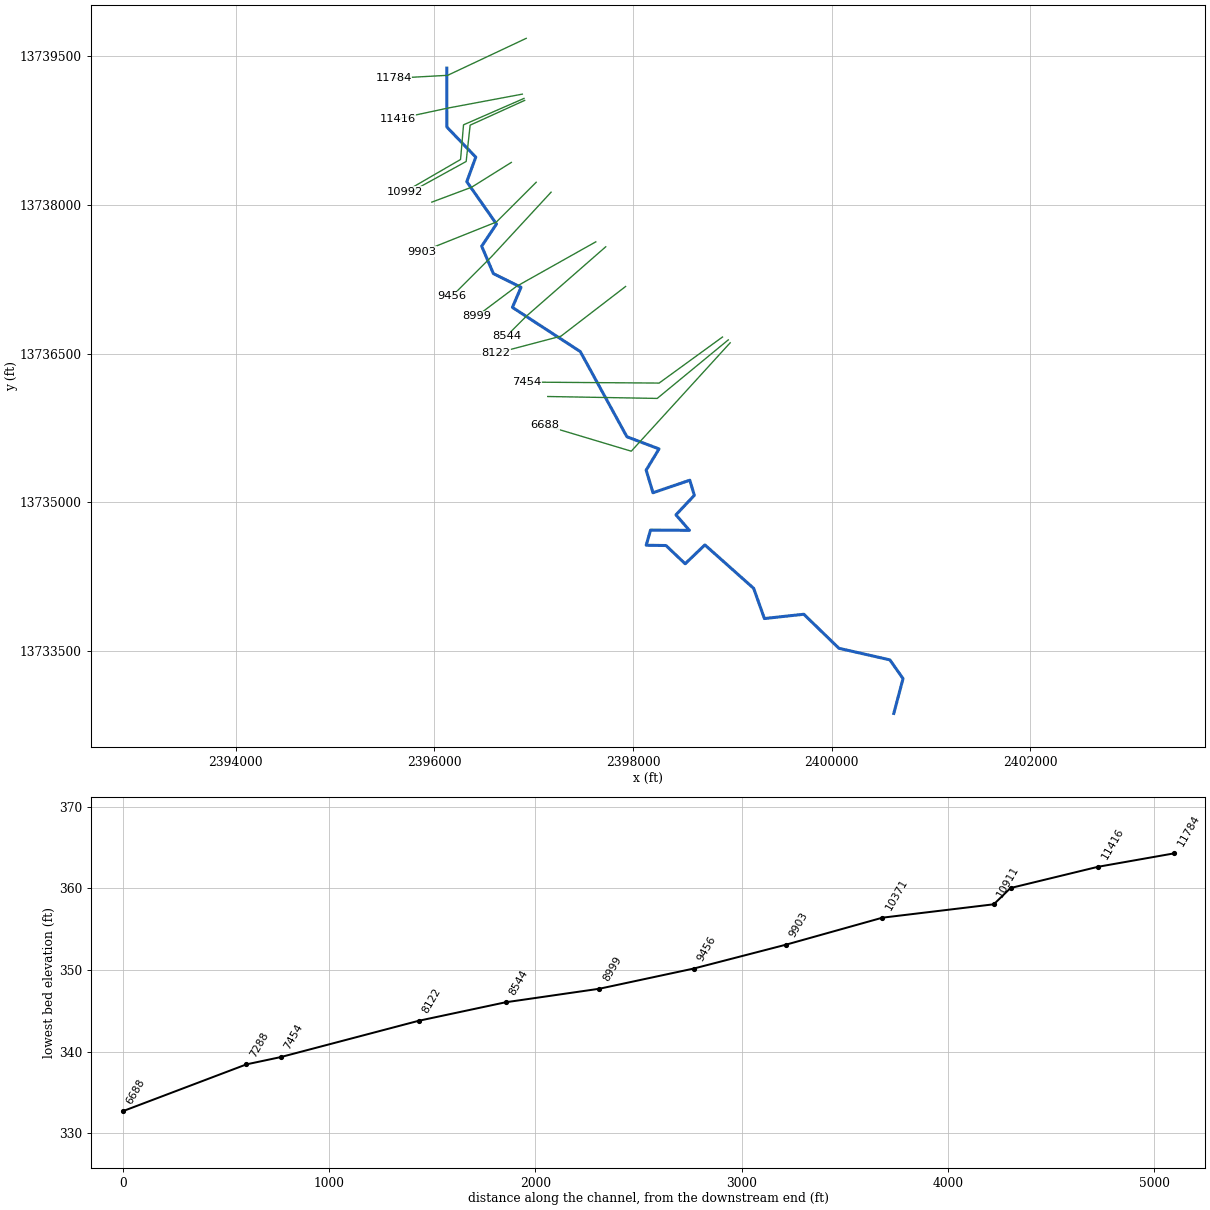
--- Stream0286.prj (project) ---

Proj Title=Stream0286 Base Level Engineering
Current Plan=p01
Default Exp/Contr=0.3,0.1
English Units
Geom File=g01
Flow File=f01
Plan File=p01
Y Axis Title=Elevation
X Axis Title(PF)=Main Channel Distance
X Axis Title(XS)=Station
BEGIN DESCRIPTION:
Stream0286
END DESCRIPTION:
DSS Export Rating Curves= 0
DSS Export Rating Curve Sorted= 0
DSS Export Volume Flow Curves= 0
DXF OffsetX= 0
DXF OffsetY= 0
DXF ScaleX= 1
DXF ScaleY= 10

--- Stream0286.p01 (plan) ---

Plan Title=Multiple Run
Program Version=4.10
Short Identifier=Multiple
Geom File=g01
Flow File=f01
Subcritical Flow
K Sum by GR= 0
Std Step Tol= 0.01
Critical Tol= 0.01
Num of Std Step Trials= 20
Max Error Tol= 0.3
Flow Tol Ratio= 0.001
Split Flow NTrial= 30
Split Flow Tol= 0.02
Split Flow Ratio= 0.02
Log Output Level= 0
Friction Slope Method= 1
Unsteady Friction Slope Method= 2
Unsteady Bridges Friction Slope Method= 1
Parabolic Critical Depth
Global Vel Dist= 1 , 1 , 1
Global Log Level= 0
CheckData=True
Encroach Param=-1 ,0,0, 0
BEGIN DESCRIPTION:
Multiple Run
END DESCRIPTION:
Computation Interval=1HOUR
Output Interval=1HOUR
Run HTab= 0
Run UNet= 0
Run PostProcess= 0
Run WQNet= 0
UNET Theta= 1
UNET Theta Warmup= 1
UNET ZTol= 0.02
UNET ZSATol= 0.05
UNET MxIter= 20
UNET MaxInSteps= 0
UNET DtIC= 0
UNET DtMin= 0
UNET MaxCRTS= 20
UNET WFStab= 2
UNET SFStab= 1
UNET WFX= 1
UNET SFX= 1
UNET DSS MLevel= 4
UNET DZMax Abort= 100
UNET Convert EG Bridges= 0
UNET Use Existing IB Tables=-1
UNET Froude Reduction=False
UNET Froude Limit= 1
UNET Froude Power= 10
UNET Time Slicing=0,0, 5
UNET Junction Losses=0
Instantaneous Interval=1HOUR
Write IC File= 0
Write IC File at Sim End=0
Echo Input=False
Echo Parameters=False
Echo Output=False
Write Detailed= 0
WQ AD Non Conservative
WQ ULTIMATE=-1
WQ Max Comp Step=1HOUR
WQ Output Interval=15MIN
WQ Output Selected Increments= 0
WQ Output face flow=0
WQ Output face velocity=0
WQ Output face area=0
WQ Output face dispersion=0
WQ Output cell volume=0
WQ Output cell surface area=0
WQ Output cell continuity=0
WQ Output cumulative cell continuity=0
WQ Output face conc=0
WQ Output face dconc_dx=0
WQ Output face courant=0
WQ Output face peclet=0
WQ Output face adv mass=0
WQ Output face disp mass=0
WQ Output cell mass=0
WQ Output cell source sink temp=0
WQ Output cell source sink nsm=0
WQ Output MaxMinRange=-1
WQ Daily Max Min Mean=-1
WQ Daily Range=0
WQ Daily Time=0
WQ Create Restart=0
WQ Fixed Restart=0
WQ System Summary=0
WQ Use Fixed Temperature=0
Sorting and Armoring Iterations= 10
XS Update Threshold= 0.02
Hydraulics Update Threshold= 0.02
Energy Slope Method= 1
Volume Change Method= 0
XS Weighting Method= 0
Number of US Weighted Cross Sections= 1
Number of DS Weighted Cross Sections= 1
Upstream XS Weight=0.25
Main XS Weight=0.5
Downstream XS Weight=0.25
Number of DS XS's Weighted with US Boundary= 1
Upstream Boundary Weight= 1
Weight of XSs Associated with US Boundary= 0
Number of US XS's Weighted with DS Boundary= 1
Downstream Boundary Weight= 0.5
Weight of XSs Associated with DS Boundary= 0.5
Sediment Output Level= 4
Mass or Volume Output= 0
Output Increment Type= 1
Profile and TS Output Increment= 10
XS Output Flag= 0
XS Output Increment= 10
Disregard all LS=0
Disregard all Conn=0
Disregard all Breaches=0
Disregard all Pumps=0

--- Stream0286.f01 (steady flow) ---

Flow Title=Multiple
Number of Profiles=7
Profile Names=10-year,25-year,50-year,1pct_min,100-year,1pct_plu,500-year
River Rch & RM= Stream0286,Reach-1,11784
     870    1428    1940    1276    2546    5080    4342
River Rch & RM= Stream0286,Reach-1,7454
    1011    1671    2281    1506    3004    5994    5164
Boundary for River Rch & Prof#=Stream0286,Reach-1,1
Up Type=0
Dn Type=3
Dn Slope=0.005
Boundary for River Rch & Prof#=Stream0286,Reach-1,2
Up Type=0
Dn Type=3
Dn Slope=0.005
Boundary for River Rch & Prof#=Stream0286,Reach-1,3
Up Type=0
Dn Type=3
Dn Slope=0.005
Boundary for River Rch & Prof#=Stream0286,Reach-1,4
Up Type=0
Dn Type=3
Dn Slope=0.005
Boundary for River Rch & Prof#=Stream0286,Reach-1,5
Up Type=0
Dn Type=3
Dn Slope=0.005
Boundary for River Rch & Prof#=Stream0286,Reach-1,6
Up Type=0
Dn Type=3
Dn Slope=0.005
Boundary for River Rch & Prof#=Stream0286,Reach-1,7
Up Type=0
Dn Type=3
Dn Slope=0.005

--- Stream0286.g01 (geometry) ---

Geom Title=Existing Conditions
Program Version=4.10

River Reach=Stream0286      ,Reach-1
Reach XY= 30
        2396125.       13739375.      2396126.55     13738780.85
      2396417.15     13738478.23      2396326.65     13738231.04
      2396625.37      13737804.8      2396476.59     13737581.05
      2396594.61     13737304.84      2396872.53      13737166.9
      2396785.95     13736964.63      2397469.41     13736519.39
      2397938.47     13735661.43      2398261.63     13735538.87
      2398132.33      13735325.1      2398200.98     13735097.63
      2398571.48     13735223.78      2398617.21     13735071.58
      2398431.98     13734874.79      2398567.68     13734718.64
      2398176.25     13734721.64      2398132.62     13734568.49
      2398331.74     13734565.87      2398525.01     13734382.07
      2398723.32     13734571.91      2399214.24     13734134.68
      2399322.52     13733830.46      2399719.15     13733873.46
      2400072.46      13733530.7      2400585.37     13733414.02
      2400717.89       13733225.        2400625.       13732875.

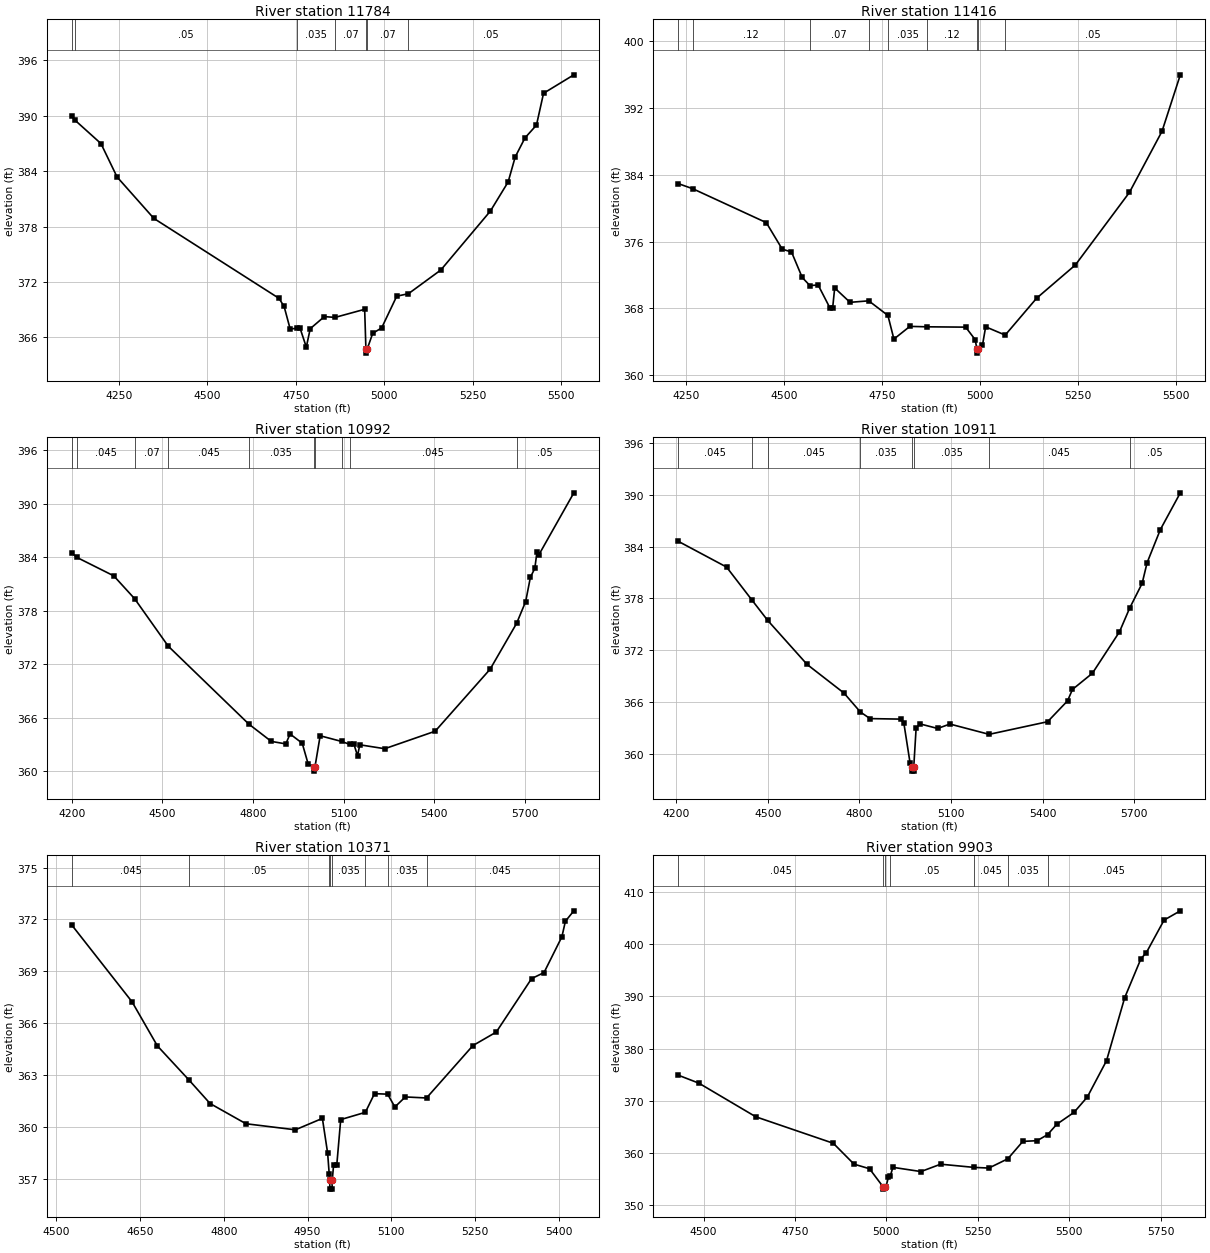
Type RM Length L Ch R = 1 ,11784   ,368,368,368
BEGIN DESCRIPTION:
Stream0286 14.0
END DESCRIPTION:
XS GIS Cut Line= 3
      2396924.99     13739674.99      2396134.27     13739302.48
      2395589.46     13739272.58
#Sta/Elev= 30
  4116.7  389.98    4125  389.55  4199.2  386.99  4244.8  383.37  4348.8  378.88
  4702.6  370.22  4717.1  369.34  4734.3  366.89  4753.7  366.98  4761.9  367.02
  4779.9  364.93    4791  366.93    4831  368.24  4861.1  368.15  4944.9  369.03
  4948.4  364.78  4948.7  364.28  4952.6  364.78  4967.7  366.43  4992.9  367.01
  5035.6  370.45  5068.7  370.72  5160.3  373.29  5300.5  379.68  5350.6  382.83
  5370.6  385.54  5398.3  387.61  5430.7  388.99  5450.7  392.44  5536.4  394.44
#Mann= 7 ,-1 , 0
  4116.7     .07       0    4125     .05       0  4753.7    .035       0
  4861.1     .07       0  4948.4     .05       0  4952.6     .07       0
  5068.7     .05       0
Bank Sta=4948.4,4952.6
XS Rating Curve= 0 ,0
Exp/Cntr=0.3,0.1

Type RM Length L Ch R = 1 ,11416   ,424,424,424
BEGIN DESCRIPTION:
Stream0286 13.0
END DESCRIPTION:
XS GIS Cut Line= 3
      2396885.86     13739112.92      2396140.92     13738973.24
      2395629.35     13738863.62
#Sta/Elev= 30
  4230.3  382.93  4267.2  382.32    4455  378.26  4495.7  375.08  4519.3  374.75
  4546.6   371.7  4566.1  370.73  4587.3  370.79  4617.8  368.01  4624.4  368.09
  4629.5  370.44  4668.7  368.72  4716.4   368.9  4765.3  367.15  4780.6  364.32
  4821.3  365.84    4865  365.79  4963.7  365.75  4988.2  364.24  4992.2  363.14
  4992.5  362.64  4996.4  363.14  5006.6  363.59  5014.7  365.79  5064.6   364.8
  5144.7  369.21  5243.6  373.19  5381.6  381.88  5464.7  389.19  5511.4  395.95
#Mann= 9 ,-1 , 0
  4230.3     .05       0  4267.2     .12       0  4566.1     .07       0
  4716.4    .045       0  4765.3    .035       0    4865     .12       0
  4992.2     .05       0  4996.4     .12       0  5064.6     .05       0
Bank Sta=4992.2,4996.4
XS Rating Curve= 0 ,0
Exp/Cntr=0.3,0.1

Type RM Length L Ch R = 1 ,10992   ,81,81,81
BEGIN DESCRIPTION:
XS6366
END DESCRIPTION:
XS GIS Cut Line= 4
      2396902.47     13739069.67       2396293.9     13738803.63
      2396263.97     13738454.44      2395703.18     13738129.25
#Sta/Elev= 30
  4199.7  384.48  4216.5  383.98  4338.8  381.91  4407.9  379.35  4519.1  374.04
  4786.1  365.31  4860.5  363.37  4908.6  363.09  4922.7   364.2  4962.9  363.17
  4982.9  360.81  5000.8  360.54  5001.1  360.04  5005.3  360.54  5022.4     364
  5093.9  363.36  5120.1  363.04  5133.5  363.13  5146.2  361.76  5153.6  362.99
  5236.3  362.55  5403.3  364.51  5585.4  371.46    5673  376.59    5703  379.03
  5718.8  381.77  5733.3  382.74  5740.3  384.54  5746.1  384.23  5862.6  391.21
#Mann= 10 ,-1 , 0
  4199.7     .05       0  4216.5    .045       0  4407.9     .07       0
  4519.1    .045       0  4786.1    .035       0  5000.8    .035       0
  5005.3    .035       0  5093.9     .05       0  5120.1    .045       0
    5673     .05       0
Bank Sta=5000.8,5005.3
XS Rating Curve= 0 ,0
Exp/Cntr=0.3,0.1

Type RM Length L Ch R = 1 ,10911   ,540,540,540
BEGIN DESCRIPTION:
Stream0286 12.0
END DESCRIPTION:
XS GIS Cut Line= 4
      2396909.13     13739049.72      2396360.42     13738800.31
      2396320.51     13738434.49      2395730.54     13738109.68
#Sta/Elev= 30
  4206.6  384.61  4364.9  381.63  4447.3  377.85  4499.5  375.47  4628.6  370.38
  4749.4  367.07  4803.1  364.88  4834.8  364.12  4935.4  364.06  4945.5  363.59
  4965.6  359.04  4973.4  358.55  4973.7  358.05  4977.6  358.05  4977.9  358.55
  4985.7  363.05  4999.2   363.5  5056.1  362.98  5096.3  363.49  5224.7   362.3
  5416.2  363.76  5481.5  366.17  5497.6  367.49  5562.9  369.36  5651.6  374.15
  5684.7  376.87  5725.8  379.75  5741.9  382.12  5785.4  385.96  5850.8  390.21
#Mann= 8 ,-1 , 0
  4206.6    .045       0  4447.3     .07       0  4499.5    .045       0
  4803.1    .035       0  4973.4    .035       0  4977.9    .035       0
  5224.7    .045       0  5684.7     .05       0
Bank Sta=4973.4,4977.9
XS Rating Curve= 0 ,0
Exp/Cntr=0.3,0.1

Type RM Length L Ch R = 1 ,10371   ,468,468,468
BEGIN DESCRIPTION:
Stream0286 11.0
END DESCRIPTION:
XS GIS Cut Line= 3
      2396774.99     13738424.99        2396375.       13738175.
      2395974.98     13738024.99
#Sta/Elev= 30
  4527.8  371.68  4635.7  367.24  4681.1  364.69  4737.9  362.71  4775.4  361.36
  4839.7  360.19  4928.1  359.84  4976.5   360.5  4985.9  358.49  4988.7  357.29
  4989.6  356.91  4989.9  356.41  4993.8  356.41  4994.1  356.91  4996.5  357.78
  5002.2  357.78  5009.3  360.43  5053.4  360.85  5069.8  361.93  5093.3   361.9
  5106.3  361.16    5125  361.74  5162.9  361.68    5246  364.71  5287.8  365.49
    5351  368.58  5373.3  368.93  5405.3     371  5411.6   371.9  5426.7   372.5
#Mann= 8 ,-1 , 0
  4527.8    .045       0  4737.9     .05       0  4988.7    .035       0
  4989.6    .035       0  4994.1    .035       0  5053.4    .045       0
  5093.3    .035       0  5162.9    .045       0
Bank Sta=4989.6,4994.1
XS Rating Curve= 0 ,0
Exp/Cntr=0.3,0.1

Type RM Length L Ch R = 1 ,9903    ,447,447,447
BEGIN DESCRIPTION:
Stream0286 10.0
END DESCRIPTION:
XS GIS Cut Line= 3
      2397024.97     13738224.97        2396625.       13737825.
      2395875.02     13737525.01
#Sta/Elev= 30
  4430.6   374.9  4487.1  373.37  4642.7  366.94  4854.8  361.87  4911.4  357.88
  4953.8     357  4990.4   353.6  4990.8   353.1    4995   353.6  4998.9   353.6
  5005.7  355.41  5010.7  355.63  5017.8  357.27  5094.5  356.46  5148.4  357.87
  5239.4  357.26  5280.3  357.13  5332.1   358.9  5373.2  362.23  5412.3  362.37
  5440.9  363.52  5466.1  365.51  5513.2  367.78  5549.6  370.72  5602.1  377.66
  5651.9  389.73  5696.3  397.18  5711.1  398.34  5759.6  404.57    5804  406.34
#Mann= 7 ,-1 , 0
  4430.6    .045       0  4990.4    .045       0    4995    .045       0
  5010.7     .05       0  5239.4    .045       0  5332.1    .035       0
  5440.9    .045       0
Bank Sta=4990.4,4995
XS Rating Curve= 0 ,0
Exp/Cntr=0.3,0.1

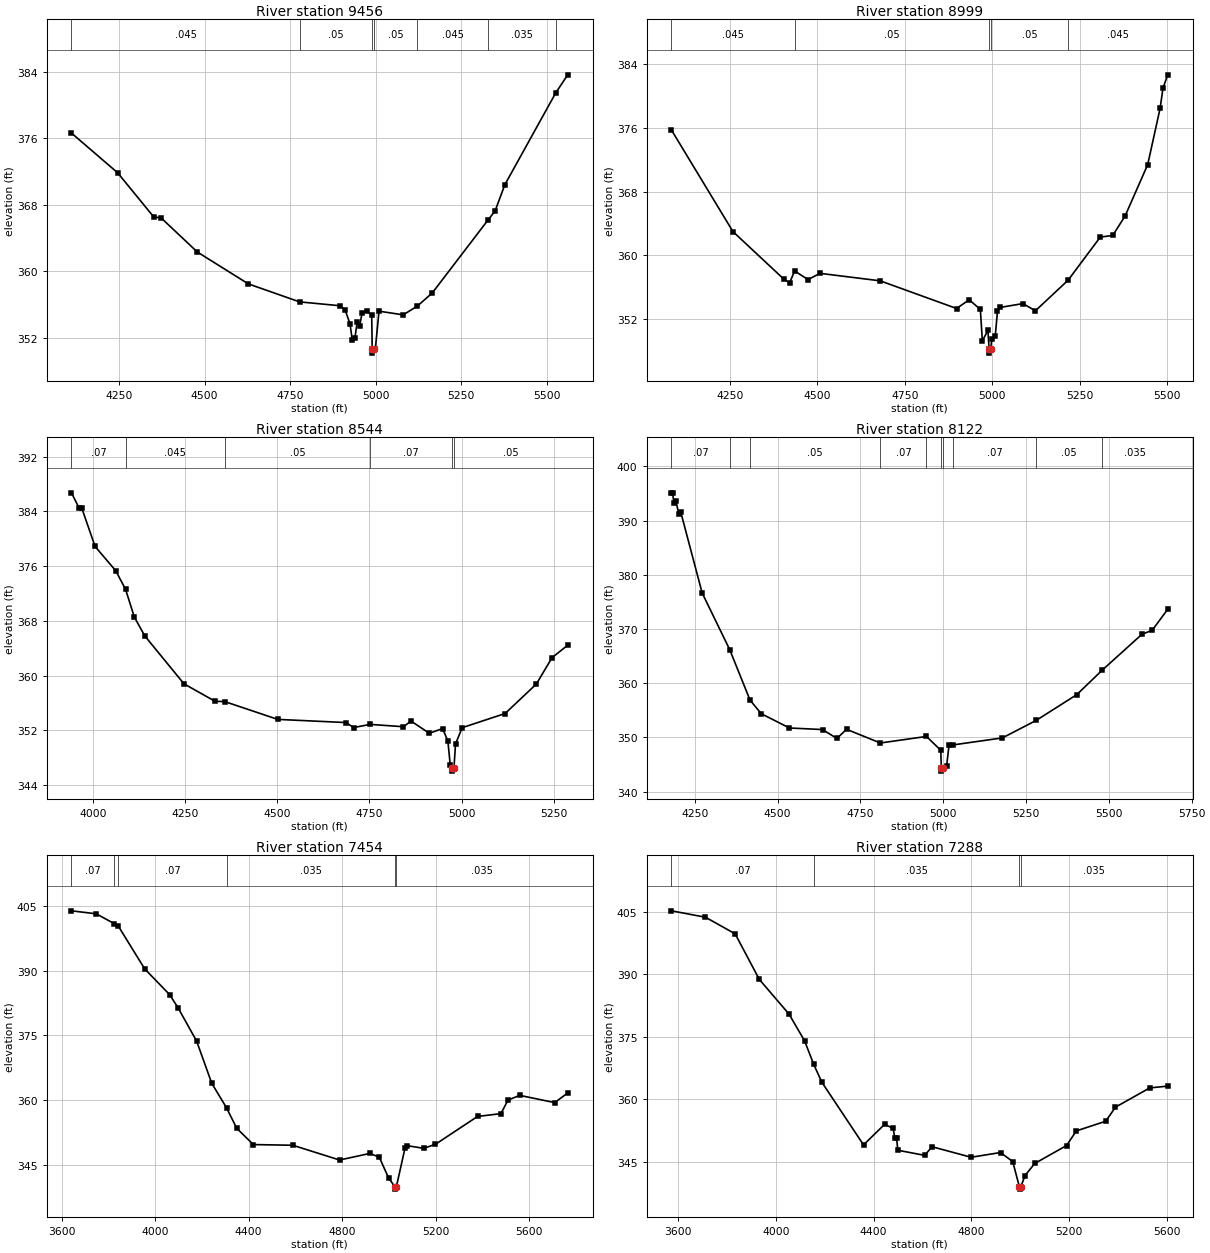
Type RM Length L Ch R = 1 ,9456    ,457,457,457
BEGIN DESCRIPTION:
Stream0286 9.0
END DESCRIPTION:
XS GIS Cut Line= 3
      2397175.02     13738125.02        2396575.       13737475.
        2396175.       13737075.
#Sta/Elev= 30
  4111.1  376.62  4245.8  371.86  4351.8  366.53  4372.8  366.44  4478.9  362.33
    4628   358.5  4777.6  356.34  4896.8  355.87  4910.9  355.36  4925.1  353.71
  4931.9  351.75  4939.3  351.95  4946.1  353.88  4953.5  353.48  4960.3  354.97
  4974.4  355.21  4988.6  354.75    4990  350.68  4990.3  350.18  4994.6  350.68
  4999.2  350.68  5009.9  355.22  5080.6  354.78  5121.9  355.83  5165.4   357.4
  5327.7  366.13  5349.3  367.27  5377.6  370.41  5525.9  381.41  5561.4  383.62
#Mann= 7 ,-1 , 0
  4111.1    .045       0  4777.6     .05       0    4990     .05       0
  4994.6     .05       0  5121.9    .045       0  5327.7    .035       0
  5525.9    .045       0
Bank Sta=4990,4994.6
XS Rating Curve= 0 ,0
Exp/Cntr=0.3,0.1

Type RM Length L Ch R = 1 ,8999    ,455,455,455
BEGIN DESCRIPTION:
Stream0286 8.0
END DESCRIPTION:
XS GIS Cut Line= 3
      2397624.97     13737624.99        2396825.       13737175.
      2396425.04     13736875.03
#Sta/Elev= 30
  4083.2  375.75  4258.8  362.99  4404.7  356.99  4420.7  356.55    4435  358.04
  4473.3  356.96  4507.7  357.74  4679.5   356.8  4897.8  353.32  4933.8  354.42
  4965.7   353.2  4971.4  349.25  4987.3  350.58  4990.7  348.21    4991  347.71
  4995.5  348.21  4998.2  349.48  5008.3   349.9  5014.6  352.97  5022.9  353.46
  5087.5  353.94  5122.9  353.03  5216.4  356.88  5308.3   362.3  5343.8   362.5
  5379.2  364.95  5443.8  371.41  5479.2  378.48  5487.5  381.02    5501   382.7
#Mann= 5 ,-1 , 0
  4083.2    .045       0    4435     .05       0  4990.7     .05       0
  4995.5     .05       0  5216.4    .045       0
Bank Sta=4990.7,4995.5
XS Rating Curve= 0 ,0
Exp/Cntr=0.3,0.1

Type RM Length L Ch R = 1 ,8544    ,422,422,422
BEGIN DESCRIPTION:
Stream0286 7.0
END DESCRIPTION:
XS GIS Cut Line= 3
      2397724.98     13737574.98        2396925.       13736875.
      2396725.02     13736675.02
#Sta/Elev= 30
  3942.2  386.72  3963.5  384.43  3970.2  384.48  4006.2  378.88  4062.2  375.34
  4088.9  372.62  4112.5  368.58    4141  365.81  4247.3  358.81  4331.8  356.25
  4357.4  356.22  4501.7  353.61  4686.3  353.15  4707.6  352.42  4752.2  352.88
  4842.4  352.54  4863.3  353.36  4912.7  351.58  4948.7  352.27    4963  350.46
  4969.6  346.88  4974.8  346.55  4975.1  346.05  4979.6  346.55  4983.8  350.03
  5001.9   352.4  5118.3  354.47  5203.2  358.79  5245.6  362.64    5288  364.45
#Mann= 6 ,-1 , 0
  3942.2     .07       0  4088.9    .045       0  4357.4     .05       0
  4752.2     .07       0  4974.8     .05       0  4979.6     .05       0
Bank Sta=4974.8,4979.6
XS Rating Curve= 0 ,0
Exp/Cntr=0.3,0.1

Type RM Length L Ch R = 1 ,8122    ,668,668,668
BEGIN DESCRIPTION:
Stream0286 6.0
END DESCRIPTION:
XS GIS Cut Line= 3
      2397925.04     13737175.03        2397275.       13736675.
      2396619.75     13736502.05
#Sta/Elev= 30
  4179.9  395.13  4183.1  395.13  4187.2  393.25  4193.5  393.61  4201.7  391.21
    4208  391.54  4272.4  376.66  4355.8  366.17  4416.9  356.89  4450.9  354.37
    4536  351.74  4635.7  351.45  4679.2  349.81  4708.3   351.5  4810.3  348.97
  4949.5  350.18  4992.8  347.62  4994.4  344.28  4994.8  343.78  4999.3  344.28
  5010.4  344.76  5017.6  348.56  5030.2  348.62  5178.7  349.91  5280.5  353.13
  5403.4   357.9  5479.3  362.37  5599.9  369.03  5630.9  369.77  5677.7  373.64
#Mann= 10 ,-1 , 0
  4179.9     .07       0  4355.8    .045       0  4416.9     .05       0
  4810.3     .07       0  4949.5     .05       0  4994.4     .05       0
  4999.3     .05       0  5030.2     .07       0  5280.5     .05       0
  5479.3    .035       0
Bank Sta=4994.4,4999.3
XS Rating Curve= 0 ,0
Exp/Cntr=0.3,0.1

Type RM Length L Ch R = 1 ,7454    ,166,166,166
BEGIN DESCRIPTION:
Stream0286 5.0
END DESCRIPTION:
XS GIS Cut Line= 3
      2398900.62      13736666.3      2398262.65     13736202.33
      2396929.43     13736211.99
#Sta/Elev= 30
  3642.6  403.86  3748.5  403.17  3825.2   400.9  3842.5  400.35  3955.9  390.39
  4062.6  384.42  4098.1   381.4  4177.7  373.67  4242.6  363.87  4305.8  358.18
  4349.3  353.45  4420.4  349.67  4589.1  349.51  4789.1  346.09  4919.1  347.62
  4959.1  346.72  4999.1  341.89  5026.5  339.84  5026.9  339.34  5031.8  339.84
  5069.1  348.88  5079.1  349.41  5149.1   348.8  5199.1  349.73  5379.1  356.19
  5479.1  356.84  5509.1  359.96  5559.1  361.08  5709.1   359.4  5764.7  361.63
#Mann= 6 ,-1 , 0
  3642.6     .07       0  3825.2     .12       0  3842.5     .07       0
  4305.8    .035       0  5026.5    .035       0  5031.8    .035       0
Bank Sta=5026.5,5031.8
XS Rating Curve= 0 ,0
Exp/Cntr=0.3,0.1

Type RM Length L Ch R = 1 ,7288    ,600,600,600
BEGIN DESCRIPTION:
Stream0286 4.0
END DESCRIPTION:
XS GIS Cut Line= 3
      2398958.57     13736637.27      2398243.32     13736047.67
      2397141.42       13736067.
#Sta/Elev= 30
  3573.5  405.27  3712.5  403.73  3833.7  399.75  3932.7  388.79  4053.9  380.49
  4117.7  374.05  4154.8  368.44    4188  364.14  4358.7  349.07  4444.8     354
  4479.9  353.04  4486.4  350.71  4494.3  350.63  4498.6  347.79  4608.8  346.56
  4638.8  348.63  4798.8   346.1  4918.8  347.24  4968.8  345.06  4996.2  338.95
  4996.6  338.45  5001.5  338.95  5018.8  341.69  5058.8  344.61  5188.9  348.92
  5228.9  352.43  5348.9  354.75  5388.9  358.13  5528.9  362.75  5602.5  363.18
#Mann= 4 ,-1 , 0
  3573.5     .07       0  4154.8    .035       0  4996.2    .035       0
  5001.5    .035       0
Bank Sta=4996.2,5001.5
XS Rating Curve= 0 ,0
Exp/Cntr=0.3,0.1

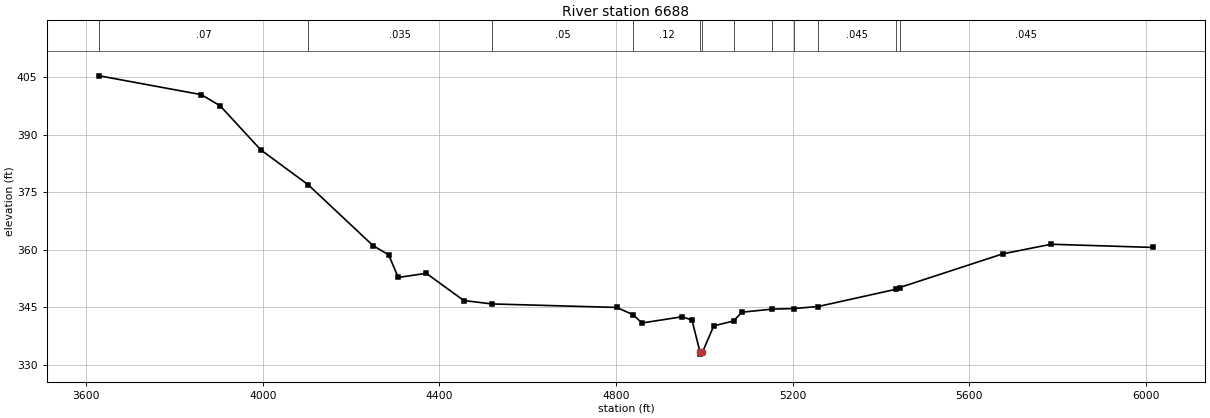
Type RM Length L Ch R = 1 ,6688    ,0,0,0
BEGIN DESCRIPTION:
Stream0286 3.0
END DESCRIPTION:
XS GIS Cut Line= 3
      2398977.91     13736608.28      2397982.34     13735516.05
      2397112.43     13735777.03
#Sta/Elev= 30
  3629.7   405.4  3860.8  400.48  3903.3  397.57  3995.2  386.08  4102.9  376.94
  4249.9  361.02  4285.1  358.66  4306.7  352.73  4370.2  353.82  4455.3  346.71
  4518.9  345.82  4801.9   344.9  4839.3  342.97  4858.7  340.84  4950.6  342.48
  4972.2  341.56  4990.4  333.21  4990.9  332.71  4995.8  333.21  5021.5  340.09
  5066.2  341.37    5085  343.66  5154.3  344.47  5202.2  344.61    5258  345.15
  5433.3  349.63  5442.2  350.09    5676   358.9  5785.6  361.41  6015.8  360.58
#Mann= 12 ,-1 , 0
  3629.7     .07       0  4102.9    .035       0  4518.9     .05       0
  4839.3     .12       0  4990.4     .05       0  4995.8     .12       0
  5066.2    .035       0  5154.3    .045       0  5202.2    .035       0
    5258    .045       0  5433.3    .035       0  5442.2    .045       0
Bank Sta=4990.4,4995.8
XS Rating Curve= 0 ,0
Exp/Cntr=0.3,0.1

Chan Stop Cuts=-1
Use User Specified Reach Order=0
Composite Channel Slope=5