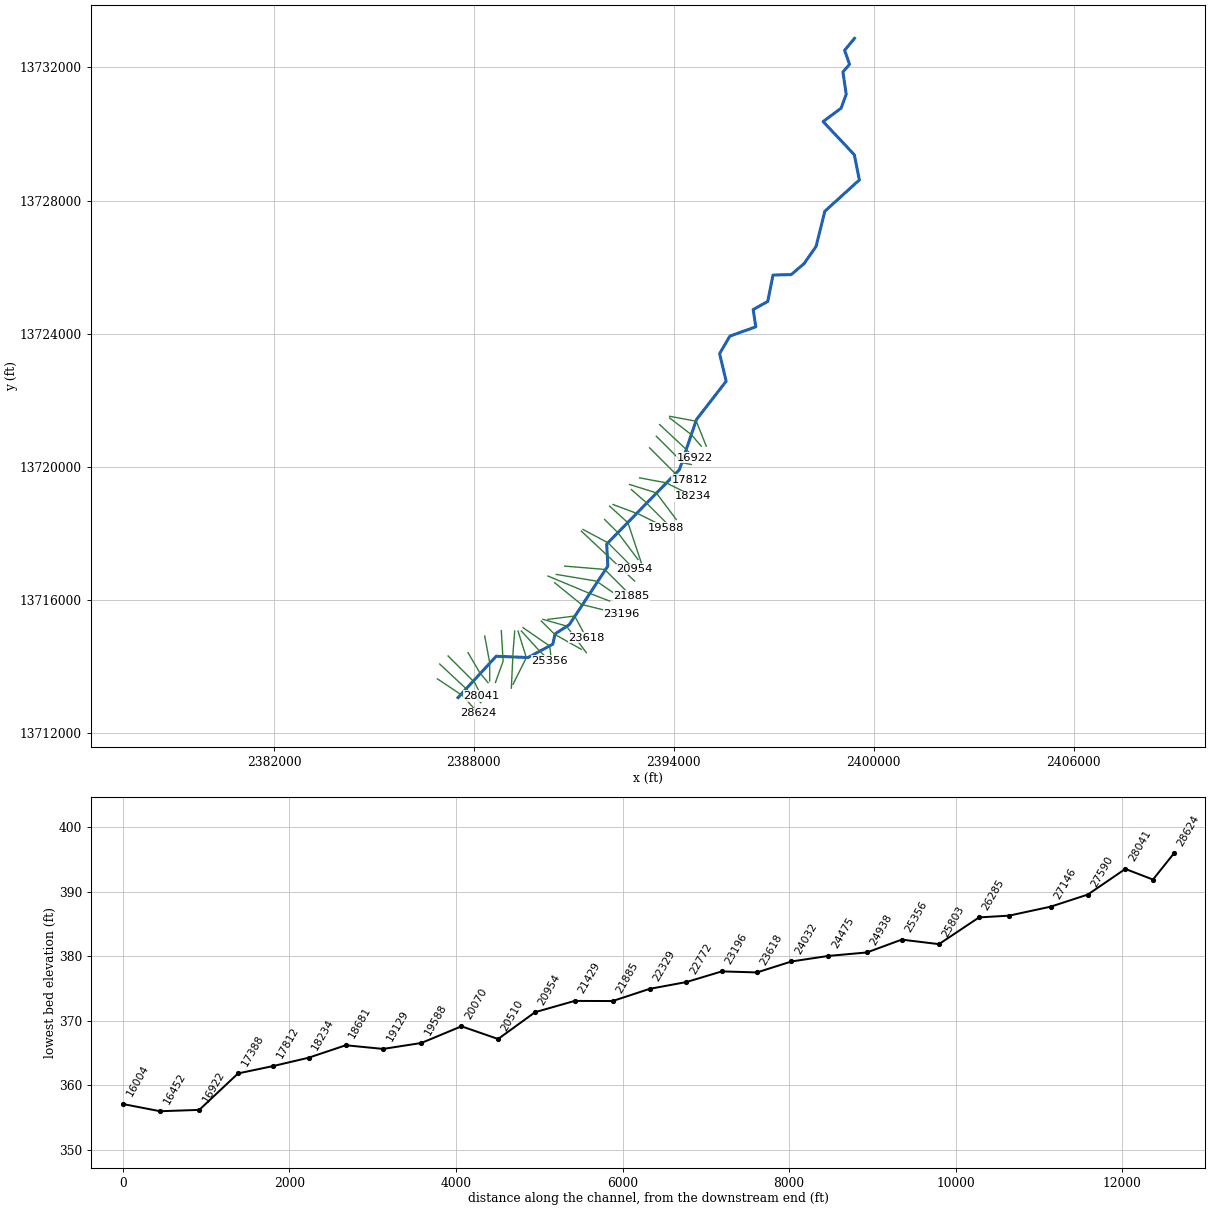
--- Stream0291.prj (project) ---

Proj Title=Stream0291 Base Level Engineering
Current Plan=p01
Default Exp/Contr=0.3,0.1
English Units
Geom File=g01
Flow File=f01
Plan File=p01
Y Axis Title=Elevation
X Axis Title(PF)=Main Channel Distance
X Axis Title(XS)=Station
BEGIN DESCRIPTION:
Stream0291
END DESCRIPTION:
DSS Export Rating Curves= 0
DSS Export Rating Curve Sorted= 0
DSS Export Volume Flow Curves= 0
DXF OffsetX= 0
DXF OffsetY= 0
DXF ScaleX= 1
DXF ScaleY= 10

--- Stream0291.p01 (plan) ---

Plan Title=Multiple Run
Program Version=4.10
Short Identifier=Multiple
Geom File=g01
Flow File=f01
Subcritical Flow
K Sum by GR= 0
Std Step Tol= 0.01
Critical Tol= 0.01
Num of Std Step Trials= 20
Max Error Tol= 0.3
Flow Tol Ratio= 0.001
Split Flow NTrial= 30
Split Flow Tol= 0.02
Split Flow Ratio= 0.02
Log Output Level= 0
Friction Slope Method= 1
Unsteady Friction Slope Method= 2
Unsteady Bridges Friction Slope Method= 1
Parabolic Critical Depth
Global Vel Dist= 1 , 1 , 1
Global Log Level= 0
CheckData=True
Encroach Param=-1 ,0,0, 0
BEGIN DESCRIPTION:
Multiple Run
END DESCRIPTION:
Computation Interval=1HOUR
Output Interval=1HOUR
Run HTab= 0
Run UNet= 0
Run PostProcess= 0
Run WQNet= 0
UNET Theta= 1
UNET Theta Warmup= 1
UNET ZTol= 0.02
UNET ZSATol= 0.05
UNET MxIter= 20
UNET MaxInSteps= 0
UNET DtIC= 0
UNET DtMin= 0
UNET MaxCRTS= 20
UNET WFStab= 2
UNET SFStab= 1
UNET WFX= 1
UNET SFX= 1
UNET DSS MLevel= 4
UNET DZMax Abort= 100
UNET Convert EG Bridges= 0
UNET Use Existing IB Tables=-1
UNET Froude Reduction=False
UNET Froude Limit= 1
UNET Froude Power= 10
UNET Time Slicing=0,0, 5
UNET Junction Losses=0
Instantaneous Interval=1HOUR
Write IC File= 0
Write IC File at Sim End=0
Echo Input=False
Echo Parameters=False
Echo Output=False
Write Detailed= 0
WQ AD Non Conservative
WQ ULTIMATE=-1
WQ Max Comp Step=1HOUR
WQ Output Interval=15MIN
WQ Output Selected Increments= 0
WQ Output face flow=0
WQ Output face velocity=0
WQ Output face area=0
WQ Output face dispersion=0
WQ Output cell volume=0
WQ Output cell surface area=0
WQ Output cell continuity=0
WQ Output cumulative cell continuity=0
WQ Output face conc=0
WQ Output face dconc_dx=0
WQ Output face courant=0
WQ Output face peclet=0
WQ Output face adv mass=0
WQ Output face disp mass=0
WQ Output cell mass=0
WQ Output cell source sink temp=0
WQ Output cell source sink nsm=0
WQ Output MaxMinRange=-1
WQ Daily Max Min Mean=-1
WQ Daily Range=0
WQ Daily Time=0
WQ Create Restart=0
WQ Fixed Restart=0
WQ System Summary=0
WQ Use Fixed Temperature=0
Sorting and Armoring Iterations= 10
XS Update Threshold= 0.02
Hydraulics Update Threshold= 0.02
Energy Slope Method= 1
Volume Change Method= 0
XS Weighting Method= 0
Number of US Weighted Cross Sections= 1
Number of DS Weighted Cross Sections= 1
Upstream XS Weight=0.25
Main XS Weight=0.5
Downstream XS Weight=0.25
Number of DS XS's Weighted with US Boundary= 1
Upstream Boundary Weight= 1
Weight of XSs Associated with US Boundary= 0
Number of US XS's Weighted with DS Boundary= 1
Downstream Boundary Weight= 0.5
Weight of XSs Associated with DS Boundary= 0.5
Sediment Output Level= 4
Mass or Volume Output= 0
Output Increment Type= 1
Profile and TS Output Increment= 10
XS Output Flag= 0
XS Output Increment= 10
Disregard all LS=0
Disregard all Conn=0
Disregard all Breaches=0
Disregard all Pumps=0

--- Stream0291.f01 (steady flow) ---

Flow Title=Multiple
Number of Profiles=7
Profile Names=10-year,25-year,50-year,1pct_min,100-year,1pct_plu,500-year
River Rch & RM= Stream0291,Reach-1,28624
     785    1279    1730    1132    2258    4506    3814
River Rch & RM= Stream0291,Reach-1,23618
    1094    1818    2488    1646    3284    6553    5675
River Rch & RM= Stream0291,Reach-1,23196
    1366    2290    3153    2097    4183    8347    7304
River Rch & RM= Stream0291,Reach-1,21885
    1574    2639    3637    2418    4824    9626    8419
River Rch & RM= Stream0291,Reach-1,18681
    1732    2908    4011    2668    5324   10623    9301
River Rch & RM= Stream0291,Reach-1,14644
    1892    3171    4367    2898    5782   11536   10052
River Rch & RM= Stream0291,Reach-1,8732
    2180    3665    5058    3361    6706   13381   11694
Boundary for River Rch & Prof#=Stream0291,Reach-1,1
Up Type=0
Dn Type=3
Dn Slope=0.005
Boundary for River Rch & Prof#=Stream0291,Reach-1,2
Up Type=0
Dn Type=3
Dn Slope=0.005
Boundary for River Rch & Prof#=Stream0291,Reach-1,3
Up Type=0
Dn Type=3
Dn Slope=0.005
Boundary for River Rch & Prof#=Stream0291,Reach-1,4
Up Type=0
Dn Type=3
Dn Slope=0.005
Boundary for River Rch & Prof#=Stream0291,Reach-1,5
Up Type=0
Dn Type=3
Dn Slope=0.005
Boundary for River Rch & Prof#=Stream0291,Reach-1,6
Up Type=0
Dn Type=3
Dn Slope=0.005
Boundary for River Rch & Prof#=Stream0291,Reach-1,7
Up Type=0
Dn Type=3
Dn Slope=0.005

--- Stream0291.g01 (geometry) ---

Geom Title=Existing Conditions
Program Version=4.10

River Reach=Stream0291      ,Reach-1
Reach XY= 30
        2387525.       13713075.      2388668.93     13714316.87
      2389623.45     13714278.75      2390369.39     13714680.59
      2390438.11     13714988.24      2390864.35       13715265.
      2392021.38      13717026.5       2391986.1     13717685.06
      2394169.46     13719922.58      2394680.85     13721427.29
      2395571.88     13722576.63      2395374.96     13723405.02
      2395682.85     13723931.19      2396461.53     13724211.43
      2396382.48     13724728.58      2396819.55     13724972.53
      2396978.35     13725766.91      2397523.72     13725778.37
      2397908.54     13726107.87      2398271.45     13726626.47
      2398533.07     13727681.32      2399569.55     13728622.53
      2399419.53     13729377.45      2398481.98     13730375.21
      2399021.88     13730776.62       2399175.4     13731195.13
      2399076.05     13731864.57      2399275.47     13732095.16
      2399126.19      13732514.5        2399425.       13732875.

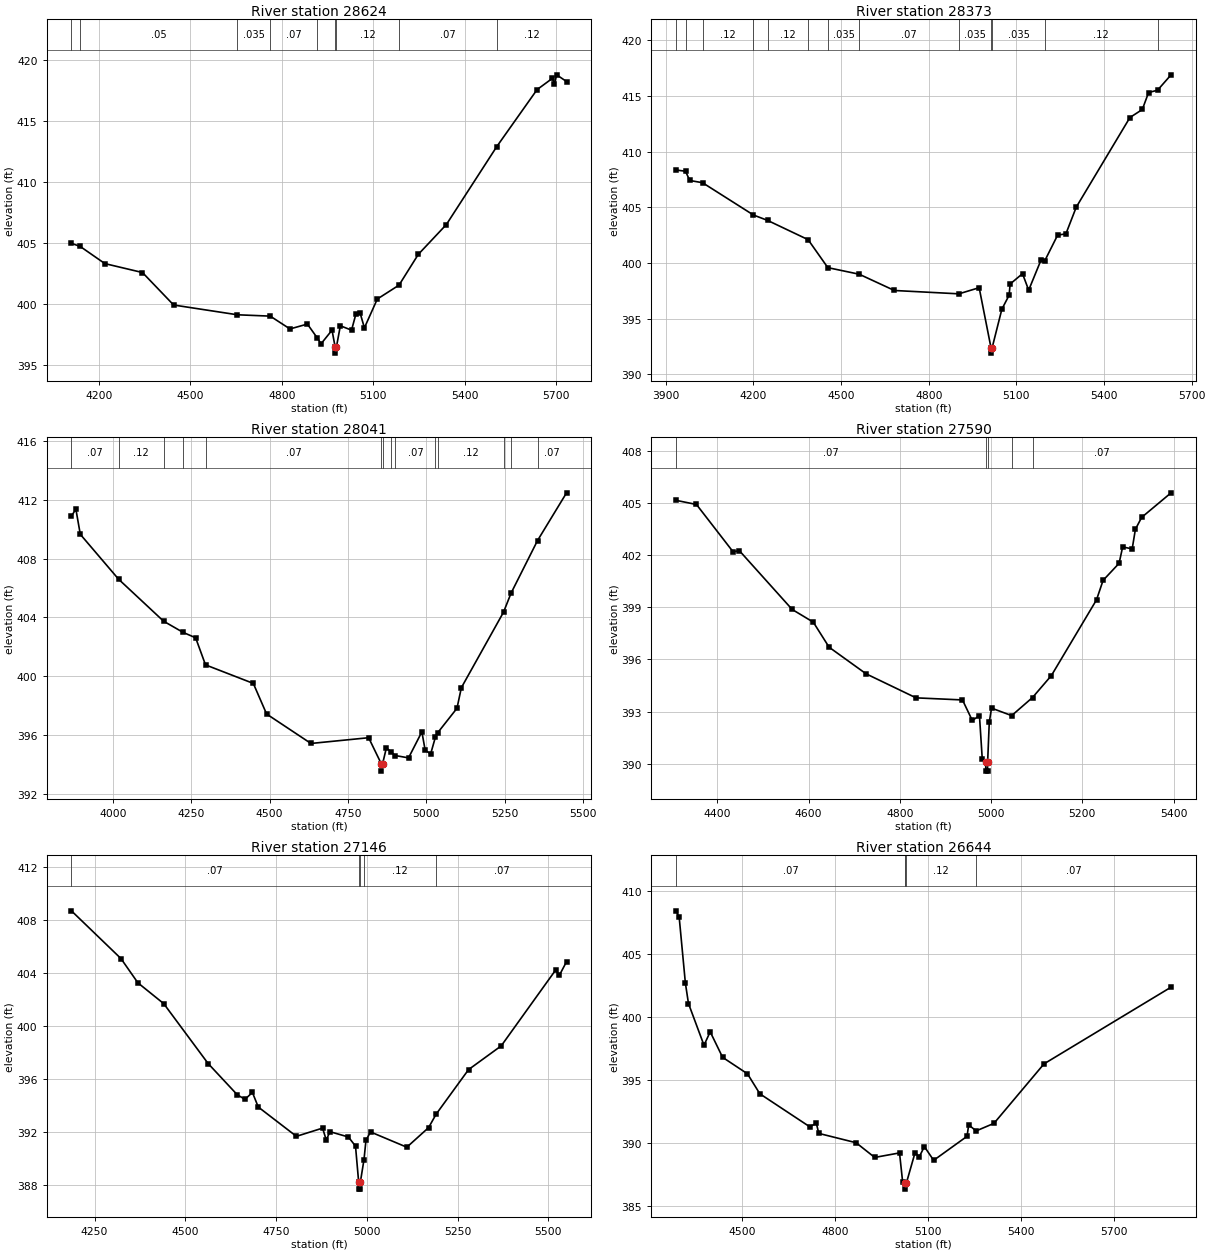
Type RM Length L Ch R = 1 ,28624   ,251,251,251
BEGIN DESCRIPTION:
Stream0291 54.0
END DESCRIPTION:
XS GIS Cut Line= 3
      2386903.88     13713637.78      2387660.57     13713133.32
      2388137.61     13712601.45
#Sta/Elev= 30
    4110  404.96  4138.5  404.71  4219.8   403.3    4343  402.57  4445.2  399.91
  4654.4  399.11  4762.1     399  4826.8  397.95  4883.9  398.35    4917  397.19
  4928.6  396.73  4964.7  397.85  4974.9  396.47  4975.2  395.97  4979.1  396.47
    4992  398.21  5028.7  397.85  5042.9  399.16  5057.1  399.23  5070.9  398.04
  5113.2   400.4  5184.5  401.54  5247.7  404.06  5339.7   406.5  5504.9  412.88
  5637.2  417.55  5687.3  418.47    5694  418.04  5701.5  418.76  5733.9  418.21
#Mann= 9 ,-1 , 0
    4110     .07       0  4138.5     .05       0  4654.4    .035       0
  4762.1     .07       0    4917     .12       0  4974.9     .05       0
  4979.1     .12       0  5184.5     .07       0  5504.9     .12       0
Bank Sta=4974.9,4979.1
XS Rating Curve= 0 ,0
Exp/Cntr=0.3,0.1

Type RM Length L Ch R = 1 ,28373   ,332,332,332
BEGIN DESCRIPTION:
XS6375
END DESCRIPTION:
XS GIS Cut Line= 3
      2386975.12     13714081.98      2387808.63     13713303.31
      2388208.69      13712919.7
#Sta/Elev= 30
  3934.6  408.34  3967.4  408.23  3981.9   407.4  4025.7   407.2  4200.1   404.3
  4248.2  403.82  4387.1  402.09  4454.6  399.58    4562  398.99  4682.4  397.53
  4903.1  397.23  4972.6  397.78    5013  392.41  5013.3  391.91  5017.2  392.41
  5050.3  395.85  5075.2  397.11  5078.6  398.11    5121  399.04  5142.1  397.56
  5184.6  400.28  5197.5  400.21  5241.2   402.5  5269.5  402.61    5305  405.01
  5488.7  413.05  5531.1  413.77  5552.5  415.29  5583.2   415.5  5629.5  416.88
#Mann= 13 ,-1 , 0
  3934.6     .12       0  3967.4     .07       0  4025.7     .12       0
  4200.1     .07       0  4248.2     .12       0  4387.1     .07       0
  4454.6    .035       0    4562     .07       0  4903.1    .035       0
    5013    .035       0  5017.2    .035       0  5197.5     .12       0
  5583.2     .07       0
Bank Sta=5013,5017.2
XS Rating Curve= 0 ,0
Exp/Cntr=0.3,0.1

Type RM Length L Ch R = 1 ,28041   ,451,451,451
BEGIN DESCRIPTION:
Stream0291 53.0
END DESCRIPTION:
XS GIS Cut Line= 3
      2387224.97     13714325.03        2388025.       13713525.
      2388224.99     13713125.03
#Sta/Elev= 30
  3868.3  410.89  3882.5  411.36  3896.6  409.65  4018.7   406.6    4162  403.75
  4224.1  402.99  4264.3  402.62  4295.8  400.78  4448.2  399.52  4490.6  397.44
    4632  395.44  4815.9  395.83  4856.2  394.06  4856.5  393.56  4860.4  394.06
  4872.4  395.14  4886.5  394.88  4900.7  394.62  4943.1  394.46  4985.6  396.23
  4996.2  394.97  5013.7  394.74  5028.9  395.88  5036.5  396.18  5097.5  397.83
  5111.5  399.23  5245.9  404.36  5270.1  405.66  5354.4  409.23  5446.9  412.47
#Mann= 14 ,-1 , 0
  3868.3     .07       0  4018.7     .12       0    4162     .07       0
  4224.1    .035       0  4295.8     .07       0  4856.2     .05       0
  4860.4     .07       0  4886.5     .12       0  4900.7     .07       0
  5028.9    .035       0  5036.5     .12       0  5245.9     .07       0
  5270.1     .12       0  5354.4     .07       0
Bank Sta=4856.2,4860.4
XS Rating Curve= 0 ,0
Exp/Cntr=0.3,0.1

Type RM Length L Ch R = 1 ,27590   ,444,444,444
BEGIN DESCRIPTION:
Stream0291 52.0
END DESCRIPTION:
XS GIS Cut Line= 3
      2387825.01     13714424.98        2388175.       13713825.
      2388424.99     13713525.01
#Sta/Elev= 30
  4309.4  405.14  4354.4   404.9  4434.7  402.18  4448.3  402.25  4564.1  398.87
  4610.4  398.14  4645.1   396.7  4726.2  395.17  4835.7  393.79  4937.4  393.67
  4958.9  392.49  4974.6  392.77  4980.8  390.25  4988.2  390.08  4988.5  389.58
  4992.3  389.58  4992.5  390.08  4996.1  392.39  5001.1   393.2  5045.2  392.77
  5090.9  393.81  5132.2  395.07  5231.1  399.42  5245.5  400.54  5280.6  401.52
  5288.4  402.46  5309.3  402.35  5316.4  403.48  5330.1  404.16  5394.5  405.57
#Mann= 5 ,-1 , 0
  4309.4     .07       0  4988.2     .05       0  4992.5     .07       0
  5045.2     .12       0  5090.9     .07       0
Bank Sta=4988.2,4992.5
XS Rating Curve= 0 ,0
Exp/Cntr=0.3,0.1

Type RM Length L Ch R = 1 ,27146   ,502,502,502
BEGIN DESCRIPTION:
Stream0291 51.0
END DESCRIPTION:
XS GIS Cut Line= 3
        2388325.     13714925.01        2388475.       13714125.
        2388475.     13713574.96
#Sta/Elev= 30
  4186.3  408.69  4322.8  405.09  4369.5  403.26  4440.7  401.69  4562.8  397.18
  4643.3  394.82  4664.5  394.48  4684.9     395    4701   393.9  4806.1  391.69
  4878.2  392.31  4888.3  391.41  4898.5  392.04  4949.4  391.64  4968.9  390.95
  4977.7  388.21    4978  387.71  4981.8  387.71  4982.1  388.21  4992.3  389.94
  4997.7  391.39  5010.3  392.02  5110.3  390.87  5170.3  392.35    5191  393.36
  5280.3  396.72  5370.3  398.51  5520.3  404.23  5530.3  403.82  5550.3  404.86
#Mann= 5 ,-1 , 0
  4186.3     .07       0  4977.7     .05       0  4982.1     .07       0
  4992.3     .12       0    5191     .07       0
Bank Sta=4977.7,4982.1
XS Rating Curve= 0 ,0
Exp/Cntr=0.3,0.1

Type RM Length L Ch R = 1 ,26644   ,359,359,359
BEGIN DESCRIPTION:
XS6374
END DESCRIPTION:
XS GIS Cut Line= 3
       2388823.1     13715085.46      2388877.93     13714169.72
      2388647.94     13713529.03
#Sta/Elev= 30
  4286.7  408.44  4297.2  407.94  4317.2   402.7  4327.2  401.07  4377.3  397.75
  4397.3  398.82  4437.4  396.79  4517.6  395.48  4557.6  393.89  4717.9  391.28
  4739.9  391.53    4748  390.74  4868.2     390  4928.3  388.83  5008.4  389.19
  5018.5  386.87  5025.9  386.81  5026.2  386.81  5026.5  386.31  5030.7  386.81
  5058.5  389.21  5072.5   388.9  5088.6  389.69  5118.6   388.6  5226.3  390.51
  5231.6  391.42  5255.7  390.94  5313.2  391.54  5474.7  396.27  5884.8  402.37
#Mann= 5 ,-1 , 0
  4286.7     .07       0  5025.9     .12       0  5026.2     .05       0
  5030.7     .12       0  5255.7     .07       0
Bank Sta=5026.2,5030.7
XS Rating Curve= 0 ,0
Exp/Cntr=0.3,0.1

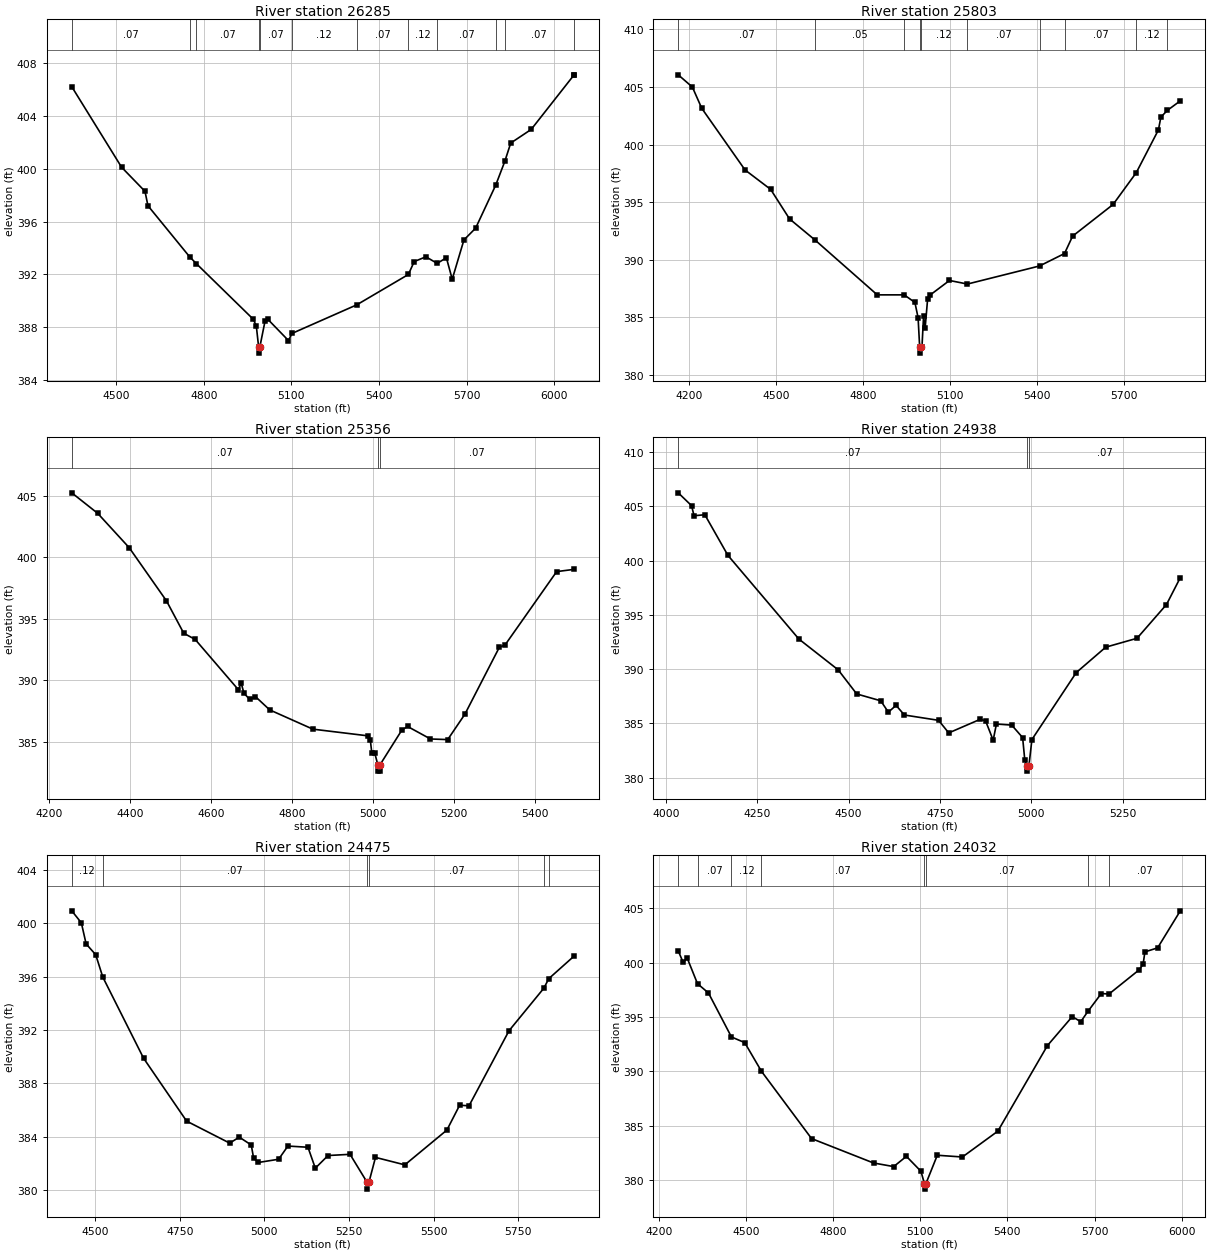
Type RM Length L Ch R = 1 ,26285   ,482,482,482
BEGIN DESCRIPTION:
Stream0291 50.0
END DESCRIPTION:
XS GIS Cut Line= 3
        2389225.     13715074.99        2389175.       13714425.
      2389124.74      13713359.1
#Sta/Elev= 30
  4348.2  406.23  4518.7  400.13  4598.9   398.3    4609  397.21  4751.7  393.34
  4774.8  392.82    4970   388.6  4980.1  388.08  4987.8  386.54  4988.1  386.04
  4992.4  386.54  5010.1  388.49  5020.1  388.59  5090.2  386.99  5101.8  387.53
    5324   389.7  5500.6     392  5520.7  392.98  5560.7  393.34  5599.3  392.84
  5630.8  393.27  5650.8  391.64  5690.9  394.62  5730.9  395.51  5799.7  398.77
  5830.8  400.57  5851.1  401.96  5921.1  402.99  6066.7  407.09  6067.2  407.13
#Mann= 12 ,-1 , 0
  4348.2     .07       0  4751.7     .05       0  4774.8     .07       0
  4987.8     .05       0  4992.4     .07       0  5101.8     .12       0
    5324     .07       0  5500.6     .12       0  5599.3     .07       0
  5799.7     .12       0  5830.8     .07       0  6066.7     .12       0
Bank Sta=4987.8,4992.4
XS Rating Curve= 0 ,0
Exp/Cntr=0.3,0.1

Type RM Length L Ch R = 1 ,25803   ,447,447,447
BEGIN DESCRIPTION:
Stream0291 49.0
END DESCRIPTION:
XS GIS Cut Line= 3
      2389324.99     13715075.02        2389575.       13714275.
        2389175.       13713475.
#Sta/Elev= 30
  4161.4  406.06  4210.1     405  4242.6  403.15  4391.9   397.8  4480.4  396.11
  4545.4  393.55  4634.5  391.69  4848.2  386.95  4941.2  386.95  4978.1  386.29
  4989.1  384.97  4994.6  382.39  4994.9  381.89  4999.4  382.39  5002.4  382.39
    5008  385.09  5013.5   384.1  5021.9  386.56  5030.3  386.93  5097.4   388.2
  5159.3  387.89  5408.3  389.46  5494.4  390.54  5522.3  392.05    5662   394.8
  5742.2  397.57  5818.5  401.28  5826.9  402.39  5849.7  402.98    5894   403.8
#Mann= 10 ,-1 , 0
  4161.4     .07       0  4634.5     .05       0  4941.2     .12       0
  4994.6     .05       0  4999.4     .12       0  5159.3     .07       0
  5408.3     .12       0  5494.4     .07       0  5742.2     .12       0
  5849.7     .07       0
Bank Sta=4994.6,4999.4
XS Rating Curve= 0 ,0
Exp/Cntr=0.3,0.1

Type RM Length L Ch R = 1 ,25356   ,418,418,418
BEGIN DESCRIPTION:
Stream0291 48.0
END DESCRIPTION:
XS GIS Cut Line= 3
      2389424.99     13715075.01        2389925.       13714525.
        2390275.       13714175.
#Sta/Elev= 30
  4256.7  405.27  4320.6   403.6  4398.3   400.8  4490.2  396.47  4532.8  393.83
  4561.1  393.32  4667.2  389.24  4674.7  389.74  4681.4  388.94  4695.6  388.43
  4709.8  388.66  4744.9  387.58  4851.4  386.01  4986.2  385.47  4992.9  385.16
  4996.6   384.1  5003.6   384.1  5011.7  383.09  5012.1  382.59  5016.2  382.59
  5016.6  383.09  5070.7  385.93  5084.9  386.23  5141.4  385.21  5183.9  385.16
  5226.3  387.23  5311.2  392.68  5325.3  392.87  5452.6  398.85    5495  399.03
#Mann= 3 ,-1 , 0
  4256.7     .07       0  5011.7     .05       0  5016.6     .07       0
Bank Sta=5011.7,5016.6
XS Rating Curve= 0 ,0
Exp/Cntr=0.3,0.1

Type RM Length L Ch R = 1 ,24938   ,463,463,463
BEGIN DESCRIPTION:
Stream0291 47.0
END DESCRIPTION:
XS GIS Cut Line= 3
      2389475.03     13715174.98        2390275.       13714625.
        2390325.       13714225.
#Sta/Elev= 30
  4033.8  406.24  4070.2  405.06  4077.1  404.13  4106.6  404.22  4169.7  400.48
  4363.9  392.77  4471.5  389.93  4522.2  387.71  4587.9  387.08  4608.8  386.03
  4629.8  386.66  4652.7  385.77  4746.2  385.28    4774  384.12  4859.8  385.37
  4874.7  385.24  4895.6  383.45  4904.5  384.94  4946.4  384.84  4976.2  383.69
  4982.2   381.6  4988.6   381.1    4989   380.6  4993.5   381.1  5001.6  383.51
    5123  389.68  5203.6  392.02  5289.3  392.84  5369.9  395.95  5407.7  398.43
#Mann= 3 ,-1 , 0
  4033.8     .07       0  4988.6     .05       0  4993.5     .07       0
Bank Sta=4988.6,4993.5
XS Rating Curve= 0 ,0
Exp/Cntr=0.3,0.1

Type RM Length L Ch R = 1 ,24475   ,443,443,443
BEGIN DESCRIPTION:
Stream0291 46.0
END DESCRIPTION:
XS GIS Cut Line= 3
      2390025.02     13715374.98        2390425.       13714975.
      2391224.97     13714525.02
#Sta/Elev= 30
  4430.8  400.93  4459.1  400.03  4473.2  398.45  4501.5  397.64  4522.5  395.96
  4642.9  389.88  4770.2  385.16  4897.5  383.51  4925.7  383.96  4961.1  383.37
  4968.2  382.37  4982.3  382.06    5042   382.3  5069.4  383.29  5128.7   383.2
  5150.4  381.63    5188  382.58    5253  382.67  5303.7  380.56  5304.1  380.06
  5308.7  380.56  5328.2  382.44  5414.9  381.88  5539.2  384.49  5576.8  386.35
  5604.6  386.31  5722.8  391.94  5825.4  395.12  5840.5  395.85  5914.3  397.52
#Mann= 6 ,-1 , 0
  4430.8     .12       0  4522.5     .07       0  5303.7     .05       0
  5308.7     .07       0  5825.4     .12       0  5840.5     .07       0
Bank Sta=5303.7,5308.7
XS Rating Curve= 0 ,0
Exp/Cntr=0.3,0.1

Type RM Length L Ch R = 1 ,24032   ,414,414,414
BEGIN DESCRIPTION:
Stream0291 45.0
END DESCRIPTION:
XS GIS Cut Line= 3
        2390075.       13715425.        2390775.       13715225.
      2391374.99     13714425.01
#Sta/Elev= 30
  4267.2  401.07  4284.1  400.02  4298.4  400.39  4333.5  398.06  4371.2  397.21
  4450.3  393.17    4496  392.65  4553.6  390.02  4726.1  383.84  4939.3   381.6
  5008.8  381.27  5052.5  382.21  5102.5  380.84  5114.6   379.7    5115   379.2
  5119.6   379.7  5158.8  382.31  5245.2  382.15  5367.1  384.52  5537.9  392.38
  5623.3  395.04  5652.5  394.57    5677  395.51  5723.3  397.16  5749.7  397.11
  5852.5  399.31  5867.1  399.83  5873.3  400.98  5917.1  401.35  5995.2  404.75
#Mann= 8 ,-1 , 0
  4267.2     .12       0  4333.5     .07       0  4450.3     .12       0
  4553.6     .07       0  5114.6     .05       0  5119.6     .07       0
    5677     .12       0  5749.7     .07       0
Bank Sta=5114.6,5119.6
XS Rating Curve= 0 ,0
Exp/Cntr=0.3,0.1

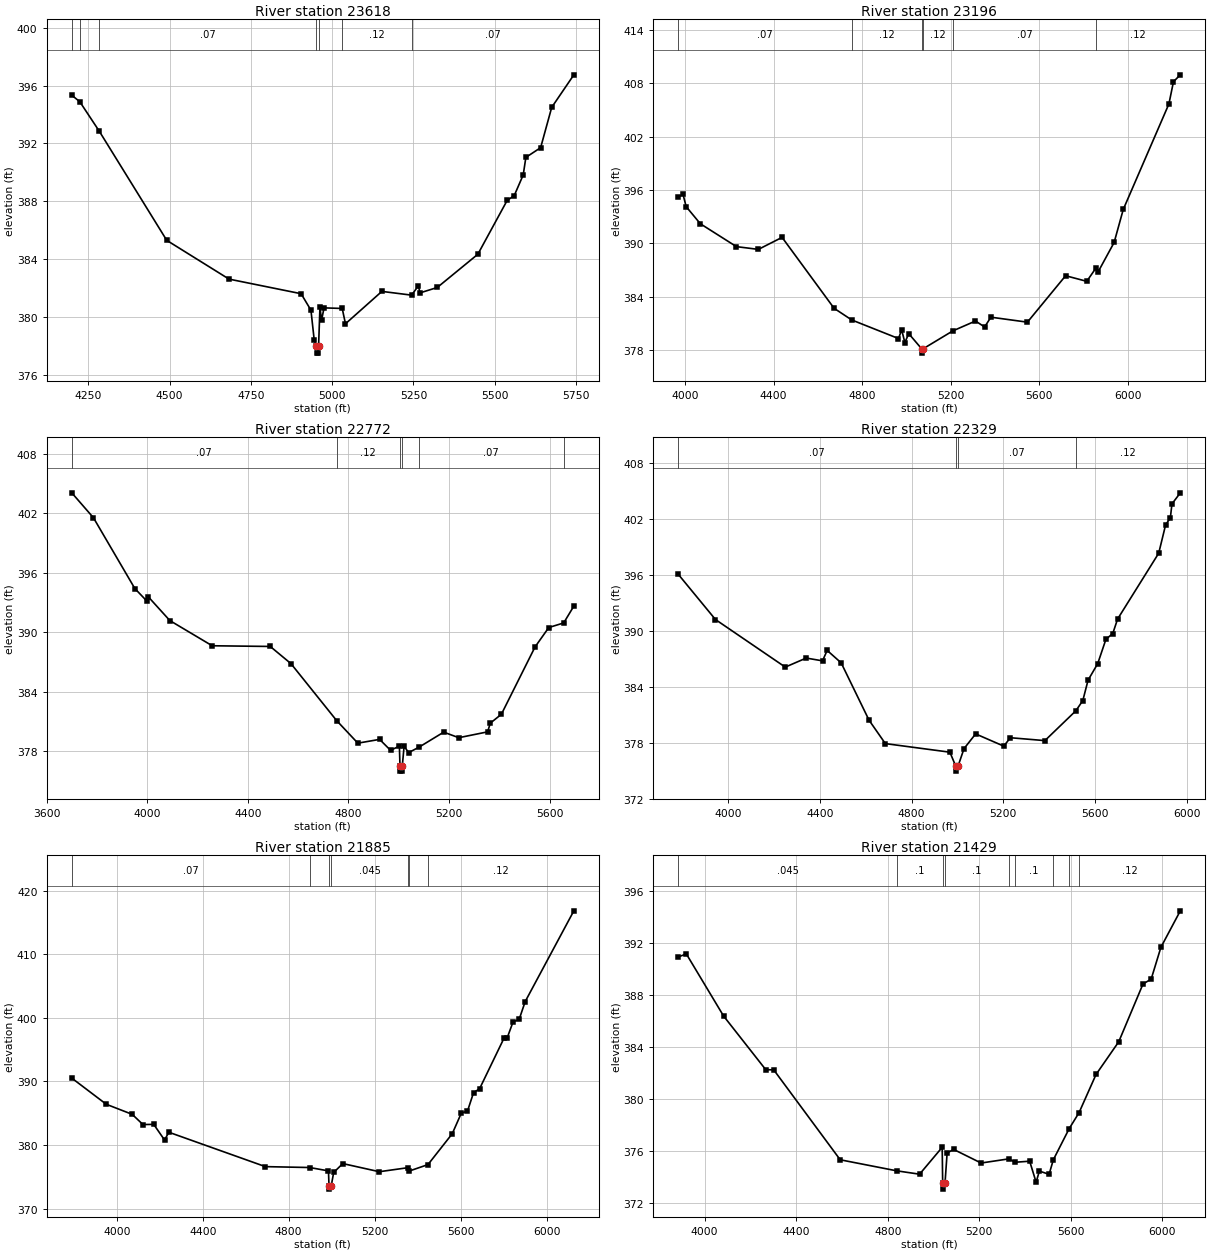
Type RM Length L Ch R = 1 ,23618   ,422,422,422
BEGIN DESCRIPTION:
Stream0291 44.0
END DESCRIPTION:
XS GIS Cut Line= 3
      2390225.02       13715425.        2391025.       13715525.
      2391374.98     13714875.04
#Sta/Elev= 30
  4199.2  395.34  4223.9  394.89  4284.1  392.84  4491.4   385.3  4682.9  382.62
  4904.6  381.61  4934.9  380.47  4944.9  378.42  4951.6     378  4952.1   377.5
  4957.9   377.5  4958.4     378  4962.6  380.66  4967.6  379.78  4975.2  380.63
  5031.1  380.59  5041.1  379.53  5153.1  381.77  5244.7  381.51    5265  382.15
  5270.7  381.67  5323.4  382.04  5448.3  384.34  5538.4  388.06  5560.3   388.4
  5587.9  389.83    5596  391.04  5641.4  391.71  5675.5   394.5  5743.6  396.75
#Mann= 7 ,-1 , 0
  4199.2     .07       0  4223.9     .12       0  4284.1     .07       0
  4951.6     .05       0  4958.4     .07       0  5031.1     .12       0
  5244.7     .07       0
Bank Sta=4951.6,4958.4
XS Rating Curve= 0 ,0
Exp/Cntr=0.3,0.1

Type RM Length L Ch R = 1 ,23196   ,424,424,424
BEGIN DESCRIPTION:
Stream0291 43.0
END DESCRIPTION:
XS GIS Cut Line= 3
        2390425.       13716525.        2391225.       13715875.
        2392425.       13715575.
#Sta/Elev= 30
  3969.2  395.21  3990.8   395.5  4005.1  394.12  4069.1   392.2  4232.1  389.63
  4331.2  389.32  4438.2  390.67  4673.1   382.7  4752.7  381.39    4964   379.3
  4978.4  380.27  4992.8  378.85  5010.3  379.85  5068.2  378.16  5068.7  377.66
  5076.1  378.16  5209.5  380.16  5311.8  381.27    5353   380.6  5381.4   381.7
  5546.3  381.14  5718.9  386.36  5814.3  385.73  5855.5  387.21  5865.8   386.8
    5938   390.1  5979.2  393.81  6185.4  405.67    6206  408.17  6236.9  408.94
#Mann= 6 ,-1 , 0
  3969.2     .07       0  4752.7     .12       0  5068.2     .05       0
  5076.1     .12       0  5209.5     .07       0  5855.5     .12       0
Bank Sta=5068.2,5076.1
XS Rating Curve= 0 ,0
Exp/Cntr=0.3,0.1

Type RM Length L Ch R = 1 ,22772   ,443,443,443
BEGIN DESCRIPTION:
Stream0291 42.0
END DESCRIPTION:
XS GIS Cut Line= 3
      2390225.02     13716724.99        2391425.       13716225.
      2392075.01       13715975.
#Sta/Elev= 30
  3699.8  404.07  3785.9  401.56  3950.6  394.42  3998.2  393.16  4003.6   393.6
  4089.8  391.19  4258.2  388.65    4489  388.58  4571.3  386.85  4752.9  381.11
  4837.3  378.83  4923.9  379.21  4967.3  378.11  5002.5  378.53  5004.9  376.51
  5005.4  376.01  5013.5  376.01    5014  376.51  5021.2  378.51  5039.4  377.88
  5079.5  378.41  5178.7  379.94  5238.7  379.38  5353.3  379.97  5364.1  380.85
    5408  381.74  5541.9  388.53  5596.6  390.49  5655.8  390.95  5696.2  392.65
#Mann= 6 ,-1 , 0
  3699.8     .07       0  4752.9     .12       0  5004.9     .05       0
    5014     .12       0  5079.5     .07       0  5655.8     .12       0
Bank Sta=5004.9,5014
XS Rating Curve= 0 ,0
Exp/Cntr=0.3,0.1

Type RM Length L Ch R = 1 ,22329   ,444,444,444
BEGIN DESCRIPTION:
Stream0291 41.0
END DESCRIPTION:
XS GIS Cut Line= 3
        2390475.       13716775.        2391675.       13716575.
      2392475.02     13716024.99
#Sta/Elev= 30
  3783.7  396.05  3945.9   391.2    4250   386.1  4341.3  387.07  4412.3  386.77
  4432.5  387.89  4493.4  386.56    4615  380.41    4686   377.9  4967.3  376.98
  4993.2  375.45  4993.7  374.95  5002.3  375.45  5028.7  377.36  5079.4  378.94
  5201.9  377.63  5230.8  378.53  5381.1  378.22  5515.7  381.41  5546.3  382.51
  5569.2   384.7  5611.2  386.47    5647  389.08  5676.8   389.7  5697.8  391.25
    5877  398.31  5906.8  401.32  5927.8  402.12  5934.7  403.59  5971.1  404.78
#Mann= 4 ,-1 , 0
  3783.7     .07       0  4993.2     .05       0  5002.3     .07       0
  5515.7     .12       0
Bank Sta=4993.2,5002.3
XS Rating Curve= 0 ,0
Exp/Cntr=0.3,0.1

Type RM Length L Ch R = 1 ,21885   ,456,456,456
BEGIN DESCRIPTION:
Stream0291 40.0
END DESCRIPTION:
XS GIS Cut Line= 3
      2390724.98       13717025.        2391925.       13716925.
      2392724.97     13716125.03
#Sta/Elev= 30
    3791  390.53  3951.6  386.41    4072  384.83  4122.2  383.22  4172.3  383.25
  4222.5  380.79  4242.6  382.01  4691.6   376.6  4897.5  376.46  4985.1  375.93
  4987.6  373.56  4988.1  373.06  4997.8  373.56  5009.3  375.68  5051.7  377.08
  5221.5   375.8  5354.1  376.43  5359.4  375.89  5447.9  376.92  5560.9  381.78
  5603.3  385.04  5631.6  385.32  5659.9  388.23  5688.1  388.86  5801.3  396.79
  5815.4  396.77  5843.7  399.37    5872  399.76  5900.3  402.58  6126.5  416.85
#Mann= 7 ,-1 , 0
    3791     .07       0  4897.5    .045       0  4987.6    .045       0
  4997.8    .045       0  5354.1     .12       0  5359.4      .1       0
  5447.9     .12       0
Bank Sta=4987.6,4997.8
XS Rating Curve= 0 ,0
Exp/Cntr=0.3,0.1

Type RM Length L Ch R = 1 ,21429   ,475,475,475
BEGIN DESCRIPTION:
Stream0291 39.0
END DESCRIPTION:
XS GIS Cut Line= 3
        2391225.       13718075.        2392025.       13717325.
      2392825.02     13716574.98
#Sta/Elev= 30
  3884.7  390.96  3920.1  391.19  4082.8  386.41  4266.9  382.28  4302.1  382.26
  4592.2  375.34  4838.8  374.49    4939  374.23  5037.7   376.3  5039.8  373.58
  5040.3  373.08  5050.2  373.58  5059.2  375.86  5087.5  376.14  5207.7  375.09
  5328.7  375.41  5356.3  375.15  5419.9  375.23    5448  373.61  5462.2  374.47
  5504.7  374.22  5523.2  375.34  5592.5  377.74  5635.6  378.97  5709.8  381.91
    5809  384.43    5915  388.88  5950.6  389.25  5993.1   391.7  6077.9  394.51
#Mann= 9 ,-1 , 0
  3884.7    .045       0  4838.8      .1       0  5039.8     .05       0
  5050.2      .1       0  5328.7     .07       0  5356.3      .1       0
  5523.2     .12       0  5592.5     .07       0  5635.6     .12       0
Bank Sta=5039.8,5050.2
XS Rating Curve= 0 ,0
Exp/Cntr=0.3,0.1

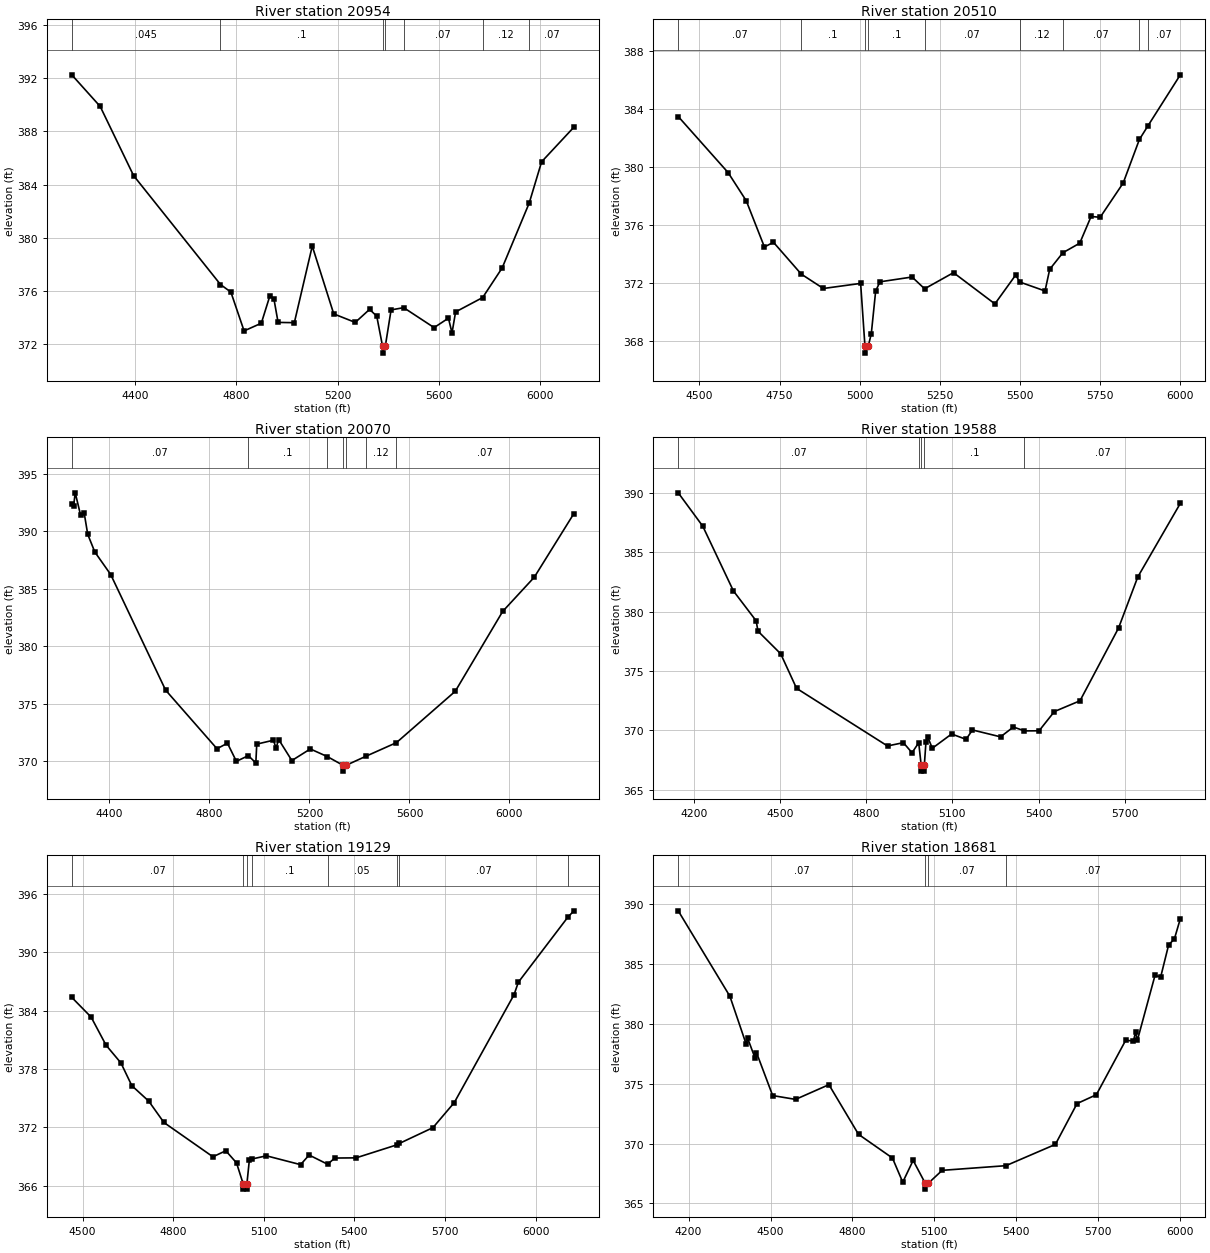
Type RM Length L Ch R = 1 ,20954   ,444,444,444
BEGIN DESCRIPTION:
Stream0291 38.0
END DESCRIPTION:
XS GIS Cut Line= 3
      2391275.02     13718124.99        2392025.       13717725.
      2392824.97     13716925.03
#Sta/Elev= 30
  4150.4  392.26  4262.6  389.88  4394.4  384.68  4737.3  376.49  4778.3  375.92
  4830.4     373  4898.4  373.58  4932.4  375.65  4948.3  375.39  4964.6  373.64
  5028.7  373.62  5099.4  379.38  5184.2  374.28  5269.1  373.64  5325.6  374.62
  5353.9  374.11    5377  371.83  5377.5  371.33  5387.5  371.83  5410.5  374.58
  5460.2  374.75  5580.2  373.25  5636.8  373.96  5650.9  372.85  5665.1  374.43
  5771.9  375.51  5848.9  377.74  5955.6  382.62  6004.5  385.72  6131.7  388.32
#Mann= 7 ,-1 , 0
  4150.4    .045       0  4737.3      .1       0    5377     .05       0
  5387.5      .1       0  5460.2     .07       0  5771.9     .12       0
  5955.6     .07       0
Bank Sta=5377,5387.5
XS Rating Curve= 0 ,0
Exp/Cntr=0.3,0.1

Type RM Length L Ch R = 1 ,20510   ,440,440,440
BEGIN DESCRIPTION:
Stream0291 37.0
END DESCRIPTION:
XS GIS Cut Line= 3
      2391925.02     13718424.98        2392325.       13718025.
      2392925.02     13717224.97
#Sta/Elev= 30
  4434.1  383.46  4589.6   379.6  4646.2  377.66  4702.8  374.48  4731.1   374.8
  4817.8  372.61  4886.6  371.62  5002.9  371.97  5016.3  367.67  5016.8  367.17
    5027  367.67  5036.2  368.52  5049.8  371.45  5063.3  372.08  5163.3  372.41
  5202.4   371.6  5292.5  372.71  5421.6  370.56  5486.2  372.54  5499.7  372.06
  5577.9  371.45  5592.5  372.94  5633.5  374.08  5686.2  374.74  5721.6  376.58
  5749.8  376.52  5821.6  378.88  5872.2  381.88  5898.9  382.82  5999.8  386.33
#Mann= 9 ,-1 , 0
  4434.1     .07       0  4817.8      .1       0  5016.3     .05       0
    5027      .1       0  5202.4     .07       0  5499.7     .12       0
  5633.5     .07       0  5872.2     .12       0  5898.9     .07       0
Bank Sta=5016.3,5027
XS Rating Curve= 0 ,0
Exp/Cntr=0.3,0.1

Type RM Length L Ch R = 1 ,20070   ,482,482,482
BEGIN DESCRIPTION:
Stream0291 36.0
END DESCRIPTION:
XS GIS Cut Line= 3
      2392075.02     13718824.98        2392625.       13718325.
        2393025.     13717124.99
#Sta/Elev= 30
  4249.3  392.36  4256.4  392.19  4263.1  393.36  4284.8   391.4  4298.9  391.61
  4313.1  389.75  4341.5  388.21    4405  386.25  4624.6  376.19  4830.1  371.09
    4872  371.57  4907.8  369.99  4955.6  370.49  4985.5  369.85  4989.2  371.49
  5055.8  371.83  5066.4  371.16  5076.9  371.89  5129.6  370.06  5203.4  371.07
  5271.9   370.4    5335  369.64  5335.5  369.14  5345.8  369.64  5426.4  370.44
    5548  371.62  5783.2  376.09  5972.9  383.04  6099.4  386.02  6257.5  391.55
#Mann= 7 ,-1 , 0
  4249.3     .07       0  4955.6      .1       0  5271.9     .07       0
    5335     .05       0  5345.8     .07       0  5426.4     .12       0
    5548     .07       0
Bank Sta=5335,5345.8
XS Rating Curve= 0 ,0
Exp/Cntr=0.3,0.1

Type RM Length L Ch R = 1 ,19588   ,459,459,459
BEGIN DESCRIPTION:
Stream0291 35.0
END DESCRIPTION:
XS GIS Cut Line= 3
      2392175.01       13718875.        2392975.       13718575.
      2393774.98     13718175.01
#Sta/Elev= 30
    4145  390.01  4230.4   387.2  4337.2  381.74  4416.4  379.22  4422.7  378.35
  4501.9  376.44  4557.1  373.53  4873.9  368.67  4929.1  368.95  4959.3   368.1
  4982.6  368.94  4991.2  367.05  4991.7  366.55  5001.7  366.55  5002.2  367.05
  5007.8  368.99  5013.4  369.45  5030.1  368.48  5097.2  369.68  5147.5  369.23
  5169.9  370.02  5267.7  369.44  5312.4  370.27  5350.9  369.94  5401.9  369.95
    5455  371.57  5544.4  372.48  5678.6  378.61  5745.7  382.92  5893.8  389.12
#Mann= 5 ,-1 , 0
    4145     .07       0  4982.6      .1       0  4991.2     .05       0
  5002.2      .1       0  5350.9     .07       0
Bank Sta=4991.2,5002.2
XS Rating Curve= 0 ,0
Exp/Cntr=0.3,0.1

Type RM Length L Ch R = 1 ,19129   ,448,448,448
BEGIN DESCRIPTION:
Stream0291 34.0
END DESCRIPTION:
XS GIS Cut Line= 3
      2392724.97     13719325.02        2393125.       13718975.
      2393924.99     13718175.01
#Sta/Elev= 30
  4464.1  385.37  4528.2  383.34  4577.6  380.45  4626.9  378.62    4663  376.28
    4719  374.69  4769.3  372.49  4931.6  368.96  4974.3  369.58  5009.8  368.33
  5032.2  366.13  5032.7  365.63  5043.5  365.63    5044  366.13  5052.2   368.6
  5060.7  368.73  5108.8  369.06  5221.9  368.15  5250.2  369.14  5311.6  368.19
  5335.1  368.83  5405.8  368.85    5540  370.18  5548.9  370.33  5660.3  371.96
    5731  374.54    5929  385.65  5943.2  386.93  6106.5   393.6    6127  394.28
#Mann= 8 ,-1 , 0
  4464.1     .07       0  5032.2     .05       0    5044     .07       0
  5060.7      .1       0  5311.6     .05       0    5540    .035       0
  5548.9     .07       0  6106.5     .12       0
Bank Sta=5032.2,5044
XS Rating Curve= 0 ,0
Exp/Cntr=0.3,0.1

Type RM Length L Ch R = 1 ,18681   ,447,447,447
BEGIN DESCRIPTION:
Stream0291 33.0
END DESCRIPTION:
XS GIS Cut Line= 3
      2392675.01       13719475.        2393475.       13719225.
      2394074.98     13718425.03
#Sta/Elev= 30
  4162.1  389.46  4351.2  382.32  4410.9  378.31  4416.2  378.81  4443.4  377.15
  4448.6  377.61  4507.8  374.02  4591.6   373.7  4713.7  374.93  4822.1  370.78
  4946.3   368.8    4984  366.78  5022.1   368.6  5066.2   366.7  5066.7   366.2
    5078   366.7  5128.4  367.77  5361.9  368.16  5542.9  369.94  5622.1  373.35
  5692.9  374.09  5800.2  378.64  5828.4  378.58  5836.7  379.33  5842.9  378.63
  5907.5  384.06  5928.4  383.94  5957.5  386.62  5978.4   387.1  6000.2   388.8
#Mann= 4 ,-1 , 0
  4162.1     .07       0  5066.2     .05       0    5078     .07       0
  5361.9     .07       0
Bank Sta=5066.2,5078
XS Rating Curve= 0 ,0
Exp/Cntr=0.3,0.1

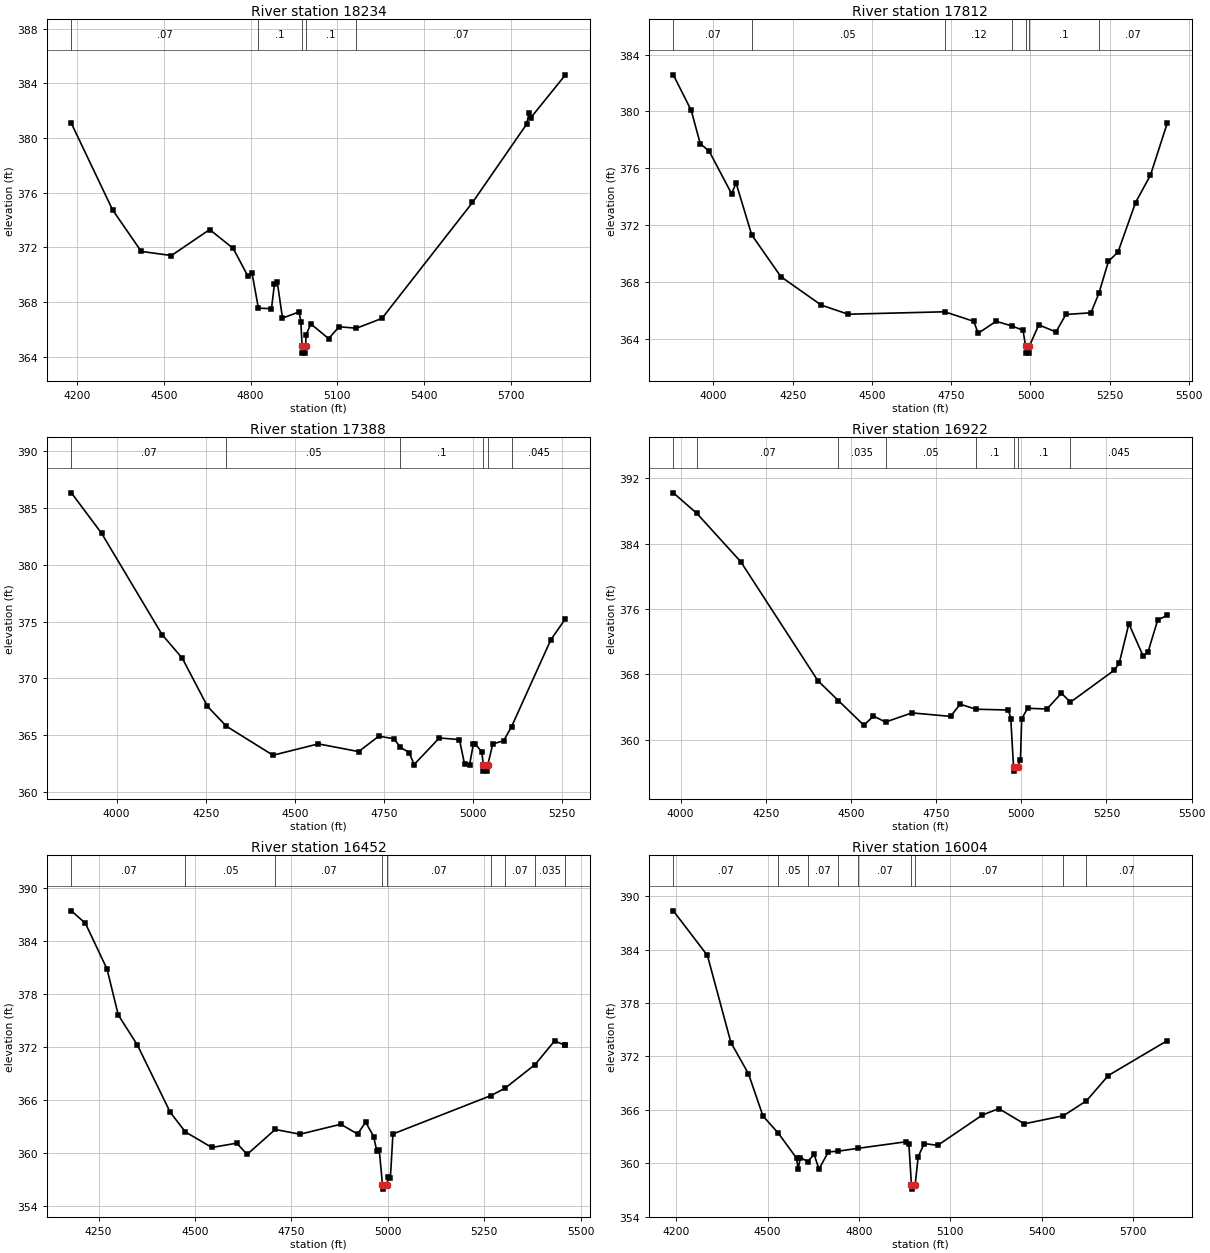
Type RM Length L Ch R = 1 ,18234   ,422,422,422
BEGIN DESCRIPTION:
Stream0291 32.0
END DESCRIPTION:
XS GIS Cut Line= 3
      2392974.96     13719675.01        2393775.       13719525.
      2394574.99     13719125.01
#Sta/Elev= 30
  4180.5  381.07    4323  374.74  4422.2   371.7  4526.5   371.4  4658.7   373.3
  4740.1  371.92    4791  369.89  4805.4  370.09  4827.2  367.55  4872.4  367.51
  4882.6  369.29  4892.7  369.43  4910.5  366.82  4968.2  367.28  4974.1  366.55
  4978.2  364.76  4978.7  364.26  4989.9  364.26  4990.4  364.76  4991.9  365.59
  5008.5   366.4    5070  365.32  5106.3  366.19    5166  366.08  5254.4   366.8
  5567.5  375.28  5754.7  381.01  5763.1  381.84  5768.7  381.47  5888.9  384.62
#Mann= 5 ,-1 , 0
  4180.5     .07       0  4827.2      .1       0  4978.2     .05       0
  4990.4      .1       0    5166     .07       0
Bank Sta=4978.2,4990.4
XS Rating Curve= 0 ,0
Exp/Cntr=0.3,0.1

Type RM Length L Ch R = 1 ,17812   ,424,424,424
BEGIN DESCRIPTION:
Stream0291 31.0
END DESCRIPTION:
XS GIS Cut Line= 3
      2393275.04     13720574.96        2394075.       13719775.
      2394474.98     13719625.01
#Sta/Elev= 30
  3873.5  382.57    3930  380.06  3958.3  377.73  3986.6  377.19  4057.3   374.2
  4071.4  374.95  4120.8   371.3  4212.9  368.36  4340.1  366.36    4425  365.72
  4729.5  365.89    4821  365.22  4835.1  364.38  4891.7  365.22  4943.2  364.88
  4976.5  364.59  4984.6  363.48  4985.1  362.98  4996.3  362.98  4996.8  363.48
  5026.2  364.97  5080.5  364.47  5111.6   365.7  5190.8  365.82  5215.7  367.18
    5246  369.44  5276.3   370.1  5331.5  373.58  5378.6  375.51    5432   379.2
#Mann= 7 ,-1 , 0
  3873.5     .07       0  4120.8     .05       0  4729.5     .12       0
  4943.2      .1       0  4984.6     .05       0  4996.8      .1       0
  5215.7     .07       0
Bank Sta=4984.6,4996.8
XS Rating Curve= 0 ,0
Exp/Cntr=0.3,0.1

Type RM Length L Ch R = 1 ,17388   ,466,466,466
BEGIN DESCRIPTION:
Stream0291 30.0
END DESCRIPTION:
XS GIS Cut Line= 3
        2393475.       13720925.        2394275.       13720125.
      2394524.97     13720075.01
#Sta/Elev= 30
  3872.9  386.34  3957.8  382.77  4127.5  373.85    4184  371.78  4254.7  367.54
  4307.6  365.79  4438.6  363.23  4565.9  364.23    4679  363.55  4735.6  364.91
    4778  364.68  4796.1  363.93  4820.4  363.47  4834.6  362.41  4905.3  364.75
  4961.8  364.61    4976  362.46  4990.1  362.38  5000.7  364.19  5006.8  364.19
  5024.7  363.53  5028.7  362.33  5029.2  361.83  5040.5  361.83    5041  362.33
  5055.3  364.22  5085.9  364.51  5108.2  365.76  5218.4  373.41  5259.2  375.25
#Mann= 6 ,-1 , 0
  3872.9     .07       0  4307.6     .05       0  4796.1      .1       0
  5028.7     .05       0    5041      .1       0  5108.2    .045       0
Bank Sta=5028.7,5041
XS Rating Curve= 0 ,0
Exp/Cntr=0.3,0.1

Type RM Length L Ch R = 1 ,16922   ,470,470,470
BEGIN DESCRIPTION:
Stream0291 29.0
END DESCRIPTION:
XS GIS Cut Line= 3
      2393575.04     13721274.97        2394325.       13720575.
      2394624.98     13720275.02
#Sta/Elev= 30
  3978.7  390.24    4048  387.71  4176.7   381.8  4402.9  367.24  4463.2   364.8
  4537.8  361.79  4566.1  362.91  4601.6  362.18    4679   363.3  4792.3  362.87
  4820.6  364.36    4867  363.75  4962.3  363.65  4969.1   362.6  4977.2  356.67
  4977.7  356.17  4989.5  356.67  4997.5  357.55  5001.1  362.59  5018.7  363.86
  5075.3  363.78  5117.7  365.71  5144.1  364.61  5273.3  368.54  5287.4  369.39
  5315.7  374.21  5358.1  370.21  5372.3  370.81  5400.5   374.7  5428.8  375.23
#Mann= 8 ,-1 , 0
  3978.7     .12       0    4048     .07       0  4463.2    .035       0
  4601.6     .05       0    4867      .1       0  4977.2     .05       0
  4989.5      .1       0  5144.1    .045       0
Bank Sta=4977.2,4989.5
XS Rating Curve= 0 ,0
Exp/Cntr=0.3,0.1

Type RM Length L Ch R = 1 ,16452   ,448,448,448
BEGIN DESCRIPTION:
Stream0291 28.0
END DESCRIPTION:
XS GIS Cut Line= 3
      2393874.97     13721475.03        2394525.       13720975.
      2394825.01     13720624.98
#Sta/Elev= 30
  4179.4  387.44  4215.7  386.03  4271.9  380.85  4300.9  375.67  4350.7  372.25
  4435.9  364.64  4475.1  362.43  4543.7  360.67  4608.1  361.16  4635.2  359.89
    4708  362.71  4772.1  362.17  4878.1   363.3  4921.6  362.19  4942.4  363.54
  4963.2  361.91  4971.4  360.24  4977.7  360.39  4986.1  356.46  4986.6  355.96
  4998.4  356.46  4999.5  357.32  5006.6  357.23  5013.2   362.2  5266.7  366.53
  5303.1  367.35  5381.8  370.05  5432.5  372.73  5459.6  372.22  5460.5  372.22
#Mann= 9 ,-1 , 0
  4179.4     .07       0  4475.1     .05       0    4708     .07       0
  4986.1     .05       0  4998.4     .07       0  5266.7    .035       0
  5303.1     .07       0  5381.8    .035       0  5459.6     .07       0
Bank Sta=4986.1,4998.4
XS Rating Curve= 0 ,0
Exp/Cntr=0.3,0.1

Type RM Length L Ch R = 1 ,16004   ,451,451,451
BEGIN DESCRIPTION:
Stream0291 27.0
END DESCRIPTION:
XS GIS Cut Line= 3
      2393875.05     13721524.99        2394675.       13721375.
      2394975.01     13720624.97
#Sta/Elev= 30
  4190.8  388.36  4302.7  383.34  4379.8  373.55  4437.5  370.04    4485   365.3
  4535.9  363.35  4595.2  360.56  4600.3  359.33  4607.9  360.63  4631.9  360.18
  4652.8  360.98  4668.9  359.33  4699.5  361.26  4732.6  361.35  4798.1  361.67
  4953.8   362.4    4964   362.1  4972.3  357.58  4972.8  357.08  4984.6  357.58
  4994.5  360.72  5014.1   362.2  5058.5     362  5205.3  365.41  5259.1  366.13
  5342.6  364.42  5471.3  365.33  5546.9  367.01  5618.6  369.85  5812.5  373.78
#Mann= 9 ,-1 , 0
  4190.8     .07       0  4535.9     .05       0  4631.9     .07       0
  4732.6     .05       0  4798.1     .07       0  4972.3     .05       0
  4984.6     .07       0  5471.3    .035       0  5546.9     .07       0
Bank Sta=4972.3,4984.6
XS Rating Curve= 0 ,0
Exp/Cntr=0.3,0.1