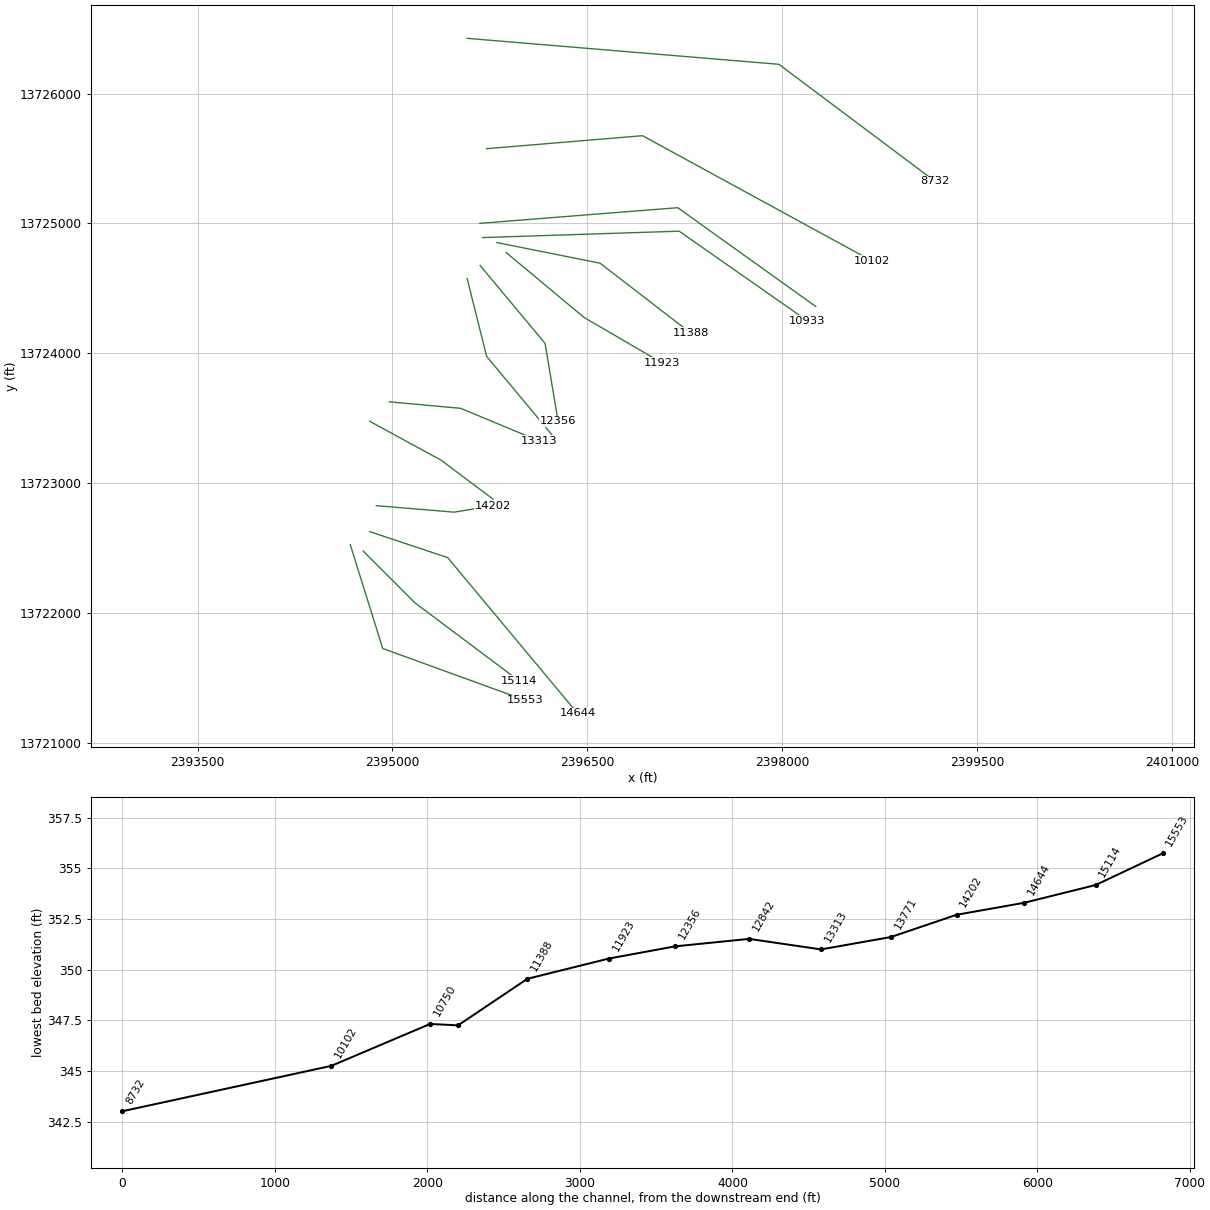
HEC-RAS study Stream0291.prj: Stream0291 Base Level Engineering

--- Stream0291.g01 (geometry) --- (continued)

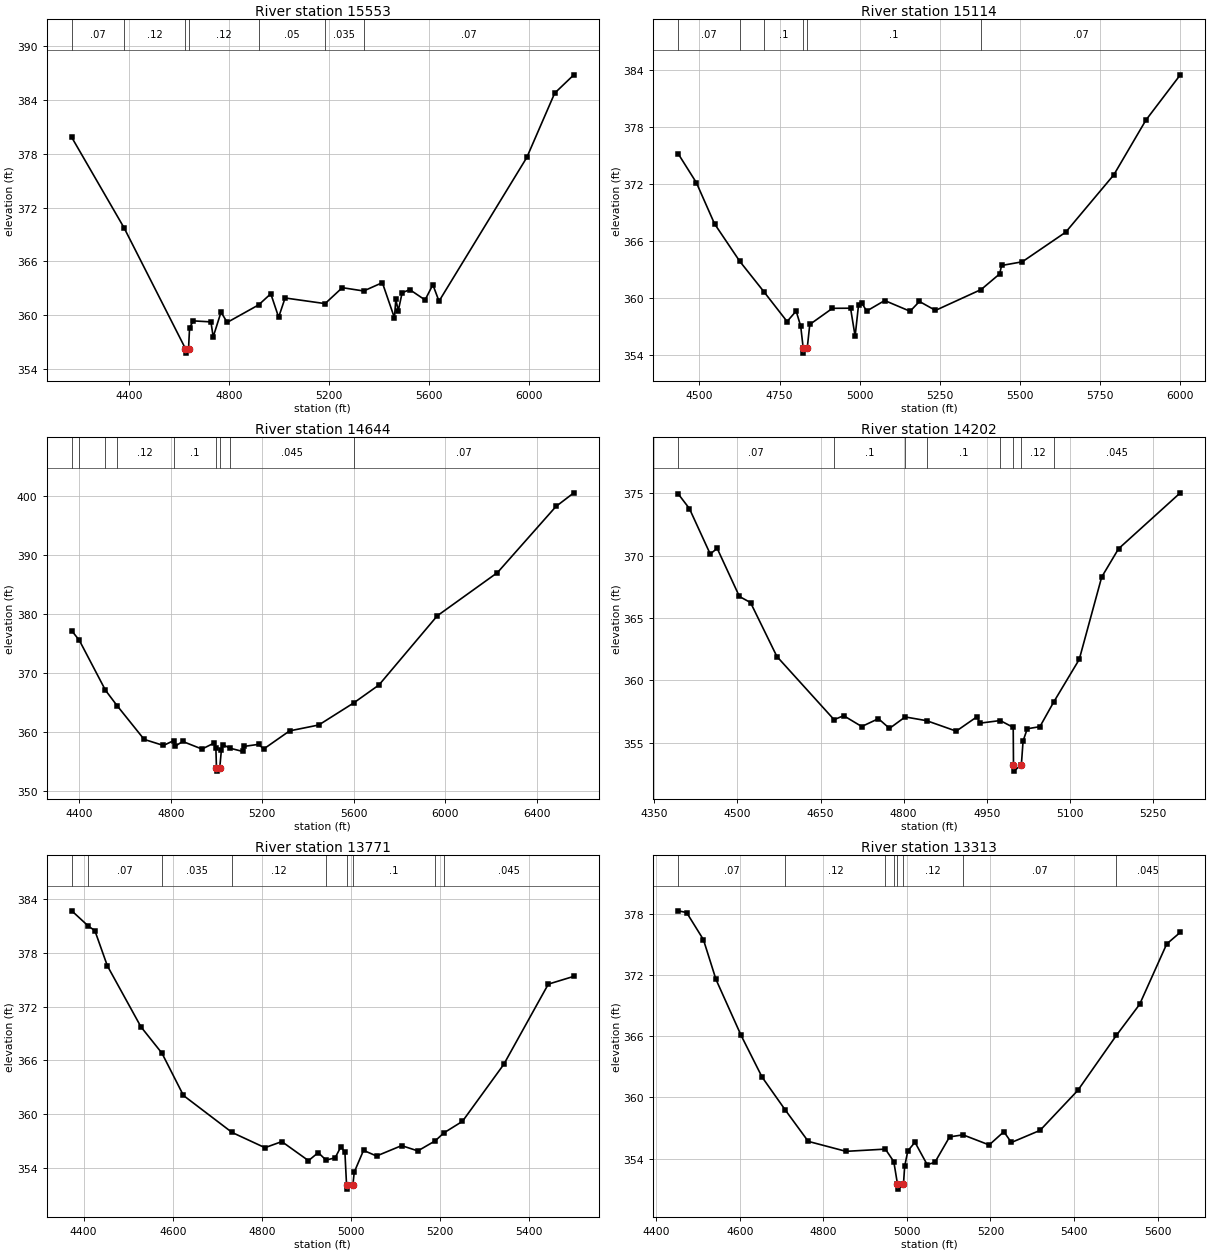
Type RM Length L Ch R = 1 ,15553   ,439,439,439
BEGIN DESCRIPTION:
Stream0291 26.0
END DESCRIPTION:
XS GIS Cut Line= 3
      2394675.01     13722524.96        2394925.       13721725.
      2396025.01       13721325.
#Sta/Elev= 30
  4169.5  379.83  4378.6  369.74  4624.3  356.24  4624.8  355.74  4636.6  356.24
  4640.9   358.6  4656.1  359.34  4726.3  359.23  4735.2  357.55  4766.6  360.32
  4791.3  359.17  4917.2  361.13  4965.7  362.37  4997.1  359.75  5022.9   361.9
  5182.9  361.27  5251.7  363.05  5337.2  362.68    5412  363.61  5460.5  359.67
  5465.8  361.73  5475.8  360.48  5491.1  362.48  5521.7  362.83  5582.9  361.68
  5614.1  363.38  5638.7  361.54  5989.9  377.59  6101.6  384.78  6178.1  386.82
#Mann= 7 ,-1 , 0
  4169.5     .07       0  4378.6     .12       0  4624.3     .05       0
  4636.6     .12       0  4917.2     .05       0  5182.9    .035       0
  5337.2     .07       0
Bank Sta=4624.3,4636.6
XS Rating Curve= 0 ,0
Exp/Cntr=0.3,0.1

Type RM Length L Ch R = 1 ,15114   ,470,470,470
BEGIN DESCRIPTION:
Stream0291 25.0
END DESCRIPTION:
XS GIS Cut Line= 3
      2394774.98     13722475.02        2395175.       13722075.
      2395974.99     13721475.01
#Sta/Elev= 30
    4434  375.17  4490.6  372.13  4547.2   367.8  4625.9  363.85  4700.6  360.67
  4773.4  357.51  4801.7  358.61  4815.9  357.02  4823.8  354.68  4824.3  354.18
  4836.2  354.68  4844.2   357.2  4914.9   358.9  4971.4  358.91  4985.6  355.96
  4996.2  359.23    5007  359.42  5021.6  358.61  5077.8  359.72    5157  358.59
  5186.2  359.62  5236.2  358.68  5378.7  360.88  5436.2  362.52  5442.4  363.41
    5507   363.8  5642.4  366.92  5792.4  372.96  5892.4  378.72  5999.7  383.49
#Mann= 6 ,-1 , 0
    4434     .07       0  4625.9     .12       0  4700.6      .1       0
  4823.8     .05       0  4836.2      .1       0  5378.7     .07       0
Bank Sta=4823.8,4836.2
XS Rating Curve= 0 ,0
Exp/Cntr=0.3,0.1

Type RM Length L Ch R = 1 ,14644   ,442,442,442
BEGIN DESCRIPTION:
Stream0291 24.0
END DESCRIPTION:
XS GIS Cut Line= 3
      2394824.98     13722625.01        2395425.       13722425.
      2396424.98     13721225.02
#Sta/Elev= 30
  4367.5  377.09  4400.8  375.45  4514.9     367  4565.5   364.4  4683.8  358.68
  4768.1  357.65  4812.4  358.46  4820.8  357.56  4852.4  358.33  4936.7  357.04
  4989.4  358.06  4997.3  357.28    5000   353.8  5000.5   353.3  5014.2   353.8
  5021.5  356.89    5028  357.78  5059.1  357.19  5113.9  356.64  5120.4  357.49
  5184.2  357.84  5206.3  357.05  5319.5  360.12  5447.1  361.12  5599.4  364.85
  5710.1   367.9  5965.2  379.63  6228.1  386.95  6483.9  398.16    6562  400.47
#Mann= 9 ,-1 , 0
  4367.5     .07       0  4400.8     .12       0  4514.9     .07       0
  4565.5     .12       0  4812.4      .1       0    5000     .05       0
  5014.2      .1       0  5059.1    .045       0  5599.4     .07       0
Bank Sta=5000,5014.2
XS Rating Curve= 0 ,0
Exp/Cntr=0.3,0.1

Type RM Length L Ch R = 1 ,14202   ,431,431,431
BEGIN DESCRIPTION:
Stream0291 23.0
END DESCRIPTION:
XS GIS Cut Line= 3
      2394874.97       13722825.        2395475.       13722775.
      2395774.95     13722824.99
#Sta/Elev= 30
  4393.2  374.96  4413.3  373.79  4450.9  370.14  4463.5  370.59  4503.6  366.73
  4523.7  366.24  4571.3  361.91  4674.5  356.84  4691.8  357.16  4724.4  356.29
  4754.5  356.92  4774.5  356.14  4802.8  357.06  4841.5  356.76    4895  355.92
  4932.6  357.08  4937.6  356.56  4974.4  356.77  4997.8  356.22  4998.3  353.21
  4998.8  352.71  5012.5  353.21  5015.6  355.13  5023.2  356.11    5046  356.28
  5070.8  358.25    5117  361.68  5157.5  368.29  5187.9  370.56  5299.4  375.05
#Mann= 8 ,-1 , 0
  4393.2     .07       0  4674.5      .1       0  4802.8     .12       0
  4841.5      .1       0  4974.4     .12       0  4998.3     .05       0
  5012.5     .12       0  5070.8    .045       0
Bank Sta=4998.3,5012.5
XS Rating Curve= 0 ,0
Exp/Cntr=0.3,0.1

Type RM Length L Ch R = 1 ,13771   ,458,458,458
BEGIN DESCRIPTION:
Stream0291 22.0
END DESCRIPTION:
XS GIS Cut Line= 3
      2394824.98     13723475.01        2395375.       13723175.
      2395774.98     13722875.01
#Sta/Elev= 30
  4373.5   382.7    4411  380.98  4425.3  380.49  4453.3  376.56  4528.7  369.74
  4575.8   366.8  4624.1  362.07  4733.2  357.94  4806.9  356.24  4844.8  356.92
  4904.6  354.79  4926.5  355.69  4944.1  354.85  4964.4  355.11  4977.2  356.33
  4986.3  355.76    4990  352.11  4990.5  351.61  5004.3  352.11  5007.3  353.51
  5028.1  355.94  5057.3  355.31  5113.6  356.47    5150  355.88  5188.8     357
  5208.6   357.9    5250  359.18  5342.7  365.54  5442.7  374.51    5500  375.38
#Mann= 9 ,-1 , 0
  4373.5    .045       0    4411     .07       0  4575.8    .035       0
  4733.2     .12       0  4944.1      .1       0    4990     .05       0
  5004.3      .1       0  5188.8     .12       0  5208.6    .045       0
Bank Sta=4990,5004.3
XS Rating Curve= 0 ,0
Exp/Cntr=0.3,0.1

Type RM Length L Ch R = 1 ,13313   ,471,471,471
BEGIN DESCRIPTION:
Stream0291 21.0
END DESCRIPTION:
XS GIS Cut Line= 3
      2394974.99       13723625.        2395525.       13723575.
      2396125.02     13723324.99
#Sta/Elev= 30
  4452.3  378.33  4472.4  378.16  4512.6   375.5  4542.7  371.59  4602.9  366.09
  4653.1     362    4709  358.75  4763.6  355.69    4854  354.71  4948.3  354.93
  4968.5   353.7  4977.3   351.5  4977.8     351  4991.7   351.5  4994.5  353.24
  5002.1  354.76  5019.2   355.6  5048.5   353.4  5066.9  353.63  5102.1  356.13
  5134.3  356.33  5196.9  355.34  5232.1  356.64    5250  355.58  5318.7  356.77
  5409.2   360.7  5501.7  366.11  5557.1  369.14  5622.1  375.08  5654.6  376.22
#Mann= 8 ,-1 , 0
  4452.3     .07       0    4709     .12       0  4948.3    .035       0
  4968.5     .12       0  4977.3     .05       0  4991.7     .12       0
  5134.3     .07       0  5501.7    .045       0
Bank Sta=4977.3,4991.7
XS Rating Curve= 0 ,0
Exp/Cntr=0.3,0.1

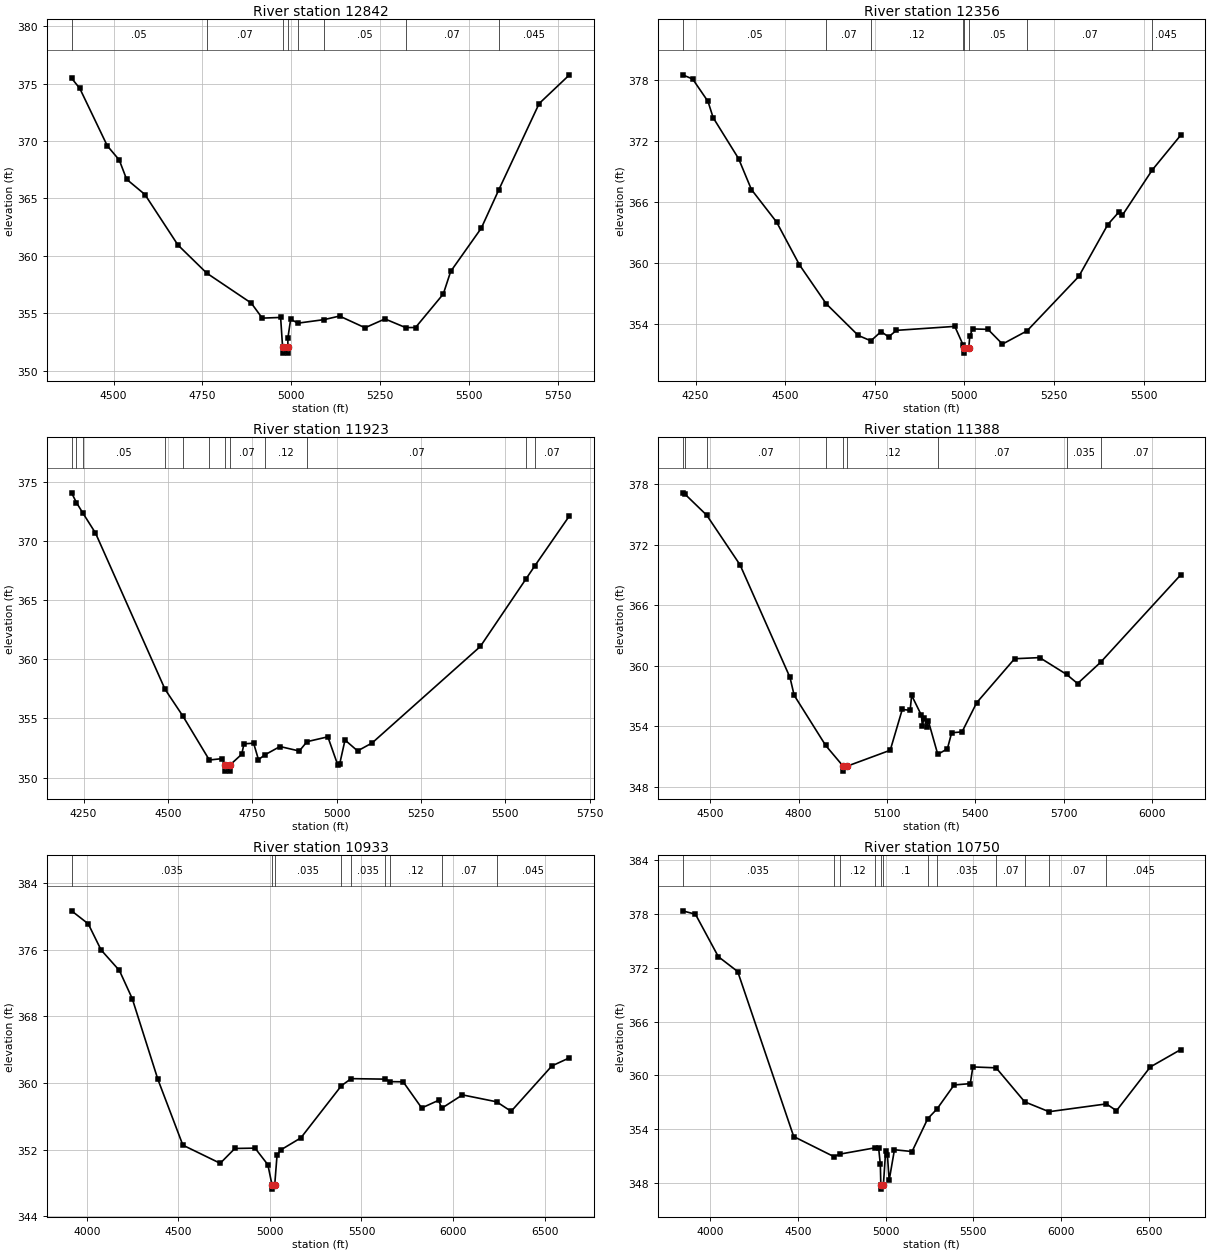
Type RM Length L Ch R = 1 ,12842   ,486,486,486
BEGIN DESCRIPTION:
Stream0291 20.0
END DESCRIPTION:
XS GIS Cut Line= 3
      2395574.99     13724575.04        2395725.       13723975.
      2396224.98     13723375.02
#Sta/Elev= 30
  4382.1  375.48  4405.3  374.58  4482.6  369.58  4516.1  368.35  4536.8  366.67
  4588.3  365.34  4681.1  360.94  4762.1  358.49  4887.2  355.88  4918.1  354.57
  4969.7  354.63  4975.3  352.02  4975.8  351.52  4989.3  351.52  4989.8  352.02
  4990.3  352.88    4998  354.48  5017.9  354.13    5092  354.44  5135.3  354.75
  5206.9  353.73  5262.9   354.5  5320.8  353.75  5348.8  353.75  5426.9  356.67
  5447.7  358.64  5533.7  362.41  5582.9  365.75  5696.4  373.27  5781.6  375.77
#Mann= 8 ,-1 , 0
  4382.1     .05       0  4762.1     .07       0  4975.3     .05       0
  4989.8     .07       0  5017.9     .12       0    5092     .05       0
  5320.8     .07       0  5582.9    .045       0
Bank Sta=4975.3,4989.8
XS Rating Curve= 0 ,0
Exp/Cntr=0.3,0.1

Type RM Length L Ch R = 1 ,12356   ,433,433,433
BEGIN DESCRIPTION:
Stream0291 19.0
END DESCRIPTION:
XS GIS Cut Line= 3
      2395675.01     13724674.99        2396175.       13724075.
        2396275.     13723474.98
#Sta/Elev= 30
  4213.7  378.52  4241.7  378.11  4284.6   375.9  4298.9  374.31  4369.9  370.28
  4405.7  367.24    4476  364.04  4539.8  359.83  4614.5     356  4703.8  352.89
    4739  352.36  4767.6  353.27  4788.4  352.75  4810.5  353.39  4973.2  353.78
  4996.8  351.92  4997.6  351.65  4998.1  351.15  5012.1  351.65    5015   352.8
  5022.6  353.53  5065.7  353.49  5106.2  352.04  5174.8  353.34  5319.1  358.69
  5400.2   363.8  5430.6  365.01  5440.8  364.71  5524.3  369.17    5603  372.56
#Mann= 8 ,-1 , 0
  4213.7     .05       0  4614.5     .07       0    4739     .12       0
  4996.8     .05       0  4997.6     .05       0  5012.1     .05       0
  5174.8     .07       0  5524.3    .045       0
Bank Sta=4997.6,5012.1
XS Rating Curve= 0 ,0
Exp/Cntr=0.3,0.1

Type RM Length L Ch R = 1 ,11923   ,535,535,535
BEGIN DESCRIPTION:
Stream0291 18.0
END DESCRIPTION:
XS GIS Cut Line= 3
        2395875.       13724775.        2396475.       13724275.
      2397074.96     13723925.02
#Sta/Elev= 30
  4214.3  374.08  4228.7  373.26  4246.9  372.41  4285.2  370.68  4491.3  357.47
  4544.1  355.21  4622.6  351.49  4661.4  351.61  4668.5  351.05    4669  350.55
  4682.6  350.55  4683.1  351.05  4718.7  351.98  4725.2  352.86  4753.9  352.91
  4768.2  351.52  4786.8  351.92    4832  352.63  4889.2  352.25    4912  353.04
  4973.8  353.45  5003.2  351.07    5009  351.17  5024.7  353.18  5061.9  352.26
  5104.9  352.93  5425.7  361.09  5561.7  366.83  5586.8  367.89  5689.9  372.14
#Mann= 12 ,-1 , 0
  4214.3     .05       0  4228.7     .07       0  4246.9     .05       0
  4491.3     .07       0  4544.1     .12       0  4622.6     .07       0
  4668.5     .05       0  4683.1     .07       0  4786.8     .12       0
    4912     .07       0  5561.7    .035       0  5586.8     .07       0
Bank Sta=4668.5,4683.1
XS Rating Curve= 0 ,0
Exp/Cntr=0.3,0.1

Type RM Length L Ch R = 1 ,11388   ,455,455,455
BEGIN DESCRIPTION:
XS6373
END DESCRIPTION:
XS GIS Cut Line= 3
      2395803.67     13724851.78      2396598.84     13724692.75
      2397295.28     13724155.34
#Sta/Elev= 30
  4406.3  377.13    4415  376.98  4488.3  374.91  4601.4  369.99    4771  358.83
    4785  357.07  4892.2  352.09  4951.1  350.05  4951.6  349.55  4965.7  350.05
  5111.3  351.62  5152.1  355.66  5178.9  355.58    5184  357.06  5217.2  355.08
  5220.2  354.06  5226.5  354.85  5234.7  353.97    5241  354.49  5272.7  351.21
  5305.3  351.76  5319.8  353.35  5355.1  353.44    5405  356.34  5533.6  360.69
  5618.7   360.8  5709.8  359.14  5747.4  358.23  5825.3  360.33  6096.9  368.98
#Mann= 9 ,-1 , 0
  4406.3    .035       0    4415     .05       0  4488.3     .07       0
  4892.2     .12       0  4951.1     .05       0  4965.7     .12       0
  5272.7     .07       0  5709.8    .035       0  5825.3     .07       0
Bank Sta=4951.1,4965.7
XS Rating Curve= 0 ,0
Exp/Cntr=0.3,0.1

Type RM Length L Ch R = 1 ,10933   ,183,183,183
BEGIN DESCRIPTION:
Stream0291 17.0
END DESCRIPTION:
XS GIS Cut Line= 3
      2395694.07     13724890.16      2397207.52     13724939.51
      2398193.59     13724249.26
#Sta/Elev= 30
  3917.4  380.65  4008.4  379.09  4078.4  375.96  4178.5  373.49  4248.5  370.12
  4388.6  360.42  4524.9  352.53  4728.8  350.35  4808.8  352.13  4918.9  352.17
  4988.9  350.18  5011.6  347.75  5012.1  347.25  5026.3  347.75  5038.9  351.29
  5058.9  351.95    5169   353.4  5390.3  359.66  5443.5  360.51  5629.1  360.45
  5657.1  360.15  5727.4  360.13  5828.6  356.99    5921  357.91  5937.3  356.95
  6051.1  358.56  6237.6  357.73  6316.8  356.59  6539.4  362.04  6635.3  363.01
#Mann= 9 ,-1 , 0
  3917.4    .035       0  5011.6    .035       0  5026.3    .035       0
  5390.3     .07       0  5443.5    .035       0  5629.1     .07       0
  5657.1     .12       0  5937.3     .07       0  6237.6    .045       0
Bank Sta=5011.6,5026.3
XS Rating Curve= 0 ,0
Exp/Cntr=0.3,0.1

Type RM Length L Ch R = 1 ,10750   ,648,648,648
BEGIN DESCRIPTION:
Stream0291 16.0
END DESCRIPTION:
XS GIS Cut Line= 3
      2395672.07     13724999.83      2397196.55     13725120.47
      2398258.95     13724359.26
#Sta/Elev= 30
  3843.6  378.34  3916.8  377.96  4047.2  373.23  4157.5  371.57  4476.5  353.18
  4704.7  350.95  4741.6  351.23  4938.6  351.92    4960  351.95    4970  350.07
  4972.7  347.82  4973.2  347.32  4987.4  347.82  5000.1  351.52  5010.2  351.13
  5020.2   348.3  5050.3  351.71  5150.6  351.51  5240.2  355.18  5292.6  356.25
  5390.1  358.93  5482.2  359.08    5497  360.94  5629.4  360.84  5792.2  357.05
  5930.8  355.95  6257.7  356.82    6315  356.06  6507.9  360.94  6679.8  362.86
#Mann= 12 ,-1 , 0
  3843.6    .035       0  4704.7     .07       0  4741.6     .12       0
  4938.6      .1       0  4972.7     .05       0  4987.4      .1       0
  5240.2     .07       0  5292.6    .035       0  5629.4     .07       0
  5792.2     .12       0  5930.8     .07       0  6257.7    .045       0
Bank Sta=4972.7,4987.4
XS Rating Curve= 0 ,0
Exp/Cntr=0.3,0.1

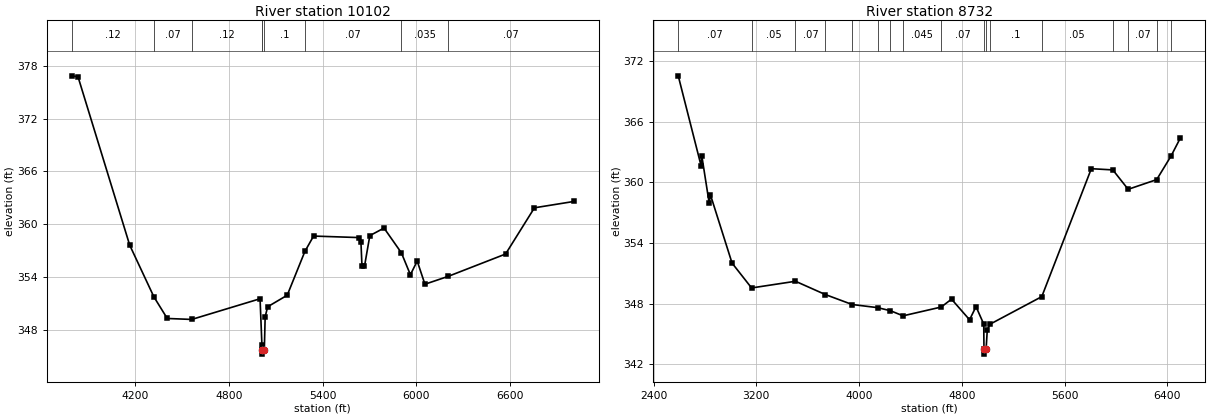
Type RM Length L Ch R = 1 ,10102   ,1370,1370,1370
BEGIN DESCRIPTION:
Stream0291 15.0
END DESCRIPTION:
XS GIS Cut Line= 3
      2395725.03       13725575.        2396925.       13725675.
      2398692.84      13724709.6
#Sta/Elev= 30
  3791.7  376.86  3831.8  376.75    4163  357.63  4318.3  351.75  4403.8   349.3
  4560.6  349.19  4998.7  351.54  5010.7  346.23  5011.3  345.75  5011.8  345.25
    5026  345.75  5031.4   349.5  5047.5  350.63  5172.8  351.94  5286.2  356.92
  5341.7  358.66  5630.2  358.49  5645.3  357.97    5652  355.27  5668.1  355.23
  5702.3  358.71  5793.4  359.57  5904.5  356.76  5962.3  354.27    6006  355.82
  6055.5  353.19  6204.2  354.08  6572.5  356.62  6757.5  361.87  7010.1  362.59
#Mann= 9 ,-1 , 0
  3791.7     .12       0  4318.3     .07       0  4560.6     .12       0
  5010.7      .1       0  5011.3     .05       0    5026      .1       0
  5286.2     .07       0  5904.5    .035       0  6204.2     .07       0
Bank Sta=5011.3,5026
XS Rating Curve= 0 ,0
Exp/Cntr=0.3,0.1

Type RM Length L Ch R = 1 ,8732    ,1218,1218,1218
BEGIN DESCRIPTION:
Stream0291 14.0
END DESCRIPTION:
XS GIS Cut Line= 3
      2395575.03       13726425.        2397975.       13726225.
      2399175.01       13725325.
#Sta/Elev= 30
    2592  370.55  2770.1  361.64  2775.1  362.66  2832.8  357.97  2842.8  358.77
  3010.9  352.02  3162.9  349.56  3504.7  350.22  3736.2  348.91  3945.9  347.92
    4144  347.61    4243  347.31    4342   346.8  4639.1  347.67  4719.3  348.45
  4859.8  346.41    4910  347.71  4970.2  345.98  4971.9  343.51  4972.4  343.01
  4988.5  343.51  4997.8  345.43  5020.3  345.98    5422   348.7  5807.6  361.36
  5974.9  361.24  6094.4  359.32  6316.4  360.28  6428.4  362.62  6500.3  364.39
#Mann= 17 ,-1 , 0
    2592     .07       0  3162.9     .05       0  3504.7     .07       0
  3736.2    .035       0  3945.9     .07       0    4144     .05       0
    4243     .07       0    4342    .045       0  4639.1     .07       0
  4971.9     .05       0  4988.5     .07       0  5020.3      .1       0
    5422     .05       0  5974.9    .035       0  6094.4     .07       0
  6316.4    .035       0  6428.4     .07       0
Bank Sta=4971.9,4988.5
XS Rating Curve= 0 ,0
Exp/Cntr=0.3,0.1