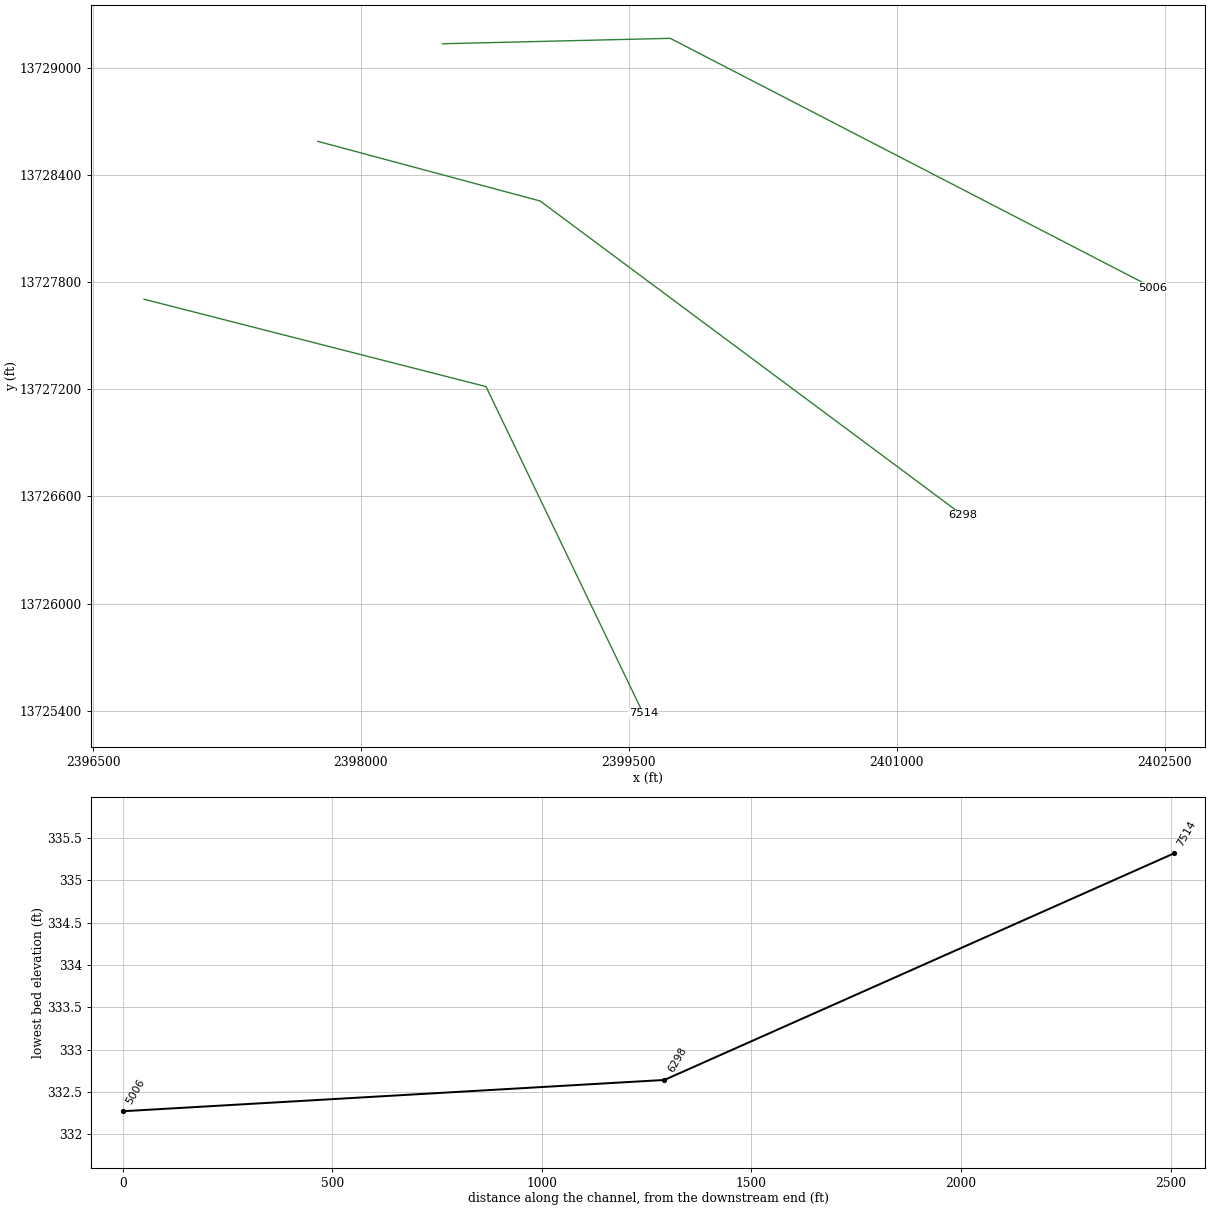
HEC-RAS study Stream0291.prj: Stream0291 Base Level Engineering

--- Stream0291.g01 (geometry) --- (continued)

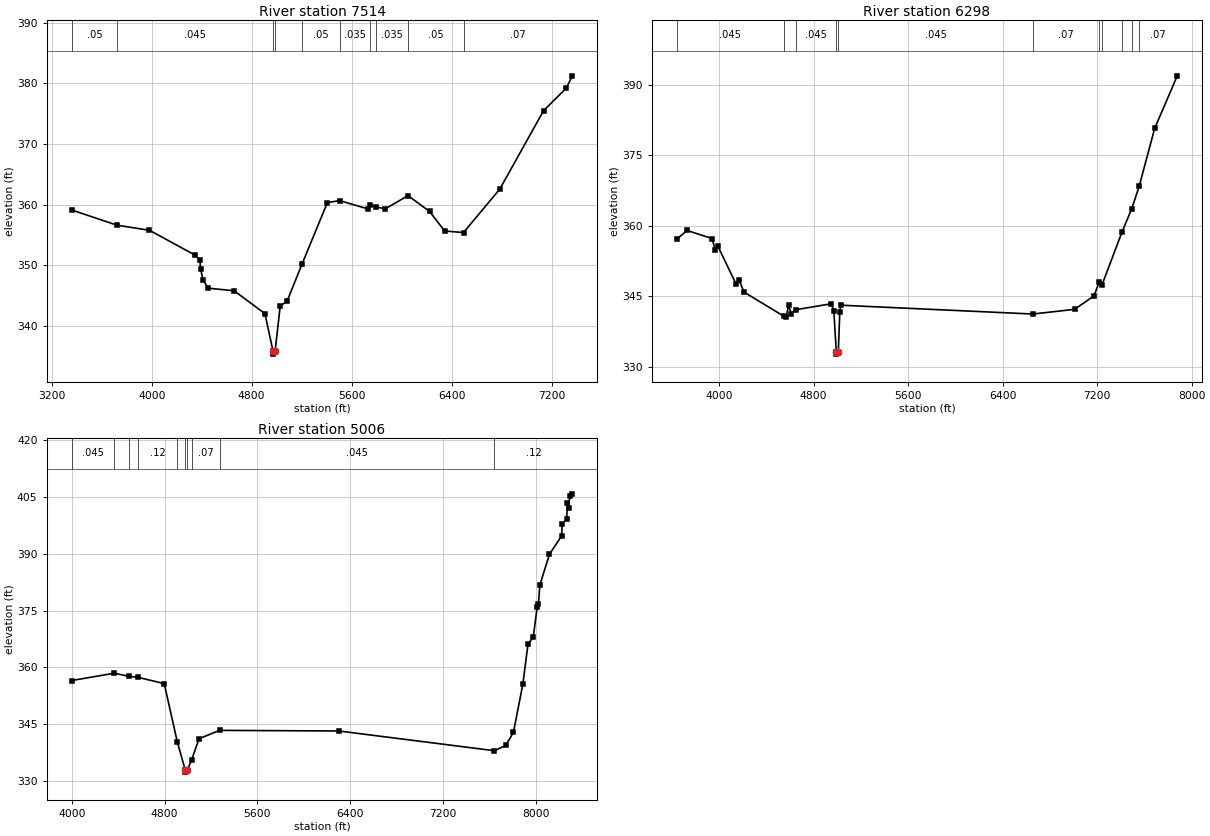
Type RM Length L Ch R = 1 ,7514    ,1216,1216,1216
BEGIN DESCRIPTION:
XS6372
END DESCRIPTION:
XS GIS Cut Line= 3
      2396785.81     13727703.75       2398700.7     13727214.55
      2399580.64     13725384.83
#Sta/Elev= 30
  3359.8   359.1  3722.3  356.59  3982.2  355.75  4344.6  351.68  4385.4  350.86
  4391.1   349.4  4411.7  347.51    4453   346.2  4659.4  345.77  4906.1  342.01
  4970.9  335.82  4971.4  335.32  4987.8  335.82  5028.6  343.29  5082.6  344.01
  5202.2  350.13  5405.8  360.31  5503.2  360.65  5728.2  359.29  5744.9  359.97
  5798.1   359.6  5869.6  359.28  6051.1  361.47  6223.4  358.86  6344.9  355.63
  6495.4  355.38    6786  362.55  7136.6   375.5  7317.6   379.2  7366.5  381.23
#Mann= 10 ,-1 , 0
  3359.8     .05       0  3722.3    .045       0  4970.9    .045       0
  4987.8    .045       0  5202.2     .05       0  5503.2    .035       0
  5744.9     .05       0  5798.1    .035       0  6051.1     .05       0
  6495.4     .07       0
Bank Sta=4970.9,4987.8
XS Rating Curve= 0 ,0
Exp/Cntr=0.3,0.1

Type RM Length L Ch R = 1 ,6298    ,1292,1292,1292
BEGIN DESCRIPTION:
XS6371
END DESCRIPTION:
XS GIS Cut Line= 3
       2397759.1     13728587.77      2399003.84     13728253.81
      2401370.89     13726493.69
#Sta/Elev= 30
  3639.8  357.12  3728.7     359  3940.5  357.27  3966.9   354.8  3987.6  355.75
  4142.9  347.59  4170.1  348.38  4210.1  345.87  4549.2  340.69  4567.4  340.57
  4588.1  343.13  4608.8  341.28  4651.9  342.12  4950.2  343.38    4971  341.75
  4991.8  333.14  4992.3  332.64  5008.8  333.14  5021.1  341.52  5029.5  343.07
    6656  341.19    7009  342.19  7173.1  345.04  7216.5  347.95  7239.3  347.28
  7411.6  358.74  7492.6  363.62  7556.2  368.46  7686.8  380.75  7878.3  391.97
#Mann= 11 ,-1 , 0
  3639.8    .045       0  4549.2    .035       0  4651.9    .045       0
  4991.8    .045       0  5008.8    .045       0    6656     .07       0
  7216.5    .045       0  7239.3     .12       0  7411.6     .07       0
  7492.6     .12       0  7556.2     .07       0
Bank Sta=4991.8,5008.8
XS Rating Curve= 0 ,0
Exp/Cntr=0.3,0.1

Type RM Length L Ch R = 1 ,5006    ,0,0,0
BEGIN DESCRIPTION:
XS6370
END DESCRIPTION:
XS GIS Cut Line= 3
      2398457.33     13729134.22      2399732.45     13729164.58
      2402434.41     13727768.06
#Sta/Elev= 30
  3999.5  356.49    4368  358.43  4493.6  357.59  4570.5  357.34  4797.4  355.67
  4909.9  340.27  4978.9  332.77  4979.4  332.27    4996  332.77  5034.1  335.55
  5097.5  341.12  5275.5  343.31  6302.2  343.15  7644.9  337.93  7741.7  339.32
  7808.2  342.76  7889.4  355.51  7934.4  366.19  7979.5  367.94  8013.2  375.95
    8024  376.64  8035.8  381.67  8118.2  389.82  8223.3  394.71    8229  397.98
  8267.6  399.08  8273.2  403.37  8283.4  402.03  8295.4   405.4  8316.5  405.85
#Mann= 10 ,-1 , 0
  3999.5    .045       0    4368    .035       0  4493.6    .045       0
  4570.5     .12       0  4909.9      .1       0  4978.9     .05       0
    4996      .1       0  5034.1     .07       0  5275.5    .045       0
  7644.9     .12       0
Bank Sta=4978.9,4996
XS Rating Curve= 0 ,0
Exp/Cntr=0.3,0.1

Chan Stop Cuts=-1
Use User Specified Reach Order=0
Composite Channel Slope=5