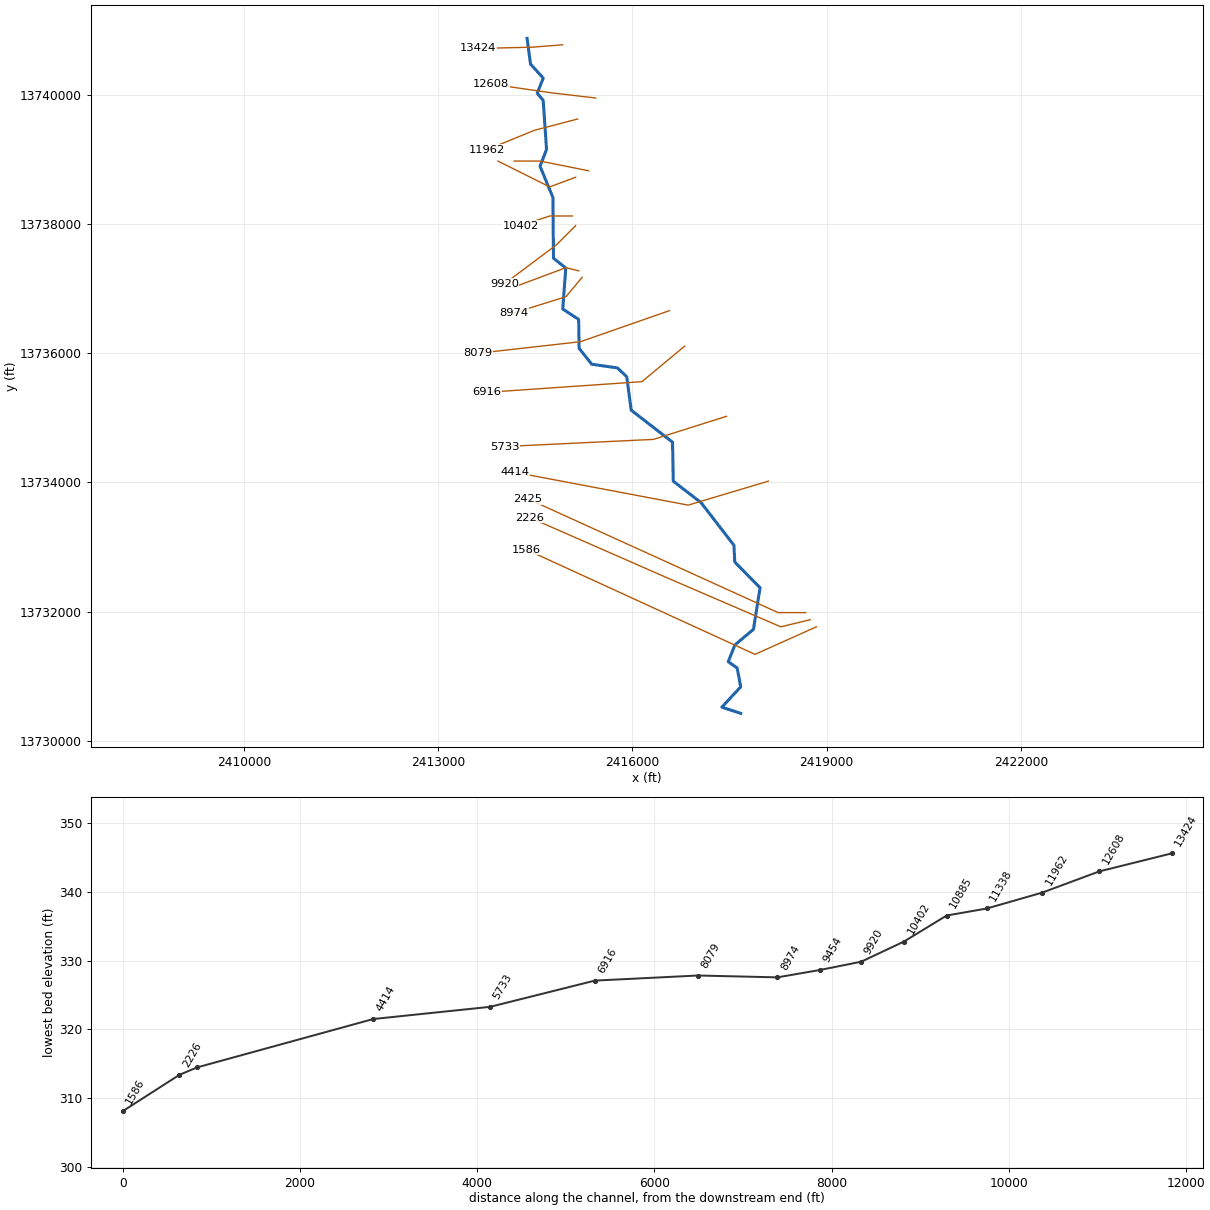
--- Stream0292.prj (project) ---

Proj Title=Stream0292 Base Level Engineering
Current Plan=p01
Default Exp/Contr=0.3,0.1
English Units
Geom File=g01
Flow File=f01
Plan File=p01
BEGIN DESCRIPTION:
Stream0292
END DESCRIPTION:

--- Stream0292.p01 (plan) ---

Plan Title=Multiple Run
Short Identifier=Multiple
Geom File=g01
Flow File=f01
Subcritical Flow
K Sum by GR= 0
Std Step Tol= 0.01
Critical Tol= 0.01
Num of Std Step Trials= 20
Max Error Tol= 0.3
Flow Tol Ratio= 0.001
Split Flow NTrial= 30
Split Flow Tol= 0.02
Split Flow Ratio= 0.02
Log Output Level= 0
Friction Slope Method= 1
Unsteady Friction Slope Method= 2
Unsteady Bridges Friction Slope Method= 1
Parabolic Critical Depth
Global Vel Dist=  1 , 1 , 1
Global Log Level= 0
CheckData=True
Encroach Param= -1, 0, 0, 0
BEGIN DESCRIPTION:
Multiple Run
END DESCRIPTION:

--- Stream0292.f01 (steady flow) ---

Flow Title=Multiple
Number of Profiles=7
Profile Names=10-year,25-year,50-year,1pct_min,100-year,1pct_plu,500-year
River Rch & RM= Stream0292,Reach-1,13424
     737    1204    1630    1070    2135    4259    3624
River Rch & RM= Stream0292,Reach-1,11962
    1033    1706    2326    1533    3059    6104    5246
River Rch & RM= Stream0292,Reach-1,6916
    1198    1978    2697    1775    3541    7066    6056
Boundary for River Rch & Prof#=Stream0292,Reach-1,1
Up Type=0
Dn Type=3
Dn Slope=0.005
Boundary for River Rch & Prof#=Stream0292,Reach-1,2
Up Type=0
Dn Type=3
Dn Slope=0.005
Boundary for River Rch & Prof#=Stream0292,Reach-1,3
Up Type=0
Dn Type=3
Dn Slope=0.005
Boundary for River Rch & Prof#=Stream0292,Reach-1,4
Up Type=0
Dn Type=3
Dn Slope=0.005
Boundary for River Rch & Prof#=Stream0292,Reach-1,5
Up Type=0
Dn Type=3
Dn Slope=0.005
Boundary for River Rch & Prof#=Stream0292,Reach-1,6
Up Type=0
Dn Type=3
Dn Slope=0.005
Boundary for River Rch & Prof#=Stream0292,Reach-1,7
Up Type=0
Dn Type=3
Dn Slope=0.005

--- Stream0292.g01 (geometry) ---

Geom Title=Existing Conditions

River Reach=Stream0292,Reach-1
Reach XY= 30
      2414375.00     13740875.00      2414428.52     13740476.28
      2414624.51     13740259.78      2414532.10     13740025.00
      2414623.94     13739914.57      2414675.78     13739154.67
      2414575.07     13738895.03      2414774.62     13738409.73
      2414782.69     13737471.33      2414972.95     13737319.16
      2414926.03     13736685.43      2415171.49     13736523.75
      2415178.75     13736076.55      2415372.55     13735830.46
      2415773.35     13735771.84      2415914.52     13735634.80
      2415982.86     13735118.83      2416621.54     13734623.50
      2416633.13     13734018.93      2417061.37     13733688.21
      2417569.54     13733027.45      2417582.69     13732768.52
      2417972.94     13732369.14      2417871.87     13731726.63
      2417585.51     13731484.81      2417482.20     13731224.70
      2417619.64     13731127.70      2417674.47     13730835.45
      2417382.48     13730521.38      2417675.00     13730425.00

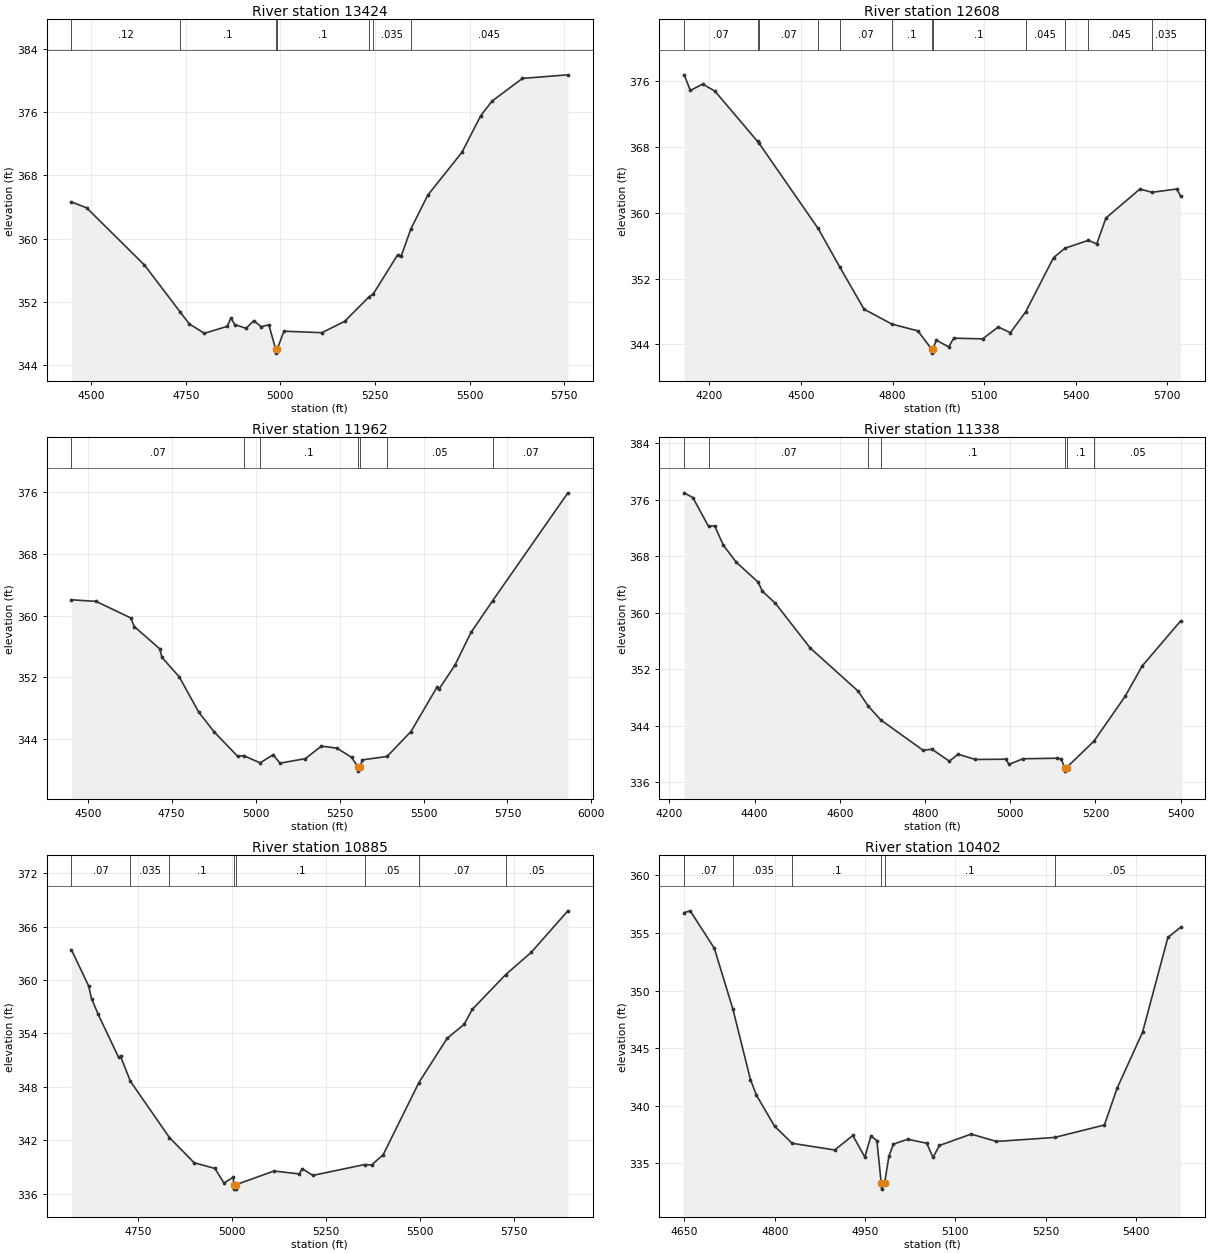
Type RM Length L Ch R = 1,13424,816,816,816
BEGIN DESCRIPTION:
Stream0292 27.0
END DESCRIPTION:
XS GIS Cut Line= 3
      2414924.99     13740775.00      2414453.59     13740737.73
      2413614.99     13740718.22
#Sta/Elev= 30
  4448.1  364.64  4488.2  363.90  4641.0  356.68  4735.2  350.76  4759.1  349.26
  4799.2  348.06  4859.4  348.94  4869.4  350.00  4879.4  349.17  4909.5  348.69
  4929.6  349.66  4949.6  348.89  4969.6  349.14  4987.6  346.06  4987.8  345.56
  4991.6  346.06  5009.6  348.33  5109.6  348.14  5169.6  349.56  5235.1  352.70
  5244.7  352.97  5309.7  357.95  5319.7  357.87  5345.1  361.26  5389.7  365.51
  5479.7  370.90  5529.7  375.55  5559.7  377.39  5639.8  380.24  5759.8  380.69
#Mann=7,-1,0
  4448.1    0.12       0  4735.2     0.1       0  4987.6    0.05       0
  4991.6     0.1       0  5235.1   0.045       0  5244.7   0.035       0
  5345.1   0.045       0
Bank Sta=4987.6,4991.6
Exp/Cntr=0.3,0.1

Type RM Length L Ch R = 1,12608,646,646,646
BEGIN DESCRIPTION:
Stream0292 26.0
END DESCRIPTION:
XS GIS Cut Line= 3
      2415435.14     13739951.16      2414772.12     13740029.16
      2413822.98     13740165.68
#Sta/Elev= 30
  4117.2  376.74  4137.5  374.84  4177.8  375.62  4218.0  374.76  4357.7  368.65
  4362.1  368.45  4555.8  358.10  4627.4  353.38  4706.4  348.29  4797.4  346.48
  4882.9  345.65  4927.7  343.45  4928.0  342.95  4931.8  343.45  4943.5  344.52
  4983.9  343.70  5000.3  344.77  5095.1  344.68  5146.3  346.13  5186.0  345.43
  5235.9  347.95  5327.4  354.54  5365.0  355.69  5441.6  356.65  5468.9  356.21
  5499.2  359.36  5610.3  362.87  5650.4  362.48  5731.6  362.88  5743.7  362.00
#Mann=12,-1,0
  4117.2    0.07       0  4357.7    0.12       0  4362.1    0.07       0
  4555.8    0.12       0  4627.4    0.07       0  4797.4     0.1       0
  4927.7    0.05       0  4931.8     0.1       0  5235.9   0.045       0
  5365.0   0.035       0  5441.6   0.045       0  5650.4   0.035       0
Bank Sta=4927.7,4931.8
Exp/Cntr=0.3,0.1

Type RM Length L Ch R = 1,11962,624,624,624
BEGIN DESCRIPTION:
Stream0292 25.0
END DESCRIPTION:
XS GIS Cut Line= 3
      2415155.69     13739626.13      2414486.09     13739450.60
      2413759.05     13739152.00
#Sta/Elev= 30
  4451.7  362.04  4524.8  361.84  4628.2  359.69  4638.6  358.58  4714.3  355.70
  4721.2  354.58  4772.9  352.05  4830.3  347.52  4876.3  344.95  4946.3  341.79
  4965.0  341.86  5013.5  340.93  5052.0  341.98  5072.7  340.89  5148.0  341.48
  5196.0  343.10  5242.4  342.83  5285.6  341.65  5305.7  340.36  5306.0  339.86
  5310.5  340.36  5318.1  341.32  5391.5  341.76  5462.7  344.99  5540.0  350.72
  5545.4  350.43  5593.4  353.57  5641.3  357.81  5706.3  361.95  5929.9  375.89
#Mann=7,-1,0
  4451.7    0.07       0  4965.0   0.035       0  5013.5     0.1       0
  5305.7   0.035       0  5310.5     0.1       0  5391.5    0.05       0
  5706.3    0.07       0
Bank Sta=5305.7,5310.5
Exp/Cntr=0.3,0.1

Type RM Length L Ch R = 1,11338,453,453,453
BEGIN DESCRIPTION:
Stream0292 24.0
END DESCRIPTION:
XS GIS Cut Line= 3
      2415324.99     13738825.00      2414575.00     13738975.00
      2414175.04     13738975.00
#Sta/Elev= 30
  4235.0  376.98  4255.4  376.30  4292.2  372.22  4306.4  372.31  4326.8  369.57
  4357.4  367.14  4408.4  364.34  4418.6  363.04  4449.2  361.32  4530.7  355.00
  4642.9  348.91  4666.8  346.78  4696.1  344.82  4795.9  340.50  4816.3  340.67
  4857.1  338.97  4877.5  339.95  4918.3  339.21  4989.6  339.25  4997.3  338.52
  5029.8  339.31  5109.8  339.39  5119.8  339.28  5127.4  338.06  5127.7  337.56
  5132.3  338.06  5196.7  341.82  5269.8  348.17  5309.8  352.46  5399.8  358.83
#Mann=7,-1,0
  4235.0   0.035       0  4292.2    0.07       0  4666.8   0.035       0
  4696.1     0.1       0  5127.4    0.05       0  5132.3     0.1       0
  5196.7    0.05       0
Bank Sta=5127.4,5132.3
Exp/Cntr=0.3,0.1

Type RM Length L Ch R = 1,10885,483,483,483
BEGIN DESCRIPTION:
Stream0292 23.0
END DESCRIPTION:
XS GIS Cut Line= 3
      2415125.04     13738725.01      2414725.00     13738575.00
      2413924.97     13738975.01
#Sta/Elev= 30
  4573.1  363.38  4618.5  359.36  4626.5  357.92  4643.5  356.21  4698.6  351.32
  4704.0  351.42  4729.8  348.65  4833.8  342.33  4899.8  339.50  4955.0  338.86
  4979.0  337.22  5003.1  337.86  5006.3  337.04  5006.6  336.54  5010.8  336.54
  5011.2  337.04  5112.1  338.57  5179.2  338.25  5187.6  338.83  5215.6  338.08
  5354.0  339.30  5372.1  339.25  5402.8  340.39  5498.2  348.50  5573.3  353.46
  5618.1  355.01  5640.4  356.71  5729.0  360.60  5796.9  363.09  5894.8  367.76
#Mann=8,-1,0
  4573.1    0.07       0  4729.8   0.035       0  4833.8     0.1       0
  5006.3    0.05       0  5011.2     0.1       0  5354.0    0.05       0
  5498.2    0.07       0  5729.0    0.05       0
Bank Sta=5006.3,5011.2
Exp/Cntr=0.3,0.1

Type RM Length L Ch R = 1,10402,482,482,482
BEGIN DESCRIPTION:
Stream0292 22.0
END DESCRIPTION:
XS GIS Cut Line= 3
      2415074.97     13738125.00      2414725.00     13738125.00
      2414275.01     13737975.00
#Sta/Elev= 30
  4649.6  356.76  4659.6  356.92  4699.6  353.67  4730.5  348.38  4759.6  342.27
  4769.6  340.91  4799.6  338.22  4829.0  336.73  4899.6  336.15  4929.6  337.41
  4949.6  335.53  4959.6  337.36  4969.6  336.97  4976.8  333.25  4977.3  332.75
  4982.3  333.25  4989.6  335.62  4997.1  336.66  5020.7  337.08  5052.3  336.74
  5062.8  335.50  5073.4  336.54  5126.1  337.53  5168.2  336.89  5264.9  337.24
  5347.4  338.32  5368.5  341.52  5410.7  346.37  5452.8  354.61  5473.9  355.49
#Mann=6,-1,0
  4649.6    0.07       0  4730.5   0.035       0  4829.0     0.1       0
  4976.8    0.05       0  4982.3     0.1       0  5264.9    0.05       0
Bank Sta=4976.8,4982.3
Exp/Cntr=0.3,0.1

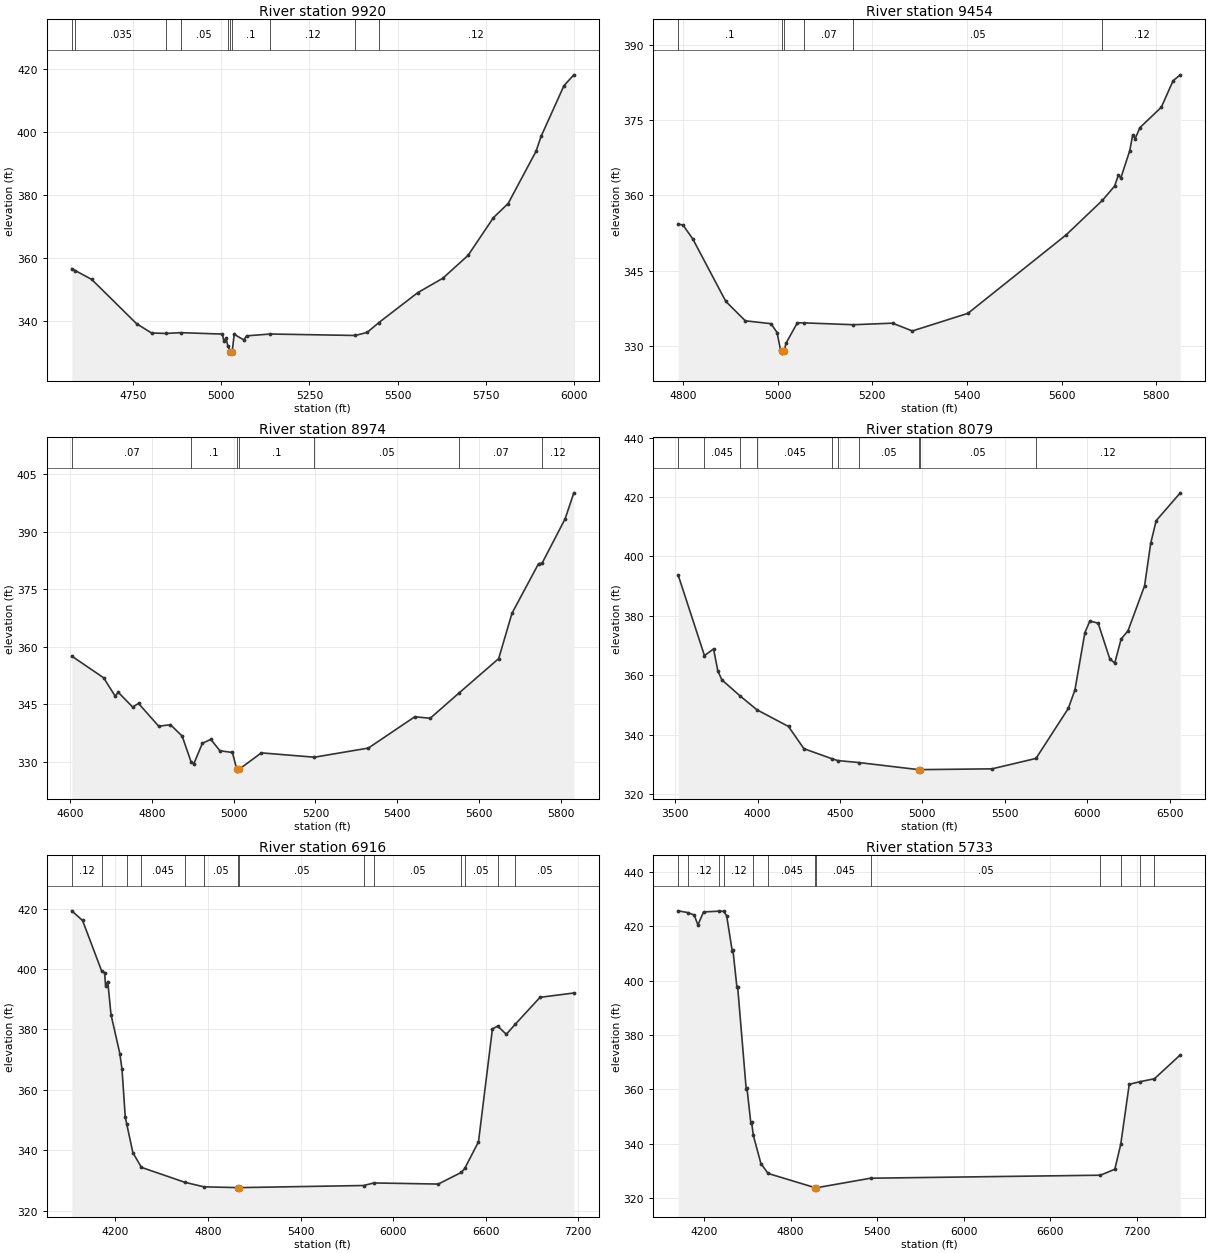
Type RM Length L Ch R = 1,9920,466,466,466
BEGIN DESCRIPTION:
Stream0292 21.0
END DESCRIPTION:
XS GIS Cut Line= 3
      2415124.98     13737974.98      2414825.00     13737675.00
      2414025.02     13737075.02
#Sta/Elev= 30
  4575.8  356.65  4586.1  356.03  4632.3  353.24  4759.6  339.18  4802.0  336.23
  4842.4  336.08  4885.2  336.33  5003.2  335.88  5007.3  333.57  5013.6  334.57
  5018.3  332.19  5025.4  330.33  5025.9  329.83  5030.9  330.33  5036.5  335.81
  5063.6  334.04  5071.9  335.32  5138.7  335.90  5379.7  335.44  5413.6  336.40
  5446.9  339.53  5557.3  349.04  5628.2  353.60  5700.0  360.88  5771.9  372.86
  5813.6  377.35  5892.7  393.93  5907.3  398.73  5971.9  414.77  6000.0  418.22
#Mann=10,-1,0
  4575.8    0.07       0  4586.1   0.035       0  4842.4    0.07       0
  4885.2    0.05       0  5018.3     0.1       0  5025.4    0.05       0
  5030.9     0.1       0  5138.7    0.12       0  5379.7    0.05       0
  5446.9    0.12       0
Bank Sta=5025.4,5030.9
Exp/Cntr=0.3,0.1

Type RM Length L Ch R = 1,9454,480,480,480
BEGIN DESCRIPTION:
Stream0292 20.0
END DESCRIPTION:
XS GIS Cut Line= 3
      2415175.02     13737275.00      2414975.00     13737325.00
      2414174.97     13737024.99
#Sta/Elev= 30
  4790.0  354.33  4800.3  354.08  4820.9  351.32  4890.5  338.92  4931.7  335.06
  4985.9  334.49  4998.8  332.73  5006.0  329.29  5008.5  329.13  5008.9  328.63
  5014.2  329.13  5017.5  330.56  5041.6  334.67  5055.7  334.65  5159.8  334.28
  5242.7  334.59  5284.5  333.04  5402.0  336.55  5609.4  352.15  5686.1  359.03
  5711.7  361.85  5719.7  364.01  5725.1  363.52  5743.8  368.91  5750.0  372.01
  5755.3  371.29  5765.1  373.47  5810.5  377.55  5835.4  382.83  5850.6  383.99
#Mann=6,-1,0
  4790.0     0.1       0  5008.5    0.05       0  5014.2     0.1       0
  5055.7    0.07       0  5159.8    0.05       0  5686.1    0.12       0
Bank Sta=5008.5,5014.2
Exp/Cntr=0.3,0.1

Type RM Length L Ch R = 1,8974,895,895,895
BEGIN DESCRIPTION:
Stream0292 19.0
END DESCRIPTION:
XS GIS Cut Line= 3
      2415225.01     13737175.01      2414975.00     13736875.00
      2414174.98     13736624.99
#Sta/Elev= 30
  4603.8  357.54  4681.9  351.88  4709.9  347.12  4717.7  348.10  4752.9  344.25
  4767.2  345.21  4816.6  339.26  4845.3  339.66  4873.9  336.71  4896.3  329.82
  4902.6  329.49  4923.4  334.82  4944.2  335.83  4966.3  332.87  4996.9  332.42
  5007.6  328.06  5008.1  327.56  5013.5  328.06  5067.7  332.32  5197.5  331.19
  5329.6  333.57  5443.3  341.73  5481.0  341.34  5550.5  347.83  5648.6  356.90
  5681.1  368.71  5746.0  381.61  5755.0  381.81  5811.0  393.29  5832.5  400.10
#Mann=7,-1,0
  4603.8    0.07       0  4896.3     0.1       0  5007.6    0.05       0
  5013.5     0.1       0  5197.5    0.05       0  5550.5    0.07       0
  5755.0    0.12       0
Bank Sta=5007.6,5013.5
Exp/Cntr=0.3,0.1

Type RM Length L Ch R = 1,8079,1163,1163,1163
BEGIN DESCRIPTION:
XS6382
END DESCRIPTION:
XS GIS Cut Line= 3
      2416574.96     13736659.99      2415200.00     13736178.75
      2413619.41     13736000.07
#Sta/Elev= 30
  3518.0  393.69  3677.1  366.68  3732.5  368.92  3758.2  361.54  3782.8  358.52
  3892.7  353.15  3996.0  348.44  4187.3  342.84  4280.8  335.37  4453.1  331.96
  4486.7  331.38  4613.3  330.72  4976.8  328.33  4977.3  327.83  4982.8  328.33
  5422.6  328.60  5689.4  332.10  5885.5  348.91  5925.8  355.12  5986.1  374.36
  6016.3  378.30  6066.7  377.58  6137.1  365.62  6167.3  364.15  6206.2  372.24
  6247.8  375.00  6348.4  390.12  6385.8  404.46  6418.9  412.05  6565.4  421.40
#Mann=10,-1,0
  3518.0    0.12       0  3677.1   0.045       0  3892.7   0.035       0
  3996.0   0.045       0  4453.1    0.05       0  4486.7   0.045       0
  4613.3    0.05       0  4976.8    0.05       0  4982.8    0.05       0
  5689.4    0.12       0
Bank Sta=4976.8,4982.8
Exp/Cntr=0.3,0.1

Type RM Length L Ch R = 1,6916,1183,1183,1183
BEGIN DESCRIPTION:
XS6381
END DESCRIPTION:
XS GIS Cut Line= 3
      2416808.75     13736110.00      2416148.75     13735560.00
      2413758.15     13735395.13
#Sta/Elev= 30
  3916.8  419.31  3986.8  416.11  4109.9  399.46  4129.5  398.85  4136.0  394.47
  4150.3  395.86  4171.1  384.95  4228.4  372.02  4242.7  366.74  4263.5  351.06
  4272.5  348.82  4313.0  339.18  4368.1  334.31  4648.0  329.39  4773.1  327.85
  4997.0  327.59  4997.5  327.09  5003.5  327.59  5809.0  328.29  5875.7  329.14
  6293.3  328.77  6443.3  332.65  6464.9  333.96  6553.9  342.77  6644.1  380.13
  6678.2  381.13  6734.3  378.39  6791.5  381.68  6953.0  390.65  7172.2  392.08
#Mann=14,-1,0
  3916.8    0.12       0  4109.9    0.07       0  4272.5    0.12       0
  4368.1   0.045       0  4648.0   0.035       0  4773.1    0.05       0
  4997.0    0.05       0  5003.5    0.05       0  5809.0    0.07       0
  5875.7    0.05       0  6443.3    0.12       0  6464.9    0.05       0
  6678.2    0.12       0  6791.5    0.05       0
Bank Sta=4997,5003.5
Exp/Cntr=0.3,0.1

Type RM Length L Ch R = 1,5733,1319,1319,1319
BEGIN DESCRIPTION:
XS6380
END DESCRIPTION:
XS GIS Cut Line= 3
      2417455.03     13735023.76      2416327.50     13734666.25
      2414031.28     13734556.25
#Sta/Elev= 30
  4021.3  425.74  4087.8  425.09  4132.2  424.20  4157.7  420.53  4196.8  425.33
  4304.1  425.62  4335.9  425.56  4357.0  423.95  4395.7  410.97  4401.0  411.14
  4428.0  397.74  4433.2  397.83  4492.6  360.10  4497.8  360.54  4524.8  347.63
  4530.1  348.01  4542.1  343.05  4594.6  332.69  4644.5  329.05  4972.6  323.78
  4973.1  323.28  4979.3  323.78  5354.9  327.30  6949.3  328.41  7048.8  330.61
  7089.7  339.73  7148.9  361.87  7225.1  362.85  7323.6  363.92  7503.0  372.71
#Mann=13,-1,0
  4021.3    0.07       0  4087.8    0.12       0  4304.1    0.07       0
  4335.9    0.12       0  4542.1   0.035       0  4644.5   0.045       0
  4972.6   0.045       0  4979.3   0.045       0  5354.9    0.05       0
  6949.3    0.12       0  7089.7    0.05       0  7225.1    0.12       0
  7323.6    0.05       0
Bank Sta=4972.6,4979.3
Exp/Cntr=0.3,0.1

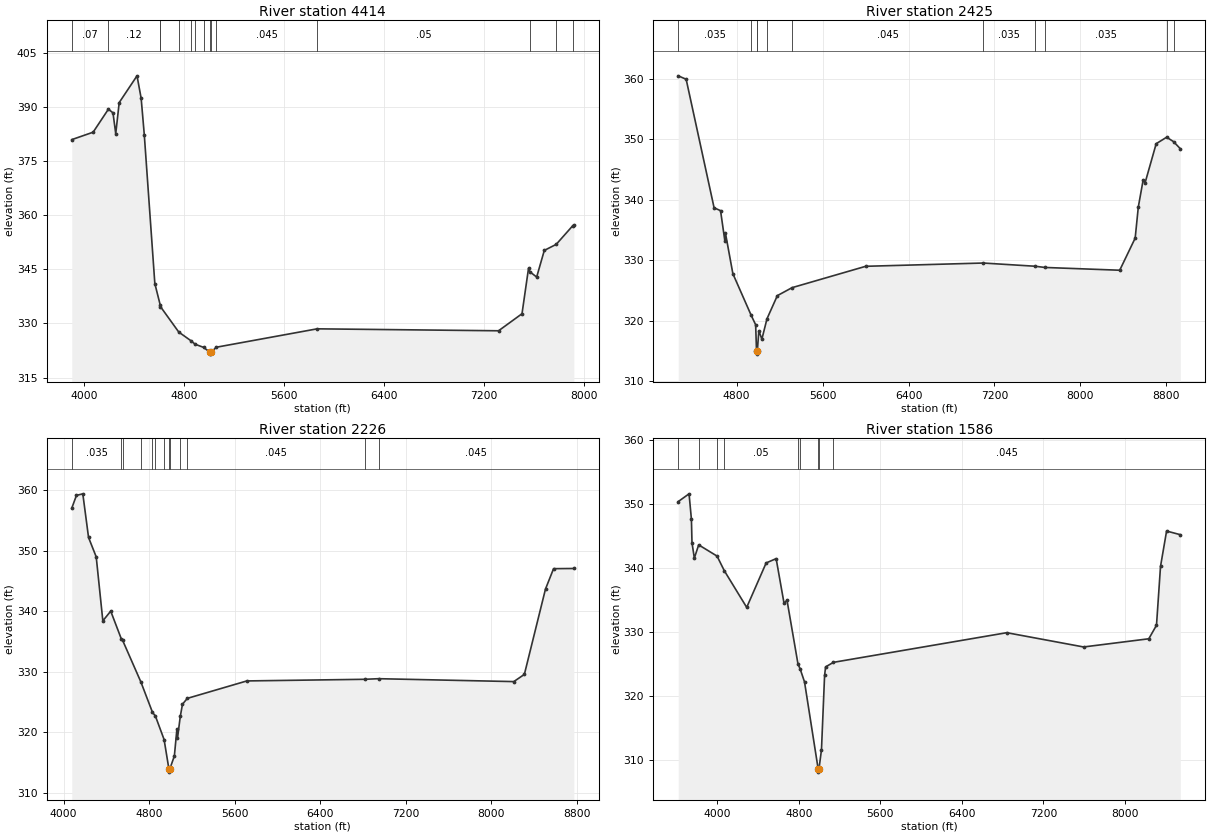
Type RM Length L Ch R = 1,4414,1989,1989,1989
BEGIN DESCRIPTION:
XS6379
END DESCRIPTION:
XS GIS Cut Line= 3
      2418101.21     13734019.99      2416863.75     13733648.75
      2414182.54     13734157.49
#Sta/Elev= 30
  3899.2  380.95  4070.3  383.01  4192.6  389.39  4229.3  388.37  4251.3  382.59
  4279.1  391.22  4421.8  398.63  4454.9  392.40  4479.9  382.35  4564.5  341.06
  4607.1  335.19  4609.6  334.67  4756.2  327.62  4852.9  325.24  4886.7  324.26
  4954.8  323.38  5006.5  322.01  5007.0  321.51  5013.5  322.01  5056.7  323.42
  5864.3  328.52  7317.2  327.98  7505.0  332.70  7557.3  345.30  7567.9  344.33
  7622.5  342.87  7683.6  350.25  7778.8  351.92  7911.1  357.08  7920.2  357.28
#Mann=15,-1,0
  3899.2    0.07       0  4192.6    0.12       0  4607.1    0.07       0
  4609.6    0.12       0  4756.2     0.1       0  4852.9    0.12       0
  4886.7     0.1       0  4954.8   0.035       0  5006.5   0.035       0
  5013.5   0.035       0  5056.7   0.045       0  5864.3    0.05       0
  7567.9    0.12       0  7778.8   0.035       0  7911.1    0.05       0
Bank Sta=5006.5,5013.5
Exp/Cntr=0.3,0.1

Type RM Length L Ch R = 1,2425,199,199,199
BEGIN DESCRIPTION:
XS6378
END DESCRIPTION:
XS GIS Cut Line= 3
      2418678.71     13731985.00      2418252.50     13731985.00
      2414389.33     13733744.74
#Sta/Elev= 30
  4257.6  360.49  4331.3  359.92  4591.3  338.67  4651.3  338.20  4691.2  333.22
  4696.7  334.50  4765.9  327.78  4936.0  320.91  4977.8  319.34  4986.1  314.98
  4986.6  314.48  4993.5  314.98  5007.4  318.34  5035.9  316.96  5083.3  320.32
  5179.7  324.15  5316.8  325.47  6001.9  329.00  7095.6  329.54  7577.7  329.01
  7668.1  328.81  8365.2  328.35  8509.0  333.66  8538.1  338.80  8583.6  343.31
  8601.2  342.80  8704.4  349.27  8801.7  350.34  8865.9  349.61  8928.9  348.44
#Mann=11,-1,0
  4257.6   0.035       0  4936.0   0.063       0  4986.1    0.05       0
  4993.5   0.063       0  5083.3   0.035       0  5316.8   0.045       0
  7095.6   0.035       0  7577.7    0.05       0  7668.1   0.035       0
  8801.7    0.12       0  8865.9   0.035       0
Bank Sta=4986.1,4993.5
Exp/Cntr=0.3,0.1

Type RM Length L Ch R = 1,2226,640,640,640
BEGIN DESCRIPTION:
XS6377
END DESCRIPTION:
XS GIS Cut Line= 4
      2418747.55     13731875.01      2418293.75     13731765.00
      2416575.00     13732507.50      2414416.21     13733456.27
#Sta/Elev= 30
  4076.5  356.99  4120.3  359.10  4179.8  359.36  4233.5  352.15  4305.2  348.95
  4367.2  338.38  4440.9  339.99  4540.1  335.40  4552.1  335.17  4723.1  328.29
  4831.7  323.27  4858.8  322.67  4940.3  318.78  4985.4  313.90  4985.9  313.40
  4993.4  313.90  5036.4  316.07  5059.9  320.46  5065.4  318.96  5091.6  322.59
  5112.4  324.62  5157.5  325.58  5714.5  328.46  6816.6  328.73  6947.0  328.83
  8212.0  328.35  8310.9  329.54  8508.6  343.64  8584.1  347.00  8773.8  347.03
#Mann=13,-1,0
  4076.5   0.035       0  4540.1    0.07       0  4552.1   0.035       0
  4723.1    0.07       0  4831.7     0.1       0  4858.8   0.035       0
  4940.3     0.1       0  4985.4    0.05       0  4993.4     0.1       0
  5091.6   0.063       0  5157.5   0.045       0  6816.6   0.035       0
  6947.0   0.045       0
Bank Sta=4985.4,4993.4
Exp/Cntr=0.3,0.1

Type RM Length L Ch R = 1,1586,0,0,0
BEGIN DESCRIPTION:
XS6376
END DESCRIPTION:
XS GIS Cut Line= 3
      2418843.71     13731764.98      2417895.00     13731338.75
      2414362.60     13732960.63
#Sta/Elev= 30
  3617.0  350.36  3723.2  351.57  3746.4  347.59  3751.9  343.94  3775.1  341.53
  3817.6  343.60  3997.9  341.85  4068.9  339.57  4288.9  333.84  4479.7  340.78
  4577.8  341.45  4655.5  334.46  4684.3  334.97  4792.5  324.97  4812.3  324.28
  4856.2  322.21  4990.1  308.62  4990.6  308.12  4998.1  308.62  5022.6  311.60
  5053.2  323.21  5063.1  324.55  5139.8  325.26  6841.1  329.89  7595.0  327.66
  8234.8  328.94  8310.3  331.05  8349.8  340.24  8409.3  345.76  8544.0  345.19
#Mann=9,-1,0
  3617.0   0.035       0  3817.6   0.063       0  3997.9   0.035       0
  4068.9    0.05       0  4792.5    0.07       0  4812.3     0.1       0
  4990.1    0.05       0  4998.1     0.1       0  5139.8   0.045       0
Bank Sta=4990.1,4998.1
Exp/Cntr=0.3,0.1

Chan Stop Cuts=-1