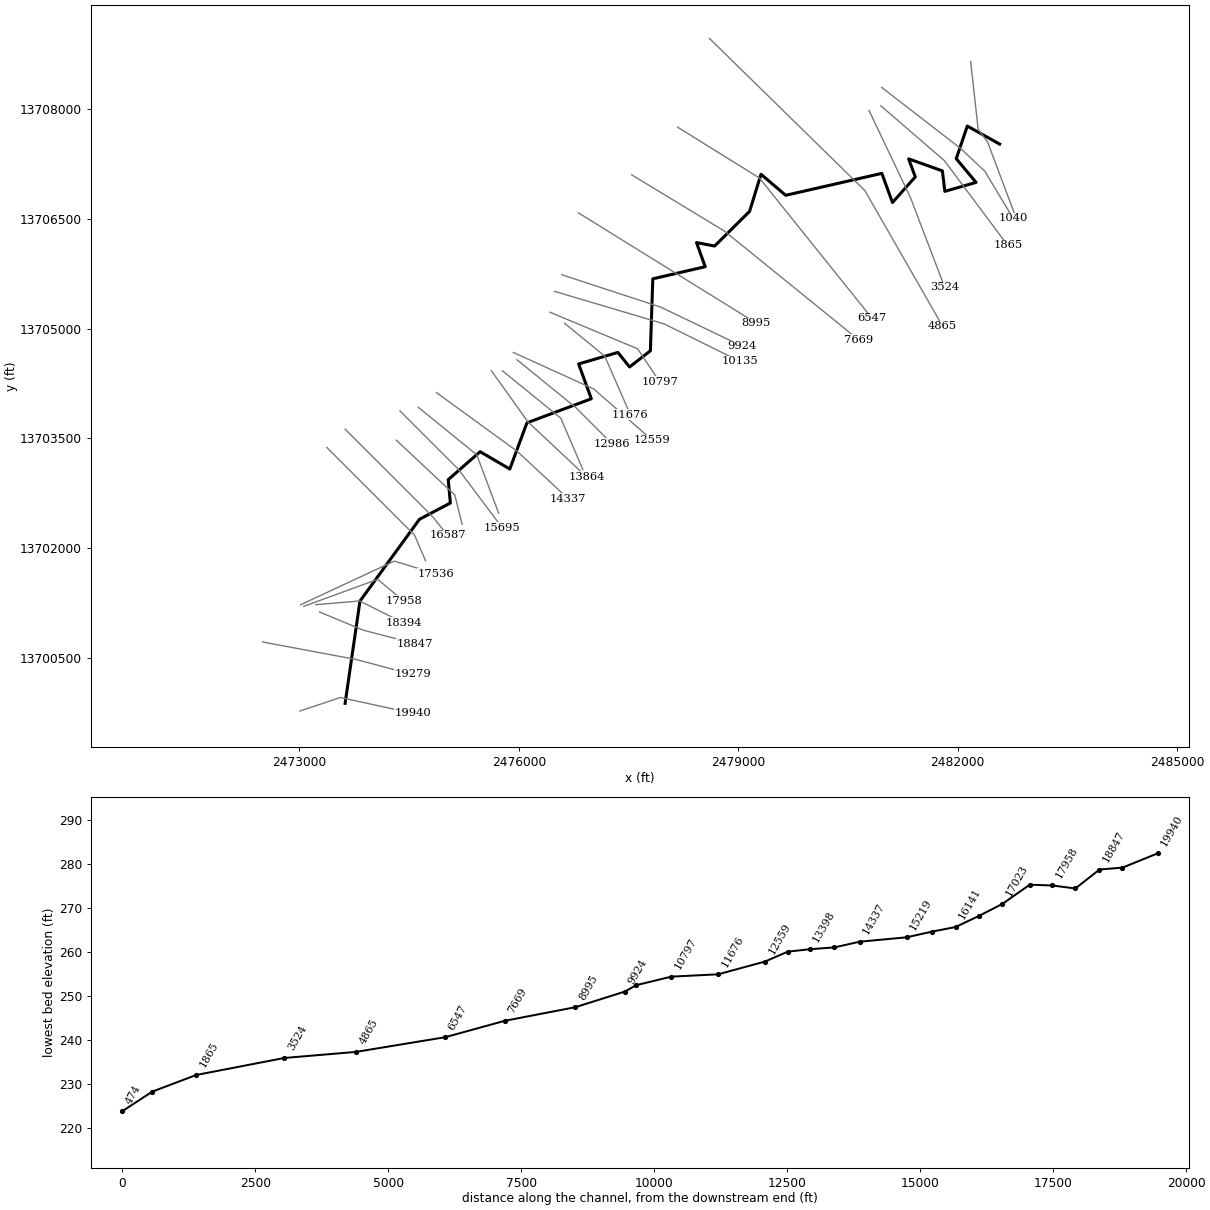
--- Stream0295.prj (project) ---

Proj Title=Stream0295 Base Level Engineering
Current Plan=p01
Default Exp/Contr=0.3,0.1
English Units
Geom File=g01
Flow File=f01
Plan File=p01
Y Axis Title=Elevation
X Axis Title(PF)=Main Channel Distance
X Axis Title(XS)=Station
BEGIN DESCRIPTION:
Stream0295
END DESCRIPTION:
DSS Export Rating Curves= 0
DSS Export Rating Curve Sorted= 0
DSS Export Volume Flow Curves= 0
DXF OffsetX= 0
DXF OffsetY= 0
DXF ScaleX= 1
DXF ScaleY= 10

--- Stream0295.p01 (plan) ---

Plan Title=Multiple Run
Short Identifier=Multiple
Geom File=g01
Flow File=f01
Subcritical Flow
K Sum by GR= 0
Std Step Tol= 0.01
Critical Tol= 0.01
Num of Std Step Trials= 20
Max Error Tol= 0.3
Flow Tol Ratio= 0.001
Split Flow NTrial= 30
Split Flow Tol= 0.02
Split Flow Ratio= 0.02
Log Output Level= 0
Friction Slope Method= 1
Unsteady Friction Slope Method= 2
Unsteady Bridges Friction Slope Method= 1
Parabolic Critical Depth
Global Vel Dist=  1 , 1 , 1
Global Log Level= 0
CheckData=True
Encroach Param= -1, 0, 0, 0
BEGIN DESCRIPTION:
Multiple Run
END DESCRIPTION:

--- Stream0295.f01 (steady flow) ---

Flow Title=Multiple
Number of Profiles=7
Profile Names=10-year,25-year,50-year,1pct_min,100-year,1pct_plu,500-year
River Rch & RM= Stream0295,Reach-1,19940
     569     903    1199     771    1538    3069    2508
River Rch & RM= Stream0295,Reach-1,17023
    1086    1774    2401    1570    3133    6251    5283
River Rch & RM= Stream0295,Reach-1,10135
    1303    2141    2910    1908    3808    7597    6460
River Rch & RM= Stream0295,Reach-1,1865
    1378    2267    3084    2023    4037    8054    6856
Boundary for River Rch & Prof#=Stream0295,Reach-1,1
Up Type=0
Dn Type=3
Dn Slope=0.005
Boundary for River Rch & Prof#=Stream0295,Reach-1,2
Up Type=0
Dn Type=3
Dn Slope=0.005
Boundary for River Rch & Prof#=Stream0295,Reach-1,3
Up Type=0
Dn Type=3
Dn Slope=0.005
Boundary for River Rch & Prof#=Stream0295,Reach-1,4
Up Type=0
Dn Type=3
Dn Slope=0.005
Boundary for River Rch & Prof#=Stream0295,Reach-1,5
Up Type=0
Dn Type=3
Dn Slope=0.005
Boundary for River Rch & Prof#=Stream0295,Reach-1,6
Up Type=0
Dn Type=3
Dn Slope=0.005
Boundary for River Rch & Prof#=Stream0295,Reach-1,7
Up Type=0
Dn Type=3
Dn Slope=0.005

--- Stream0295.g01 (geometry) ---

Geom Title=Existing Conditions
Program Version=4.10

River Reach=Stream0295      ,Reach-1
Reach XY= 30
        2473625.       13699875.      2473828.09     13701273.37
      2474641.24     13702392.23      2475064.24     13702615.32
      2475035.17     13702934.68      2475471.29     13703317.33
      2475877.28     13703080.05      2476111.27      13703711.8
      2476991.82     13704041.46      2476818.14     13704517.19
      2477355.08     13704675.25      2477514.52     13704475.93
      2477799.41     13704697.69      2477832.45     13705681.69
      2478549.09     13705847.85      2478430.06     13706177.86
      2478677.75     13706130.29      2479155.98     13706604.68
      2479311.79     13707111.89      2479649.87     13706824.46
      2480964.39      13707124.4      2481109.83     13706725.36
      2481421.89     13707076.65      2481330.44     13707322.95
      2481792.22     13707158.73      2481826.02     13706878.45
      2482252.51     13707001.04      2481981.98     13707325.21
      2482133.09     13707771.65        2482575.       13707525.

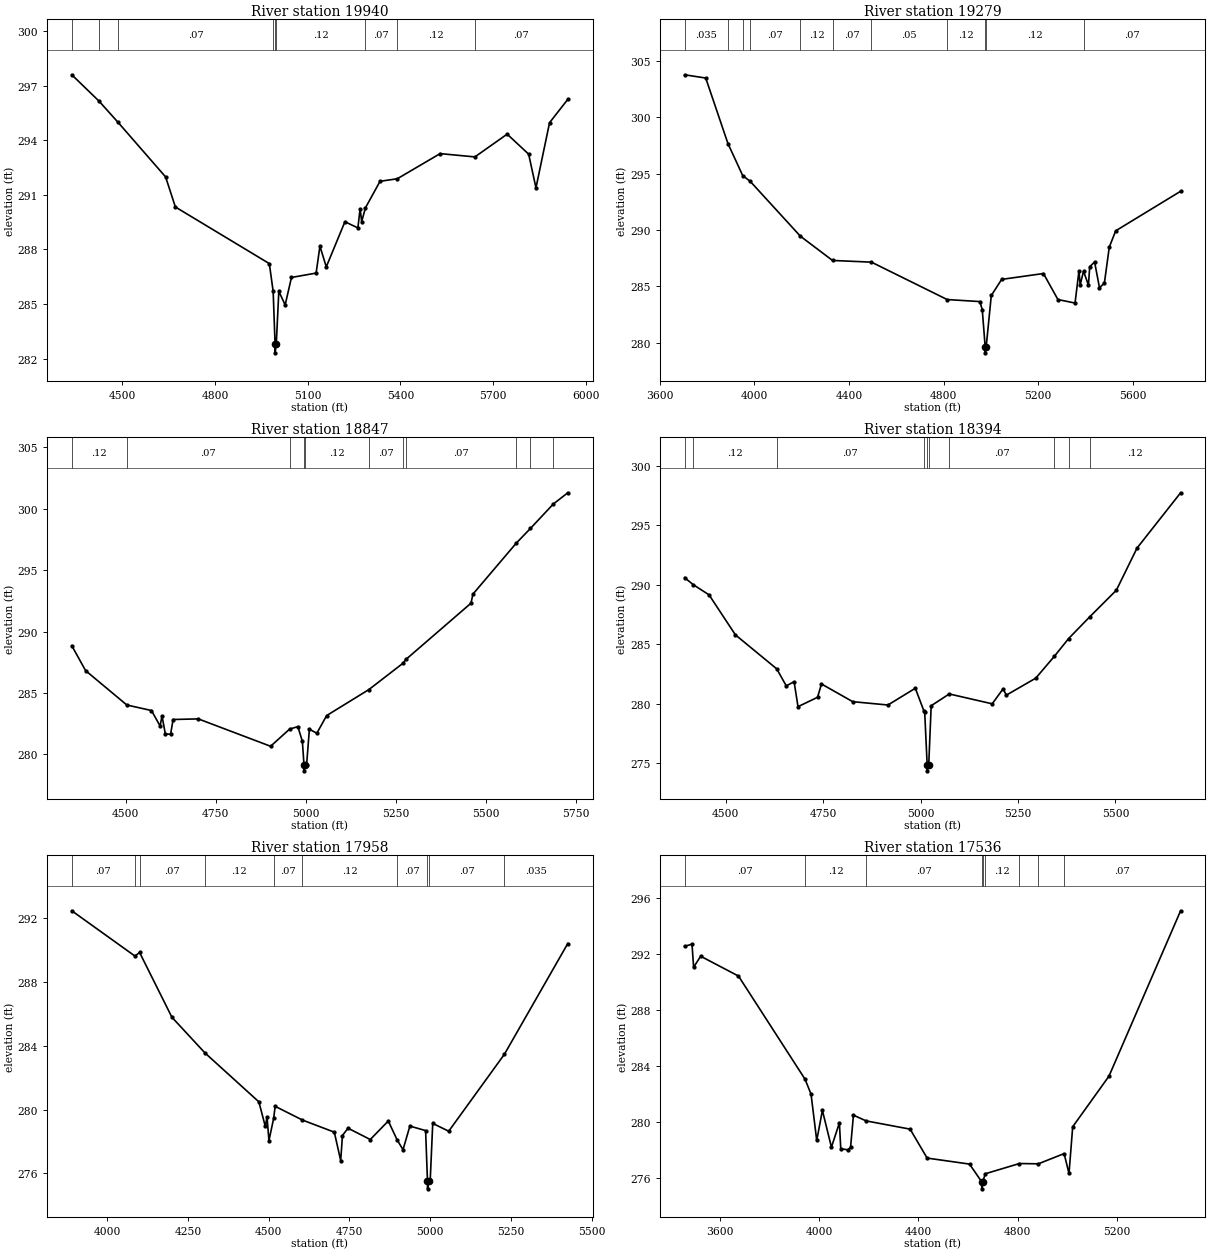
Type RM Length L Ch R = 1 ,19940   ,661,661,661
BEGIN DESCRIPTION:
Stream0295 38.0
END DESCRIPTION:
XS GIS Cut Line= 3
      2473007.02     13699770.22      2473560.42     13699954.69
      2474558.67     13699737.67
#Sta/Elev= 30
  4336.5  297.59  4424.3  296.15  4485.6  294.99  4640.1  291.98  4671.7  290.33
  4975.7  287.22  4988.1  285.69  4994.2  282.82  4994.4  282.32  4998.2  282.82
  5006.4   285.7  5026.9  284.95  5047.3  286.46  5127.1   286.7  5139.4  288.18
  5159.9  287.04  5220.3  289.52  5262.2  289.18  5269.4  290.23  5274.5  289.53
  5286.6  290.28  5333.9  291.74  5389.7  291.88  5528.3  293.26  5640.8  293.08
  5745.2  294.33  5814.8  293.23  5838.4  291.38  5882.4  294.96  5941.4  296.24
#Mann= 9 ,-1 , 0
  4336.5     .07       0  4424.3    .035       0  4485.6     .07       0
  4988.1     .12       0  4994.2     .05       0  4998.2     .12       0
  5286.6     .07       0  5389.7     .12       0  5640.8     .07       0
Bank Sta=4994.2,4998.2
XS Rating Curve= 0 ,0
Exp/Cntr=0.3,0.1

Type RM Length L Ch R = 1 ,19279   ,432,432,432
BEGIN DESCRIPTION:
Stream0295 37.0
END DESCRIPTION:
XS GIS Cut Line= 3
      2472497.09     13700714.23        2473775.       13700475.
      2474546.64     13700269.68
#Sta/Elev= 30
  3704.3  303.77  3793.7  303.48  3887.6  297.67    3950  294.83  3982.4   294.3
  4194.3  289.44  4330.1  287.29  4494.8  287.14  4815.2  283.82  4953.5  283.64
  4963.7  282.92  4976.1  279.59  4976.4  279.09  4980.1  279.59  5001.9  284.18
  5045.8  285.61  5222.6  286.13  5283.8  283.82  5356.2  283.51  5372.8  286.36
    5378  285.12  5392.1  286.34    5413   285.1  5418.3  286.74    5439  287.15
  5459.7  284.86  5480.4  285.29  5501.1  288.47  5528.2  289.92  5802.9  293.43
#Mann= 11 ,-1 , 0
  3704.3    .035       0  3887.6     .07       0    3950    .035       0
  3982.4     .07       0  4194.3     .12       0  4330.1     .07       0
  4494.8     .05       0  4815.2     .12       0  4976.1     .05       0
  4980.1     .12       0  5392.1     .07       0
Bank Sta=4976.1,4980.1
XS Rating Curve= 0 ,0
Exp/Cntr=0.3,0.1

Type RM Length L Ch R = 1 ,18847   ,453,453,453
BEGIN DESCRIPTION:
Stream0295 36.0
END DESCRIPTION:
XS GIS Cut Line= 3
      2473275.02     13701124.99        2473875.       13700875.
      2474580.21     13700692.58
#Sta/Elev= 30
  4350.1  288.85  4388.5  286.82  4503.1  284.02  4571.6  283.57  4595.5  282.31
  4600.9  283.13  4610.1  281.66  4624.7  281.64  4631.7  282.84  4701.6  282.89
  4902.6  280.66  4955.5  282.06  4978.4  282.26  4990.9  281.06  4995.4  279.16
  4995.6  278.66  4999.4  279.16  5002.7  279.16  5010.4  282.05  5031.1  281.72
  5058.4  283.16  5175.9  285.28  5270.5  287.42    5279  287.74  5459.5  292.31
  5464.9  293.05  5585.6  297.21  5624.8   298.4  5688.1  300.38  5728.5   301.3
#Mann= 11 ,-1 , 0
  4350.1     .12       0  4503.1     .07       0  4955.5     .12       0
  4995.4     .05       0  4999.4     .12       0  5175.9     .07       0
  5270.5     .12       0    5279     .07       0  5585.6     .12       0
  5624.8    .035       0  5688.1     .07       0
Bank Sta=4995.4,4999.4
XS Rating Curve= 0 ,0
Exp/Cntr=0.3,0.1

Type RM Length L Ch R = 1 ,18394   ,436,436,436
BEGIN DESCRIPTION:
Stream0295 35.0
END DESCRIPTION:
XS GIS Cut Line= 3
      2473224.98       13701225.        2473825.       13701275.
      2474424.98     13700975.01
#Sta/Elev= 30
  4394.4  290.61    4416  290.03  4457.1  289.16  4524.9  285.79  4630.9  282.93
  4655.3   281.5  4675.4  281.85  4685.4  279.75  4735.6  280.54  4745.6  281.66
  4825.9  280.17  4916.2  279.89  4986.5   281.3  5008.7  279.37  5010.5  279.31
  5016.9  274.85  5017.1  274.35  5020.9  274.85  5027.2  279.83  5073.6  280.82
  5183.8  279.99  5211.7  281.25  5220.1  280.72  5295.6  282.15  5343.6     284
  5379.8  285.48  5433.8   287.3  5502.4  289.55  5555.5   293.1  5667.3  297.75
#Mann= 10 ,-1 , 0
  4394.4     .07       0    4416     .12       0  4630.9     .07       0
  5008.7     .12       0  5016.9     .05       0  5020.9     .12       0
  5073.6     .07       0  5343.6     .12       0  5379.8     .07       0
  5433.8     .12       0
Bank Sta=5016.9,5020.9
XS Rating Curve= 0 ,0
Exp/Cntr=0.3,0.1

Type RM Length L Ch R = 1 ,17958   ,422,422,422
BEGIN DESCRIPTION:
Stream0295 34.0
END DESCRIPTION:
XS GIS Cut Line= 3
      2473061.33     13701202.53       2474070.4     13701571.44
      2474425.01     13701274.99
#Sta/Elev= 30
  3889.8  292.45  4085.7  289.61  4099.8  289.84    4200  285.78  4302.6  283.54
  4469.4  280.48  4489.3  278.94  4494.7  279.53  4500.6  278.05  4515.2  279.45
  4519.9   280.2  4604.3  279.34  4703.1  278.58  4722.9   276.8  4728.3  278.37
  4745.5  278.83  4814.5  278.12  4870.3  279.28  4897.4  278.11  4915.9  277.48
  4937.2  278.96  4985.9  278.68  4991.7  275.53  4991.9  275.03  4995.7  275.53
  5000.2  275.56    5008  279.13  5057.5  278.64    5230  283.46  5426.4   290.4
#Mann= 10 ,-1 , 0
  3889.8     .07       0  4085.7     .12       0  4099.8     .07       0
  4302.6     .12       0  4515.2     .07       0  4604.3     .12       0
  4897.4     .07       0  4991.7     .05       0  4995.7     .07       0
    5230    .035       0
Bank Sta=4991.7,4995.7
XS Rating Curve= 0 ,0
Exp/Cntr=0.3,0.1

Type RM Length L Ch R = 1 ,17536   ,513,513,513
BEGIN DESCRIPTION:
Stream0295 33.0
END DESCRIPTION:
XS GIS Cut Line= 3
      2473017.87     13701224.21      2474298.26     13701821.01
      2474861.27     13701647.77
#Sta/Elev= 30
  3456.4  292.56  3486.3  292.71  3492.8  291.06  3521.2  291.85  3673.9  290.43
  3942.5  283.05  3966.7  281.98  3989.6  278.67  4012.5  280.82    4049  278.19
  4081.1  279.93  4086.6  278.08  4115.2     278  4126.2  278.19  4137.8  280.48
    4189  280.07  4366.5  279.48  4435.1  277.41  4606.2  276.98  4655.5  275.71
  4655.7  275.21  4659.5  275.71  4670.1  276.29  4807.4  277.02    4884     277
  4987.9  277.73  5007.7  276.31  5022.6  279.65    5169  283.27  5458.1   295.1
#Mann= 9 ,-1 , 0
  3456.4     .07       0  3942.5     .12       0    4189     .07       0
  4655.5     .05       0  4659.5     .07       0  4670.1     .12       0
  4807.4     .07       0    4884     .12       0  4987.9     .07       0
Bank Sta=4655.5,4659.5
XS Rating Curve= 0 ,0
Exp/Cntr=0.3,0.1

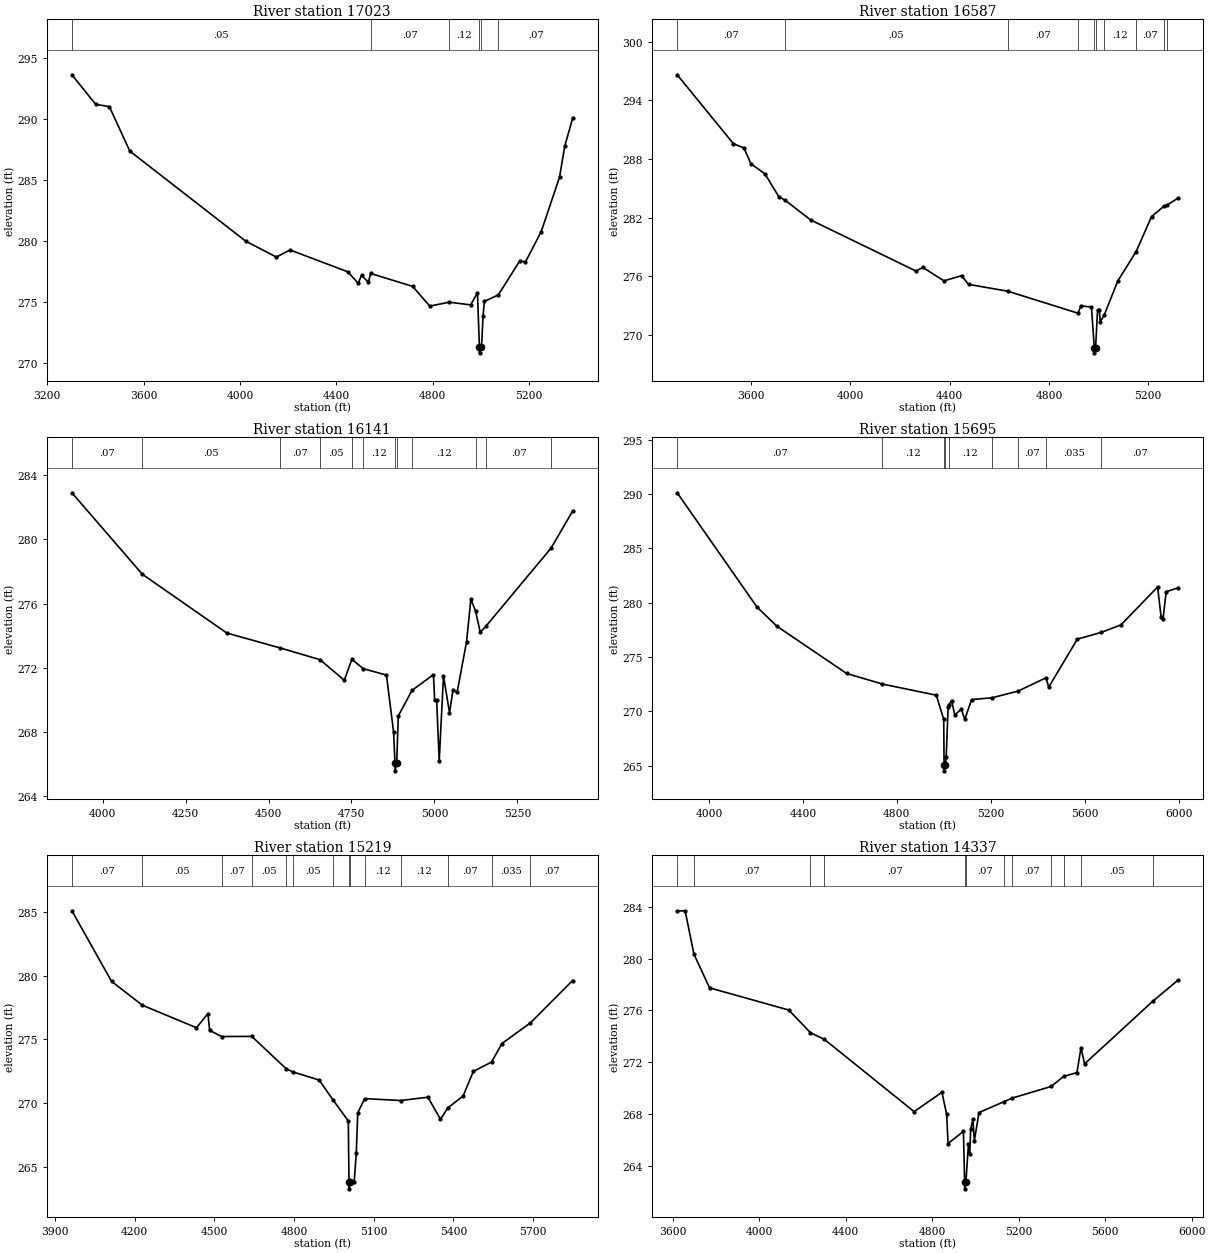
Type RM Length L Ch R = 1 ,17023   ,436,436,436
BEGIN DESCRIPTION:
Stream0295 32.0
END DESCRIPTION:
XS GIS Cut Line= 3
      2473375.01     13703374.99        2474575.       13702175.
      2474724.99     13701825.02
#Sta/Elev= 30
  3302.5  293.59  3401.5  291.17    3458  290.99  3542.9  287.35  4023.7  279.99
    4151  278.69  4207.6  279.27    4448  277.48  4490.4  276.54  4504.6   277.2
  4532.8  276.63  4542.1  277.35  4716.7  276.29  4787.4  274.68  4868.2     275
  4957.1  274.78  4985.4  275.77  4993.5  271.36  4993.9  270.86  4998.6  271.36
  5002.3  271.36  5008.6  273.86    5014  275.06  5072.1   275.6  5160.9  278.37
  5184.5  278.29  5249.8  280.76  5325.9  285.22  5347.7  287.76  5380.3  290.03
#Mann= 6 ,-1 , 0
  3302.5     .05       0  4542.1     .07       0  4868.2     .12       0
  4993.5     .05       0  4998.6     .12       0  5072.1     .07       0
Bank Sta=4993.5,4998.6
XS Rating Curve= 0 ,0
Exp/Cntr=0.3,0.1

Type RM Length L Ch R = 1 ,16587   ,446,446,446
BEGIN DESCRIPTION:
Stream0295 31.0
END DESCRIPTION:
XS GIS Cut Line= 3
      2473625.01     13703624.99        2474825.       13702425.
        2475025.       13702175.
#Sta/Elev= 30
  3302.4  296.62  3528.7  289.57  3571.1  289.13  3599.4  287.51  3655.9  286.47
  3712.5  284.11  3735.4  283.81  3839.8  281.76  4264.1  276.53  4292.3  276.89
  4377.2  275.52  4447.9  276.05  4476.2  275.16  4634.2  274.46  4916.8  272.21
  4928.7  272.95  4971.2  272.85  4982.7  268.65  4983.1  268.15  4987.9  268.65
  4995.9  272.54  5002.6  272.54  5006.7  271.35  5022.3  271.99  5077.1   275.5
  5151.1  278.51  5213.2   282.1  5263.8  283.17  5274.4  283.25  5319.6  283.99
#Mann= 10 ,-1 , 0
  3302.4     .07       0  3735.4     .05       0  4634.2     .07       0
  4916.8     .12       0  4982.7     .05       0  4987.9     .12       0
  5022.3     .12       0  5151.1     .07       0  5263.8     .05       0
  5274.4     .07       0
Bank Sta=4982.7,4987.9
XS Rating Curve= 0 ,0
Exp/Cntr=0.3,0.1

Type RM Length L Ch R = 1 ,16141   ,446,446,446
BEGIN DESCRIPTION:
Stream0295 30.0
END DESCRIPTION:
XS GIS Cut Line= 3
      2474325.03     13703474.97        2475125.       13702725.
      2475224.99     13702325.05
#Sta/Elev= 30
  3907.5   282.9  4119.7  277.83  4374.2  274.17  4533.3  273.25  4655.2  272.51
  4728.3  271.23  4751.1  272.53  4785.4  271.95  4855.3  271.55  4876.8  268.01
    4881  266.09  4881.4  265.59  4886.2  266.09    4891  269.01  4932.4   270.6
    4997  271.58  5000.6  269.97  5006.6  269.97  5014.3  266.22  5027.2  271.51
  5045.3  269.21  5055.6   270.6  5068.5   270.5  5096.8  273.64  5109.7  276.28
  5123.9  275.52    5138  274.22    5155  274.59  5351.5  279.46  5416.3  281.76
#Mann= 12 ,-1 , 0
  3907.5     .07       0  4119.7     .05       0  4533.3     .07       0
  4655.2     .05       0  4751.1     .07       0  4785.4     .12       0
    4881     .05       0  4886.2     .12       0  4932.4     .12       0
  5123.9     .12       0    5155     .07       0  5351.5     .05       0
Bank Sta=4881,4886.2
XS Rating Curve= 0 ,0
Exp/Cntr=0.3,0.1

Type RM Length L Ch R = 1 ,15695   ,476,476,476
BEGIN DESCRIPTION:
Stream0295 29.0
END DESCRIPTION:
XS GIS Cut Line= 3
      2474375.03     13703874.97        2475175.       13703075.
      2475774.98     13702275.03
#Sta/Elev= 30
    3865  290.12  4204.4  279.61  4289.2  277.84  4586.2  273.49    4738  272.52
    4968  271.49  4999.5  269.26  5000.9  265.03  5001.4  264.53  5006.3  265.03
  5009.9  265.79  5018.2  270.45    5020  270.58  5032.8     271  5046.3  269.68
  5074.5   270.2    5089  269.27  5118.2  271.09  5204.8  271.25    5316  271.87
  5434.5  273.09  5446.3  272.24  5568.2  276.65  5669.5  277.27  5753.6  277.96
  5909.9  281.45  5924.5  278.72  5932.8  278.48  5946.3  281.01  5996.3  281.37
#Mann= 9 ,-1 , 0
    3865     .07       0    4738     .12       0  5000.9     .05       0
  5006.3     .12       0    5020     .12       0  5204.8     .12       0
    5316     .07       0  5434.5    .035       0  5669.5     .07       0
Bank Sta=5000.9,5006.3
XS Rating Curve= 0 ,0
Exp/Cntr=0.3,0.1

Type RM Length L Ch R = 1 ,15219   ,882,882,882
BEGIN DESCRIPTION:
Stream0295 28.0
END DESCRIPTION:
XS GIS Cut Line= 3
      2474625.01     13703924.99        2475425.       13703275.
      2475725.01     13702474.97
#Sta/Elev= 30
  3963.4   285.1  4112.8  279.55  4228.6  277.68  4432.4  275.91  4475.6  277.02
    4482   275.7    4527  275.22  4640.6  275.23  4770.5  272.68  4796.3  272.43
  4894.3   271.8  4947.2  270.22    5004  268.58  5006.6  263.75    5007  263.25
    5012  263.75  5026.2  263.82  5034.2  266.07  5039.6  269.22  5065.8  270.34
  5201.2  270.19  5303.9  270.45  5351.1  268.71    5378   269.6  5436.5  270.55
  5474.8  272.48  5543.3  273.21  5582.5  274.67  5689.6  276.29  5848.6  279.62
#Mann= 14 ,-1 , 0
  3963.4     .07       0  4228.6     .05       0    4527     .07       0
  4640.6     .05       0  4770.5     .07       0  4796.3     .05       0
  4947.2     .07       0  5006.6     .05       0    5012     .07       0
  5065.8     .12       0  5201.2     .12       0    5378     .07       0
  5543.3    .035       0  5689.6     .07       0
Bank Sta=5006.6,5012
XS Rating Curve= 0 ,0
Exp/Cntr=0.3,0.1

Type RM Length L Ch R = 1 ,14337   ,473,473,473
BEGIN DESCRIPTION:
Stream0295 27.0
END DESCRIPTION:
XS GIS Cut Line= 3
      2474874.99     13704125.01        2475975.       13703325.
      2476674.99     13702675.01
#Sta/Elev= 30
  3621.2  283.66  3657.9  283.68  3698.5  280.34  3770.8  277.74  4137.1  276.03
  4237.6  274.28  4301.8  273.77  4716.7   268.2  4845.3  269.69  4867.4  267.99
  4873.6  265.74  4944.7  266.68  4950.3  262.75  4950.8  262.25  4956.1  262.75
  4967.8  265.68    4974  264.92  4978.3  266.86  4988.4   267.6  4995.3  265.97
  5016.8  268.13  5133.9  268.98  5171.5  269.25  5350.4  270.14  5407.9  270.91
  5469.7  271.21  5488.4  273.13  5504.9  271.88  5819.8   276.7  5936.6  278.33
#Mann= 12 ,-1 , 0
  3621.2    .035       0  3698.5     .07       0  4237.6     .05       0
  4301.8     .07       0  4950.3     .05       0  4956.1     .07       0
  5133.9     .05       0  5171.5     .07       0  5350.4     .05       0
  5407.9    .035       0  5488.4     .05       0  5819.8     .07       0
Bank Sta=4950.3,4956.1
XS Rating Curve= 0 ,0
Exp/Cntr=0.3,0.1

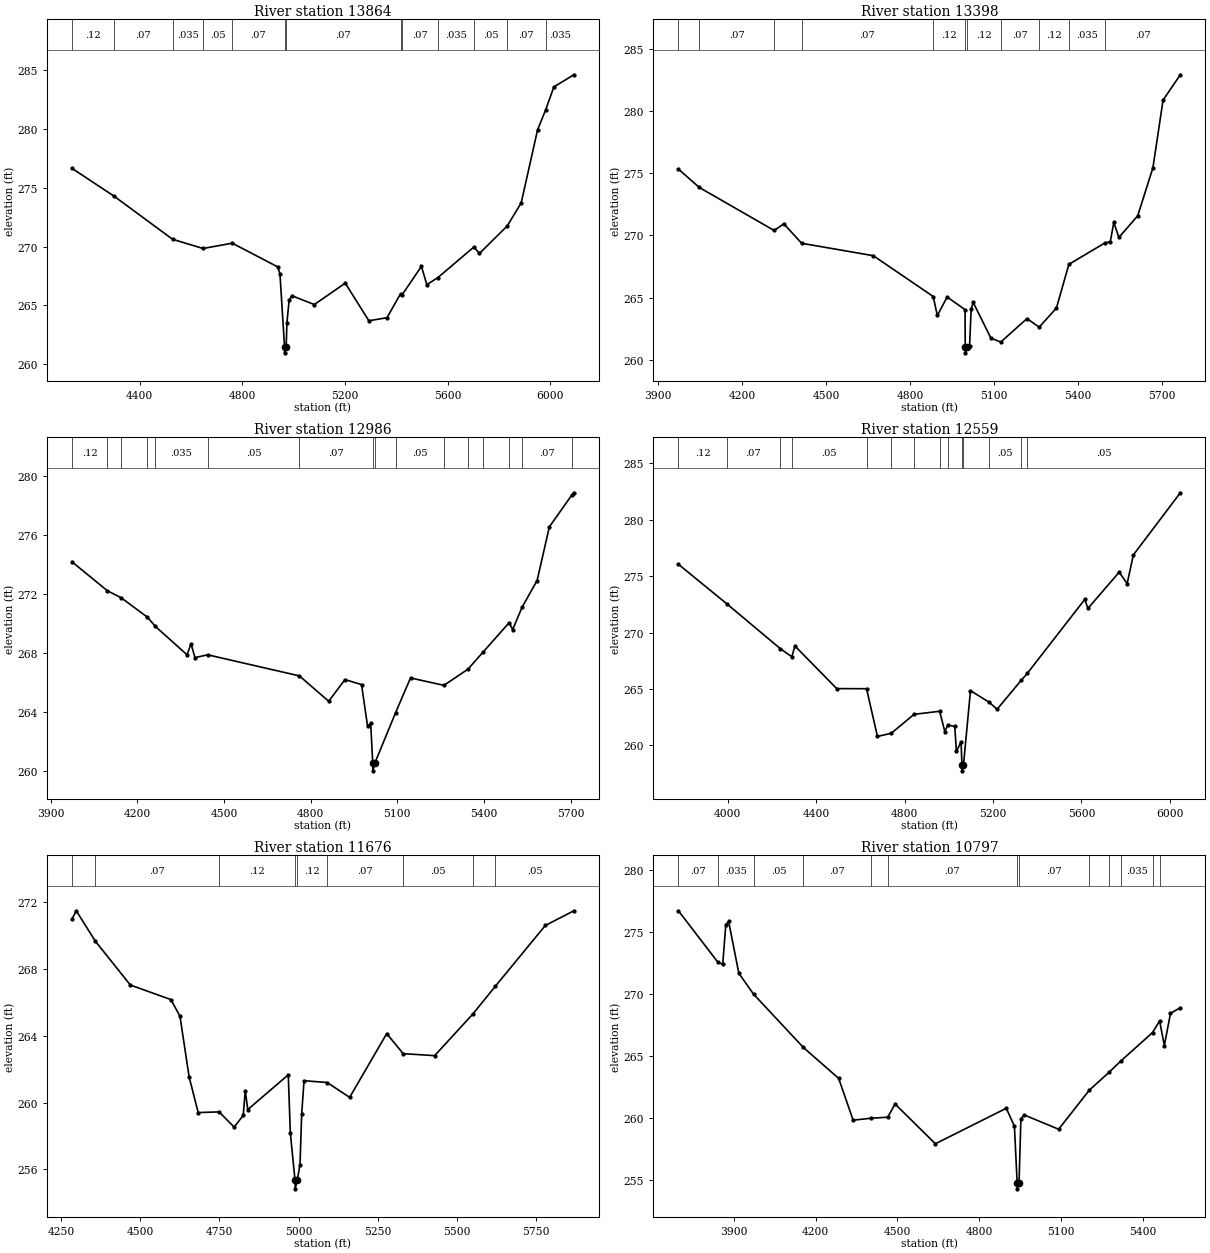
Type RM Length L Ch R = 1 ,13864   ,466,466,466
BEGIN DESCRIPTION:
Stream0295 26.0
END DESCRIPTION:
XS GIS Cut Line= 3
      2475624.99     13704425.01        2476125.       13703725.
      2476924.97     13702975.02
#Sta/Elev= 30
  4135.6  276.66  4299.2   274.3  4528.1  270.62  4646.7  269.84  4760.7  270.29
  4938.1  268.27  4946.7  267.65  4964.4  261.46  4964.9  260.96  4970.8  261.46
  4973.7  263.51  4982.3  265.43  4992.8  265.82  5080.6  265.07  5201.2  266.89
  5293.1  263.69  5363.9  263.95  5416.6  265.98  5422.9   265.9  5498.2  268.32
  5519.2  266.76  5562.7  267.37  5702.4  269.96  5724.4  269.42  5832.5  271.75
  5887.1  273.72    5951  279.94  5981.9   281.6  6014.5  283.59  6092.4  284.62
#Mann= 13 ,-1 , 0
  4135.6     .12       0  4299.2     .07       0  4528.1    .035       0
  4646.7     .05       0  4760.7     .07       0  4964.4     .05       0
  4970.8     .07       0  5416.6     .12       0  5422.9     .07       0
  5562.7    .035       0  5702.4     .05       0  5832.5     .07       0
  5981.9    .035       0
Bank Sta=4964.4,4970.8
XS Rating Curve= 0 ,0
Exp/Cntr=0.3,0.1

Type RM Length L Ch R = 1 ,13398   ,412,412,412
BEGIN DESCRIPTION:
Stream0295 25.0
END DESCRIPTION:
XS GIS Cut Line= 3
        2475775.       13704425.        2476575.       13703775.
      2476874.98     13703075.05
#Sta/Elev= 30
  3972.8  275.35  4047.3  273.87  4314.7   270.4  4349.2  270.94  4412.8  269.37
  4668.8  268.37  4882.7  265.08  4897.3  263.55  4932.5  265.04  4996.4  264.02
    4997  261.04  4997.5  260.54  5003.7  261.04  5012.6   261.1  5018.1  264.04
  5025.3  264.61  5088.8  261.72  5123.9  261.41  5217.5   263.3  5261.2  262.61
  5322.7  264.15  5367.1  267.67  5496.6  269.41  5514.9  269.49  5527.6  271.05
  5545.7  269.84  5612.8  271.58  5667.2  275.45  5703.5  280.91  5765.1  282.95
#Mann= 11 ,-1 , 0
  3972.8     .12       0  4047.3     .07       0  4314.7    .035       0
  4412.8     .07       0  4882.7     .12       0    4997     .05       0
  5003.7     .12       0  5123.9     .07       0  5261.2     .12       0
  5367.1    .035       0  5496.6     .07       0
Bank Sta=4997,5003.7
XS Rating Curve= 0 ,0
Exp/Cntr=0.3,0.1

Type RM Length L Ch R = 1 ,12986   ,427,427,427
BEGIN DESCRIPTION:
Stream0295 24.0
END DESCRIPTION:
XS GIS Cut Line= 3
      2475975.04     13704574.97        2476775.       13703925.
      2477274.97     13703425.03
#Sta/Elev= 30
  3973.4  274.17  4096.4   272.2  4143.9  271.73  4234.7  270.41    4262  269.79
    4372  267.86  4385.7  268.61  4399.3  267.67  4443.4  267.86  4760.9  266.43
  4862.4  264.71  4918.6  266.18  4976.1  265.84  4996.9  263.02  5007.7  263.21
  5014.9  260.49  5015.4  259.99  5021.6  260.49  5094.1  263.94  5145.6  266.29
  5261.4  265.79  5344.3  266.88  5396.8  268.04  5487.6  270.05  5499.1  269.56
  5532.2   271.1    5584   272.9  5626.4  276.54    5704  278.69  5711.2  278.85
#Mann= 16 ,-1 , 0
  3973.4     .12       0  4096.4     .07       0  4143.9     .12       0
  4234.7     .07       0    4262    .035       0  4443.4     .05       0
  4760.9     .07       0  5014.9     .05       0  5021.6     .07       0
  5094.1     .05       0  5261.4     .07       0  5344.3    .035       0
  5396.8     .07       0  5487.6     .05       0  5532.2     .07       0
    5704     .05       0
Bank Sta=5014.9,5021.6
XS Rating Curve= 0 ,0
Exp/Cntr=0.3,0.1

Type RM Length L Ch R = 1 ,12559   ,883,883,883
BEGIN DESCRIPTION:
Stream0295 23.0
END DESCRIPTION:
XS GIS Cut Line= 3
      2475925.02     13704674.99        2477025.       13704175.
      2477825.01     13703474.99
#Sta/Elev= 30
  3776.4  276.05    3994  272.57  4236.9  268.58  4289.7  267.85  4303.6  268.81
  4492.6  265.03  4627.8  265.02  4677.1  260.79  4739.6  261.07  4842.8  262.75
  4958.7  263.02  4981.9  261.22  4995.3  261.79  5026.9  261.68  5034.5  259.46
  5055.4  260.31  5059.6  258.24  5060.1  257.74  5066.3  258.24  5098.1  264.85
  5182.6  263.82  5218.6   263.2  5327.4  265.76  5355.2  266.38  5615.4  272.94
  5629.6  272.14    5771  275.35  5807.1  274.34  5835.1  276.88  6047.7  282.39
#Mann= 14 ,-1 , 0
  3776.4     .12       0    3994     .07       0  4236.9    .035       0
  4289.7     .05       0  4627.8     .07       0  4739.6     .05       0
  4842.8     .07       0  4958.7     .05       0  4995.3     .07       0
  5059.6     .05       0  5066.3     .07       0  5182.6     .05       0
  5327.4    .035       0  5355.2     .05       0
Bank Sta=5059.6,5066.3
XS Rating Curve= 0 ,0
Exp/Cntr=0.3,0.1

Type RM Length L Ch R = 1 ,11676   ,879,879,879
BEGIN DESCRIPTION:
Stream0295 22.0
END DESCRIPTION:
XS GIS Cut Line= 3
      2476625.03     13705074.97        2477175.       13704625.
        2477525.       13703825.
#Sta/Elev= 30
  4284.9     271  4298.5   271.5  4358.6  269.68  4469.3  267.05  4597.1  266.18
  4625.8  265.18  4654.5  261.56  4683.2  259.41  4749.2  259.45  4796.7  258.54
  4825.4  259.24  4831.8  260.73  4839.7  259.59  4967.5  261.67    4974   258.2
  4988.9  255.34  4989.4  254.84  4995.7  255.34  5004.5  256.29  5009.9  259.34
  5017.3  261.32  5090.3  261.21  5161.2  260.32  5278.1  264.14  5330.2  262.94
  5429.4  262.82  5549.3   265.3  5621.1  266.98  5778.7  270.62  5868.7   271.5
#Mann= 9 ,-1 , 0
  4284.9    .035       0  4358.6     .07       0  4749.2     .12       0
  4988.9     .05       0  4995.7     .12       0  5090.3     .07       0
  5330.2     .05       0  5549.3    .035       0  5621.1     .05       0
Bank Sta=4988.9,4995.7
XS Rating Curve= 0 ,0
Exp/Cntr=0.3,0.1

Type RM Length L Ch R = 1 ,10797   ,662,662,662
BEGIN DESCRIPTION:
Stream0295 21.0
END DESCRIPTION:
XS GIS Cut Line= 3
      2476425.03     13705224.99        2477625.       13704725.
        2477925.       13704275.
#Sta/Elev= 30
  3696.6  276.71  3841.2  272.57  3859.1  272.39  3870.4  275.59  3880.7  275.86
  3918.1  271.68  3972.3  269.99  4154.8   265.7  4284.3  263.21  4337.4  259.84
  4403.9     260  4464.2  260.08  4491.2  261.14  4639.1  257.94  4899.1   260.8
  4928.9  259.36  4938.9  254.81  4939.4  254.31  4945.9  254.81  4952.7  259.92
  4964.1  260.27  5091.2  259.11  5203.2  262.25  5276.1   263.7  5319.3  264.61
  5435.5   266.9  5461.5  267.84  5478.8  265.85  5501.3  268.45  5537.4   268.9
#Mann= 13 ,-1 , 0
  3696.6     .07       0  3841.2    .035       0  3972.3     .05       0
  4154.8     .07       0  4403.9     .05       0  4464.2     .07       0
  4938.9     .05       0  4945.9     .07       0  5203.2     .07       0
  5276.1     .05       0  5319.3    .035       0  5435.5     .05       0
  5461.5     .07       0
Bank Sta=4938.9,4945.9
XS Rating Curve= 0 ,0
Exp/Cntr=0.3,0.1

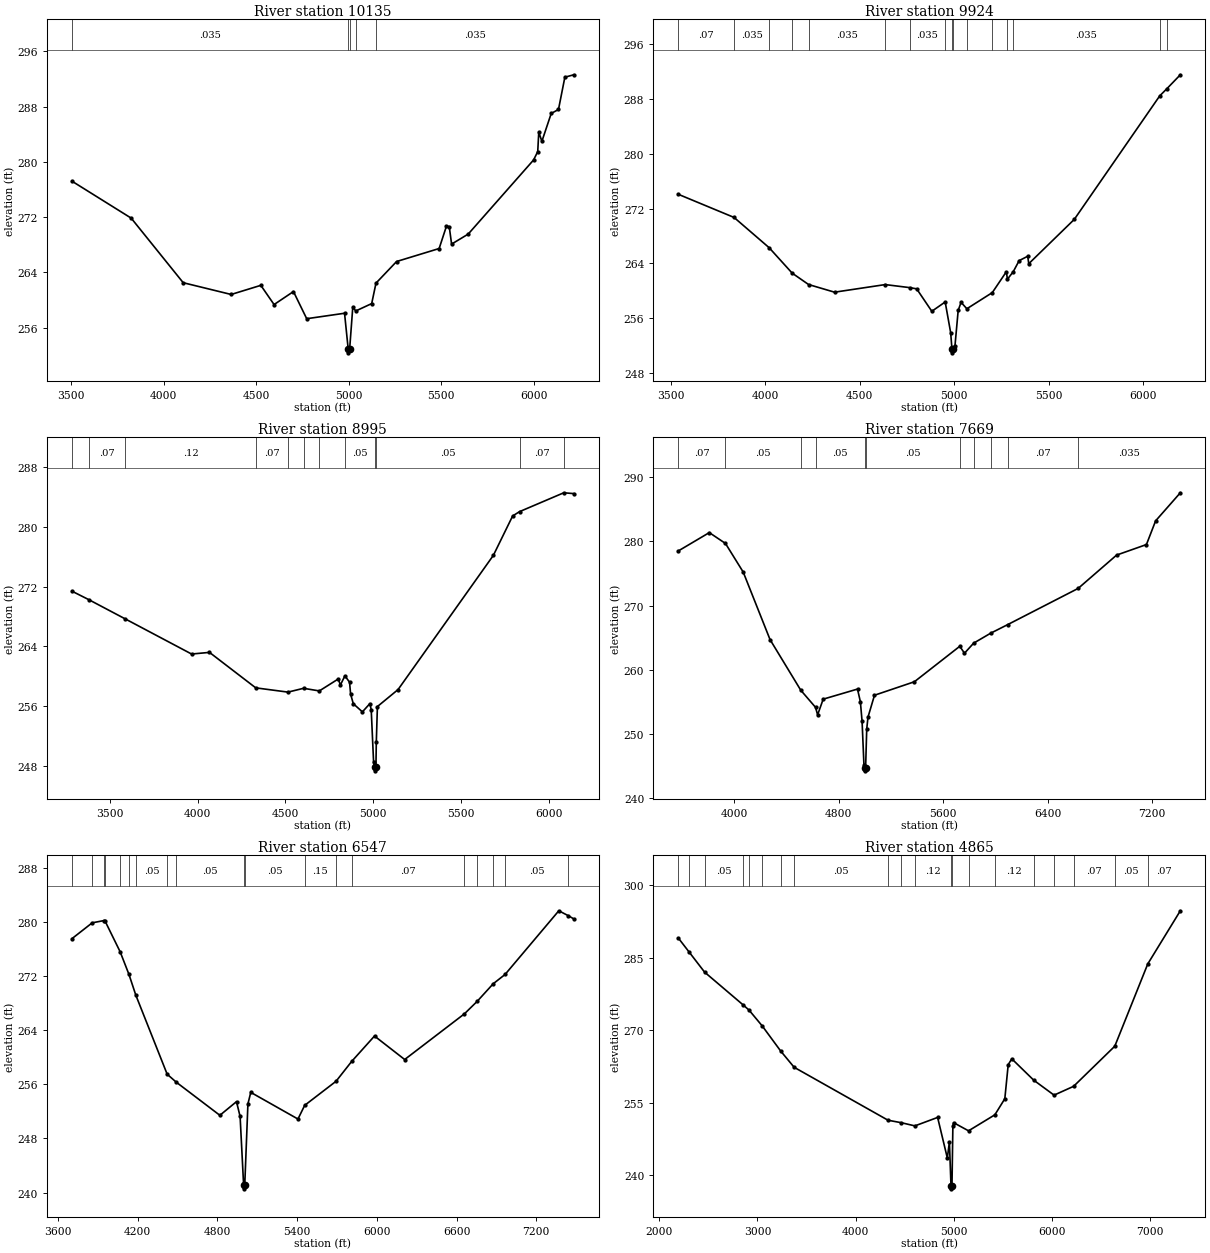
Type RM Length L Ch R = 1 ,10135   ,211,211,211
BEGIN DESCRIPTION:
XS6396
END DESCRIPTION:
XS GIS Cut Line= 3
      2476490.13     13705510.24       2477987.5     13705065.36
      2479018.29      13704555.4
#Sta/Elev= 30
  3504.5  277.21  3824.6  271.86  4105.8  262.51    4365  260.81  4525.2  262.13
  4596.8  259.35  4701.6  261.23  4773.2   257.3  4977.7  258.09  4997.6  252.86
  4998.1  252.36  5005.1  252.86  5022.2  258.98  5038.3  258.42  5124.4  259.49
  5147.6  262.45    5259  265.58  5488.9  267.46  5528.2  270.68  5543.5  270.63
  5556.2   268.1    5646  269.55  5999.3  280.28  6021.7  281.49  6027.3  284.29
  6044.2  282.98  6094.6  287.01  6133.9  287.59  6168.3  292.26  6216.6  292.61
#Mann= 5 ,-1 , 0
  3504.5    .035       0  4997.6    .035       0  5005.1    .035       0
  5038.3    .063       0  5147.6    .035       0
Bank Sta=4997.6,5005.1
XS Rating Curve= 0 ,0
Exp/Cntr=0.3,0.1

Type RM Length L Ch R = 1 ,9924    ,929,929,929
BEGIN DESCRIPTION:
XS6395
END DESCRIPTION:
XS GIS Cut Line= 3
      2476587.79      13705738.1       2477944.1     13705293.23
      2479050.46     13704761.74
#Sta/Elev= 30
  3541.3  274.07  3835.3   270.7  4020.9  266.28  4142.9  262.56  4229.5   260.9
    4367  259.78  4634.9  260.89  4763.8  260.45  4801.3  260.27  4881.5  256.99
  4952.2  258.35  4981.3  253.85  4988.1  251.42  4988.6  250.92  4995.6  251.42
  5003.9  251.92    5021  257.12  5036.3   258.3  5066.9  257.36  5201.5  259.72
  5275.6  262.76  5281.6  261.68  5312.2  262.77  5343.5  264.39  5388.8  265.03
  5394.3  263.94  5635.3  270.42  6087.2  288.46  6123.7  289.47  6196.1  291.54
#Mann= 16 ,-1 , 0
  3541.3     .07       0  3835.3    .035       0  4020.9     .07       0
  4142.9     .12       0  4229.5    .035       0  4634.9     .05       0
  4763.8    .035       0  4952.2     .05       0  4988.1     .05       0
  4995.6     .05       0  5066.9    .035       0  5201.5     .05       0
  5281.6    .063       0  5312.2    .035       0  6087.2     .07       0
  6123.7    .035       0
Bank Sta=4988.1,4995.6
XS Rating Curve= 0 ,0
Exp/Cntr=0.3,0.1

Type RM Length L Ch R = 1 ,8995    ,1326,1326,1326
BEGIN DESCRIPTION:
XS6394
END DESCRIPTION:
XS GIS Cut Line= 2
      2476815.62     13706584.46      2479246.18     13705076.21
#Sta/Elev= 30
  3282.9  271.38  3378.7  270.25  3587.1  267.67  3964.8  262.98  4066.9   263.2
  4330.5  258.46  4514.4  257.89    4603   258.4    4693  258.05  4800.4  259.64
  4813.3  258.85  4838.8  260.07  4865.3  259.21  4871.2  257.63  4886.6  256.34
  4938.5  255.25    4981  256.35  4988.7  255.55  5002.3   248.5    5008  247.87
  5008.5  247.37  5015.6  247.87  5017.7  251.18    5024  255.96  5141.7  258.23
    5685  276.17  5794.8  281.43  5834.2  282.01  6086.3  284.53  6143.4  284.42
#Mann= 12 ,-1 , 0
  3282.9    .035       0  3378.7     .07       0  3587.1     .12       0
  4330.5     .07       0  4514.4     .12       0    4603     .05       0
    4693    .035       0  4838.8     .05       0    5008     .05       0
  5015.6     .05       0  5834.2     .07       0  6086.3    .035       0
Bank Sta=5008,5015.6
XS Rating Curve= 0 ,0
Exp/Cntr=0.3,0.1

Type RM Length L Ch R = 1 ,7669    ,1122,1122,1122
BEGIN DESCRIPTION:
XS6393
END DESCRIPTION:
XS GIS Cut Line= 3
      2477542.62      13707105.3      2478812.15      13706334.9
      2480644.89     13704849.18
#Sta/Elev= 30
  3571.3  278.53  3807.5  281.37  3931.3  279.68  4067.3  275.22  4272.8  264.71
  4508.2  256.83    4621  254.17  4637.2     253  4679.9  255.44  4942.7  257.01
  4964.8  255.03  4977.8  251.98    4992  245.24  4997.3  244.78  4997.8  244.28
  5004.9  244.78  5013.3  250.76  5022.9  252.63  5072.8  256.05  5378.5  258.15
  5726.1  263.67  5762.2  262.59  5832.4  264.16  5962.1   265.7  6091.8  267.03
  6632.9  272.68  6927.5  277.87    7156  279.51  7226.4   283.2  7415.6  287.57
#Mann= 11 ,-1 , 0
  3571.3     .07       0  3931.3     .05       0  4508.2    .035       0
    4621     .05       0  4997.3     .05       0  5004.9     .05       0
  5726.1     .15       0  5832.4    .035       0  5962.1     .05       0
  6091.8     .07       0  6632.9    .035       0
Bank Sta=4997.3,5004.9
XS Rating Curve= 0 ,0
Exp/Cntr=0.3,0.1

Type RM Length L Ch R = 1 ,6547    ,1682,1682,1682
BEGIN DESCRIPTION:
XS6392
END DESCRIPTION:
XS GIS Cut Line= 3
      2478171.99     13707756.32      2479289.58     13707061.89
      2480830.19     13705141.56
#Sta/Elev= 30
  3704.6   277.5    3857  279.84  3947.5  280.18  3955.4  280.04  4067.5  275.56
  4133.8  272.22  4185.5  269.15  4421.4  257.48  4490.7  256.29  4818.1  251.41
  4943.3  253.43  4970.4  251.24    4997  241.05  4997.5  240.55  5005.3  241.05
  5029.2  253.09  5050.7   254.8    5406  250.86  5456.5  252.88  5692.7  256.44
  5809.9  259.36  5982.1  263.12  6209.3  259.65    6659   266.4  6754.9  268.24
  6875.6  270.84  6964.8  272.21  7369.5  281.62  7442.3  280.88  7482.3  280.42
#Mann= 19 ,-1 , 0
  3704.6     .05       0    3857     .07       0  3947.5     .05       0
  3955.4     .07       0  4067.5     .05       0  4133.8     .07       0
  4185.5     .05       0  4421.4    .035       0  4490.7     .05       0
    4997     .05       0  5005.3     .05       0  5456.5     .15       0
  5692.7    .035       0  5809.9     .07       0    6659     .05       0
  6754.9     .07       0  6875.6    .035       0  6964.8     .05       0
  7442.3     .07       0
Bank Sta=4997,5005.3
XS Rating Curve= 0 ,0
Exp/Cntr=0.3,0.1

Type RM Length L Ch R = 1 ,4865    ,1341,1341,1341
BEGIN DESCRIPTION:
XS6391
END DESCRIPTION:
XS GIS Cut Line= 3
      2478606.01     13708971.59      2480732.73     13706888.28
      2481796.11     13705032.79
#Sta/Elev= 30
  2195.4  289.03  2306.5  286.11  2461.7  282.02  2856.3  275.21    2915  274.16
  3049.7  270.88  3237.8  265.69  3374.5  262.34  4331.7  251.39  4468.5  250.87
  4605.2  250.22    4837  251.97    4936  243.58  4957.2   246.9  4973.6   237.7
  4974.1   237.2  4983.3   237.7  4992.6  250.18  4999.6  250.89  5152.2   249.2
  5420.5  252.51  5522.1  255.84  5556.6  262.88  5593.2  264.09  5816.4  259.68
  6024.1  256.58    6223   258.4  6643.1   266.7  6979.3  283.72  7311.1  294.71
#Mann= 20 ,-1 , 0
  2195.4     .05       0  2306.5     .07       0  2461.7     .05       0
  2856.3     .07       0    2915     .05       0  3049.7     .07       0
  3237.8    .035       0  3374.5     .05       0  4331.7     .12       0
  4468.5    .035       0  4605.2     .12       0  4973.6     .05       0
  4983.3     .12       0  5152.2     .05       0  5420.5     .12       0
  5816.4     .05       0  6024.1    .033       0    6223     .07       0
  6643.1     .05       0  6979.3     .07       0
Bank Sta=4973.6,4983.3
XS Rating Curve= 0 ,0
Exp/Cntr=0.3,0.1

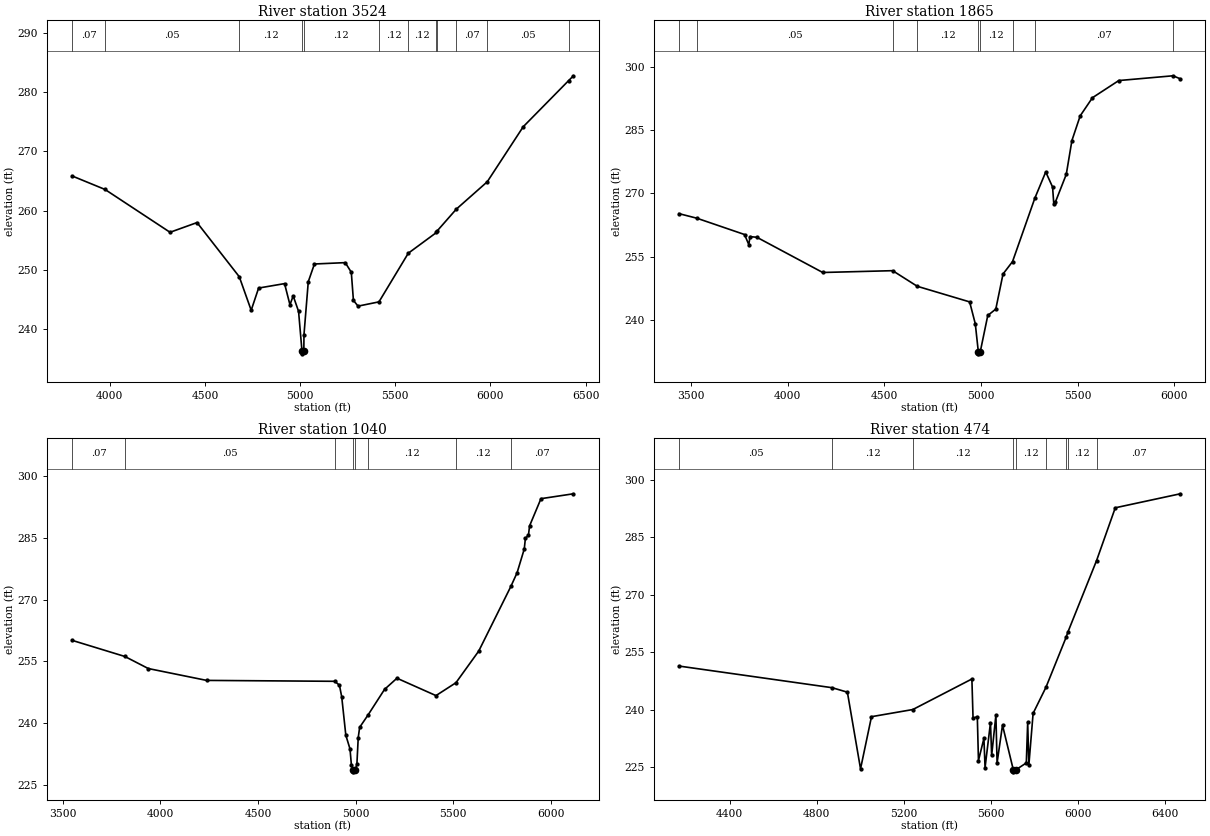
Type RM Length L Ch R = 1 ,3524    ,1659,1659,1659
BEGIN DESCRIPTION:
E20865
END DESCRIPTION:
XS GIS Cut Line= 3
      2480788.85     13707984.81      2481355.14     13706794.32
      2481824.89     13705565.25
#Sta/Elev= 30
  3802.1  265.85  3975.2  263.57  4316.9  256.34  4458.7  257.98  4680.6  248.84
  4743.2  243.18  4782.2  246.93  4918.5  247.68  4946.8  244.11  4963.9   245.6
  4992.1     243    5010  236.33  5010.5  235.83  5019.8  236.33  5020.4     239
  5043.1     248  5075.4  250.99  5237.4  251.22  5269.1   249.6  5280.3  244.85
  5304.6  243.88  5414.5   244.6  5568.6  252.81  5716.7  256.31  5721.1   256.6
  5820.9  260.25  5983.3  264.86  6172.3  274.15  6411.3  281.95  6436.2  282.75
#Mann= 12 ,-1 , 0
  3802.1     .07       0  3975.2     .05       0  4680.6     .12       0
    5010     .05       0  5019.8     .12       0  5414.5     .12       0
  5568.6     .12       0  5716.7     .12       0  5721.1     .12       0
  5820.9     .07       0  5983.3     .05       0  6411.3     .07       0
Bank Sta=5010,5019.8
XS Rating Curve= 0 ,0
Exp/Cntr=0.3,0.1

Type RM Length L Ch R = 1 ,1865    ,825,825,825
BEGIN DESCRIPTION:
XS6390
END DESCRIPTION:
XS GIS Cut Line= 3
      2480949.78     13708049.08       2481817.8     13707300.61
      2482685.67     13706139.83
#Sta/Elev= 30
  3436.2  265.19  3529.1   264.1  3775.7  260.24  3797.7  257.85  3804.3  259.74
  3839.4  259.59  4180.5  251.24  4542.4  251.67  4669.8  247.97    4941  244.27
  4970.2  239.09  4985.9  232.46  4986.4  231.96    4996  232.46  5034.8  241.05
  5076.4  242.57  5113.8  250.88    5163  253.82  5278.4  268.84  5334.9  275.07
  5370.3  271.49  5376.6  267.46  5384.9  267.93  5441.2  274.49  5470.4  282.51
  5513.3  288.37  5576.7  292.66  5713.1  296.73    5994  297.86  6031.7  297.13
#Mann= 9 ,-1 , 0
  3436.2     .07       0  3529.1     .05       0  4542.4     .12       0
  4669.8     .12       0  4985.9     .05       0    4996     .12       0
    5163     .12       0  5278.4     .07       0    5994    .035       0
Bank Sta=4985.9,4996
XS Rating Curve= 0 ,0
Exp/Cntr=0.3,0.1

Type RM Length L Ch R = 1 ,1040    ,566,566,566
BEGIN DESCRIPTION:
E20864
END DESCRIPTION:
XS GIS Cut Line= 4
       2480962.6     13708300.08      2482043.67     13707463.54
      2482371.85     13707154.67      2482757.93     13706511.21
#Sta/Elev= 30
  3547.8  260.11  3818.2  256.19  3938.3  253.26  4237.1  250.38    4893  250.16
  4917.3  249.22    4929  246.37    4950  237.06  4971.4  233.74  4978.3  229.96
  4987.4  228.68  4987.9  228.18  4997.6  228.68  5006.6  229.97  5013.5  236.48
  5020.8  238.98  5063.3  241.95  5148.3   248.2  5211.8  250.91  5411.7  246.69
  5514.1  249.82  5630.7   257.5  5795.3   273.2    5827   276.5  5863.9  282.29
  5869.7  284.87  5885.3  285.62  5891.1   287.9  5949.4   294.5  6115.8  295.69
#Mann= 8 ,-1 , 0
  3547.8     .07       0  3818.2     .05       0    4893     .12       0
  4987.4     .05       0  4997.6     .12       0  5063.3     .12       0
  5514.1     .12       0  5795.3     .07       0
Bank Sta=4987.4,4997.6
XS Rating Curve= 0 ,0
Exp/Cntr=0.3,0.1

Type RM Length L Ch R = 1 ,474     ,0,0,0
BEGIN DESCRIPTION:
E20863
END DESCRIPTION:
XS GIS Cut Line= 4
      2482178.81     13708653.95      2482281.76     13707727.37
      2482410.46     13707553.63      2482815.87     13706472.54
#Sta/Elev= 30
  4166.8  251.36  4870.6   245.7  4940.5  244.53  5000.9   224.5  5051.2  238.13
  5241.2     240  5512.4  247.98  5517.7  237.74  5537.3  238.13  5542.6  226.66
  5567.6  232.45  5572.9  224.85  5597.8  236.57  5603.2  228.02  5622.7  238.55
  5628.1  226.06    5653  235.91  5702.8  224.22  5703.3  223.72  5713.6  224.22
  5762.4  226.05  5768.7  236.69    5774  225.45  5793.6     239  5852.5   245.8
  5945.2  258.87  5952.6  260.13  6085.1  278.92    6171  292.71  6469.9  296.37
#Mann= 9 ,-1 , 0
  4166.8     .05       0  4870.6     .12       0  5241.2     .12       0
  5702.8     .05       0  5713.6     .12       0  5852.5     .12       0
  5945.2     .12       0  5952.6     .12       0  6085.1     .07       0
Bank Sta=5702.8,5713.6
XS Rating Curve= 0 ,0
Exp/Cntr=0.3,0.1

Chan Stop Cuts=-1
Use User Specified Reach Order=0
Composite Channel Slope=5