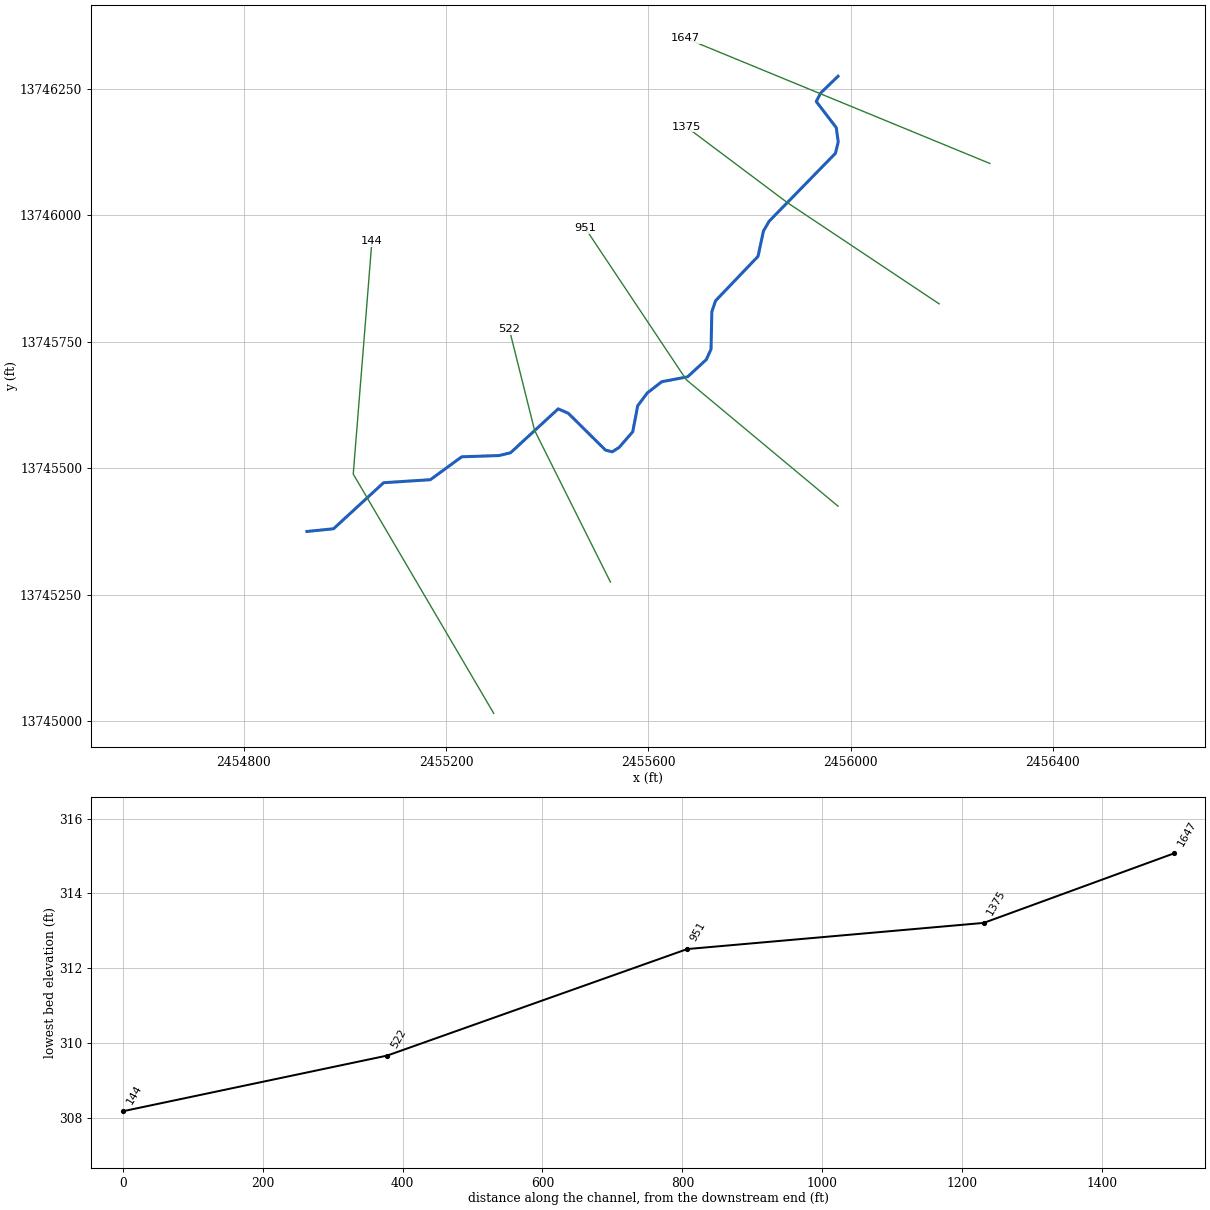
--- Stream0301.prj (project) ---

Proj Title=Stream0301 Base Level Engineering
Current Plan=p01
Default Exp/Contr=0.3,0.1
English Units
Geom File=g01
Flow File=f01
Plan File=p01
BEGIN DESCRIPTION:
Stream0301
END DESCRIPTION:

--- Stream0301.p01 (plan) ---

Plan Title=Multiple Run
Short Identifier=Multiple
Geom File=g01
Flow File=f01
Subcritical Flow
K Sum by GR= 0
Std Step Tol= 0.01
Critical Tol= 0.01
Num of Std Step Trials= 20
Max Error Tol= 0.3
Flow Tol Ratio= 0.001
Split Flow NTrial= 30
Split Flow Tol= 0.02
Split Flow Ratio= 0.02
Log Output Level= 0
Friction Slope Method= 1
Unsteady Friction Slope Method= 2
Unsteady Bridges Friction Slope Method= 1
Parabolic Critical Depth
Global Vel Dist=  1 , 1 , 1
Global Log Level= 0
CheckData=True
Encroach Param= -1, 0, 0, 0
BEGIN DESCRIPTION:
Multiple Run
END DESCRIPTION:

--- Stream0301.f01 (steady flow) ---

Flow Title=Multiple
Number of Profiles=7
Profile Names=10-year,25-year,50-year,1pct_min,100-year,1pct_plu,500-year
River Rch & RM= Stream0301,Reach-1,1647
     489     770    1018     652    1301    2596    2103
Boundary for River Rch & Prof#=Stream0301,Reach-1,1
Up Type=0
Dn Type=3
Dn Slope=0.005
Boundary for River Rch & Prof#=Stream0301,Reach-1,2
Up Type=0
Dn Type=3
Dn Slope=0.005
Boundary for River Rch & Prof#=Stream0301,Reach-1,3
Up Type=0
Dn Type=3
Dn Slope=0.005
Boundary for River Rch & Prof#=Stream0301,Reach-1,4
Up Type=0
Dn Type=3
Dn Slope=0.005
Boundary for River Rch & Prof#=Stream0301,Reach-1,5
Up Type=0
Dn Type=3
Dn Slope=0.005
Boundary for River Rch & Prof#=Stream0301,Reach-1,6
Up Type=0
Dn Type=3
Dn Slope=0.005
Boundary for River Rch & Prof#=Stream0301,Reach-1,7
Up Type=0
Dn Type=3
Dn Slope=0.005

--- Stream0301.g01 (geometry) ---

Geom Title=Existing Conditions

River Reach=Stream0301,Reach-1
Reach XY= 30
      2455975.00     13746275.00      2455940.56     13746241.83
      2455931.95     13746225.12      2455971.57     13746173.36
      2455975.36     13746145.15      2455969.90     13746122.71
      2455838.63     13745988.21      2455827.53     13745968.95
      2455816.82     13745918.96      2455732.88     13745831.16
      2455725.53     13745809.77      2455723.90     13745735.33
      2455714.61     13745714.90      2455677.55     13745680.75
      2455626.46     13745671.10      2455597.87     13745648.82
      2455578.89     13745623.50      2455569.13     13745572.16
      2455542.04     13745541.05      2455528.58     13745532.50
      2455515.13     13745535.95      2455441.67     13745608.73
      2455421.67     13745617.38      2455327.43     13745530.55
      2455304.95     13745525.13      2455230.98     13745522.64
      2455169.02     13745477.36      2455076.50     13745471.39
      2454977.51     13745380.33      2454925.00     13745375.00

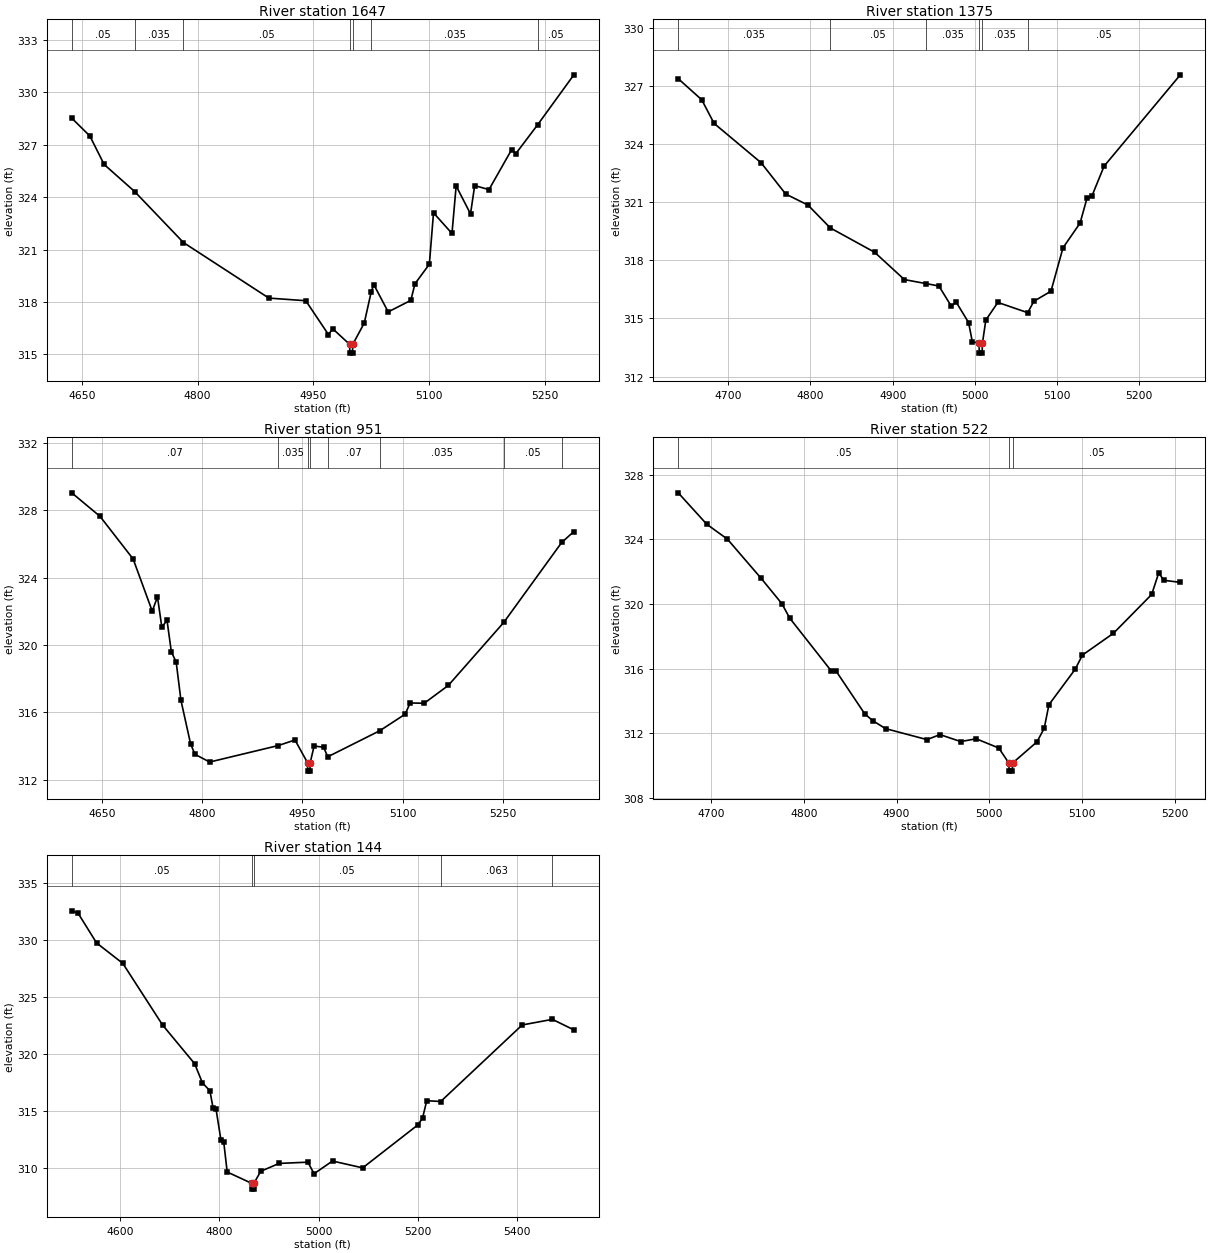
Type RM Length L Ch R = 1,1647,272,272,272
BEGIN DESCRIPTION:
XS6402
END DESCRIPTION:
XS GIS Cut Line= 2
      2456275.21     13746102.59      2455674.03     13746350.01
#Sta/Elev= 30
  4637.1  328.52  4660.5  327.50  4679.0  325.87  4718.5  324.32  4781.7  321.40
  4892.3  318.22  4940.1  318.07  4969.5  316.13  4974.9  316.47  4996.9  315.57
  4997.1  315.07  5000.6  315.07  5000.9  315.57  5015.8  316.79  5024.9  318.59
  5028.2  318.99  5046.8  317.43  5076.1  318.09  5081.5  319.04  5100.1  320.16
  5105.5  323.10  5129.4  321.92  5134.8  324.64  5153.4  323.04  5158.8  324.66
  5177.3  324.43  5206.7  326.72  5212.1  326.49  5240.3  328.14  5287.2  331.00
#Mann=7,-1,0
  4637.1    0.05       0  4718.5   0.035       0  4781.7    0.05       0
  4996.9    0.05       0  5000.9    0.05       0  5024.9   0.035       0
  5240.3    0.05       0
Bank Sta=4996.9,5000.9
Exp/Cntr=0.3,0.1

Type RM Length L Ch R = 1,1375,424,424,424
BEGIN DESCRIPTION:
Stream0301 3.0
END DESCRIPTION:
XS GIS Cut Line= 3
      2456175.03     13745824.98      2455875.00     13746025.00
      2455674.99     13746175.01
#Sta/Elev= 30
  4639.2  327.39  4667.8  326.30  4682.8  325.08  4739.9  323.05  4769.9  321.43
  4797.0  320.86  4824.1  319.68  4878.1  318.42  4914.2  317.01  4940.9  316.80
  4956.2  316.68  4971.2  315.64  4977.3  315.84  4992.3  314.79  4996.8  313.81
  5005.1  313.71  5005.3  313.21  5008.8  313.21  5009.1  313.71  5013.3  314.92
  5027.9  315.83  5064.2  315.30  5071.7  315.89  5092.5  316.41  5107.1  318.65
  5127.9  319.93  5136.2  321.20  5142.5  321.35  5157.1  322.87  5249.8  327.59
#Mann=6,-1,0
  4639.2   0.035       0  4824.1    0.05       0  4940.9   0.035       0
  5005.1   0.035       0  5009.1   0.035       0  5064.2    0.05       0
Bank Sta=5005.1,5009.1
Exp/Cntr=0.3,0.1

Type RM Length L Ch R = 1,951,429,429,429
BEGIN DESCRIPTION:
Stream0301 2.0
END DESCRIPTION:
XS GIS Cut Line= 3
      2455974.99     13745425.01      2455675.00     13745675.00
      2455474.97     13745975.04
#Sta/Elev= 30
  4605.2  329.04  4647.5  327.64  4697.0  325.11  4725.6  322.01  4733.4  322.86
  4739.9  321.07  4747.7  321.46  4754.2  319.59  4761.4  318.99  4768.5  316.72
  4782.9  314.14  4789.4  313.51  4811.5  313.05  4914.2  314.03  4939.1  314.36
  4957.9  313.01  4958.1  312.51  4961.6  312.51  4961.9  313.01  4967.7  314.00
  4982.0  313.93  4988.1  313.36  5066.0  314.91  5103.9  315.89  5111.4  316.56
  5132.4  316.54  5168.5  317.60  5251.4  321.34  5338.1  326.09  5356.3  326.74
#Mann=8,-1,0
  4605.2    0.07       0  4914.2   0.035       0  4957.9    0.05       0
  4961.9   0.035       0  4988.1    0.07       0  5066.0   0.035       0
  5251.4    0.05       0  5338.1   0.035       0
Bank Sta=4957.9,4961.9
Exp/Cntr=0.3,0.1

Type RM Length L Ch R = 1,522,378,378,378
BEGIN DESCRIPTION:
Stream0301 1.0
END DESCRIPTION:
XS GIS Cut Line= 3
      2455524.99     13745275.02      2455375.00     13745575.00
      2455325.01     13745774.96
#Sta/Elev= 30
  4664.5  326.88  4695.2  324.94  4717.6  324.01  4753.9  321.59  4776.3  320.02
  4784.7  319.13  4829.4  315.87  4835.0  315.83  4865.7  313.20  4874.1  312.79
  4888.1  312.29  4932.8  311.61  4946.8  311.92  4969.1  311.49  4985.9  311.66
  5010.2  311.09  5021.1  310.16  5021.3  309.66  5024.8  309.66  5025.1  310.16
  5051.4  311.47  5059.2  312.31  5064.3  313.77  5092.7  315.97  5100.4  316.84
  5133.9  318.19  5175.1  320.59  5182.8  321.94  5188.0  321.47  5206.0  321.34
#Mann=3,-1,0
  4664.5    0.05       0  5021.1    0.05       0  5025.1    0.05       0
Bank Sta=5021.1,5025.1
Exp/Cntr=0.3,0.1

Type RM Length L Ch R = 1,144,0,0,0
BEGIN DESCRIPTION:
XS6401
END DESCRIPTION:
XS GIS Cut Line= 3
      2455294.29     13745015.33      2455016.49     13745488.45
      2455053.39     13745948.53
#Sta/Elev= 30
  4503.5  332.53  4516.2  332.32  4553.4  329.72  4606.2  327.93  4686.3  322.53
  4750.7  319.15  4766.4  317.47  4781.4  316.78  4787.8  315.28  4793.6  315.22
  4803.5  312.51  4809.3  312.28  4816.2  309.67  4865.9  308.67  4866.2  308.17
  4869.7  308.17  4869.9  308.67  4883.6  309.73  4920.6  310.42  4978.6  310.53
  4991.0  309.52  5028.1  310.63  5088.8  310.03  5199.2  313.77  5209.2  314.37
  5217.7  315.91  5245.8  315.84  5409.8  322.54  5470.5  323.03  5513.7  322.11
#Mann=5,-1,0
  4503.5    0.05       0  4865.9    0.05       0  4869.9    0.05       0
  5245.8   0.063       0  5470.5   0.094       0
Bank Sta=4865.9,4869.9
Exp/Cntr=0.3,0.1

Chan Stop Cuts=-1