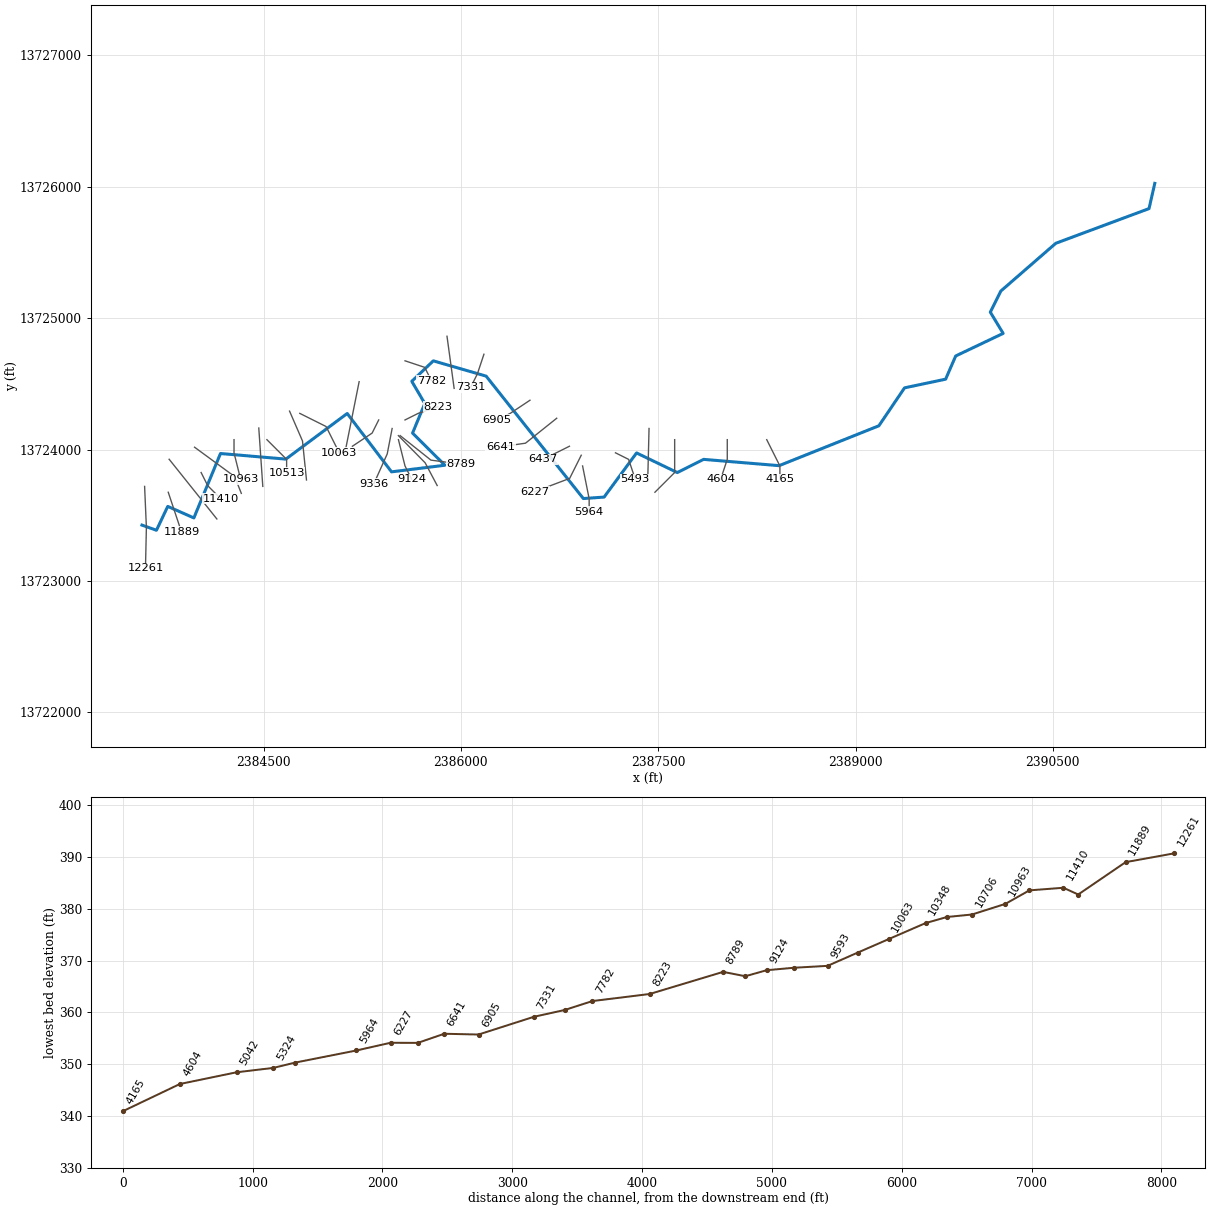
--- Stream0303.prj (project) ---

Proj Title=Stream0303 Base Level Engineering
Current Plan=p01
Default Exp/Contr=0.3,0.1
English Units
Geom File=g01
Flow File=f01
Plan File=p01
Y Axis Title=Elevation
X Axis Title(PF)=Main Channel Distance
X Axis Title(XS)=Station
BEGIN DESCRIPTION:
Stream0303
END DESCRIPTION:
DSS Export Rating Curves= 0
DSS Export Rating Curve Sorted= 0
DSS Export Volume Flow Curves= 0
DXF OffsetX= 0
DXF OffsetY= 0
DXF ScaleX= 1
DXF ScaleY= 10

--- Stream0303.p01 (plan) ---

Plan Title=Multiple Run
Program Version=4.10
Short Identifier=Multiple
Geom File=g01
Flow File=f01
Subcritical Flow
K Sum by GR= 0
Std Step Tol= 0.01
Critical Tol= 0.01
Num of Std Step Trials= 20
Max Error Tol= 0.3
Flow Tol Ratio= 0.001
Split Flow NTrial= 30
Split Flow Tol= 0.02
Split Flow Ratio= 0.02
Log Output Level= 0
Friction Slope Method= 1
Unsteady Friction Slope Method= 2
Unsteady Bridges Friction Slope Method= 1
Parabolic Critical Depth
Global Vel Dist= 1 , 1 , 1
Global Log Level= 0
CheckData=True
Encroach Param=-1 ,0,0, 0
BEGIN DESCRIPTION:
Multiple Run
END DESCRIPTION:
Computation Interval=1HOUR
Output Interval=1HOUR
Run HTab= 0
Run UNet= 0
Run PostProcess= 0
Run WQNet= 0
UNET Theta= 1
UNET Theta Warmup= 1
UNET ZTol= 0.02
UNET ZSATol= 0.05
UNET MxIter= 20
UNET MaxInSteps= 0
UNET DtIC= 0
UNET DtMin= 0
UNET MaxCRTS= 20
UNET WFStab= 2
UNET SFStab= 1
UNET WFX= 1
UNET SFX= 1
UNET DSS MLevel= 4
UNET DZMax Abort= 100
UNET Convert EG Bridges= 0
UNET Use Existing IB Tables=-1
UNET Froude Reduction=False
UNET Froude Limit= 1
UNET Froude Power= 10
UNET Time Slicing=0,0, 5
UNET Junction Losses=0
Instantaneous Interval=1HOUR
Write IC File= 0
Write IC File at Sim End=0
Echo Input=False
Echo Parameters=False
Echo Output=False
Write Detailed= 0
WQ AD Non Conservative
WQ ULTIMATE=-1
WQ Max Comp Step=1HOUR
WQ Output Interval=15MIN
WQ Output Selected Increments= 0
WQ Output face flow=0
WQ Output face velocity=0
WQ Output face area=0
WQ Output face dispersion=0
WQ Output cell volume=0
WQ Output cell surface area=0
WQ Output cell continuity=0
WQ Output cumulative cell continuity=0
WQ Output face conc=0
WQ Output face dconc_dx=0
WQ Output face courant=0
WQ Output face peclet=0
WQ Output face adv mass=0
WQ Output face disp mass=0
WQ Output cell mass=0
WQ Output cell source sink temp=0
WQ Output cell source sink nsm=0
WQ Output MaxMinRange=-1
WQ Daily Max Min Mean=-1
WQ Daily Range=0
WQ Daily Time=0
WQ Create Restart=0
WQ Fixed Restart=0
WQ System Summary=0
WQ Use Fixed Temperature=0
Sorting and Armoring Iterations= 10
XS Update Threshold= 0.02
Hydraulics Update Threshold= 0.02
Energy Slope Method= 1
Volume Change Method= 0
XS Weighting Method= 0
Number of US Weighted Cross Sections= 1
Number of DS Weighted Cross Sections= 1
Upstream XS Weight=0.25
Main XS Weight=0.5
Downstream XS Weight=0.25
Number of DS XS's Weighted with US Boundary= 1
Upstream Boundary Weight= 1
Weight of XSs Associated with US Boundary= 0
Number of US XS's Weighted with DS Boundary= 1
Downstream Boundary Weight= 0.5
Weight of XSs Associated with DS Boundary= 0.5
Sediment Output Level= 4
Mass or Volume Output= 0
Output Increment Type= 1
Profile and TS Output Increment= 10
XS Output Flag= 0
XS Output Increment= 10
Disregard all LS=0
Disregard all Conn=0
Disregard all Breaches=0
Disregard all Pumps=0

--- Stream0303.f01 (steady flow) ---

Flow Title=Multiple
Number of Profiles=7
Profile Names=10-year,25-year,50-year,1pct_min,100-year,1pct_plu,500-year
River Rch & RM= Stream0303,Reach-1,12261
     787    1296    1765    1164    2323    4634    3986
River Rch & RM= Stream0303,Reach-1,10063
     917    1518    2074    1372    2737    5461    4722
River Rch & RM= Stream0303,Reach-1,5042
    1115    1865    2566    1707    3406    6795    5948
River Rch & RM= Stream0303,Reach-1,3699
    1217    2037    2804    1866    3723    7428    6506
River Rch & RM= Stream0303,Reach-1,2442
    1335    2240    3089    2059    4108    8196    7200
Boundary for River Rch & Prof#=Stream0303,Reach-1,1
Up Type=0
Dn Type=3
Dn Slope=0.005
Boundary for River Rch & Prof#=Stream0303,Reach-1,2
Up Type=0
Dn Type=3
Dn Slope=0.005
Boundary for River Rch & Prof#=Stream0303,Reach-1,3
Up Type=0
Dn Type=3
Dn Slope=0.005
Boundary for River Rch & Prof#=Stream0303,Reach-1,4
Up Type=0
Dn Type=3
Dn Slope=0.005
Boundary for River Rch & Prof#=Stream0303,Reach-1,5
Up Type=0
Dn Type=3
Dn Slope=0.005
Boundary for River Rch & Prof#=Stream0303,Reach-1,6
Up Type=0
Dn Type=3
Dn Slope=0.005
Boundary for River Rch & Prof#=Stream0303,Reach-1,7
Up Type=0
Dn Type=3
Dn Slope=0.005

--- Stream0303.g01 (geometry) ---

Geom Title=Existing Conditions

River Reach=Stream0303,Reach-1
Reach XY= 30
      2383575.00     13723425.00      2383685.44     13723385.83
      2383771.31     13723567.35      2383969.83     13723479.59
      2384172.28     13723969.60      2384669.14     13723927.06
      2385135.49     13724274.07      2385472.69     13723830.08
      2385878.03     13723880.47      2385632.31     13724124.90
      2385725.49     13724350.04      2385626.58     13724518.95
      2385790.16     13724674.62      2386191.68     13724558.36
      2386930.65     13723626.96      2387088.67     13723638.22
      2387335.43     13723973.96      2387644.95     13723824.74
      2387844.98     13723925.04      2388419.07     13723877.24
      2389177.44     13724180.52      2389372.69     13724469.18
      2389685.12     13724535.22      2389761.45     13724711.63
      2390122.42     13724883.48      2390024.60     13725045.13
      2390104.46     13725205.53      2390522.70     13725569.17
      2391231.39     13725833.00      2391275.00     13726025.00

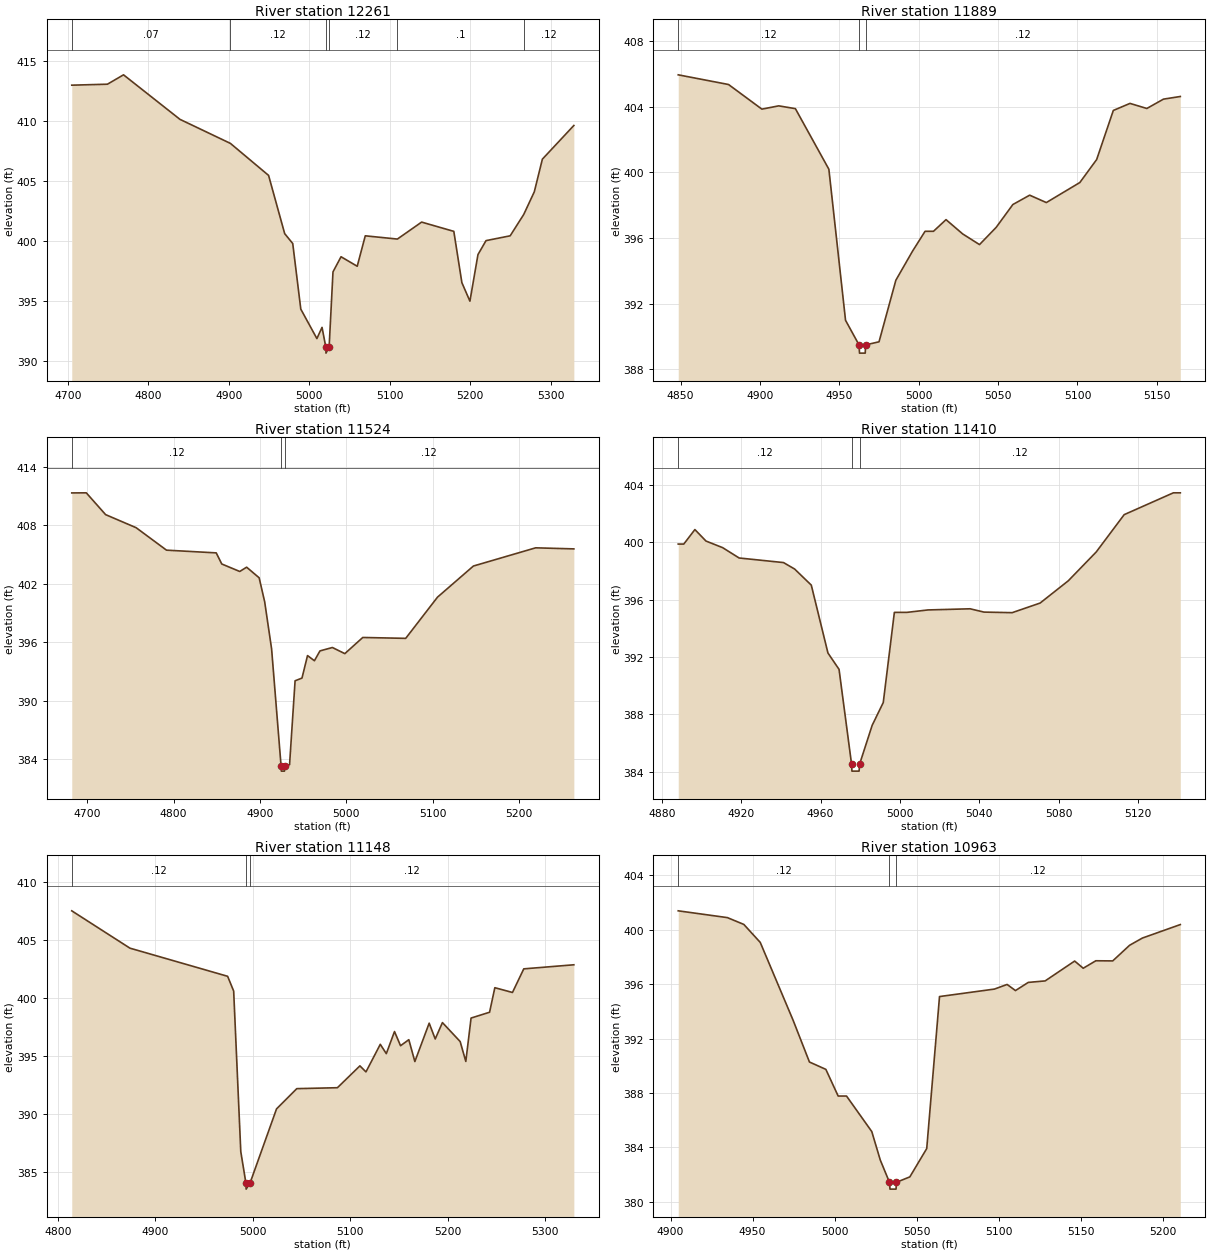
Type RM Length L Ch R = 1,12261,372,372,372
BEGIN DESCRIPTION:
XS6420
END DESCRIPTION:
XS GIS Cut Line= 3
      2383595.31     13723719.25      2383608.87     13723407.29
      2383601.83     13723095.92
#Sta/Elev= 30
  4705.0  412.95  4749.3  413.03  4769.3  413.81  4839.4  410.11  4902.1  408.11
  4949.5  405.45  4969.5  400.61  4979.5  399.79  4989.5  394.34  5009.5  391.89
  5015.9  392.82  5020.6  391.18  5020.8  390.68  5024.7  391.18  5029.5  397.43
  5039.5  398.69  5059.6  397.90  5069.6  400.43  5109.5  400.16  5139.6  401.57
  5179.6  400.80  5189.6  396.54  5199.6  395.00  5209.6  398.87  5219.6  400.03
  5249.6  400.43  5266.5  402.21  5279.6  404.09  5289.6  406.80  5328.7  409.60
#Mann=6,-1,0
  4705.0    0.07       0  4902.1    0.12       0  5020.6    0.05       0
  5024.7    0.12       0  5109.5     0.1       0  5266.5    0.12       0
Bank Sta=5020.6,5024.7
Exp/Cntr=0.3,0.1

Type RM Length L Ch R = 1,11889,365,365,365
BEGIN DESCRIPTION:
Stream0303 25.0
END DESCRIPTION:
XS GIS Cut Line= 3
      2383774.99     13723675.03      2383825.00     13723525.00
      2383875.01     13723374.96
#Sta/Elev= 30
  4848.5  405.94  4880.2  405.35  4901.2  403.85  4911.8  404.05  4922.3  403.88
  4943.4  400.19  4953.9  390.99  4962.4  389.49  4962.7  388.99  4966.3  388.99
  4966.5  389.49  4975.0  389.68  4985.6  393.43  4996.1  395.20  5004.0  396.41
  5009.3  396.41  5017.2  397.12  5027.7  396.25  5038.3  395.60  5048.8  396.65
  5059.3  398.04  5069.9  398.61  5080.4  398.16  5101.5  399.38  5112.1  400.78
  5122.6  403.77  5133.1  404.20  5143.7  403.89  5154.2  404.46  5164.8  404.62
#Mann=3,-1,0
  4848.5    0.12       0  4962.4    0.05       0  4966.5    0.12       0
Bank Sta=4962.4,4966.5
Exp/Cntr=0.3,0.1

Type RM Length L Ch R = 1,11524,114,114,114
BEGIN DESCRIPTION:
XS6419
END DESCRIPTION:
XS GIS Cut Line= 2
      2383781.82     13723926.04      2384144.61     13723471.71
#Sta/Elev= 30
  4682.0  411.33  4698.8  411.34  4721.2  409.10  4756.5  407.76  4791.7  405.45
  4849.3  405.17  4855.7  404.03  4876.5  403.26  4884.5  403.70  4899.0  402.61
  4905.4  400.14  4913.4  395.31  4924.4  383.25  4924.7  382.75  4928.3  382.75
  4928.5  383.25  4934.2  383.41  4940.6  392.03  4948.6  392.31  4955.0  394.62
  4963.0  394.09  4969.4  395.10  4983.8  395.45  4998.2  394.82  5019.0  396.48
  5068.7  396.39  5105.5  400.62  5147.1  403.82  5219.2  405.69  5263.4  405.58
#Mann=3,-1,0
  4682.0    0.12       0  4924.4    0.05       0  4928.5    0.12       0
Bank Sta=4924.4,4928.5
Exp/Cntr=0.3,0.1

Type RM Length L Ch R = 1,11410,262,262,262
BEGIN DESCRIPTION:
Stream0303 24.0
END DESCRIPTION:
XS GIS Cut Line= 3
      2384025.00     13723825.00      2384075.00     13723725.00
      2384174.99     13723625.01
#Sta/Elev= 29
  4888.2  399.87  4891.0  399.87  4896.6  400.88  4902.2  400.08  4910.6  399.62
  4918.9  398.90  4941.3  398.58  4946.9  398.13  4955.3  397.01  4963.7  392.28
  4969.3  391.14  4975.6  384.55  4975.8  384.05  4979.4  384.05  4979.7  384.55
  4986.0  387.24  4991.6  388.83  4997.2  395.11  5003.5  395.11  5014.1  395.28
  5035.4  395.36  5042.4  395.13  5056.6  395.09  5070.7  395.76  5084.9  397.31
  5099.0  399.32  5113.1  401.92  5137.9  403.44  5141.4  403.44
#Mann=3,-1,0
  4888.2    0.12       0  4975.6    0.05       0  4979.7    0.12       0
Bank Sta=4975.6,4979.7
Exp/Cntr=0.3,0.1

Type RM Length L Ch R = 1,11148,185,185,185
BEGIN DESCRIPTION:
XS6418
END DESCRIPTION:
XS GIS Cut Line= 3
      2383975.08     13724017.61      2384280.24     13723793.83
      2384330.53     13723666.42
#Sta/Elev= 30
  4814.1  407.48  4873.8  404.27  4974.1  401.85  4980.3  400.58  4987.6  386.78
  4992.9  384.05  4993.1  383.55  4997.0  384.05  5024.3  390.45  5045.1  392.19
  5086.8  392.27  5109.9  394.15  5116.1  393.63  5130.8  396.00  5137.0  395.20
  5145.4  397.10  5151.6  395.88  5160.1  396.40  5166.3  394.52  5181.0  397.82
  5187.2  396.46  5194.6  397.87  5212.8  396.24  5218.6  394.53  5224.0  398.26
  5243.0  398.76  5248.4  400.87  5266.5  400.46  5278.1  402.49  5329.5  402.84
#Mann=3,-1,0
  4814.1    0.12       0  4992.9    0.05       0  4997.0    0.12       0
Bank Sta=4992.9,4997
Exp/Cntr=0.3,0.1

Type RM Length L Ch R = 1,10963,257,257,257
BEGIN DESCRIPTION:
Stream0303 23.0
END DESCRIPTION:
XS GIS Cut Line= 3
      2384275.00     13724074.99      2384275.00     13723975.00
      2384324.99     13723775.04
#Sta/Elev= 30
  4904.7  401.39  4934.7  400.89  4944.7  400.39  4954.7  399.07  4974.7  393.36
  4984.7  390.28  4994.7  389.74  5002.2  387.78  5007.3  387.78  5022.7  385.17
  5027.9  383.07  5033.5  381.44  5033.8  380.94  5037.5  380.94  5037.7  381.44
  5045.9  381.84  5056.2  383.92  5064.0  395.09  5097.5  395.64  5105.2  395.98
  5110.3  395.53  5118.1  396.13  5128.4  396.24  5146.4  397.70  5151.6  397.17
  5159.3  397.72  5169.6  397.71  5179.9  398.86  5187.7  399.39  5210.8  400.38
#Mann=3,-1,0
  4904.7    0.12       0  5033.5    0.05       0  5037.7    0.12       0
Bank Sta=5033.5,5037.7
Exp/Cntr=0.3,0.1

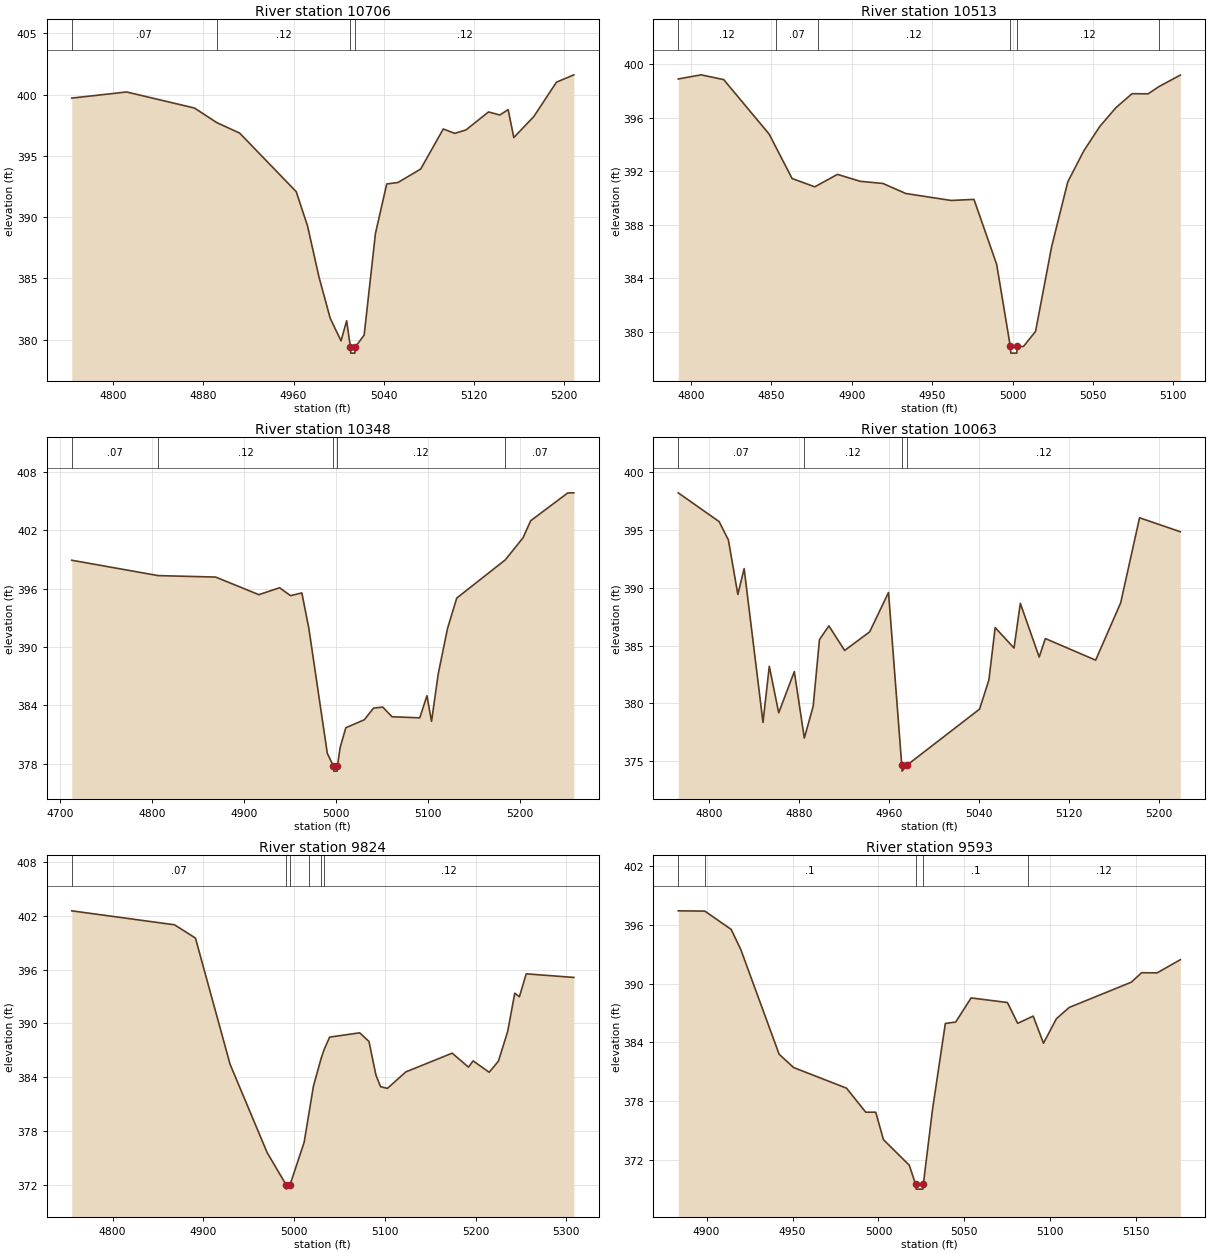
Type RM Length L Ch R = 1,10706,193,193,193
BEGIN DESCRIPTION:
XS6417
END DESCRIPTION:
XS GIS Cut Line= 2
      2384463.33     13724163.45      2384493.83     13723719.60
#Sta/Elev= 30
  4763.5  399.71  4812.1  400.21  4872.2  398.90  4892.0  397.71  4912.3  396.85
  4962.4  392.07  4972.4  389.28  4982.5  385.13  4992.5  381.74  5002.1  379.89
  5007.1  381.53  5010.4  379.39  5010.7  378.89  5014.4  378.89  5014.7  379.39
  5022.6  380.36  5032.6  388.66  5042.6  392.70  5052.6  392.82  5072.7  393.92
  5092.7  397.19  5102.8  396.83  5112.8  397.11  5132.8  398.58  5142.8  398.33
  5150.2  398.77  5155.2  396.49  5172.9  398.20  5193.0  401.01  5208.4  401.61
#Mann=4,-1,0
  4763.5    0.07       0  4892.0    0.12       0  5010.4    0.05       0
  5014.7    0.12       0
Bank Sta=5010.4,5014.7
Exp/Cntr=0.3,0.1

Type RM Length L Ch R = 1,10513,165,165,165
BEGIN DESCRIPTION:
Stream0303 22.0
END DESCRIPTION:
XS GIS Cut Line= 3
      2384524.97     13724075.03      2384675.00     13723925.00
      2384675.00     13723824.97
#Sta/Elev= 30
  4792.1  398.90  4806.3  399.21  4820.4  398.85  4848.7  394.77  4852.8  393.81
  4862.9  391.46  4877.0  390.84  4878.7  390.95  4891.1  391.77  4905.3  391.25
  4919.4  391.09  4933.6  390.34  4961.8  389.82  4976.0  389.90  4990.1  385.05
  4998.6  378.91  4998.9  378.41  5002.6  378.41  5002.9  378.91  5006.8  378.91
  5014.3  380.04  5024.3  386.37  5034.3  391.20  5044.3  393.53  5054.3  395.36
  5064.3  396.76  5074.3  397.80  5084.3  397.79  5091.0  398.33  5104.3  399.19
#Mann=6,-1,0
  4792.1    0.12       0  4852.8    0.07       0  4878.7    0.12       0
  4998.6    0.05       0  5002.9    0.12       0  5091.0    0.07       0
Bank Sta=4998.6,5002.9
Exp/Cntr=0.3,0.1

Type RM Length L Ch R = 1,10348,285,285,285
BEGIN DESCRIPTION:
XS6416
END DESCRIPTION:
XS GIS Cut Line= 3
      2384697.29     13724292.27      2384795.63     13724065.09
      2384825.97     13723768.38
#Sta/Elev= 30
  4712.4  398.91  4806.3  397.33  4868.8  397.18  4915.8  395.37  4938.3  396.08
  4950.2  395.27  4962.5  395.55  4970.1  391.93  4990.2  379.06  4996.9  377.73
  4997.2  377.23  5000.9  377.23  5001.2  377.73  5004.1  379.64  5010.3  381.69
  5030.4  382.51  5040.5  383.71  5050.5  383.81  5060.6  382.82  5090.7  382.71
  5098.5  384.98  5103.5  382.35  5110.8  387.24  5120.9  391.90  5130.9  395.02
  5183.7  398.95  5202.9  401.21  5211.3  402.97  5251.6  405.83  5258.2  405.84
#Mann=5,-1,0
  4712.4    0.07       0  4806.3    0.12       0  4996.9    0.05       0
  5001.2    0.12       0  5183.7    0.07       0
Bank Sta=4996.9,5001.2
Exp/Cntr=0.3,0.1

Type RM Length L Ch R = 1,10063,239,239,239
BEGIN DESCRIPTION:
Stream0303 21.0
END DESCRIPTION:
XS GIS Cut Line= 3
      2384774.98     13724275.01      2384975.00     13724175.00
      2385074.98     13723975.03
#Sta/Elev= 30
  4772.2  398.23  4808.6  395.74  4816.9  394.14  4825.3  389.43  4830.9  391.67
  4847.7  378.35  4853.3  383.21  4861.7  379.18  4875.6  382.75  4884.5  376.99
  4892.4  379.75  4898.0  385.52  4906.4  386.71  4920.4  384.58  4942.7  386.19
  4959.5  389.60  4971.3  374.63  4971.6  374.13  4975.7  374.63  5040.6  379.50
  5048.9  382.02  5054.5  386.56  5071.3  384.79  5076.9  388.66  5093.7  384.01
  5099.2  385.61  5144.0  383.74  5166.3  388.71  5183.1  396.07  5219.4  394.86
#Mann=4,-1,0
  4772.2    0.07       0  4884.5    0.12       0  4971.3    0.05       0
  4975.7    0.12       0
Bank Sta=4971.3,4975.7
Exp/Cntr=0.3,0.1

Type RM Length L Ch R = 1,9824,231,231,231
BEGIN DESCRIPTION:
XS6415
END DESCRIPTION:
XS GIS Cut Line= 2
      2385226.26     13724516.09      2385117.74     13723973.54
#Sta/Elev= 30
  4755.0  402.57  4868.3  401.01  4891.3  399.53  4929.5  385.44  4970.3  375.60
  4991.1  372.02  4991.4  371.52  4995.6  372.02  5011.1  376.75  5015.9  379.69
  5021.3  383.00  5029.9  386.14  5033.3  387.14  5039.2  388.48  5072.3  388.96
  5082.5  388.00  5090.2  384.25  5095.3  382.95  5102.8  382.76  5123.2  384.60
  5174.2  386.69  5192.2  385.13  5197.3  385.83  5215.0  384.56  5225.2  385.80
  5235.4  389.12  5243.2  393.38  5248.3  392.98  5255.8  395.54  5308.3  395.14
#Mann=6,-1,0
  4755.0    0.07       0  4991.1    0.05       0  4995.6    0.07       0
  5015.9    0.12       0  5029.9     0.1       0  5033.3    0.12       0
Bank Sta=4991.1,4995.6
Exp/Cntr=0.3,0.1

Type RM Length L Ch R = 1,9593,257,257,257
BEGIN DESCRIPTION:
Stream0303 20.0
END DESCRIPTION:
XS GIS Cut Line= 3
      2385375.02     13724225.04      2385325.00     13724125.00
      2385175.02     13724025.02
#Sta/Elev= 30
  4883.5  397.45  4899.0  397.42  4914.3  395.55  4919.9  393.49  4942.2  382.78
  4950.6  381.42  4981.4  379.31  4992.6  376.85  4998.4  376.85  5002.9  374.04
  5017.9  371.43  5021.6  369.48  5021.9  368.98  5025.8  368.98  5026.1  369.48
  5031.4  377.08  5038.9  385.93  5044.9  386.07  5053.9  388.54  5075.0  388.07
  5081.0  385.94  5087.2  386.45  5090.0  386.68  5096.0  383.91  5103.5  386.41
  5111.0  387.57  5147.1  390.15  5153.1  391.12  5162.1  391.10  5175.6  392.45
#Mann=5,-1,0
  4883.5    0.07       0  4899.0     0.1       0  5021.6    0.05       0
  5026.1     0.1       0  5087.2    0.12       0
Bank Sta=5021.6,5026.1
Exp/Cntr=0.3,0.1

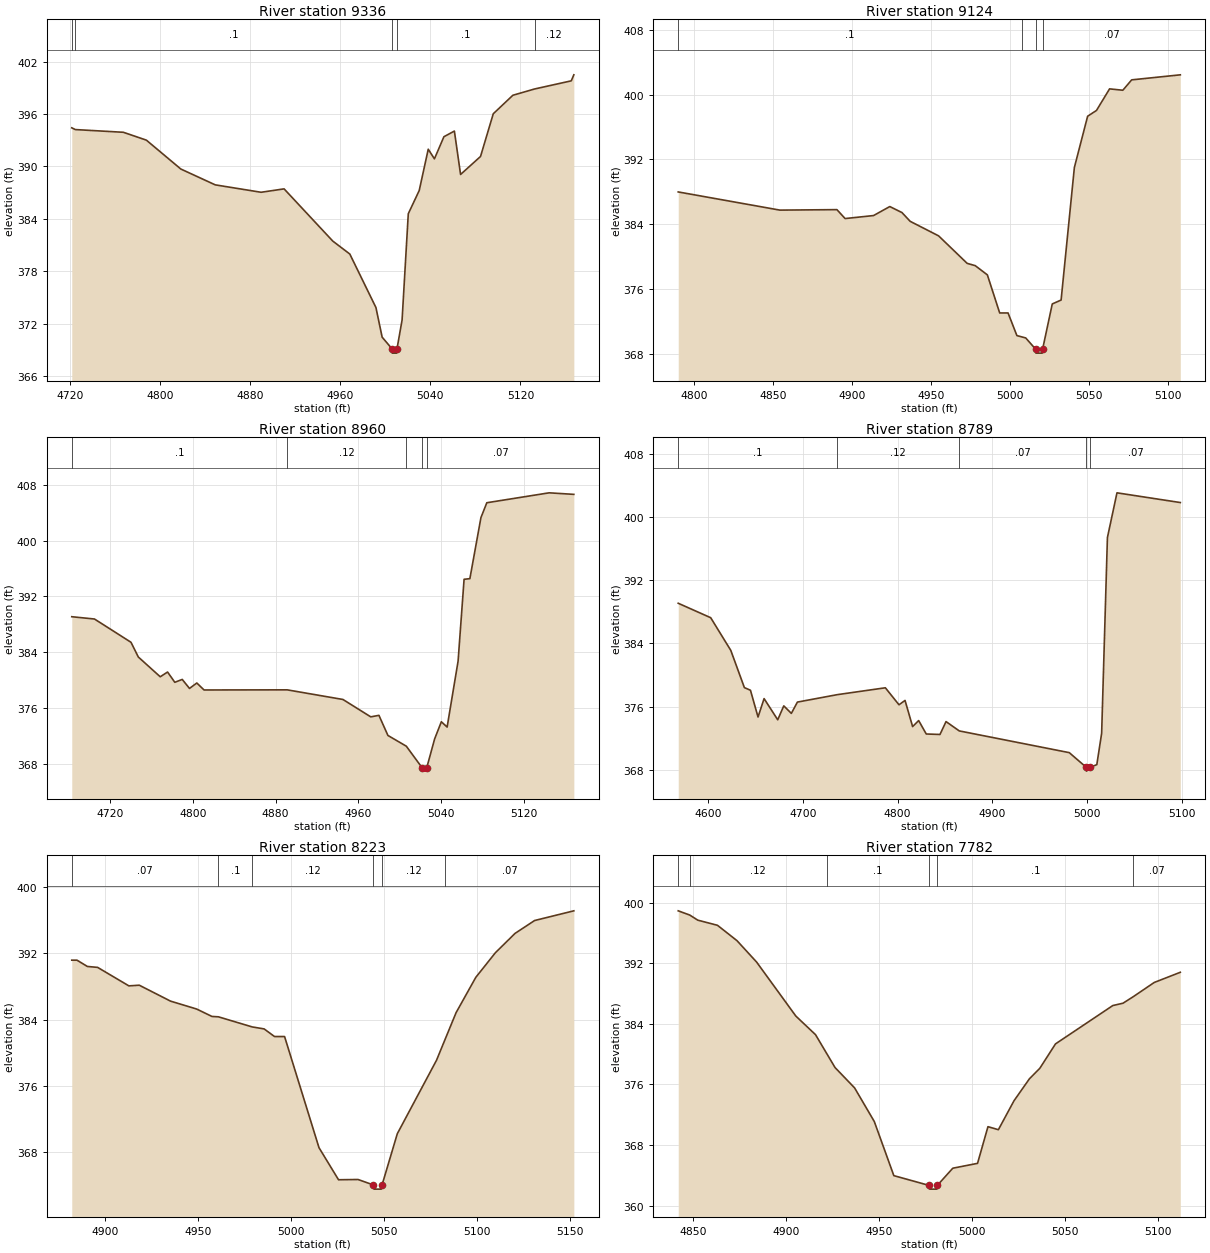
Type RM Length L Ch R = 1,9336,212,212,212
BEGIN DESCRIPTION:
XS6413
END DESCRIPTION:
XS GIS Cut Line= 3
      2385477.16     13724160.00      2385439.86     13723966.76
      2385338.23     13723739.78
#Sta/Elev= 30
  4721.9  394.42  4725.1  394.22  4767.7  393.91  4788.1  393.01  4818.7  389.70
  4849.2  387.89  4889.9  387.04  4910.3  387.43  4953.5  381.45  4968.6  379.97
  4991.8  373.84  4997.3  370.45  5006.0  369.12  5006.3  368.62  5010.2  368.62
  5010.5  369.12  5015.0  372.42  5020.5  384.58  5030.2  387.24  5038.2  391.97
  5043.7  390.87  5052.1  393.40  5061.4  394.05  5066.9  389.08  5084.6  391.14
  5095.9  396.03  5113.3  398.15  5132.6  398.87  5165.1  399.80  5167.4  400.49
#Mann=5,-1,0
  4721.9    0.07       0  4725.1     0.1       0  5006.0    0.05       0
  5010.5     0.1       0  5132.6    0.12       0
Bank Sta=5006,5010.5
Exp/Cntr=0.3,0.1

Type RM Length L Ch R = 1,9124,164,164,164
BEGIN DESCRIPTION:
Stream0303 19.0
END DESCRIPTION:
XS GIS Cut Line= 3
      2385525.00     13724075.00      2385575.00     13723875.00
      2385625.02     13723774.96
#Sta/Elev= 30
  4789.7  388.00  4854.1  385.76  4890.2  385.82  4895.4  384.72  4913.4  385.09
  4923.7  386.20  4931.4  385.46  4936.6  384.38  4954.6  382.59  4972.7  379.20
  4977.8  378.92  4985.5  377.78  4993.3  373.09  4998.6  373.09  5004.2  370.30
  5007.5  370.13  5009.8  370.01  5016.0  368.64  5016.3  368.14  5020.2  368.14
  5020.5  368.64  5026.6  374.20  5032.2  374.68  5040.6  391.01  5049.0  397.33
  5054.6  398.04  5062.9  400.70  5071.3  400.53  5076.9  401.81  5107.7  402.43
#Mann=4,-1,0
  4789.7     0.1       0  5007.5    0.07       0  5016.0    0.05       0
  5020.5    0.07       0
Bank Sta=5016,5020.5
Exp/Cntr=0.3,0.1

Type RM Length L Ch R = 1,8960,171,171,171
BEGIN DESCRIPTION:
XS6421
END DESCRIPTION:
XS GIS Cut Line= 3
      2385524.65     13724105.76      2385728.07     13723898.94
      2385819.64     13723725.98
#Sta/Elev= 30
  4682.8  389.09  4704.8  388.76  4740.1  385.43  4747.2  383.32  4768.4  380.49
  4775.5  381.17  4782.5  379.70  4789.7  380.11  4796.7  378.82  4803.8  379.60
  4810.8  378.60  4891.2  378.62  4945.2  377.24  4972.1  374.75  4980.0  374.97
  4988.7  372.09  5006.5  370.55  5021.7  367.48  5022.1  366.98  5026.3  367.48
  5033.9  371.59  5040.4  374.05  5046.0  373.29  5056.6  382.73  5062.4  394.45
  5068.0  394.54  5078.7  403.28  5084.4  405.41  5144.7  406.83  5168.6  406.61
#Mann=5,-1,0
  4682.8     0.1       0  4891.2    0.12       0  5006.5    0.07       0
  5021.7    0.05       0  5026.3    0.07       0
Bank Sta=5021.7,5026.3
Exp/Cntr=0.3,0.1

Type RM Length L Ch R = 1,8789,566,566,566
BEGIN DESCRIPTION:
XS6412
END DESCRIPTION:
XS GIS Cut Line= 3
      2385538.17     13724105.79      2385772.15     13723919.29
      2386001.34     13723888.95
#Sta/Elev= 30
  4568.3  389.07  4602.6  387.24  4623.8  383.11  4638.2  378.39  4644.6  378.06
  4652.6  374.67  4659.0  377.00  4673.4  374.32  4679.8  376.08  4687.8  375.13
  4694.2  376.56  4736.3  377.50  4787.1  378.37  4801.5  376.22  4807.9  376.77
  4815.9  373.46  4822.3  374.22  4830.3  372.52  4844.8  372.46  4851.2  374.09
  4865.2  372.91  4981.4  370.16  4999.2  368.32  4999.6  367.82  5003.8  368.32
  5010.5  368.64  5015.6  372.61  5021.7  397.39  5031.8  403.05  5098.7  401.82
#Mann=5,-1,0
  4568.3     0.1       0  4736.3    0.12       0  4865.2    0.07       0
  4999.2    0.05       0  5003.8    0.07       0
Bank Sta=4999.2,5003.8
Exp/Cntr=0.3,0.1

Type RM Length L Ch R = 1,8223,441,441,441
BEGIN DESCRIPTION:
Stream0303 18.0
END DESCRIPTION:
XS GIS Cut Line= 3
      2385575.02     13724225.01      2385675.00     13724275.00
      2385825.01     13724325.00
#Sta/Elev= 30
  4882.3  391.16  4885.1  391.16  4890.7  390.40  4896.2  390.29  4913.0  388.06
  4918.6  388.14  4935.4  386.22  4949.4  385.27  4957.7  384.37  4961.1  384.33
  4979.3  383.11  4985.7  382.87  4991.3  381.95  4996.7  381.95  5015.2  368.55
  5025.7  364.68  5036.2  364.71  5044.5  364.05  5044.8  363.55  5048.7  363.55
  5049.1  364.05  5057.3  370.23  5078.4  379.10  5082.9  381.56  5088.9  384.83
  5099.5  389.09  5110.0  392.05  5120.6  394.39  5131.1  395.94  5152.2  397.11
#Mann=6,-1,0
  4882.3    0.07       0  4961.1     0.1       0  4979.3    0.12       0
  5044.5    0.05       0  5049.1    0.12       0  5082.9    0.07       0
Bank Sta=5044.5,5049.1
Exp/Cntr=0.3,0.1

Type RM Length L Ch R = 1,7782,213,213,213
BEGIN DESCRIPTION:
Stream0303 17.0
END DESCRIPTION:
XS GIS Cut Line= 3
      2385575.02     13724674.99      2385725.00     13724625.00
      2385775.00     13724525.00
#Sta/Elev= 30
  4842.2  398.91  4848.4  398.35  4852.7  397.68  4863.3  397.00  4873.8  394.97
  4884.3  392.16  4905.4  385.03  4916.0  382.57  4922.0  380.09  4926.5  378.23
  4937.0  375.55  4947.6  371.11  4958.1  363.97  4976.9  362.69  4977.3  362.19
  4981.2  362.19  4981.5  362.69  4989.8  364.95  5003.1  365.59  5008.7  370.43
  5014.3  370.03  5022.7  373.85  5031.0  376.75  5036.6  378.14  5045.0  381.35
  5075.8  386.41  5081.3  386.72  5086.8  387.58  5098.1  389.46  5112.1  390.80
#Mann=6,-1,0
  4842.2    0.05       0  4848.4    0.12       0  4922.0     0.1       0
  4976.9    0.05       0  4981.5     0.1       0  5086.8    0.07       0
Bank Sta=4976.9,4981.5
Exp/Cntr=0.3,0.1

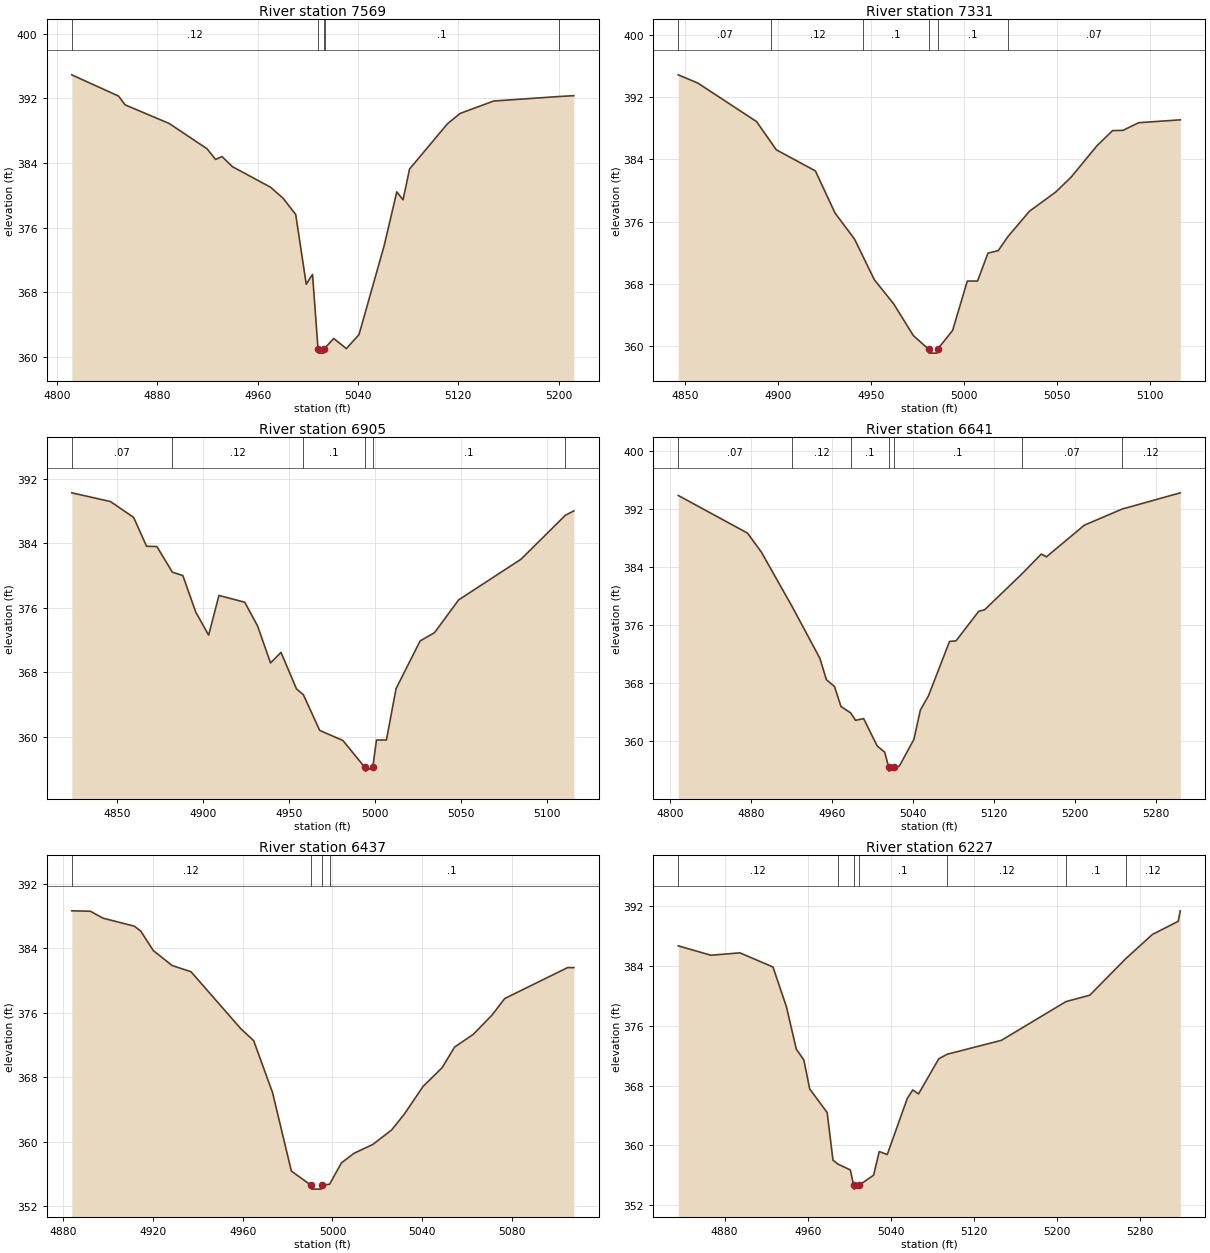
Type RM Length L Ch R = 1,7569,238,238,238
BEGIN DESCRIPTION:
XS6411
END DESCRIPTION:
XS GIS Cut Line= 2
      2385894.22     13724861.94      2385948.47     13724465.23
#Sta/Elev= 30
  4811.7  394.90  4849.0  392.27  4854.2  391.19  4889.4  388.88  4919.6  385.75
  4926.4  384.43  4931.5  384.79  4939.8  383.54  4970.1  381.01  4980.2  379.64
  4990.3  377.62  4998.7  368.99  5003.7  370.21  5008.1  360.97  5008.5  360.47
  5012.5  360.47  5012.8  360.97  5013.4  361.07  5020.6  362.28  5030.7  361.03
  5040.8  362.77  5060.9  373.81  5070.9  380.42  5075.9  379.44  5081.1  383.25
  5111.4  388.86  5121.5  390.13  5148.2  391.66  5200.6  392.22  5212.1  392.32
#Mann=5,-1,0
  4811.7    0.12       0  5008.1    0.05       0  5012.8    0.12       0
  5013.4     0.1       0  5200.6    0.07       0
Bank Sta=5008.1,5012.8
Exp/Cntr=0.3,0.1

Type RM Length L Ch R = 1,7331,426,426,426
BEGIN DESCRIPTION:
Stream0303 16.0
END DESCRIPTION:
XS GIS Cut Line= 3
      2386174.99     13724724.96      2386125.00     13724575.00
      2386074.99     13724474.97
#Sta/Elev= 30
  4846.5  394.83  4857.0  393.78  4888.6  388.84  4896.6  386.11  4899.2  385.22
  4920.2  382.52  4930.8  377.11  4941.3  373.76  4946.0  371.46  4951.9  368.57
  4962.4  365.44  4972.9  361.40  4981.1  359.65  4981.4  359.15  4985.5  359.15
  4985.9  359.65  4994.0  362.06  5001.9  368.39  5007.4  368.39  5013.0  371.97
  5018.5  372.29  5023.8  374.11  5035.3  377.34  5049.3  379.78  5057.7  381.71
  5071.6  385.74  5080.0  387.68  5085.6  387.71  5094.0  388.69  5116.4  389.06
#Mann=6,-1,0
  4846.5    0.07       0  4896.6    0.12       0  4946.0     0.1       0
  4981.1    0.05       0  4985.9     0.1       0  5023.8    0.07       0
Bank Sta=4981.1,4985.9
Exp/Cntr=0.3,0.1

Type RM Length L Ch R = 1,6905,264,264,264
BEGIN DESCRIPTION:
Stream0303 15.0
END DESCRIPTION:
XS GIS Cut Line= 3
      2386524.97     13724374.98      2386375.00     13724275.00
      2386275.04     13724225.02
#Sta/Elev= 30
  4823.8  390.25  4846.3  389.17  4859.8  387.20  4867.3  383.62  4873.3  383.59
  4882.3  380.41  4888.4  379.99  4895.9  375.46  4903.4  372.60  4909.4  377.52
  4924.4  376.68  4931.9  373.72  4939.4  369.15  4945.5  370.46  4954.5  365.93
  4958.5  365.21  4968.0  360.78  4981.5  359.53  4994.1  356.23  4994.5  355.73
  4998.9  356.23  5001.0  359.59  5006.8  359.59  5012.4  365.96  5026.4  371.88
  5034.8  372.91  5048.8  376.97  5085.1  382.02  5110.9  387.47  5115.8  388.01
#Mann=6,-1,0
  4823.8    0.07       0  4882.3    0.12       0  4958.5     0.1       0
  4994.1    0.05       0  4998.9     0.1       0  5110.9    0.07       0
Bank Sta=4994.1,4998.9
Exp/Cntr=0.3,0.1

Type RM Length L Ch R = 1,6641,204,204,204
BEGIN DESCRIPTION:
XS6410
END DESCRIPTION:
XS GIS Cut Line= 3
      2386728.37     13724238.04      2386490.99     13724048.13
      2386301.12     13724021.01
#Sta/Elev= 30
  4808.3  393.87  4876.7  388.68  4890.5  386.04  4921.0  378.50  4948.2  371.42
  4954.6  368.49  4962.6  367.54  4969.0  364.79  4978.6  363.90  4983.4  362.88
  4991.4  363.12  5004.7  359.36  5012.2  358.49  5016.2  356.38  5016.5  355.88
  5021.0  356.38  5026.6  356.56  5041.0  360.25  5047.4  364.29  5055.4  366.26
  5076.2  373.75  5082.6  373.83  5105.0  377.90  5110.8  378.11  5147.7  383.06
  5166.8  385.79  5171.9  385.41  5209.3  389.77  5246.8  392.00  5304.1  394.23
#Mann=7,-1,0
  4808.3    0.07       0  4921.0    0.12       0  4978.6     0.1       0
  5016.2    0.05       0  5021.0     0.1       0  5147.7    0.07       0
  5246.8    0.12       0
Bank Sta=5016.2,5021
Exp/Cntr=0.3,0.1

Type RM Length L Ch R = 1,6437,210,210,210
BEGIN DESCRIPTION:
Stream0303 14.0
END DESCRIPTION:
XS GIS Cut Line= 3
      2386824.96     13724024.98      2386725.00     13723975.00
      2386624.97     13723924.98
#Sta/Elev= 30
  4883.9  388.67  4892.2  388.62  4897.8  387.76  4911.8  386.76  4914.6  386.16
  4920.2  383.74  4928.6  381.88  4937.0  381.11  4959.3  374.00  4964.9  372.56
  4973.3  366.12  4981.7  356.36  4990.4  354.62  4990.8  354.12  4994.9  354.12
  4995.3  354.62  4998.7  354.72  5004.0  357.38  5009.6  358.57  5018.0  359.67
  5026.4  361.48  5032.0  363.43  5040.4  366.89  5048.8  369.18  5054.4  371.76
  5062.7  373.33  5071.1  375.74  5076.7  377.78  5104.7  381.62  5107.5  381.62
#Mann=4,-1,0
  4883.9    0.12       0  4990.4    0.05       0  4995.3    0.12       0
  4998.7     0.1       0
Bank Sta=4990.4,4995.3
Exp/Cntr=0.3,0.1

Type RM Length L Ch R = 1,6227,263,263,263
BEGIN DESCRIPTION:
XS6409
END DESCRIPTION:
XS GIS Cut Line= 3
      2386914.84     13723956.61      2386826.67     13723780.27
      2386559.36     13723678.76
#Sta/Elev= 30
  4835.4  386.73  4866.9  385.47  4894.8  385.79  4926.6  383.89  4939.5  378.57
  4949.0  372.90  4956.3  371.43  4961.9  367.56  4978.7  364.40  4984.3  358.02
  4989.0  357.50  5001.0  356.71  5004.2  354.64  5004.6  354.14  5009.1  354.64
  5023.4  356.01  5028.8  359.17  5036.5  358.77  5055.7  366.26  5061.1  367.43
  5066.6  366.89  5086.1  371.60  5094.2  372.21  5146.3  374.07  5208.5  379.26
  5231.4  380.12  5265.9  385.00  5291.6  388.25  5316.4  390.01  5318.5  391.42
#Mann=7,-1,0
  4835.4    0.12       0  4989.0     0.1       0  5004.2    0.05       0
  5009.1     0.1       0  5094.2    0.12       0  5208.5     0.1       0
  5265.9    0.12       0
Bank Sta=5004.2,5009.1
Exp/Cntr=0.3,0.1

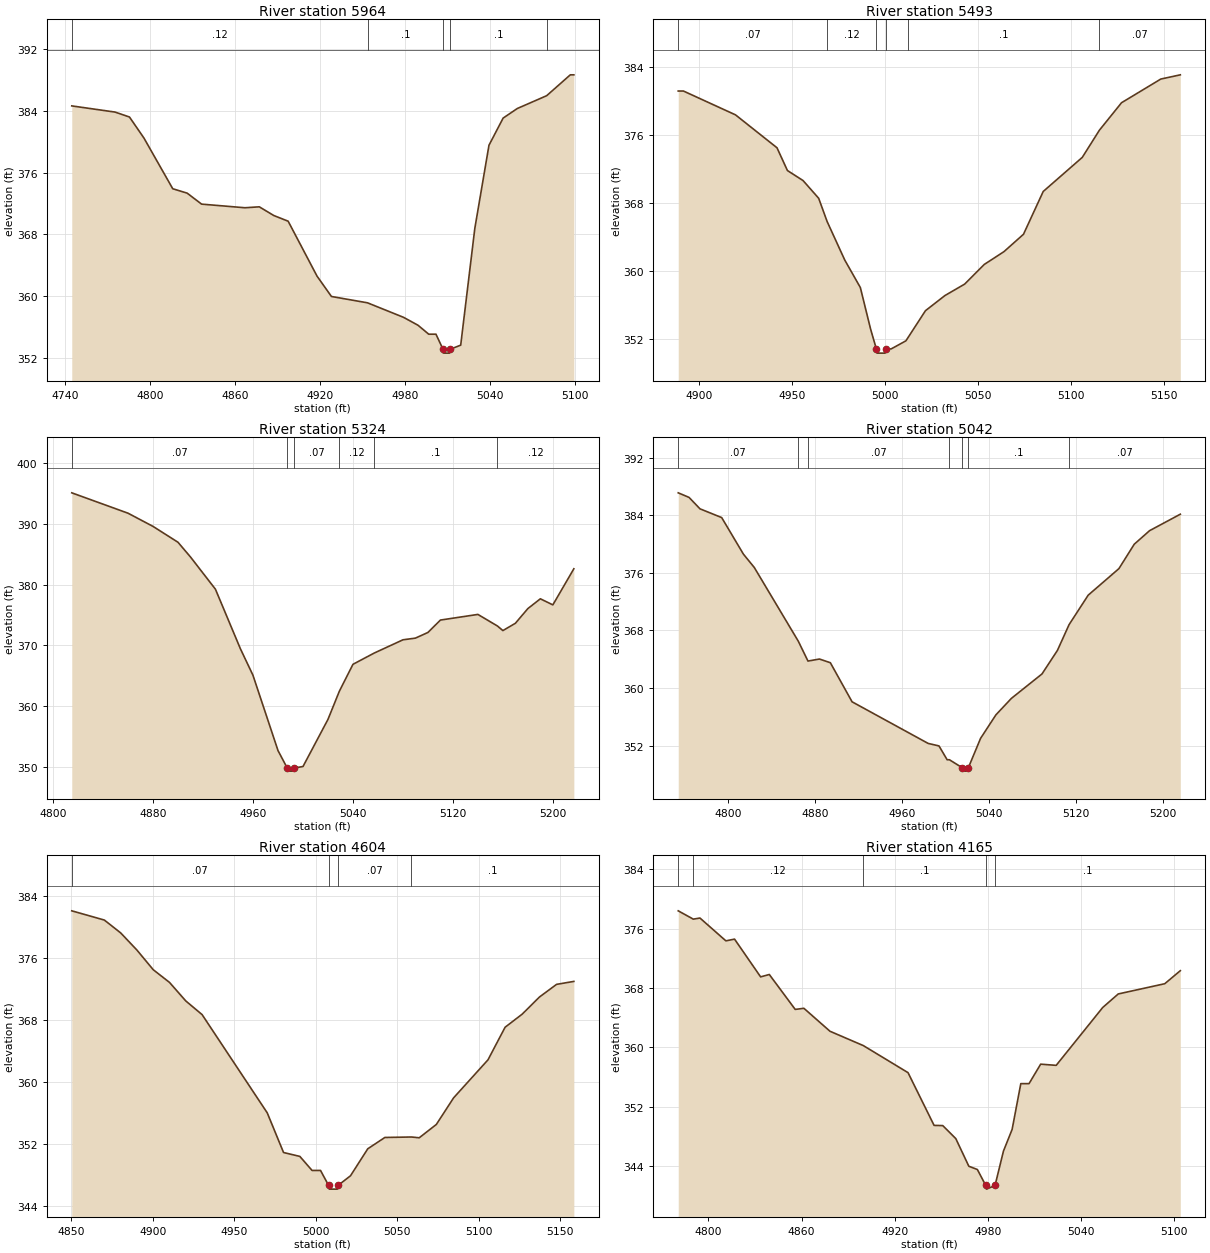
Type RM Length L Ch R = 1,5964,471,471,471
BEGIN DESCRIPTION:
Stream0303 13.0
END DESCRIPTION:
XS GIS Cut Line= 3
      2386925.00     13723875.02      2386975.00     13723625.00
      2386975.00     13723524.97
#Sta/Elev= 30
  4744.5  384.64  4775.1  383.84  4785.3  383.20  4795.5  380.49  4815.9  373.92
  4826.1  373.35  4836.3  371.93  4866.9  371.46  4877.1  371.58  4887.3  370.46
  4897.5  369.72  4917.9  362.62  4928.1  359.98  4953.6  359.16  4979.1  357.28
  4989.3  356.26  4996.9  355.10  5002.0  355.10  5007.0  353.15  5007.3  352.65
  5011.6  352.65  5012.0  353.15  5019.5  353.68  5029.5  368.81  5039.5  379.55
  5049.5  383.06  5059.5  384.30  5080.3  385.96  5097.0  388.66  5099.5  388.66
#Mann=5,-1,0
  4744.5    0.12       0  4953.6     0.1       0  5007.0    0.05       0
  5012.0     0.1       0  5080.3    0.07       0
Bank Sta=5007,5012
Exp/Cntr=0.3,0.1

Type RM Length L Ch R = 1,5493,169,169,169
BEGIN DESCRIPTION:
Stream0303 12.0
END DESCRIPTION:
XS GIS Cut Line= 3
      2387174.98     13723975.01      2387275.00     13723925.00
      2387324.99     13723775.04
#Sta/Elev= 30
  4888.7  381.21  4891.5  381.21  4919.5  378.40  4941.8  374.52  4947.4  371.84
  4955.8  370.66  4964.2  368.57  4968.7  365.85  4978.2  361.30  4986.6  358.05
  4992.1  353.16  4995.2  350.82  4995.6  350.32  4999.9  350.32  5000.2  350.82
  5003.2  350.82  5011.1  351.77  5012.4  352.21  5021.6  355.32  5032.1  357.11
  5042.7  358.46  5053.2  360.77  5063.8  362.28  5074.3  364.33  5084.9  369.37
  5105.9  373.39  5115.1  376.59  5127.0  379.83  5148.1  382.62  5158.6  383.12
#Mann=6,-1,0
  4888.7    0.07       0  4968.7    0.12       0  4995.2    0.05       0
  5000.2    0.12       0  5012.4     0.1       0  5115.1    0.07       0
Bank Sta=4995.2,5000.2
Exp/Cntr=0.3,0.1

Type RM Length L Ch R = 1,5324,282,282,282
BEGIN DESCRIPTION:
XS6414
END DESCRIPTION:
XS GIS Cut Line= 2
      2387430.22     13724160.00      2387420.09     13723758.23
#Sta/Elev= 30
  4815.1  395.09  4860.1  391.74  4880.1  389.57  4900.1  386.96  4910.1  384.54
  4930.1  379.23  4950.1  369.42  4960.1  365.09  4980.2  352.67  4987.6  349.79
  4988.0  349.29  4992.3  349.29  4992.7  349.79  5000.2  350.05  5020.2  357.81
  5029.3  362.44  5040.2  366.87  5057.2  368.72  5080.2  370.90  5090.2  371.18
  5100.2  372.11  5110.2  374.15  5140.2  375.08  5155.8  373.18  5160.2  372.42
  5170.2  373.62  5180.2  376.04  5190.2  377.65  5200.2  376.65  5217.0  382.59
#Mann=6,-1,0
  4815.1    0.07       0  4987.6    0.05       0  4992.7    0.07       0
  5029.3    0.12       0  5057.2     0.1       0  5155.8    0.12       0
Bank Sta=4987.6,4992.7
Exp/Cntr=0.3,0.1

Type RM Length L Ch R = 1,5042,438,438,438
BEGIN DESCRIPTION:
Stream0303 11.0
END DESCRIPTION:
XS GIS Cut Line= 3
      2387625.00     13724074.99      2387625.00     13723825.00
      2387475.02     13723675.02
#Sta/Elev= 30
  4754.0  387.11  4764.0  386.47  4774.0  384.89  4794.0  383.67  4814.0  378.59
  4824.0  376.74  4864.5  366.50  4873.4  363.74  4884.0  364.02  4894.0  363.51
  4914.0  358.08  4984.0  352.30  4994.0  351.95  5001.5  350.03  5003.6  350.03
  5015.1  348.95  5015.6  348.45  5020.6  348.45  5021.1  348.95  5032.3  353.01
  5046.4  356.27  5060.6  358.55  5088.8  361.95  5103.0  365.22  5113.7  368.79
  5131.3  372.89  5159.6  376.58  5173.7  379.97  5187.8  381.85  5216.1  384.14
#Mann=7,-1,0
  4754.0    0.07       0  4864.5     0.1       0  4873.4    0.07       0
  5003.6     0.1       0  5015.1    0.05       0  5021.1     0.1       0
  5113.7    0.07       0
Bank Sta=5015.1,5021.1
Exp/Cntr=0.3,0.1

Type RM Length L Ch R = 1,4604,439,439,439
BEGIN DESCRIPTION:
Stream0303 10.0
END DESCRIPTION:
XS GIS Cut Line= 3
      2388025.00     13724075.05      2388025.00     13723925.00
      2387974.99     13723774.96
#Sta/Elev= 30
  4850.3  382.06  4870.3  380.87  4880.3  379.22  4890.3  377.00  4900.3  374.47
  4910.3  372.83  4920.3  370.44  4930.3  368.68  4970.3  356.01  4980.3  350.90
  4990.3  350.40  4997.8  348.59  5003.0  348.59  5007.9  346.68  5008.4  346.18
  5013.4  346.18  5013.9  346.68  5021.4  347.90  5032.0  351.38  5042.5  352.84
  5058.8  352.90  5063.6  352.80  5074.1  354.52  5084.7  357.95  5105.8  362.85
  5116.3  367.05  5126.8  368.74  5137.4  370.95  5147.9  372.58  5158.5  372.96
#Mann=4,-1,0
  4850.3    0.07       0  5007.9    0.05       0  5013.9    0.07       0
  5058.8     0.1       0
Bank Sta=5007.9,5013.9
Exp/Cntr=0.3,0.1

Type RM Length L Ch R = 1,4165,466,466,466
BEGIN DESCRIPTION:
Stream0303 9.0
END DESCRIPTION:
XS GIS Cut Line= 3
      2388325.01     13724074.98      2388425.00     13723875.00
      2388425.00     13723774.99
#Sta/Elev= 30
  4780.5  378.39  4790.2  377.27  4794.5  377.42  4811.2  374.35  4816.8  374.58
  4833.6  369.50  4839.2  369.82  4855.9  365.12  4861.5  365.27  4878.3  362.18
  4899.8  360.25  4928.6  356.61  4945.4  349.51  4951.0  349.48  4959.4  347.73
  4967.8  344.01  4973.3  343.57  4978.7  341.43  4979.2  340.93  4984.7  341.43
  4990.1  346.04  4995.7  348.97  5001.3  355.13  5006.6  355.13  5014.1  357.75
  5024.1  357.59  5054.1  365.38  5064.1  367.20  5094.1  368.58  5104.1  370.33
#Mann=5,-1,0
  4780.5    0.07       0  4790.2    0.12       0  4899.8     0.1       0
  4978.7    0.05       0  4984.7     0.1       0
Bank Sta=4978.7,4984.7
Exp/Cntr=0.3,0.1