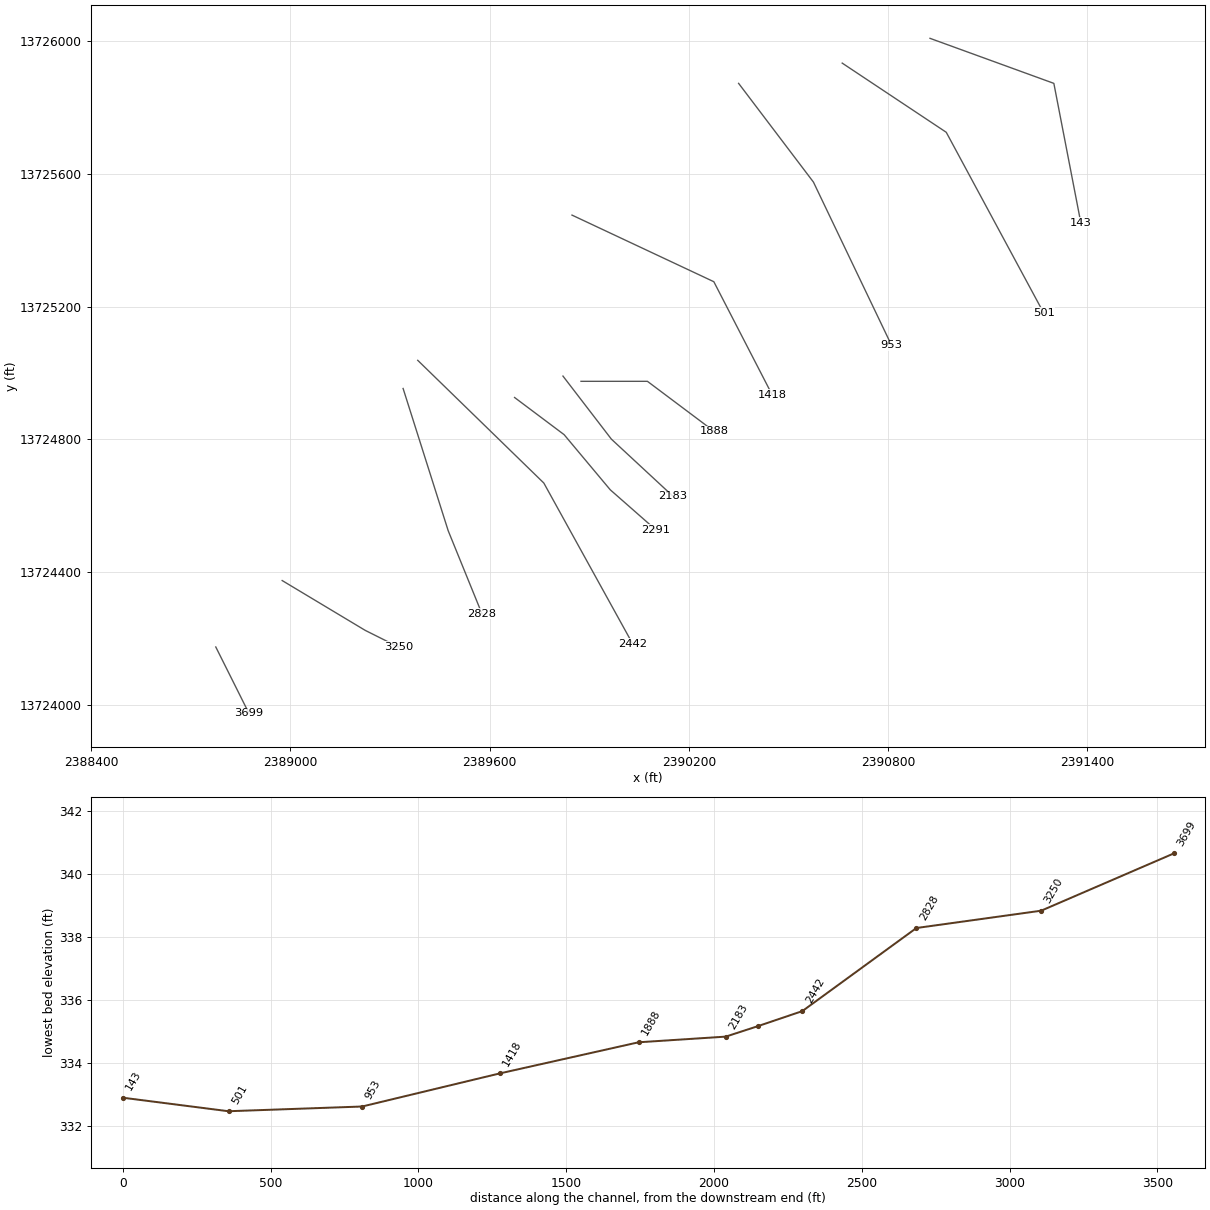
HEC-RAS study Stream0303.prj: Stream0303 Base Level Engineering

--- Stream0303.g01 (geometry) --- (continued)

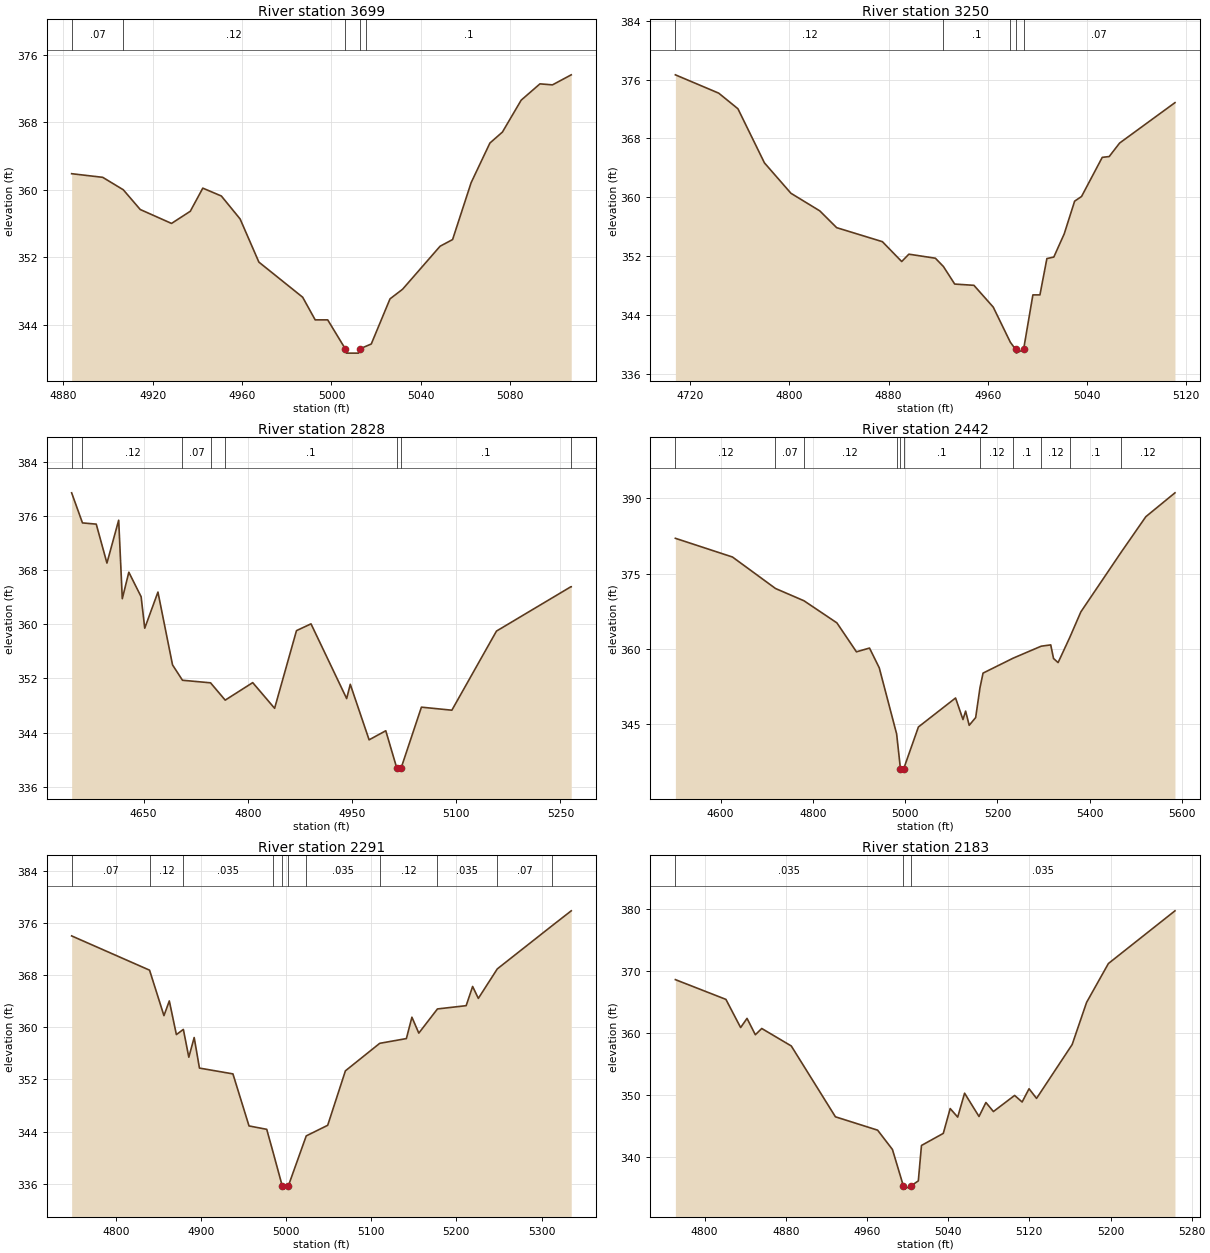
Type RM Length L Ch R = 1,3699,449,449,449
BEGIN DESCRIPTION:
Stream0303 8.0
END DESCRIPTION:
XS GIS Cut Line= 3
      2388775.02     13724174.97      2388825.00     13724075.00
      2388875.01     13723974.97
#Sta/Elev= 30
  4883.7  361.91  4897.6  361.48  4906.8  360.01  4914.4  357.67  4928.4  356.02
  4936.8  357.46  4942.4  360.20  4950.7  359.27  4959.1  356.55  4967.5  351.44
  4987.1  347.28  4992.7  344.60  4998.3  344.60  5006.2  341.16  5006.7  340.66
  5012.1  340.66  5012.6  341.16  5015.3  341.46  5017.8  341.74  5026.2  347.09
  5031.8  348.22  5048.6  353.32  5054.2  354.11  5062.5  360.85  5070.9  365.54
  5076.5  366.84  5084.9  370.62  5093.3  372.55  5098.9  372.43  5107.3  373.62
#Mann=5,-1,0
  4883.7    0.07       0  4906.8    0.12       0  5006.2    0.05       0
  5012.6    0.12       0  5015.3     0.1       0
Bank Sta=5006.2,5012.6
Exp/Cntr=0.3,0.1

Type RM Length L Ch R = 1,3250,422,422,422
BEGIN DESCRIPTION:
Stream0303 7.0
END DESCRIPTION:
XS GIS Cut Line= 3
      2388975.01     13724374.99      2389225.00     13724225.00
      2389324.96     13724175.02
#Sta/Elev= 30
  4707.9  376.64  4742.9  374.15  4758.4  372.03  4779.8  364.68  4801.2  360.55
  4824.5  358.16  4838.1  355.88  4875.0  353.98  4890.6  351.28  4896.4  352.28
  4917.8  351.73  4924.3  350.60  4933.4  348.22  4948.9  348.05  4964.5  345.09
  4978.3  340.32  4982.6  339.34  4983.1  338.84  4989.0  339.34  4996.5  346.75
  5002.2  346.75  5007.8  351.68  5013.4  351.89  5021.8  355.04  5030.2  359.48
  5035.8  360.12  5052.5  365.43  5058.1  365.54  5066.5  367.37  5111.2  372.86
#Mann=5,-1,0
  4707.9    0.12       0  4924.3     0.1       0  4978.3    0.07       0
  4982.6    0.05       0  4989.0    0.07       0
Bank Sta=4982.6,4989
Exp/Cntr=0.3,0.1

Type RM Length L Ch R = 1,2828,386,386,386
BEGIN DESCRIPTION:
Stream0303 6.0
END DESCRIPTION:
XS GIS Cut Line= 3
      2389339.20     13724953.43      2389475.00     13724525.00
      2389576.55     13724275.30
#Sta/Elev= 30
  4546.5  379.45  4562.1  375.00  4581.9  374.82  4597.3  369.06  4614.2  375.40
  4619.4  363.79  4628.8  367.71  4646.5  364.08  4651.7  359.43  4670.7  364.77
  4691.7  354.00  4706.0  351.73  4746.4  351.35  4767.5  348.79  4807.1  351.38
  4838.6  347.58  4870.1  359.07  4891.0  360.07  4942.3  349.02  4947.5  351.13
  4974.6  342.92  4998.6  344.26  5014.3  338.79  5014.8  338.29  5020.8  338.79
  5049.9  347.75  5093.7  347.30  5157.9  359.00  5265.0  365.56  5265.5  365.56
#Mann=8,-1,0
  4546.5    0.07       0  4562.1    0.12       0  4706.0    0.07       0
  4746.4    0.12       0  4767.5     0.1       0  5014.3    0.05       0
  5020.8     0.1       0  5265.0    0.07       0
Bank Sta=5014.3,5020.8
Exp/Cntr=0.3,0.1

Type RM Length L Ch R = 1,2442,151,151,151
BEGIN DESCRIPTION:
Stream0303 5.0
END DESCRIPTION:
XS GIS Cut Line= 3
      2389383.27     13725038.23      2389763.03     13724668.64
      2390030.43     13724184.61
#Sta/Elev= 30
  4502.0  382.04  4625.8  378.31  4719.0  372.04  4780.8  369.59  4852.1  365.19
  4894.5  359.42  4922.8  360.17  4943.9  356.24  4981.6  343.06  4989.8  336.15
  4990.3  335.65  4997.0  336.15  5028.8  344.45  5109.3  350.22  5125.4  345.93
  5131.1  347.61  5138.9  344.78  5152.9  346.32  5162.2  352.24  5168.9  355.18
  5234.0  358.15  5294.8  360.54  5315.6  360.80  5321.7  358.09  5331.6  357.28
  5356.9  362.29  5380.9  367.38  5467.7  379.19  5521.8  386.35  5584.9  391.10
#Mann=11,-1,0
  4502.0    0.12       0  4719.0    0.07       0  4780.8    0.12       0
  4981.6     0.1       0  4989.8    0.05       0  4997.0     0.1       0
  5162.2    0.12       0  5234.0     0.1       0  5294.8    0.12       0
  5356.9     0.1       0  5467.7    0.12       0
Bank Sta=4989.8,4997
Exp/Cntr=0.3,0.1

Type RM Length L Ch R = 1,2291,108,108,108
BEGIN DESCRIPTION:
XS6407
END DESCRIPTION:
XS GIS Cut Line= 4
      2389674.90     13724926.31      2389824.07     13724814.44
      2389963.09     13724648.29      2390101.06     13724527.15
#Sta/Elev= 30
  4748.2  374.04  4839.7  368.78  4856.6  361.80  4862.9  364.06  4871.2  358.89
  4879.4  359.69  4885.8  355.42  4892.1  358.44  4898.3  353.75  4937.6  352.86
  4956.5  344.87  4977.3  344.35  4984.6  340.91  4995.5  335.67  4996.0  335.17
  5002.7  335.67  5023.7  343.34  5048.9  344.97  5069.7  353.33  5110.0  357.55
  5141.3  358.28  5147.8  361.56  5155.9  359.12  5177.8  362.83  5211.5  363.33
  5219.1  366.28  5225.8  364.45  5248.1  368.98  5312.3  375.59  5334.9  377.89
#Mann=11,-1,0
  4748.2    0.07       0  4839.7    0.12       0  4879.4   0.035       0
  4984.6     0.1       0  4995.5    0.05       0  5002.7     0.1       0
  5023.7   0.035       0  5110.0    0.12       0  5177.8   0.035       0
  5248.1    0.07       0  5312.3   0.035       0
Bank Sta=4995.5,5002.7
Exp/Cntr=0.3,0.1

Type RM Length L Ch R = 1,2183,295,295,295
BEGIN DESCRIPTION:
XS6406
END DESCRIPTION:
XS GIS Cut Line= 3
      2389820.65     13724990.79      2389966.48     13724800.87
      2390151.89     13724628.95
#Sta/Elev= 30
  4771.2  368.67  4821.0  365.48  4835.5  360.93  4841.8  362.41  4850.0  359.77
  4856.3  360.78  4885.4  357.96  4928.9  346.52  4970.5  344.36  4985.1  341.24
  4995.9  335.34  4996.4  334.84  5003.2  335.34  5010.6  336.17  5013.7  341.89
  5035.2  343.84  5042.0  347.85  5049.4  346.47  5056.2  350.33  5070.4  346.57
  5077.2  348.83  5084.6  347.37  5105.5  349.97  5112.9  348.91  5119.7  351.05
  5127.1  349.49  5162.2  358.19  5176.4  364.99  5197.9  371.27  5263.5  379.78
#Mann=3,-1,0
  4771.2   0.035       0  4995.9   0.035       0  5003.2   0.035       0
Bank Sta=4995.9,5003.2
Exp/Cntr=0.3,0.1

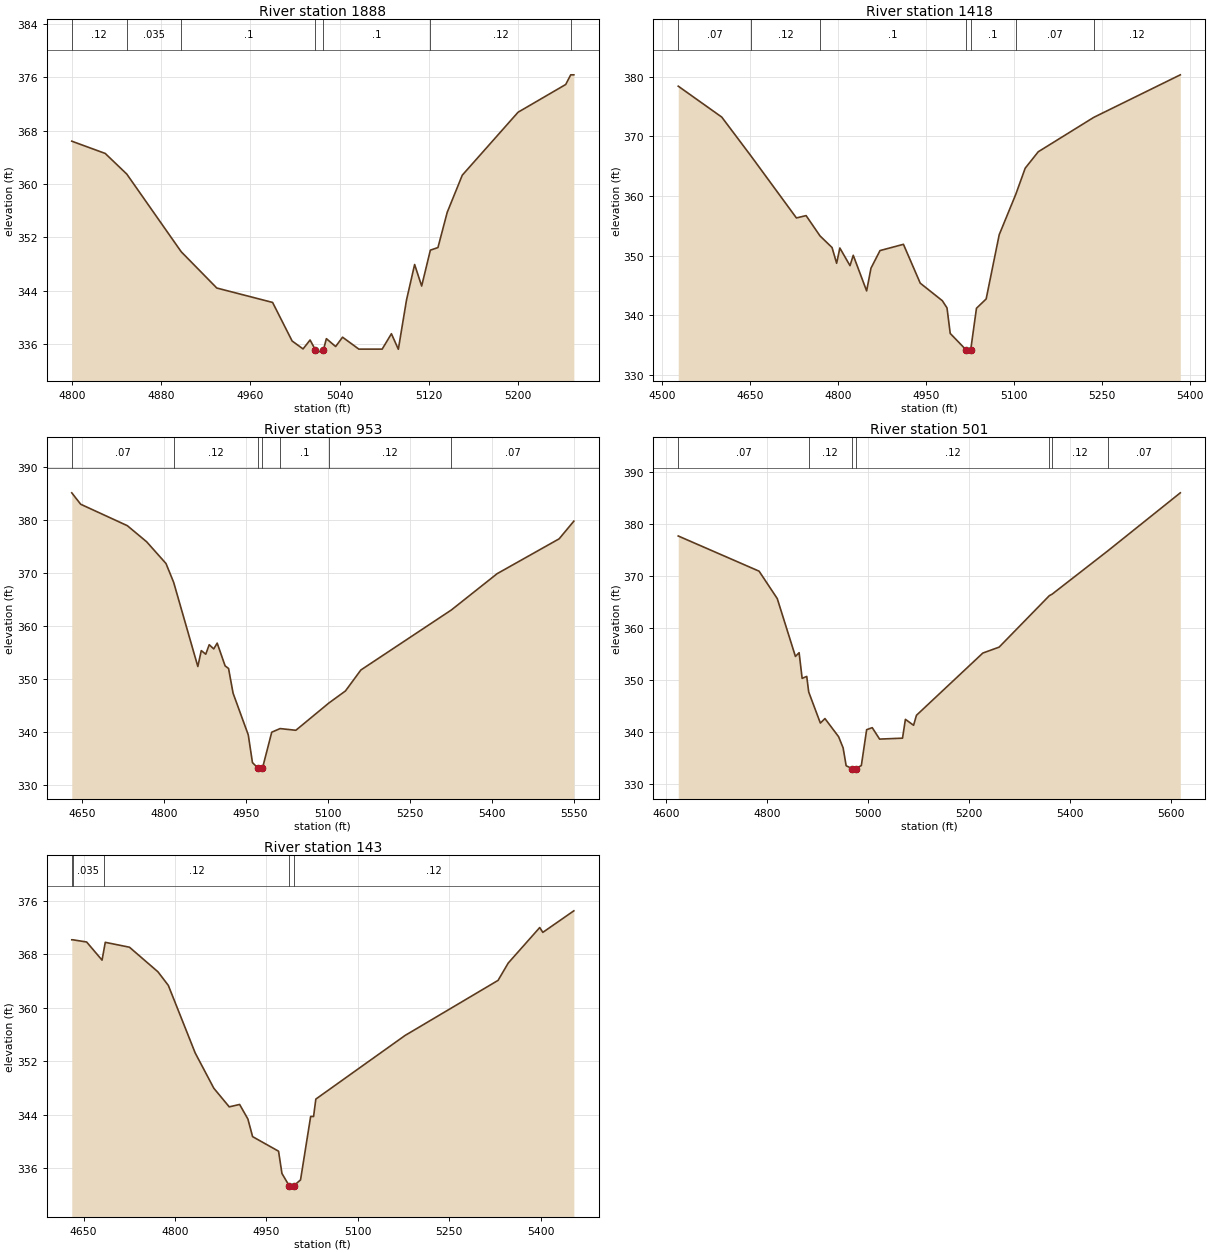
Type RM Length L Ch R = 1,1888,470,470,470
BEGIN DESCRIPTION:
Stream0303 4.0
END DESCRIPTION:
XS GIS Cut Line= 3
      2389874.97     13724975.00      2390075.00     13724975.00
      2390274.97     13724825.02
#Sta/Elev= 30
  4800.0  366.44  4830.0  364.60  4849.3  361.51  4898.1  349.86  4930.0  344.42
  4980.0  342.26  4997.5  336.48  5007.3  335.29  5013.6  336.63  5018.3  335.16
  5018.8  334.66  5025.6  335.16  5028.2  336.83  5036.5  335.65  5042.7  337.05
  5057.3  335.26  5078.2  335.26  5086.5  337.57  5092.7  335.24  5100.0  342.61
  5107.3  347.95  5113.6  344.72  5121.4  350.10  5128.2  350.49  5136.5  355.77
  5150.0  361.34  5200.0  370.78  5242.7  374.94  5247.2  376.39  5250.0  376.39
#Mann=7,-1,0
  4800.0    0.12       0  4849.3   0.035       0  4898.1     0.1       0
  5018.3    0.05       0  5025.6     0.1       0  5121.4    0.12       0
  5247.2    0.07       0
Bank Sta=5018.3,5025.6
Exp/Cntr=0.3,0.1

Type RM Length L Ch R = 1,1418,465,465,465
BEGIN DESCRIPTION:
Stream0303 3.0
END DESCRIPTION:
XS GIS Cut Line= 3
      2389847.82     13725475.62      2390275.00     13725275.00
      2390450.70     13724934.38
#Sta/Elev= 30
  4528.0  378.42  4602.2  373.23  4652.0  366.71  4729.3  356.33  4745.8  356.72
  4769.5  353.32  4790.0  351.37  4797.8  348.73  4803.3  351.29  4820.6  348.33
  4826.1  350.07  4848.9  344.10  4856.3  347.91  4871.7  350.86  4911.6  351.91
  4940.2  345.40  4977.8  342.46  4985.8  341.25  4991.3  336.97  5018.8  334.17
  5019.3  333.67  5026.1  334.17  5036.0  341.19  5052.5  342.75  5074.7  353.51
  5103.0  360.30  5119.0  364.67  5141.2  367.42  5235.8  373.19  5383.2  380.32
#Mann=7,-1,0
  4528.0    0.07       0  4652.0    0.12       0  4769.5     0.1       0
  5018.8    0.05       0  5026.1     0.1       0  5103.0    0.07       0
  5235.8    0.12       0
Bank Sta=5018.8,5026.1
Exp/Cntr=0.3,0.1

Type RM Length L Ch R = 1,953,452,452,452
BEGIN DESCRIPTION:
Stream0303 2.0
END DESCRIPTION:
XS GIS Cut Line= 3
      2390349.63     13725872.35      2390575.00     13725575.00
      2390810.38     13725083.12
#Sta/Elev= 30
  4631.7  385.08  4648.0  382.93  4733.3  378.89  4768.7  375.85  4804.1  371.75
  4818.1  368.20  4862.3  352.34  4868.6  355.34  4876.8  354.66  4883.1  356.45
  4891.4  355.66  4897.7  356.75  4912.2  352.46  4918.5  351.97  4926.8  347.30
  4954.6  339.44  4962.2  334.23  4973.0  333.12  4973.5  332.62  4980.4  333.12
  4997.5  339.96  5012.8  340.64  5041.6  340.32  5102.0  345.46  5132.3  347.73
  5160.5  351.68  5326.1  363.00  5409.8  369.84  5523.2  376.41  5550.1  379.74
#Mann=7,-1,0
  4631.7    0.07       0  4818.1    0.12       0  4973.0    0.05       0
  4980.4    0.12       0  5012.8     0.1       0  5102.0    0.12       0
  5326.1    0.07       0
Bank Sta=4973,4980.4
Exp/Cntr=0.3,0.1

Type RM Length L Ch R = 1,501,358,358,358
BEGIN DESCRIPTION:
Stream0303 1.0
END DESCRIPTION:
XS GIS Cut Line= 3
      2390661.62     13725933.35      2390975.00     13725725.00
      2391268.53     13725180.61
#Sta/Elev= 30
  4623.7  377.70  4783.9  370.93  4819.9  365.66  4855.9  354.53  4863.2  355.25
  4869.2  350.31  4878.3  350.69  4882.2  347.70  4905.3  341.71  4914.4  342.58
  4941.4  339.10  4950.4  336.95  4956.4  333.51  4967.7  332.97  4968.2  332.47
  4975.2  332.97  4986.5  333.54  4997.0  340.44  5008.1  340.83  5022.7  338.63
  5068.1  338.81  5073.8  342.43  5090.0  341.29  5095.7  343.21  5227.2  355.18
  5259.5  356.32  5359.0  366.22  5364.4  366.50  5474.5  374.81  5618.5  386.00
#Mann=7,-1,0
  4623.7    0.07       0  4882.2    0.12       0  4967.7    0.05       0
  4975.2    0.12       0  5359.0    0.07       0  5364.4    0.12       0
  5474.5    0.07       0
Bank Sta=4967.7,4975.2
Exp/Cntr=0.3,0.1

Type RM Length L Ch R = 1,143,0,0,0
BEGIN DESCRIPTION:
XS6405
END DESCRIPTION:
XS GIS Cut Line= 3
      2390926.05     13726007.97      2391299.03     13725872.34
      2391380.21     13725452.90
#Sta/Elev= 30
  4630.5  370.18  4632.2  370.18  4654.9  369.85  4680.2  367.14  4683.1  368.60
  4685.5  369.80  4725.2  369.07  4772.0  365.39  4789.0  363.36  4833.1  353.26
  4863.7  347.98  4889.0  345.20  4906.0  345.56  4919.6  343.38  4927.3  340.75
  4969.9  338.57  4975.5  335.24  4987.4  333.40  4987.9  332.90  4994.9  333.40
  5006.0  334.28  5022.6  343.76  5027.4  343.76  5031.1  346.36  5177.5  355.87
  5330.2  364.11  5346.9  366.70  5398.6  372.01  5403.7  371.29  5454.6  374.51
#Mann=5,-1,0
  4630.5    0.12       0  4632.2   0.035       0  4683.1    0.12       0
  4987.4    0.05       0  4994.9    0.12       0
Bank Sta=4987.4,4994.9
Exp/Cntr=0.3,0.1

Chan Stop Cuts=-1