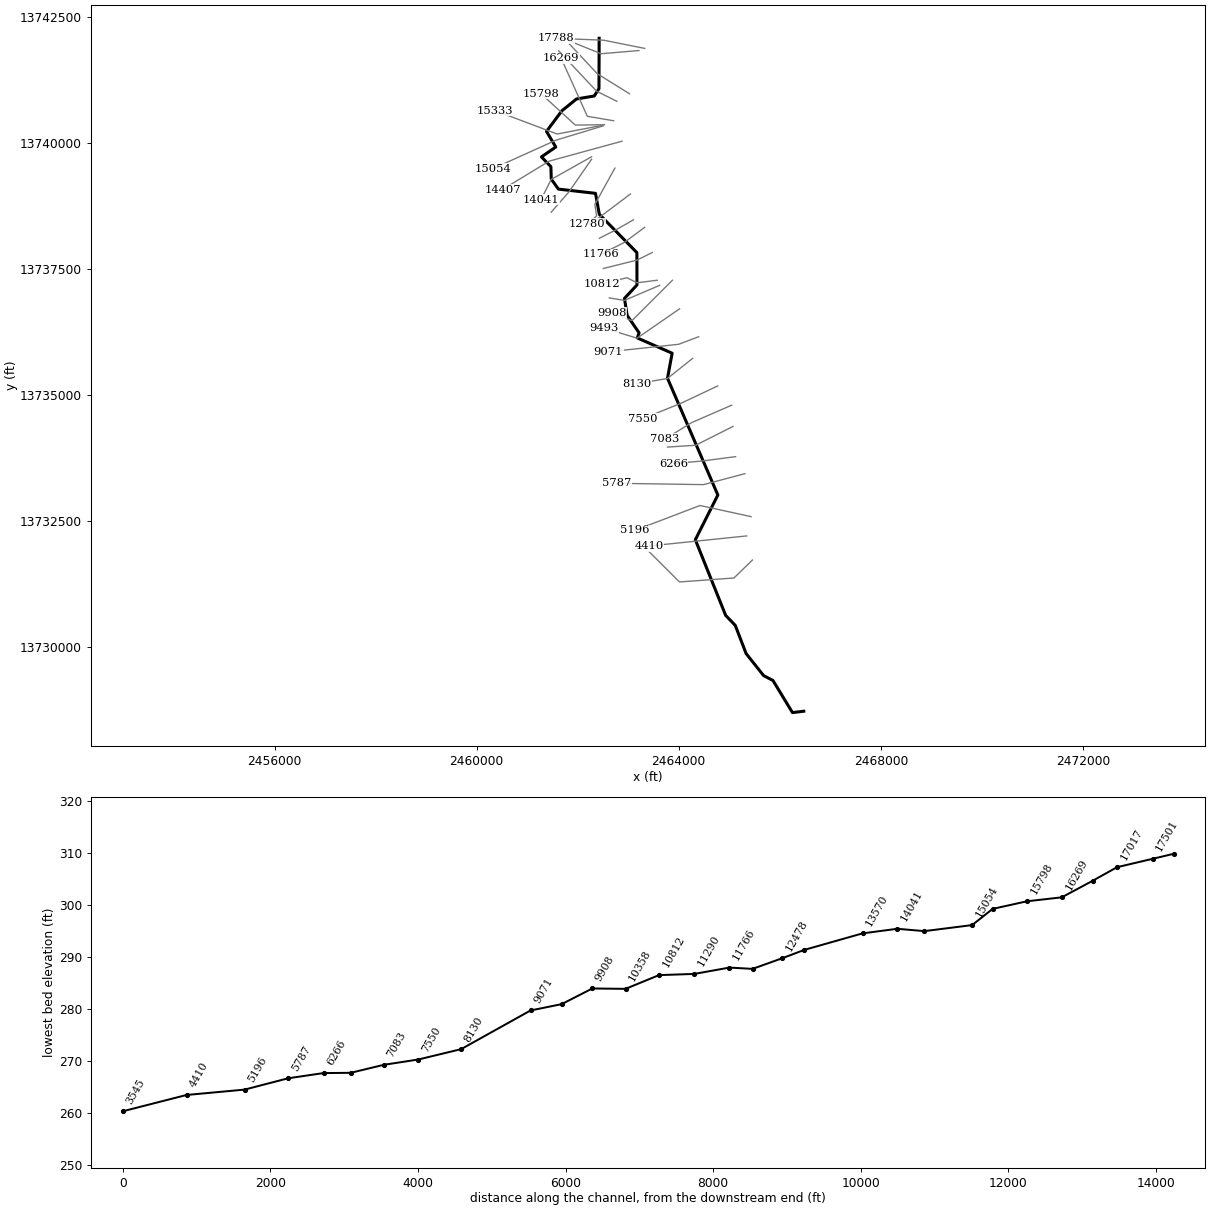
--- TINSLEY CREEK.prj (project) ---

Proj Title=TINSLEY CREEK Base Level Engineering
Current Plan=p01
Default Exp/Contr=0.3,0.1
English Units
Geom File=g01
Flow File=f01
Plan File=p01
Y Axis Title=Elevation
X Axis Title(PF)=Main Channel Distance
X Axis Title(XS)=Station
BEGIN DESCRIPTION:
TINSLEY CREEK
END DESCRIPTION:
DSS Export Rating Curves= 0
DSS Export Rating Curve Sorted= 0
DSS Export Volume Flow Curves= 0
DXF OffsetX= 0
DXF OffsetY= 0
DXF ScaleX= 1
DXF ScaleY= 10

--- TINSLEY CREEK.p01 (plan) ---

Plan Title=Multiple Run
Short Identifier=Multiple
Geom File=g01
Flow File=f01
Subcritical Flow
K Sum by GR= 0
Std Step Tol= 0.01
Critical Tol= 0.01
Num of Std Step Trials= 20
Max Error Tol= 0.3
Flow Tol Ratio= 0.001
Split Flow NTrial= 30
Split Flow Tol= 0.02
Split Flow Ratio= 0.02
Log Output Level= 0
Friction Slope Method= 1
Unsteady Friction Slope Method= 2
Unsteady Bridges Friction Slope Method= 1
Parabolic Critical Depth
Global Vel Dist=  1 , 1 , 1
Global Log Level= 0
CheckData=True
Encroach Param= -1, 0, 0, 0
BEGIN DESCRIPTION:
Multiple Run
END DESCRIPTION:

--- TINSLEY CREEK.f01 (steady flow) ---

Flow Title=Multiple
Number of Profiles=7
Profile Names=10-year,25-year,50-year,1pct_min,100-year,1pct_plu,500-year
River Rch & RM= TINSLEY CREEK,Reach-1,17788
     698    1126    1512     983    1962    3914    3270
River Rch & RM= TINSLEY CREEK,Reach-1,17017
     995    1624    2199    1439    2871    5728    4847
River Rch & RM= TINSLEY CREEK,Reach-1,8130
    1286    2125    2899    1910    3811    7604    6524
River Rch & RM= TINSLEY CREEK,Reach-1,3545
    1404    2325    3177    2096    4182    8343    7178
Boundary for River Rch & Prof#=TINSLEY CREEK,Reach-1,1
Up Type=0
Dn Type=3
Dn Slope=0.005
Boundary for River Rch & Prof#=TINSLEY CREEK,Reach-1,2
Up Type=0
Dn Type=3
Dn Slope=0.005
Boundary for River Rch & Prof#=TINSLEY CREEK,Reach-1,3
Up Type=0
Dn Type=3
Dn Slope=0.005
Boundary for River Rch & Prof#=TINSLEY CREEK,Reach-1,4
Up Type=0
Dn Type=3
Dn Slope=0.005
Boundary for River Rch & Prof#=TINSLEY CREEK,Reach-1,5
Up Type=0
Dn Type=3
Dn Slope=0.005
Boundary for River Rch & Prof#=TINSLEY CREEK,Reach-1,6
Up Type=0
Dn Type=3
Dn Slope=0.005
Boundary for River Rch & Prof#=TINSLEY CREEK,Reach-1,7
Up Type=0
Dn Type=3
Dn Slope=0.005

--- TINSLEY CREEK.g01 (geometry) ---

Geom Title=Existing Conditions
Program Version=4.10

River Reach=TINSLEY CREEK   ,Reach-1
Reach XY= 30
        2462425.       13742075.      2462421.18     13741076.58
       2462327.7     13740930.36      2461976.58     13740871.18
      2461688.63     13740638.21       2461382.6     13740228.33
      2461565.99     13739917.98      2461282.51     13739721.85
      2461469.54     13739527.45      2461477.06     13739280.86
      2461618.66     13739083.02      2462352.36     13738999.01
      2462428.16     13738583.34      2463171.47     13737823.55
      2463173.38     13737181.03      2462926.05     13736914.57
      2462978.62      13736576.5      2463215.56     13736231.59
      2463179.66     13736130.26      2463869.55     13735827.47
      2463777.26     13735330.94      2464774.24     13733014.31
      2464328.34     13732126.72      2464928.54     13730626.47
      2465119.17      13730427.3      2465333.14     13729868.93
      2465680.61     13729430.59      2465864.61      13729335.1
      2466251.16     13728697.55        2466475.       13728725.

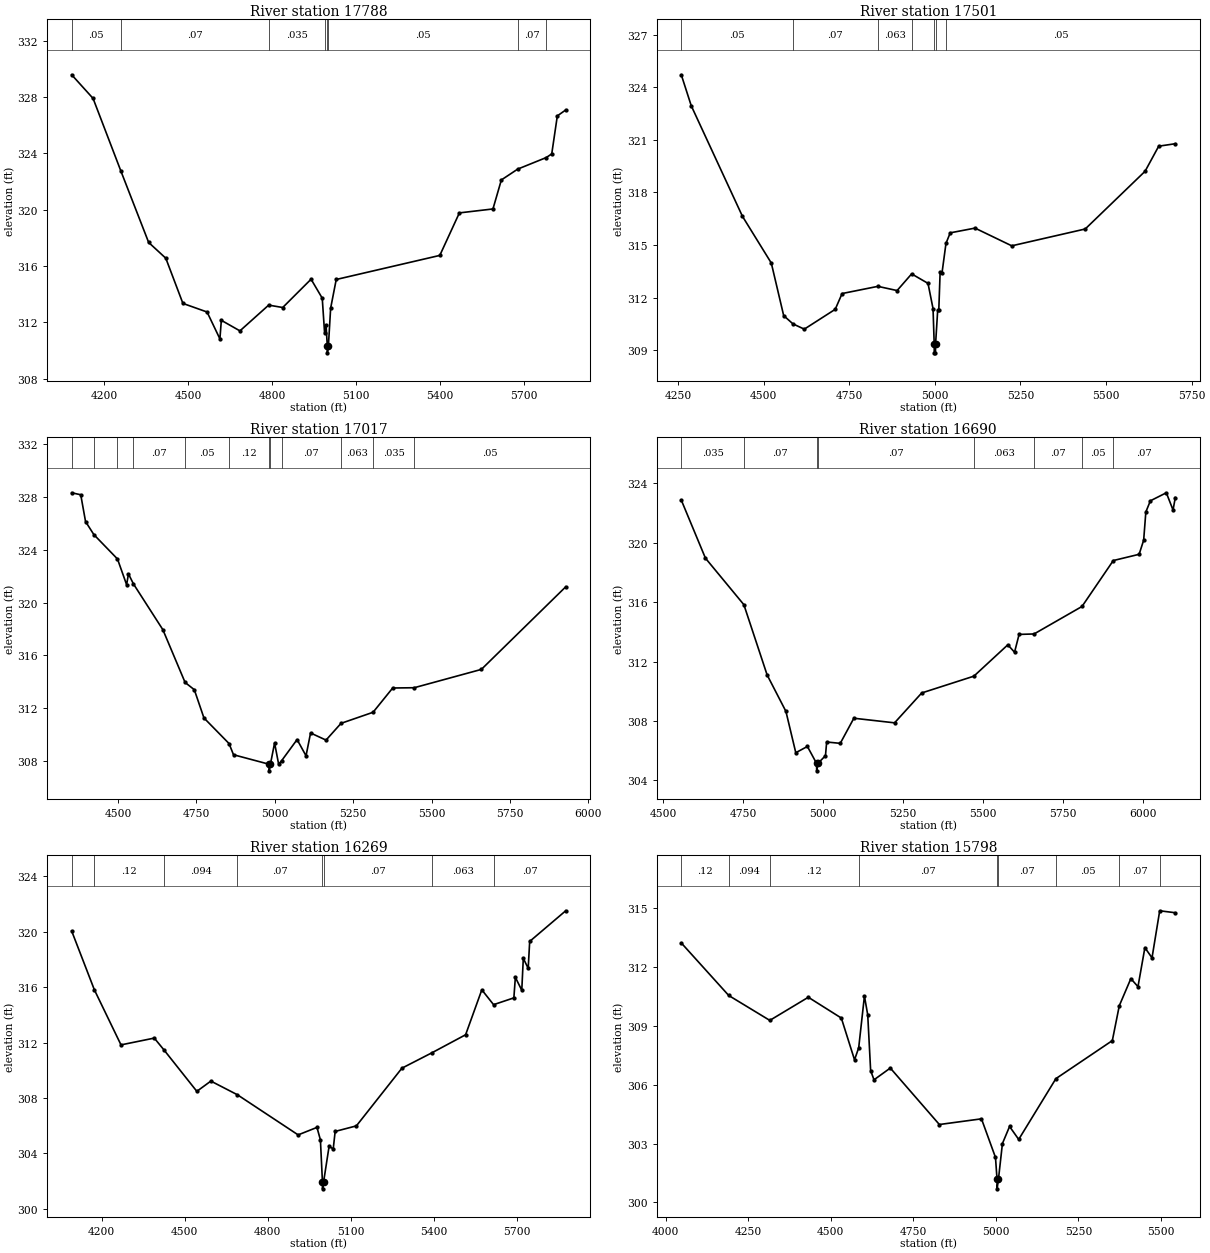
Type RM Length L Ch R = 1 ,17788   ,287,287,287
BEGIN DESCRIPTION:
TINSLEY CREEK 38.0
END DESCRIPTION:
XS GIS Cut Line= 3
      2463325.04     13741874.99      2462518.08     13742036.52
      2461575.03       13742075.
#Sta/Elev= 30
  4083.8  329.58  4160.3   327.9  4260.2  322.72  4359.1  317.67  4420.4  316.55
  4481.6  313.34    4568  312.73  4613.9  310.82    4619  312.14  4685.5  311.39
  4788.3  313.22  4838.5  313.05  4939.9  315.06  4979.9  313.71  4988.3  311.23
  4993.5  311.81  4997.9  310.33  4998.2  309.83  5001.9  310.33  5009.9     313
  5029.9  315.04  5400.3  316.75  5470.3  319.77  5590.4  320.05  5620.4  322.11
  5678.9  322.88  5780.9   323.7  5800.6  323.96  5820.6  326.66  5850.6  327.08
#Mann= 8 ,-1 , 0
  4083.8     .05       0  4260.2     .07       0  4788.3    .035       0
  4988.3     .05       0  4997.9     .05       0  5001.9     .05       0
  5678.9     .07       0  5780.9    .063       0
Bank Sta=4997.9,5001.9
XS Rating Curve= 0 ,0
Exp/Cntr=0.3,0.1

Type RM Length L Ch R = 1 ,17501   ,484,484,484
BEGIN DESCRIPTION:
XS7855
END DESCRIPTION:
XS GIS Cut Line= 3
      2463213.03     13741832.13      2462463.57     13741768.54
      2461823.17     13742027.43
#Sta/Elev= 30
  4259.4  324.71  4288.6  322.94  4438.1  316.64  4522.3  313.98  4558.5  310.98
  4585.6  310.51  4618.7  310.21    4709  311.34  4729.1  312.24  4833.6  312.65
  4889.7  312.41  4932.2  313.36    4980  312.82  4994.7  311.38  4998.1  309.36
  4998.3  308.86  5001.8  308.86  5002.1  309.36  5008.3  311.29  5011.5  311.29
  5015.4  313.46  5020.8   313.4  5032.5   315.1  5044.9   315.7  5117.3  315.97
  5224.6  314.96  5439.2  315.92    5614  319.21  5653.8  320.64  5702.3  320.78
#Mann= 7 ,-1 , 0
  4259.4     .05       0  4585.6     .07       0  4833.6    .063       0
  4932.2    .035       0  4998.1    .035       0  5002.1    .035       0
  5032.5     .05       0
Bank Sta=4998.1,5002.1
XS Rating Curve= 0 ,0
Exp/Cntr=0.3,0.1

Type RM Length L Ch R = 1 ,17017   ,327,327,327
BEGIN DESCRIPTION:
TINSLEY CREEK 37.0
END DESCRIPTION:
XS GIS Cut Line= 3
        2463025.       13740975.      2462386.36     13741373.37
      2461824.97     13741975.03
#Sta/Elev= 30
  4352.3  328.32  4381.2  328.17  4396.5  326.14    4423  325.15  4498.4   323.3
  4527.5  321.35  4533.4  322.17  4549.3  321.41  4643.1  317.94    4714  313.94
  4743.4  313.39  4774.1  311.25  4854.1  309.31  4868.4  308.46    4982  307.74
  4982.3  307.24  4986.1  307.74  4999.4  309.35  5012.3  307.75  5021.9  308.01
  5071.2  309.61  5099.7  308.38  5114.2  310.11  5163.5  309.57  5211.3  310.84
  5313.5  311.68  5376.1  313.52  5444.6  313.54  5658.9  314.93  5927.9  321.19
#Mann= 12 ,-1 , 0
  4352.3     .12       0    4423    .094       0  4498.4     .05       0
  4549.3     .07       0    4714     .05       0  4854.1     .12       0
    4982     .05       0  4986.1     .12       0  5021.9     .07       0
  5211.3    .063       0  5313.5    .035       0  5444.6     .05       0
Bank Sta=4982,4986.1
XS Rating Curve= 0 ,0
Exp/Cntr=0.3,0.1

Type RM Length L Ch R = 1 ,16690   ,421,421,421
BEGIN DESCRIPTION:
TINSLEY CREEK 36.0
END DESCRIPTION:
XS GIS Cut Line= 3
      2462775.01       13740825.        2462375.       13741025.
      2461625.01     13741824.99
#Sta/Elev= 30
  4557.4  322.87  4632.9  318.96    4753  315.83  4825.7   311.1  4884.4  308.65
  4915.2  305.87  4951.5  306.29  4980.2  305.15  4980.5  304.65  4984.3  305.15
    5008  305.67  5011.7  306.59  5054.2   306.5  5096.7  308.19  5223.9  307.88
  5308.7  309.89  5471.7  311.02  5577.8  313.13  5598.8  312.63    5613  313.83
  5659.8  313.86  5809.6  315.71  5907.4   318.8  5988.1  319.22  6002.3  320.17
  6009.1  322.07  6023.3  322.82  6073.1  323.36  6094.1   322.2  6101.2  323.04
#Mann= 8 ,-1 , 0
  4557.4    .035       0    4753     .07       0  4980.2     .05       0
  4984.3     .07       0  5471.7    .063       0  5659.8     .07       0
  5809.6     .05       0  5907.4     .07       0
Bank Sta=4980.2,4984.3
XS Rating Curve= 0 ,0
Exp/Cntr=0.3,0.1

Type RM Length L Ch R = 1 ,16269   ,471,471,471
BEGIN DESCRIPTION:
TINSLEY CREEK 35.0
END DESCRIPTION:
XS GIS Cut Line= 3
      2462710.82     13740439.18      2462190.46     13740528.02
      2461674.99     13741675.02
#Sta/Elev= 30
  4091.8  320.04  4173.8   315.8    4270  311.83  4390.3  312.32  4425.2  311.47
  4544.1  308.48  4594.8  309.22    4691  308.23  4910.2  305.34  4978.2  305.88
  4990.7  304.98    4998  301.95  4998.3  301.45  5002.2  301.95    5022  304.51
    5037  304.33    5044  305.59  5120.7  305.99  5285.2  310.15  5394.6  311.27
  5515.4  312.56    5574   315.8  5616.5  314.73  5689.8  315.22  5695.2   316.7
  5718.4  315.77  5723.9  318.07  5741.6  317.35    5747  319.29  5877.2   321.5
#Mann= 8 ,-1 , 0
  4091.8    .094       0  4173.8     .12       0  4425.2    .094       0
    4691     .07       0    4998     .05       0  5002.2     .07       0
  5394.6    .063       0  5616.5     .07       0
Bank Sta=4998,5002.2
XS Rating Curve= 0 ,0
Exp/Cntr=0.3,0.1

Type RM Length L Ch R = 1 ,15798   ,465,465,465
BEGIN DESCRIPTION:
TINSLEY CREEK 34.0
END DESCRIPTION:
XS GIS Cut Line= 3
      2462529.91     13740359.87       2461952.5     13740353.52
      2461275.01     13740974.99
#Sta/Elev= 30
  4046.9  313.23  4190.7  310.55  4315.1  309.28  4431.8  310.46  4531.8   309.4
  4571.8  307.27  4584.4  307.88  4601.8  310.52  4611.8  309.56  4620.6  306.72
  4630.8  306.25  4680.2  306.85  4828.8  303.97  4956.4  304.26  4998.9  302.29
  5003.5  301.19  5003.8  300.69  5007.9  301.19  5019.9     303  5041.5  303.87
  5069.2  303.21  5181.9  306.31  5352.9  308.25    5374  310.03    5409  311.41
  5430.6     311  5451.5  312.99  5473.1  312.47  5496.4  314.87  5543.7  314.77
#Mann= 9 ,-1 , 0
  4046.9     .12       0  4190.7    .094       0  4315.1     .12       0
  4584.4     .07       0  5003.5     .05       0  5007.9     .07       0
  5181.9     .05       0    5374     .07       0  5496.4     .05       0
Bank Sta=5003.5,5007.9
XS Rating Curve= 0 ,0
Exp/Cntr=0.3,0.1

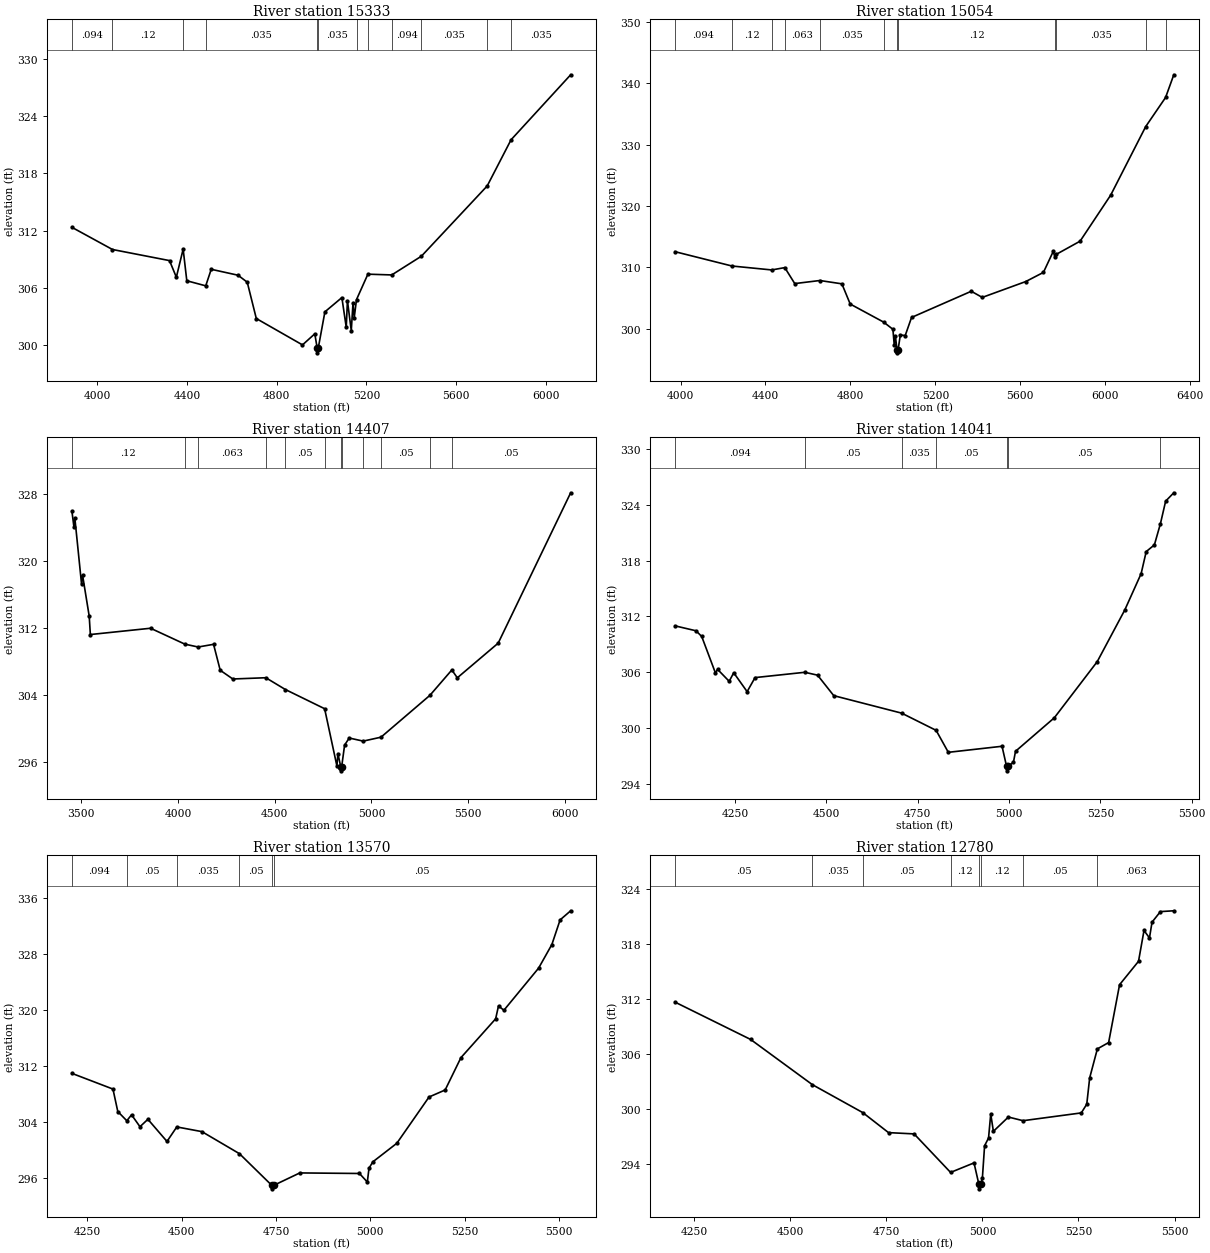
Type RM Length L Ch R = 1 ,15333   ,279,279,279
BEGIN DESCRIPTION:
TINSLEY CREEK 33.0
END DESCRIPTION:
XS GIS Cut Line= 3
       2462482.3     13740347.17      2461593.98     13740175.85
      2460359.85     13740642.22
#Sta/Elev= 30
  3886.6  312.36  4067.5  310.04  4321.8  308.88  4352.3  307.14  4382.6  310.08
  4398.9  306.77  4483.3  306.24  4507.8  307.97  4627.3  307.35  4668.4  306.62
  4708.8  302.82  4914.7  300.06  4969.7  301.22  4980.2  299.73  4980.5  299.23
  4985.1  299.73  5014.7  303.52  5090.4  305.01  5109.9   301.9  5115.2  304.69
  5132.3  301.55  5140.1  304.48  5145.4   302.9  5155.6   304.8  5206.4  307.46
  5312.8  307.38    5445  309.34  5738.4  316.69  5844.8  321.52  6110.6  328.32
#Mann= 12 ,-1 , 0
  3886.6    .094       0  4067.5     .12       0  4382.6    .063       0
  4483.3    .035       0  4980.2    .035       0  4985.1    .035       0
  5155.6     .07       0  5206.4    .035       0  5312.8    .094       0
    5445    .035       0  5738.4    .063       0  5844.8    .035       0
Bank Sta=4980.2,4985.1
XS Rating Curve= 0 ,0
Exp/Cntr=0.3,0.1

Type RM Length L Ch R = 1 ,15054   ,647,647,647
BEGIN DESCRIPTION:
TINSLEY CREEK 32.0
END DESCRIPTION:
XS GIS Cut Line= 3
      2462504.56     13740337.66      2461573.15     13740054.72
      2460319.74     13739487.06
#Sta/Elev= 30
  3973.9  312.57    4242  310.24  4429.5   309.6  4490.9  309.98  4537.8  307.38
  4656.1  307.88  4759.8  307.34  4799.1  304.05  4956.5  301.11  5000.2  299.94
  5006.5  297.37    5012   298.8  5019.6  296.61    5020  296.11  5024.6  296.61
  5035.1  299.01  5058.2  298.93    5088  301.87  5369.4  306.13  5421.1  305.13
  5625.9  307.71  5709.2   309.2  5755.4  312.61  5762.8  311.75  5769.4  312.13
  5881.9  314.28    6026  321.77    6191  332.93  6284.7  337.67  6323.3  341.36
#Mann= 12 ,-1 , 0
  3973.9    .094       0    4242     .12       0  4429.5    .094       0
  4490.9    .063       0  4656.1    .035       0  4956.5     .12       0
  5019.6     .05       0  5024.6     .12       0  5762.8    .094       0
  5769.4    .035       0    6191    .063       0  6284.7    .035       0
Bank Sta=5019.6,5024.6
XS Rating Curve= 0 ,0
Exp/Cntr=0.3,0.1

Type RM Length L Ch R = 1 ,14407   ,366,366,366
BEGIN DESCRIPTION:
TINSLEY CREEK 31.0
END DESCRIPTION:
XS GIS Cut Line= 3
      2462876.92     13740033.45      2461437.05     13739638.29
       2460510.5     13739075.09
#Sta/Elev= 30
  3452.1  325.97  3462.2  324.13  3467.4   325.1  3501.8  317.28    3507  318.34
  3541.5  313.42  3547.4  311.23  3858.5  311.98    4036  310.08  4104.4  309.74
  4184.1  310.06  4218.5  306.96  4283.7  305.92  4454.1  306.07  4555.4  304.66
    4758  302.37  4821.5  295.53  4826.7  297.01  4841.1  295.45  4841.5  294.95
  4846.2  295.45  4861.2  298.02  4885.1  298.87  4957.3   298.5  5049.4  298.97
  5302.2  303.97  5415.5     307  5443.7  306.06  5654.9   310.2  6029.5  328.16
#Mann= 12 ,-1 , 0
  3452.1     .12       0    4036    .094       0  4104.4    .063       0
  4454.1    .094       0  4555.4     .05       0    4758    .063       0
  4841.1    .035       0  4846.2    .063       0  4957.3    .035       0
  5049.4     .05       0  5302.2    .063       0  5415.5     .05       0
Bank Sta=4841.1,4846.2
XS Rating Curve= 0 ,0
Exp/Cntr=0.3,0.1

Type RM Length L Ch R = 1 ,14041   ,471,471,471
BEGIN DESCRIPTION:
TINSLEY CREEK 30.0
END DESCRIPTION:
XS GIS Cut Line= 3
      2462275.02     13739725.01        2461475.       13739275.
      2461275.01     13738875.01
#Sta/Elev= 30
    4086  310.98  4143.4  310.45    4159  309.84  4196.6  305.91  4202.3  306.31
  4234.2  305.02  4246.6  305.94  4283.3  303.91    4305  305.42  4441.2  305.99
  4476.1  305.68  4520.4  303.48  4706.2   301.6  4800.6  299.75    4834  297.39
    4981  298.04  4993.3   295.9  4993.7   295.4  4998.6   295.9  5012.3  296.34
  5017.9   297.5  5124.1   301.1  5241.5  307.13  5316.9  312.68  5361.7  316.59
  5375.6  318.96    5398  319.68  5414.6  321.97  5428.8  324.38  5451.1  325.28
#Mann= 7 ,-1 , 0
    4086    .094       0  4441.2     .05       0  4706.2    .035       0
  4800.6     .05       0  4993.3     .05       0  4998.6     .05       0
  5414.6    .063       0
Bank Sta=4993.3,4998.6
XS Rating Curve= 0 ,0
Exp/Cntr=0.3,0.1

Type RM Length L Ch R = 1 ,13570   ,790,790,790
BEGIN DESCRIPTION:
TINSLEY CREEK 29.0
END DESCRIPTION:
XS GIS Cut Line= 3
      2462275.01     13739675.01        2461825.       13739025.
      2461474.99     13738624.99
#Sta/Elev= 30
  4209.3  310.99  4318.1  308.75  4330.9  305.55  4354.8  304.23  4367.4  305.08
  4389.7  303.38  4410.7  304.44  4461.3  301.28  4487.3  303.35  4553.9  302.68
  4653.5  299.53  4739.1  295.02  4739.5  294.52  4744.4  295.02  4813.4  296.79
  4971.5  296.71  4992.4  295.49  4996.8  297.46    5007  298.37  5070.6  301.02
    5156  307.62  5198.7  308.62  5240.5  313.23  5332.5  318.77  5340.1  320.61
  5354.4  319.99  5446.4     326  5481.6  329.37  5503.4  332.88  5531.4  334.18
#Mann= 6 ,-1 , 0
  4209.3    .094       0  4354.8     .05       0  4487.3    .035       0
  4653.5     .05       0  4739.1     .05       0  4744.4     .05       0
Bank Sta=4739.1,4744.4
XS Rating Curve= 0 ,0
Exp/Cntr=0.3,0.1

Type RM Length L Ch R = 1 ,12780   ,302,302,302
BEGIN DESCRIPTION:
TINSLEY CREEK 28.0
END DESCRIPTION:
XS GIS Cut Line= 4
      2462736.15     13739500.02      2462339.58     13738779.84
      2462374.48      13738551.4      2462190.67     13738389.78
#Sta/Elev= 30
    4200   311.7  4396.7  307.63  4557.4   302.7  4688.7  299.65  4755.6  297.47
  4822.2  297.33  4917.1  293.13  4978.1  294.17  4990.7  291.84  4991.1  291.34
  4996.2  291.84  4999.8  292.47  5005.6  296.04  5015.9  296.88  5021.6   299.5
  5028.5  297.61  5067.5  299.17  5105.7  298.77  5257.3  299.62  5271.5  300.57
  5279.1  303.44  5299.1   306.6  5328.4  307.29  5356.9   313.6  5406.2  316.15
  5420.5  319.51  5434.7   318.7  5441.4  320.42  5463.2  321.57    5498  321.66
#Mann= 8 ,-1 , 0
    4200     .05       0  4557.4    .035       0  4688.7     .05       0
  4917.1     .12       0  4990.7     .05       0  4996.2     .12       0
  5105.7     .05       0  5299.1    .063       0
Bank Sta=4990.7,4996.2
XS Rating Curve= 0 ,0
Exp/Cntr=0.3,0.1

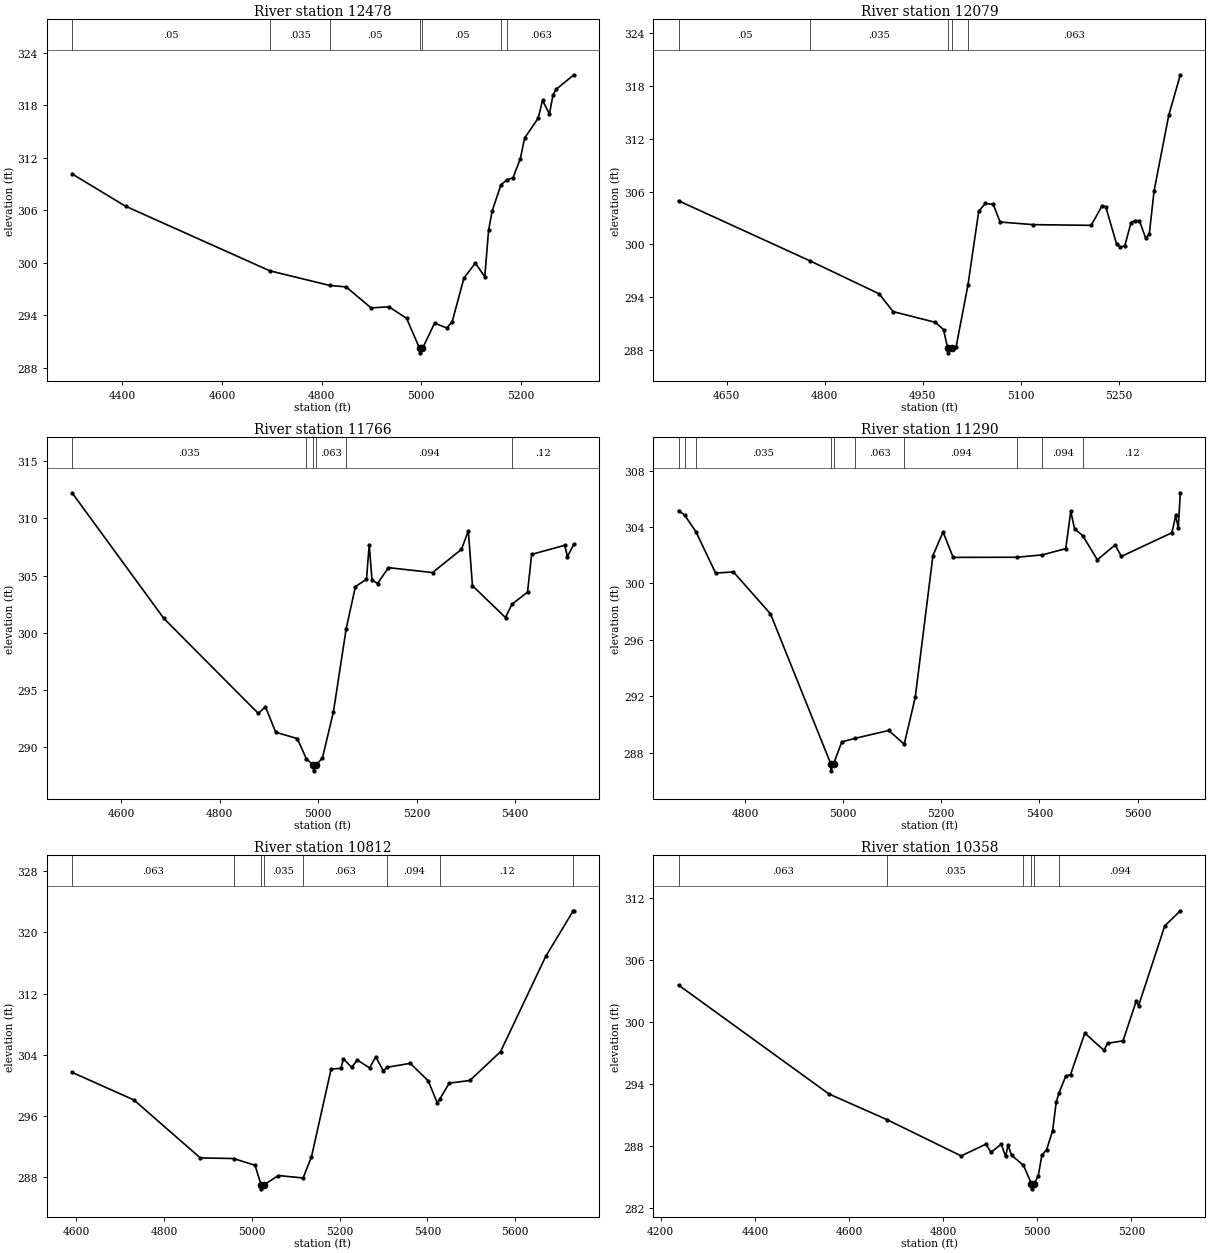
Type RM Length L Ch R = 1 ,12478   ,399,399,399
BEGIN DESCRIPTION:
TINSLEY CREEK 27.0
END DESCRIPTION:
XS GIS Cut Line= 3
      2463043.94     13738986.08      2462447.45     13738535.54
      2462234.86     13738386.41
#Sta/Elev= 30
  4299.3  310.15  4406.7  306.46    4696  299.09  4816.7  297.41  4849.4  297.25
  4899.5  294.85  4935.3  294.98  4970.7  293.66    4997  290.22  4997.4  289.72
  5002.6  290.22    5027  293.12  5051.4  292.55  5062.3  293.27  5085.8  298.25
  5108.7  299.97  5127.7  298.41  5135.3   303.7  5142.5  305.91  5160.1   308.9
  5172.7   309.5  5184.3  309.69  5199.1  311.91  5207.8  314.26  5234.9  316.51
  5243.6  318.54  5257.5     317  5264.5  319.12  5270.6  319.79  5306.5  321.47
#Mann= 7 ,-1 , 0
  4299.3     .05       0    4696    .035       0  4816.7     .05       0
    4997     .05       0  5002.6     .05       0  5160.1    .035       0
  5172.7    .063       0
Bank Sta=4997,5002.6
XS Rating Curve= 0 ,0
Exp/Cntr=0.3,0.1

Type RM Length L Ch R = 1 ,12079   ,313,313,313
BEGIN DESCRIPTION:
TINSLEY CREEK 26.0
END DESCRIPTION:
XS GIS Cut Line= 3
      2463104.34     13738473.48      2462754.32     13738273.47
      2462429.21     13738107.62
#Sta/Elev= 30
  4576.4  304.96  4778.1  298.12  4883.3   294.4  4904.9  292.37  4969.7  291.15
    4982  290.33  4988.5  288.19    4989  287.69  4994.3  288.19  5001.2  288.34
  5019.4  295.39  5035.9  303.76  5046.1  304.66  5058.1  304.55  5068.6  302.55
  5119.2  302.25  5208.1  302.17  5224.7  304.39  5230.3  304.29  5246.9  300.05
  5252.5   299.7  5259.4  299.83  5269.1  302.49  5274.8  302.71  5281.9  302.69
  5291.4  300.73    5297  301.18  5304.3  306.08  5326.8  314.67  5344.5  319.27
#Mann= 5 ,-1 , 0
  4576.4     .05       0  4778.1    .035       0  4988.5    .035       0
  4994.3    .035       0  5019.4    .063       0
Bank Sta=4988.5,4994.3
XS Rating Curve= 0 ,0
Exp/Cntr=0.3,0.1

Type RM Length L Ch R = 1 ,11766   ,476,476,476
BEGIN DESCRIPTION:
TINSLEY CREEK 25.0
END DESCRIPTION:
XS GIS Cut Line= 4
      2463324.97     13738324.98        2462925.       13738025.
        2462825.       13737975.      2462460.85     13737792.93
#Sta/Elev= 30
    4500  312.23  4686.4  301.25  4878.1  292.96  4892.7  293.54  4913.5  291.31
  4957.3  290.76  4975.6     289  4989.8  288.44  4990.3  287.94  4995.6  288.44
  5008.4  289.07  5030.7  293.09  5056.6  300.36  5075.4  304.04  5097.8  304.67
  5103.4   307.7    5109  304.62  5120.2   304.3  5142.5  305.69    5232  305.26
  5290.7  307.29  5304.6   308.9    5313  304.11  5380.1  301.33  5392.9  302.48
  5424.8  303.55  5433.2  306.85  5500.3  307.64  5505.9  306.66  5518.9  307.74
#Mann= 6 ,-1 , 0
    4500    .035       0  4975.6    .063       0  4989.8     .05       0
  4995.6    .063       0  5056.6    .094       0  5392.9     .12       0
Bank Sta=4989.8,4995.6
XS Rating Curve= 0 ,0
Exp/Cntr=0.3,0.1

Type RM Length L Ch R = 1 ,11290   ,478,478,478
BEGIN DESCRIPTION:
TINSLEY CREEK 24.0
END DESCRIPTION:
XS GIS Cut Line= 4
      2463475.02     13737825.01        2463175.       13737675.
        2462975.       13737625.      2462508.44     13737508.36
#Sta/Elev= 30
  4664.6  305.16  4676.8  304.86    4700  303.67  4740.1  300.74  4776.4  300.82
  4851.9  297.85  4974.8  287.22  4975.2  286.72  4980.6  287.22  4997.2  288.77
  5023.8  289.02  5092.8  289.58  5124.5  288.61  5146.9  291.92    5183  301.98
  5203.6  303.65  5224.2  301.85  5354.3  301.86  5406.2  302.03  5453.6  302.47
  5463.9  305.12  5471.6  303.87  5488.3  303.39    5518  301.68  5554.1  302.73
    5567  301.92    5670   303.6  5677.8  304.82  5682.9  303.92  5687.1  306.43
#Mann= 10 ,-1 , 0
  4664.6    .094       0  4676.8    .063       0    4700    .035       0
  4974.8    .035       0  4980.6    .035       0  5023.8    .063       0
  5124.5    .094       0  5354.3     .12       0  5406.2    .094       0
  5488.3     .12       0
Bank Sta=4974.8,4980.6
XS Rating Curve= 0 ,0
Exp/Cntr=0.3,0.1

Type RM Length L Ch R = 1 ,10812   ,454,454,454
BEGIN DESCRIPTION:
TINSLEY CREEK 23.0
END DESCRIPTION:
XS GIS Cut Line= 4
      2463574.96     13737274.99        2463175.       13737225.
        2462975.       13737325.      2462472.61      13737203.7
#Sta/Elev= 30
  4590.4  301.71  4731.4   298.1  4882.6  290.53  4958.6  290.45  5007.4  289.56
  5021.3  286.99  5021.8  286.49  5027.2  286.99  5060.6  288.23  5116.9  287.91
    5136  290.68  5180.7  302.13  5203.1  302.24  5208.7  303.48  5227.4  302.37
  5240.6  303.31  5268.5  302.29  5282.5  303.76  5299.4  301.92  5309.2  302.38
  5361.1  302.89  5402.2  300.59  5422.8  297.69  5428.6  298.25    5450   300.3
    5497  300.65  5566.8  304.41  5669.7  316.85  5732.5  322.82  5733.9  322.82
#Mann= 8 ,-1 , 0
  4590.4    .063       0  4958.6    .035       0  5021.3    .035       0
  5027.2    .035       0  5116.9    .063       0  5309.2    .094       0
  5428.6     .12       0  5732.5    .094       0
Bank Sta=5021.3,5027.2
XS Rating Curve= 0 ,0
Exp/Cntr=0.3,0.1

Type RM Length L Ch R = 1 ,10358   ,450,450,450
BEGIN DESCRIPTION:
TINSLEY CREEK 22.0
END DESCRIPTION:
XS GIS Cut Line= 3
      2463624.97     13737174.99        2462925.       13736875.
      2462624.99       13736925.
#Sta/Elev= 30
    4238  303.59  4557.1  293.05  4680.4  290.56  4838.2  287.04  4890.8  288.18
  4901.6  287.39  4923.4  288.18  4932.5  286.99  4937.9  288.08  4945.2  287.11
  4970.5  286.13  4987.5  284.35    4988  283.85  4993.5  284.35  5002.1  285.14
  5009.7  287.12  5019.8  287.64  5032.5  289.49  5040.1  292.25  5046.2  293.16
  5060.4  294.77  5070.5  294.92  5100.9  298.93  5141.5  297.27  5149.1  297.95
    5182  298.19  5209.9  302.02    5215  301.59  5270.7  309.33  5303.7  310.79
#Mann= 6 ,-1 , 0
    4238    .063       0  4680.4    .035       0  4970.5    .063       0
  4987.5     .05       0  4993.5    .063       0  5046.2    .094       0
Bank Sta=4987.5,4993.5
XS Rating Curve= 0 ,0
Exp/Cntr=0.3,0.1

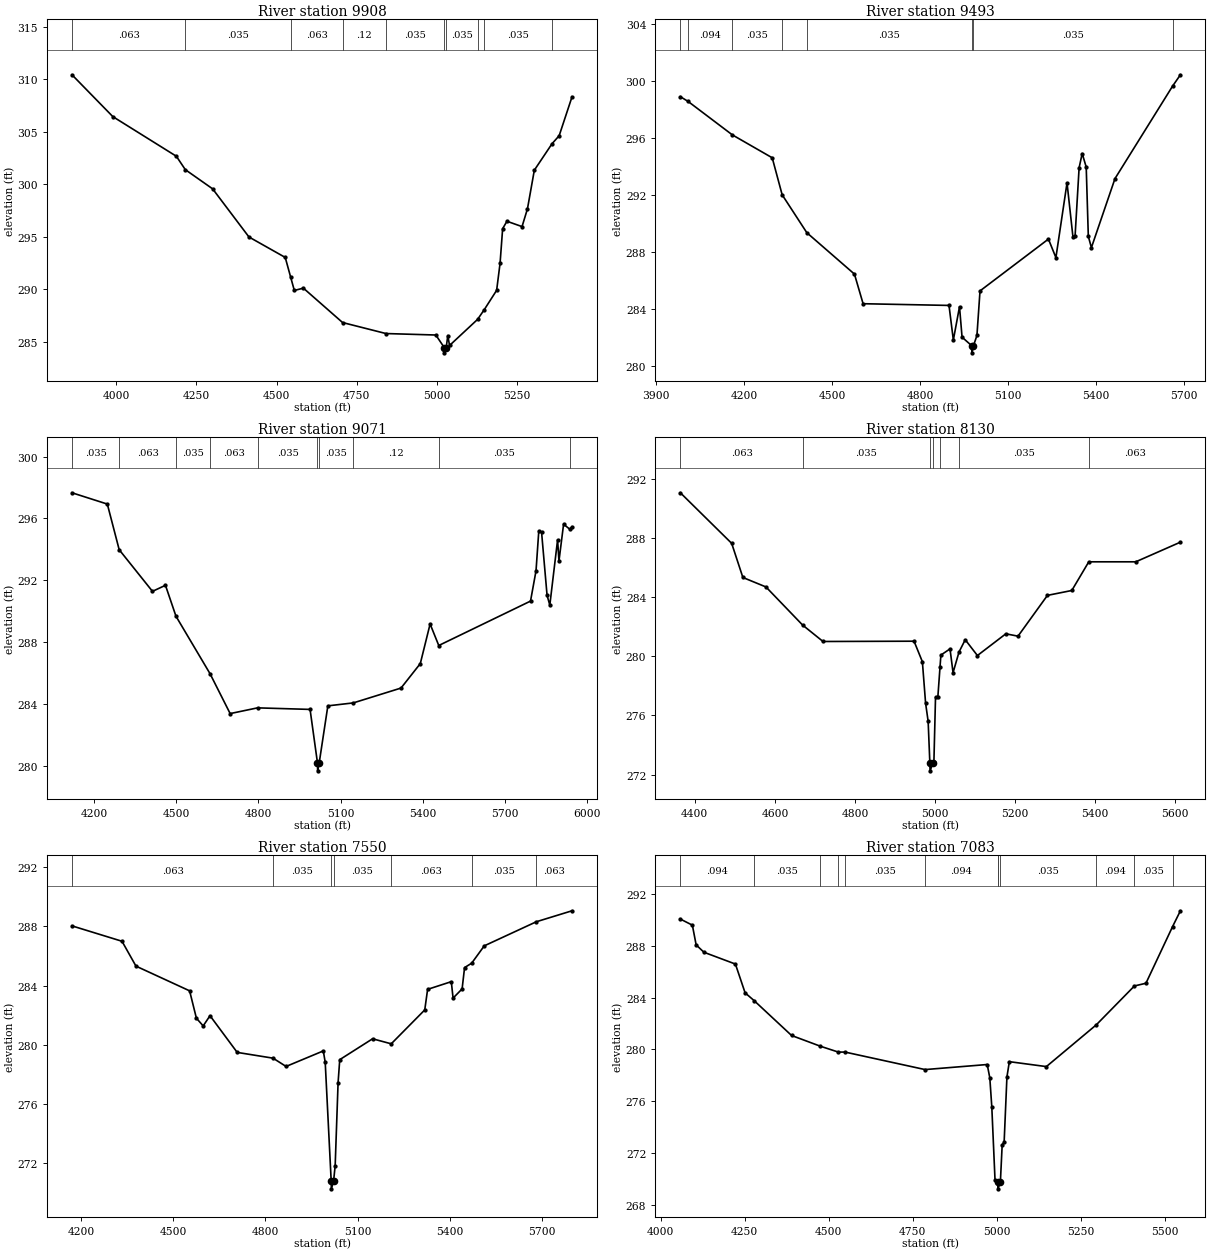
Type RM Length L Ch R = 1 ,9908    ,415,415,415
BEGIN DESCRIPTION:
TINSLEY CREEK 21.0
END DESCRIPTION:
XS GIS Cut Line= 3
      2463875.01     13737275.01        2463075.       13736475.
      2462674.98     13736625.01
#Sta/Elev= 30
  3862.4  310.44  3989.7  306.45  4187.7  302.67  4215.7  301.39  4300.8  299.56
    4414  294.97  4527.1  293.02  4543.9  291.15  4555.4  289.87  4583.7  290.09
  4705.8  286.81  4841.1  285.76  4996.5  285.62  5022.8  284.42  5023.3  283.92
  5028.8  284.42  5033.8  285.57  5039.2  284.62  5126.6  287.11  5147.5  288.04
    5186  289.88  5196.7  292.46  5204.7  295.76  5218.1  296.47  5265.2  295.96
  5282.1  297.66  5303.5  301.34  5358.6  303.86  5380.9  304.63    5421  308.34
#Mann= 10 ,-1 , 0
  3862.4    .063       0  4215.7    .035       0  4543.9    .063       0
  4705.8     .12       0  4841.1    .035       0  5022.8    .035       0
  5028.8    .035       0  5126.6    .063       0  5147.5    .035       0
  5358.6    .063       0
Bank Sta=5022.8,5028.8
XS Rating Curve= 0 ,0
Exp/Cntr=0.3,0.1

Type RM Length L Ch R = 1 ,9493    ,422,422,422
BEGIN DESCRIPTION:
TINSLEY CREEK 20.0
END DESCRIPTION:
XS GIS Cut Line= 3
      2464016.94      13736708.6        2463175.       13736125.
        2462525.       13736325.
#Sta/Elev= 30
    3983   298.9  4009.2  298.57  4160.1  296.22  4296.1  294.61    4330  292.01
    4414  289.35  4576.4  286.44  4605.9  284.36  4898.7  284.24  4913.5  281.81
  4934.5  284.15  4943.2  282.01  4976.1  281.41  4976.6  280.91  4982.1  281.41
  4993.9  282.13  5004.4  285.26  5237.6   288.9  5263.1   287.6    5301  292.85
  5321.3  289.03  5328.5  289.13  5342.2  293.91  5352.7  294.91  5366.4  293.96
  5373.6  289.09  5384.1   288.3  5464.5  293.15  5660.7  299.64  5687.5  300.44
#Mann= 8 ,-1 , 0
    3983    .063       0  4009.2    .094       0  4160.1    .035       0
    4330    .063       0    4414    .035       0  4976.1    .035       0
  4982.1    .035       0  5660.7    .063       0
Bank Sta=4976.1,4982.1
XS Rating Curve= 0 ,0
Exp/Cntr=0.3,0.1

Type RM Length L Ch R = 1 ,9071    ,941,941,941
BEGIN DESCRIPTION:
TINSLEY CREEK 19.0
END DESCRIPTION:
XS GIS Cut Line= 3
      2464393.98     13736154.49      2463998.81     13736004.59
      2462604.39     13735854.71
#Sta/Elev= 30
  4119.9  297.66  4248.9  296.93  4292.2  293.98  4413.7  291.29  4461.1  291.68
  4499.5  289.68  4623.7  285.97  4697.2  283.39  4797.2  283.76  4988.9  283.66
    5016  280.19  5016.5  279.69  5022.1  280.19  5053.8  283.89  5146.6  284.08
  5320.8  285.04  5391.2  286.62    5427  289.18  5458.6  287.79  5793.5  290.66
  5813.6  292.62  5823.7   295.2  5833.8  295.12  5853.9  291.03  5863.9   290.4
  5892.3  294.62  5897.3  293.25  5914.2  295.63  5936.4  295.31    5945  295.46
#Mann= 10 ,-1 , 0
  4119.9    .035       0  4292.2    .063       0  4499.5    .035       0
  4623.7    .063       0  4797.2    .035       0    5016    .035       0
  5022.1    .035       0  5146.6     .12       0  5458.6    .035       0
  5936.4    .063       0
Bank Sta=5016,5022.1
XS Rating Curve= 0 ,0
Exp/Cntr=0.3,0.1

Type RM Length L Ch R = 1 ,8130    ,580,580,580
BEGIN DESCRIPTION:
TINSLEY CREEK 18.0
END DESCRIPTION:
XS GIS Cut Line= 3
      2464275.01     13735725.01        2463775.       13735325.
      2463175.01       13735225.
#Sta/Elev= 30
    4364  291.06  4492.1  287.64  4520.1  285.33  4577.7  284.69  4669.3  282.11
  4720.2     281  4947.5  281.02  4968.3  279.63  4976.3  276.83  4982.7   275.6
    4987  272.75  4987.5  272.25  4994.4  272.75  4997.1  272.88  5001.1  277.23
  5006.9  277.23  5012.3  279.26  5014.5  280.08  5037.3   280.5  5044.9  278.89
  5059.8  280.29  5075.3  281.12  5105.7  280.05  5176.7  281.52  5207.1  281.36
  5280.6  284.12  5341.4  284.45  5383.8  286.39  5501.1  286.39  5612.6  287.72
#Mann= 7 ,-1 , 0
    4364    .063       0  4669.3    .035       0    4987    .035       0
  4994.4    .035       0  5012.3    .063       0  5059.8    .035       0
  5383.8    .063       0
Bank Sta=4987,4994.4
XS Rating Curve= 0 ,0
Exp/Cntr=0.3,0.1

Type RM Length L Ch R = 1 ,7550    ,467,467,467
BEGIN DESCRIPTION:
TINSLEY CREEK 17.0
END DESCRIPTION:
XS GIS Cut Line= 3
      2464770.96     13735177.93      2464071.48     13734846.36
      2463281.13     13734523.86
#Sta/Elev= 30
  4170.5  288.03  4333.3  286.99  4378.8  285.31  4553.4  283.64  4575.5  281.79
  4597.6  281.27  4619.8  281.96  4708.3  279.48    4825  279.09  4867.4  278.53
  4988.6  279.58  4994.8  278.81  5014.3  270.76  5014.8  270.26  5021.9  270.76
  5027.2  271.82  5036.7  277.44  5042.1  278.99    5149   280.4  5209.7  280.06
  5318.8  282.35  5328.1  283.74  5405.2  284.26    5411  283.15  5440.4  283.77
  5448.4  285.21  5471.6  285.51  5512.5  286.68  5682.2  288.31  5798.2  289.05
#Mann= 7 ,-1 , 0
  4170.5    .063       0    4825    .035       0  5014.3    .035       0
  5021.9    .035       0  5209.7    .063       0  5471.6    .035       0
  5682.2    .063       0
Bank Sta=5014.3,5021.9
XS Rating Curve= 0 ,0
Exp/Cntr=0.3,0.1

Type RM Length L Ch R = 1 ,7083    ,449,449,449
BEGIN DESCRIPTION:
TINSLEY CREEK 16.0
END DESCRIPTION:
XS GIS Cut Line= 3
      2465048.01     13734796.38      2464257.71     13734451.19
      2463725.04     13734125.02
#Sta/Elev= 30
  4058.9  290.05  4094.6  289.58  4105.8  288.06    4129  287.49  4222.6  286.58
  4251.4  284.36  4278.2  283.76  4389.6  281.07  4475.4  280.24  4528.6  279.79
  4548.6  279.79  4786.6  278.44  4971.4  278.83  4979.1   277.8    4985  275.57
  4994.6  269.92  5002.2  269.75  5002.7  269.74  5003.2  269.24  5010.5  269.74
  5015.9  272.65  5021.7  272.84    5030  277.87  5037.2  279.05  5147.3  278.67
  5295.7  281.89  5409.1  284.89  5443.4   285.1  5522.6  289.47  5545.9  290.69
#Mann= 12 ,-1 , 0
  4058.9    .094       0  4278.2    .035       0  4475.4    .063       0
  4528.6    .094       0  4548.6    .035       0  4786.6    .094       0
  5002.2    .035       0  5002.7     .05       0  5010.5    .035       0
  5295.7    .094       0  5409.1    .035       0  5522.6    .094       0
Bank Sta=5002.7,5010.5
XS Rating Curve= 0 ,0
Exp/Cntr=0.3,0.1

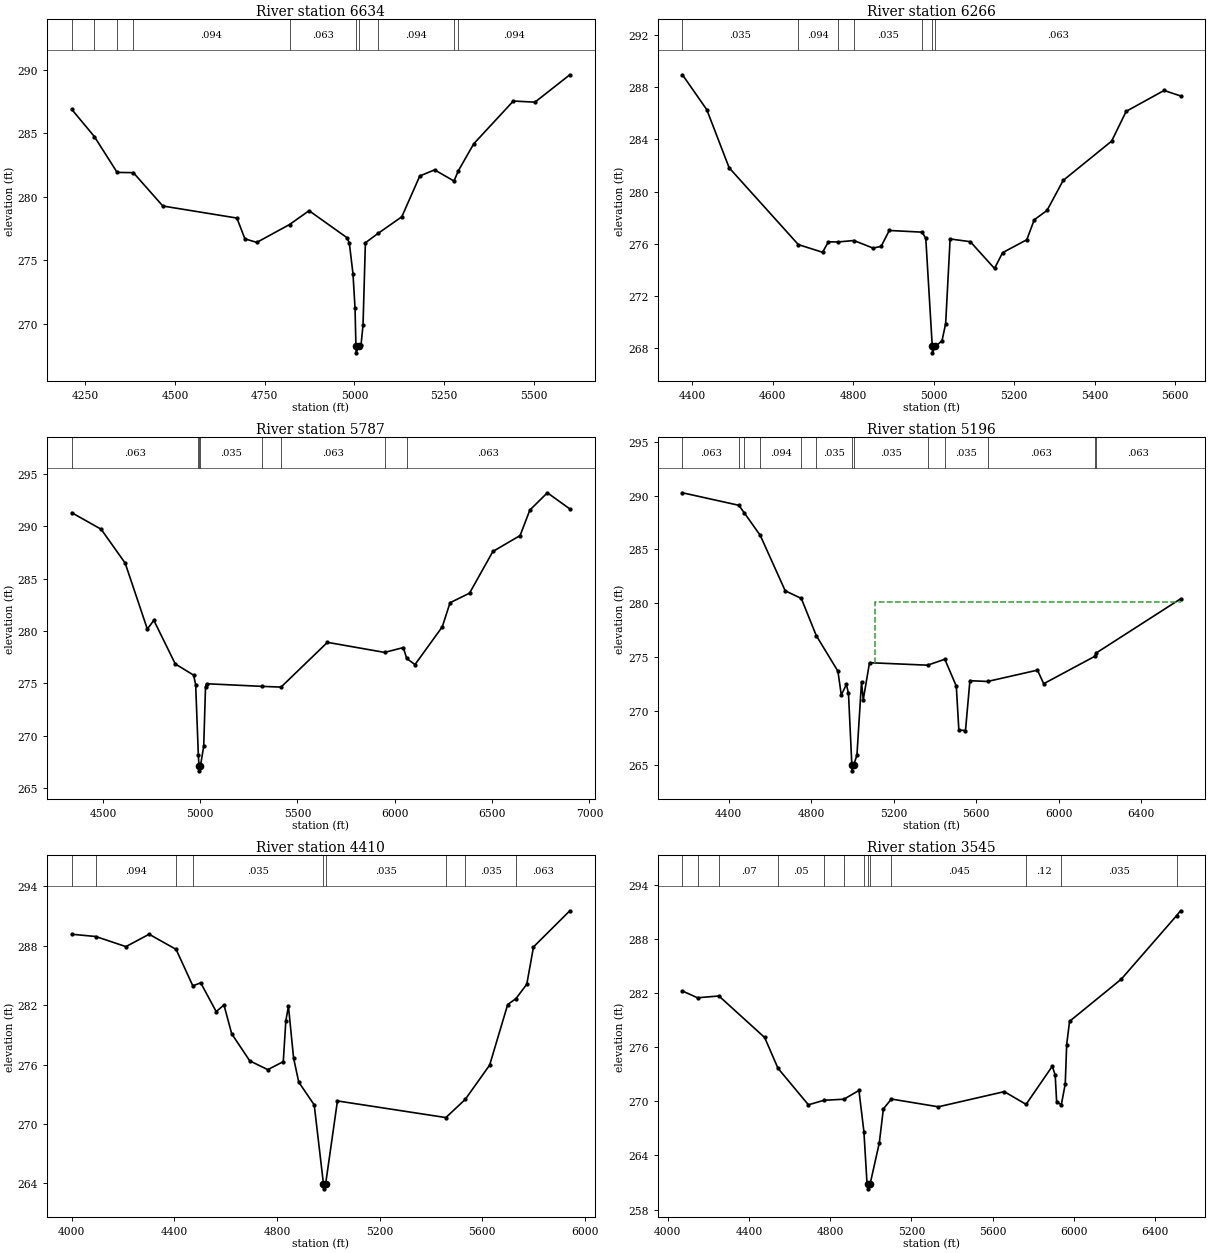
Type RM Length L Ch R = 1 ,6634    ,368,368,368
BEGIN DESCRIPTION:
TINSLEY CREEK 15.0
END DESCRIPTION:
XS GIS Cut Line= 3
        2465075.       13734375.      2464334.92     13734001.52
      2463778.08      13733965.3
#Sta/Elev= 30
  4212.8   286.9  4275.7  284.76  4339.2  281.93  4384.4  281.91  4466.4  279.28
  4672.7  278.33    4695  276.69  4728.1  276.41  4819.3  277.82  4873.7  278.91
  4979.3  276.78  4985.7  276.38    4996  273.92  5001.6  271.25  5004.2   268.2
  5004.7   267.7    5012   268.2  5018.3  268.31  5023.9  269.88  5030.5  276.38
  5065.8  277.12  5131.9  278.43    5182  281.65  5223.2  282.13  5277.2  281.25
  5289.4  282.06  5332.3  284.19  5442.5  287.56  5502.7  287.47  5599.8  289.63
#Mann= 10 ,-1 , 0
  4212.8    .063       0  4275.7    .094       0  4339.2    .063       0
  4384.4    .094       0  4819.3    .063       0  5004.2     .05       0
    5012    .063       0  5065.8    .094       0  5277.2    .063       0
  5289.4    .094       0
Bank Sta=5004.2,5012
XS Rating Curve= 0 ,0
Exp/Cntr=0.3,0.1

Type RM Length L Ch R = 1 ,6266    ,479,479,479
BEGIN DESCRIPTION:
TINSLEY CREEK 14.0
END DESCRIPTION:
XS GIS Cut Line= 3
        2465125.       13733775.      2464457.56     13733688.12
      2463894.34     13733638.15
#Sta/Elev= 30
  4375.3  288.94  4435.8  286.27  4491.4  281.82  4663.4  275.94  4723.6  275.35
  4738.3  276.15  4762.3  276.14  4801.7  276.25  4849.3  275.67  4869.4   275.8
  4889.6  277.02  4971.5  276.89  4980.4  276.41  4996.5  268.15    4997  267.65
  5004.5  268.15  5020.7  268.57  5029.8  269.89  5040.9  276.37  5091.1  276.16
  5151.3  274.11  5171.4  275.32  5231.6  276.31  5250.1  277.84  5281.8  278.55
    5322  280.85  5442.5  283.86  5478.7  286.14    5573  287.74  5613.8  287.32
#Mann= 7 ,-1 , 0
  4375.3    .035       0  4663.4    .094       0  4762.3    .063       0
  4801.7    .035       0  4971.5    .063       0  4996.5     .05       0
  5004.5    .063       0
Bank Sta=4996.5,5004.5
XS Rating Curve= 0 ,0
Exp/Cntr=0.3,0.1

Type RM Length L Ch R = 1 ,5787    ,591,591,591
BEGIN DESCRIPTION:
XS7854
END DESCRIPTION:
XS GIS Cut Line= 3
      2465310.21     13733437.71      2464492.63     13733220.27
      2462779.63     13733246.35
#Sta/Elev= 30
  4340.1  291.28  4491.2   289.7  4614.5  286.47  4728.4  280.18  4761.9  281.01
    4872  276.85  4966.3  275.78  4976.7  274.88  4990.5  268.19  4993.6  267.15
  4994.1  266.65  5001.6  267.15  5018.1  268.99  5027.4  274.66  5032.6  274.96
    5317  274.71  5415.5  274.64  5653.8  278.91  5947.5  277.95  6043.8  278.41
  6061.1  277.37  6103.8  276.79  6243.9  280.39  6283.9  282.69  6383.9   283.6
  6503.9  287.58  6643.9   289.1  6693.9  291.53  6783.9  293.18  6899.3  291.64
#Mann= 8 ,-1 , 0
  4340.1    .063       0  4990.5    .035       0  4993.6    .035       0
  5001.6    .035       0    5317    .094       0  5415.5    .063       0
  5947.5    .094       0  6061.1    .063       0
Bank Sta=4993.6,5001.6
XS Rating Curve= 0 ,0
Exp/Cntr=0.3,0.1

Type RM Length L Ch R = 1 ,5196    ,786,786,786
BEGIN DESCRIPTION:
XS7853
END DESCRIPTION:
XS GIS Cut Line= 3
      2465431.97     13732585.35      2464421.01     13732806.17
      2463130.71     13732312.55
#Sta/Elev= 30
  4175.1  290.26  4448.5   289.1  4475.4  288.39  4552.8   286.3  4673.6  281.17
  4751.7  280.46  4824.4  277.01  4929.4  273.71  4945.7   271.5  4970.4  272.48
  4980.6  271.66    4997  264.97  4997.5  264.47  5005.1  264.97  5021.6  265.93
  5043.8  272.71  5052.3  271.07  5082.6   274.5  5364.4  274.27    5448  274.82
  5503.6  272.33  5516.1  268.25  5548.2  268.21  5569.7  272.83  5655.4  272.76
  5897.5  273.81  5927.6  272.55  6176.4   275.1  6182.3   275.4  6591.4  280.42
#Mann= 13 ,-1 , 0
  4175.1    .063       0  4448.5    .094       0  4475.4    .063       0
  4552.8    .094       0  4751.7    .063       0  4824.4    .035       0
    4997    .035       0  5005.1    .035       0  5364.4    .094       0
    5448    .035       0  5655.4    .063       0  6176.4    .035       0
  6182.3    .063       0
#XS Ineff= 2 , 0
       0                  5110.9       0  280.15
Permanent Ineff=
       F       F
Bank Sta=4997,5005.1
XS Rating Curve= 0 ,0
Exp/Cntr=0.3,0.1

Type RM Length L Ch R = 1 ,4410    ,865,865,865
BEGIN DESCRIPTION:
XS7852
END DESCRIPTION:
XS GIS Cut Line= 2
      2465345.01     13732202.67      2463414.14     13732002.63
#Sta/Elev= 30
  3999.8  289.16  4093.4  288.93  4210.9  287.91  4301.4  289.16  4406.5  287.63
  4471.6  283.95  4502.5  284.25  4562.8  281.34    4593  282.02  4623.1  279.11
  4693.5  276.37  4763.9  275.48  4824.2  276.29  4834.2  280.41  4844.3  281.89
  4864.4  276.65  4884.5  274.22  4944.8  271.92  4980.8  263.94  4981.3  263.44
  4989.3  263.94  5035.3  272.32  5457.9  270.64  5533.6  272.48  5628.5  275.94
  5698.9  282.06  5730.8  282.65  5773.3  284.11  5799.4  287.88    5941  291.53
#Mann= 9 ,-1 , 0
  3999.8    .063       0  4093.4    .094       0  4406.5    .063       0
  4471.6    .035       0  4980.8    .035       0  4989.3    .035       0
  5457.9    .045       0  5533.6    .035       0  5730.8    .063       0
Bank Sta=4980.8,4989.3
XS Rating Curve= 0 ,0
Exp/Cntr=0.3,0.1

Type RM Length L Ch R = 1 ,3545    ,0,0,0
BEGIN DESCRIPTION:
XS7851
END DESCRIPTION:
XS GIS Cut Line= 4
      2465458.07     13731724.34      2465092.75     13731367.71
      2464014.27     13731289.44      2463405.41     13731898.29
#Sta/Elev= 30
    4072  282.22  4146.2  281.47  4251.6  281.67  4476.8  277.07  4542.5  273.66
  4692.3  269.61  4768.6  270.11  4867.1  270.23  4941.2   271.2  4965.6  266.65
  4981.3   260.8  4986.8   260.8  4987.3   260.3  4995.9   260.8  5041.5  265.39
  5061.5  269.16  5100.9  270.25  5332.2  269.39  5657.1  271.07  5764.3  269.66
  5893.5  273.89  5907.7   272.9  5914.8  269.96  5937.8  269.61  5957.2  271.92
  5964.3  276.28  5978.4  278.86    6233  283.53  6505.9  290.58  6524.9  291.11
#Mann= 13 ,-1 , 0
    4072    .094       0  4146.2    .063       0  4251.6     .07       0
  4542.5     .05       0  4768.6    .035       0  4867.1     .05       0
  4965.6     .12       0  4986.8     .05       0  4995.9     .12       0
  5100.9    .045       0  5764.3     .12       0  5937.8    .035       0
  6505.9    .063       0
Bank Sta=4986.8,4995.9
XS Rating Curve= 0 ,0
Exp/Cntr=0.3,0.1

Chan Stop Cuts=-1
Use User Specified Reach Order=0
Composite Channel Slope=5