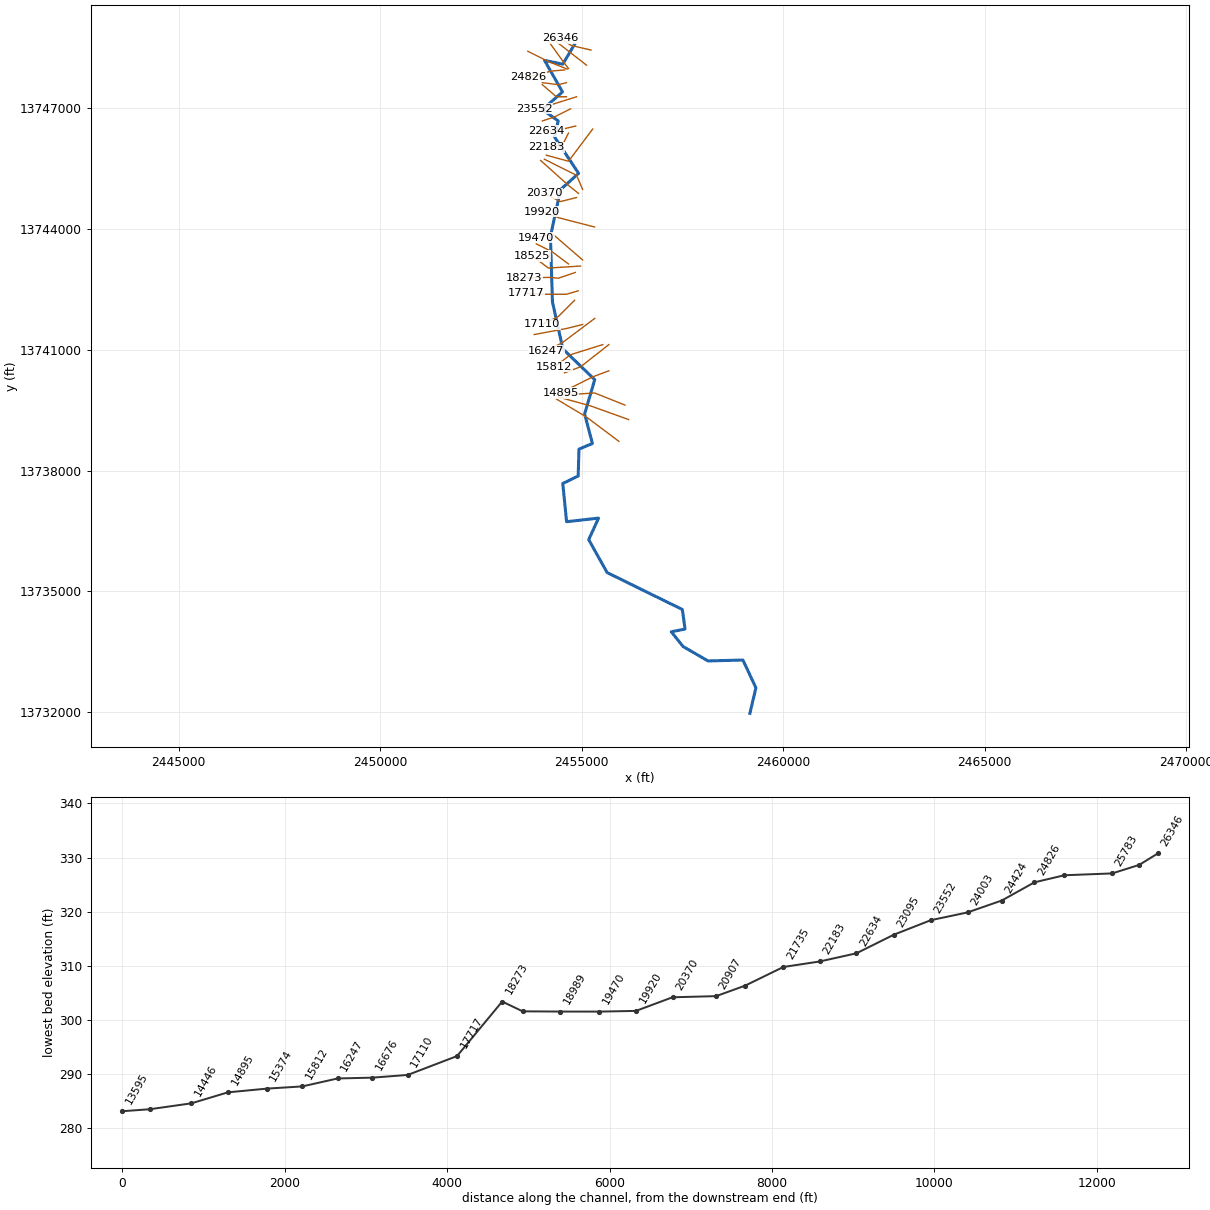
--- UNNAMED SLOUGH 1.prj (project) ---

Proj Title=UNNAMED SLOUGH 1 Base Level Engineering
Current Plan=p01
Default Exp/Contr=0.3,0.1
English Units
Geom File=g01
Flow File=f01
Plan File=p01
BEGIN DESCRIPTION:
UNNAMED SLOUGH 1
END DESCRIPTION:

--- UNNAMED SLOUGH 1.p01 (plan) ---

Plan Title=Multiple Run
Short Identifier=Multiple
Geom File=g01
Flow File=f01
Subcritical Flow
K Sum by GR= 0
Std Step Tol= 0.01
Critical Tol= 0.01
Num of Std Step Trials= 20
Max Error Tol= 0.3
Flow Tol Ratio= 0.001
Split Flow NTrial= 30
Split Flow Tol= 0.02
Split Flow Ratio= 0.02
Log Output Level= 0
Friction Slope Method= 1
Unsteady Friction Slope Method= 2
Unsteady Bridges Friction Slope Method= 1
Parabolic Critical Depth
Global Vel Dist=  1 , 1 , 1
Global Log Level= 0
CheckData=True
Encroach Param= -1, 0, 0, 0
BEGIN DESCRIPTION:
Multiple Run
END DESCRIPTION:

--- UNNAMED SLOUGH 1.f01 (steady flow) ---

Flow Title=Multiple
Number of Profiles=7
Profile Names=10-year,25-year,50-year,1pct_min,100-year,1pct_plu,500-year
River Rch & RM= UNNAMED SLOUGH 1,Reach-1,26346
     643    1021    1358     873    1743    3477    2843
River Rch & RM= UNNAMED SLOUGH 1,Reach-1,21264
     941    1529    2064    1346    2686    5359    4508
River Rch & RM= UNNAMED SLOUGH 1,Reach-1,20370
    1278    2112    2881    1899    3788    7558    6488
River Rch & RM= UNNAMED SLOUGH 1,Reach-1,13933
    1458    2418    3309    2184    4358    8695    7494
River Rch & RM= UNNAMED SLOUGH 1,Reach-1,7497
    1664    2772    3801    2514    5017   10010    8661
Boundary for River Rch & Prof#=UNNAMED SLOUGH 1,Reach-1,1
Up Type=0
Dn Type=3
Dn Slope=0.005
Boundary for River Rch & Prof#=UNNAMED SLOUGH 1,Reach-1,2
Up Type=0
Dn Type=3
Dn Slope=0.005
Boundary for River Rch & Prof#=UNNAMED SLOUGH 1,Reach-1,3
Up Type=0
Dn Type=3
Dn Slope=0.005
Boundary for River Rch & Prof#=UNNAMED SLOUGH 1,Reach-1,4
Up Type=0
Dn Type=3
Dn Slope=0.005
Boundary for River Rch & Prof#=UNNAMED SLOUGH 1,Reach-1,5
Up Type=0
Dn Type=3
Dn Slope=0.005
Boundary for River Rch & Prof#=UNNAMED SLOUGH 1,Reach-1,6
Up Type=0
Dn Type=3
Dn Slope=0.005
Boundary for River Rch & Prof#=UNNAMED SLOUGH 1,Reach-1,7
Up Type=0
Dn Type=3
Dn Slope=0.005

--- UNNAMED SLOUGH 1.g01 (geometry) ---

Geom Title=Existing Conditions

River Reach=UNNAMED SLOUGH 1,Reach-1
Reach XY= 30
      2454825.00     13748575.00      2454531.67     13748083.96
      2454079.99     13748177.55      2454525.45     13747395.03
      2454024.53     13746954.53      2454419.20     13746677.30
      2454328.44     13746276.25      2454925.00     13745375.00
      2454478.53     13744973.54      2454226.21     13743814.49
      2454276.05     13742185.44      2454534.15     13741018.27
      2455325.09     13740255.13      2455074.68     13739404.84
      2455267.51     13738671.38      2454933.95     13738531.70
      2454914.49     13737865.19      2454532.48     13737678.62
      2454626.61     13736731.02      2455419.44     13736820.26
      2455175.68     13736285.75      2455632.80     13735468.79
      2457499.02     13734552.37      2457566.00     13734067.93
      2457224.41     13734000.00      2457515.00     13733635.61
      2458135.51     13733276.21      2459002.01     13733298.52
      2459324.63     13732609.73      2459175.00     13731975.00

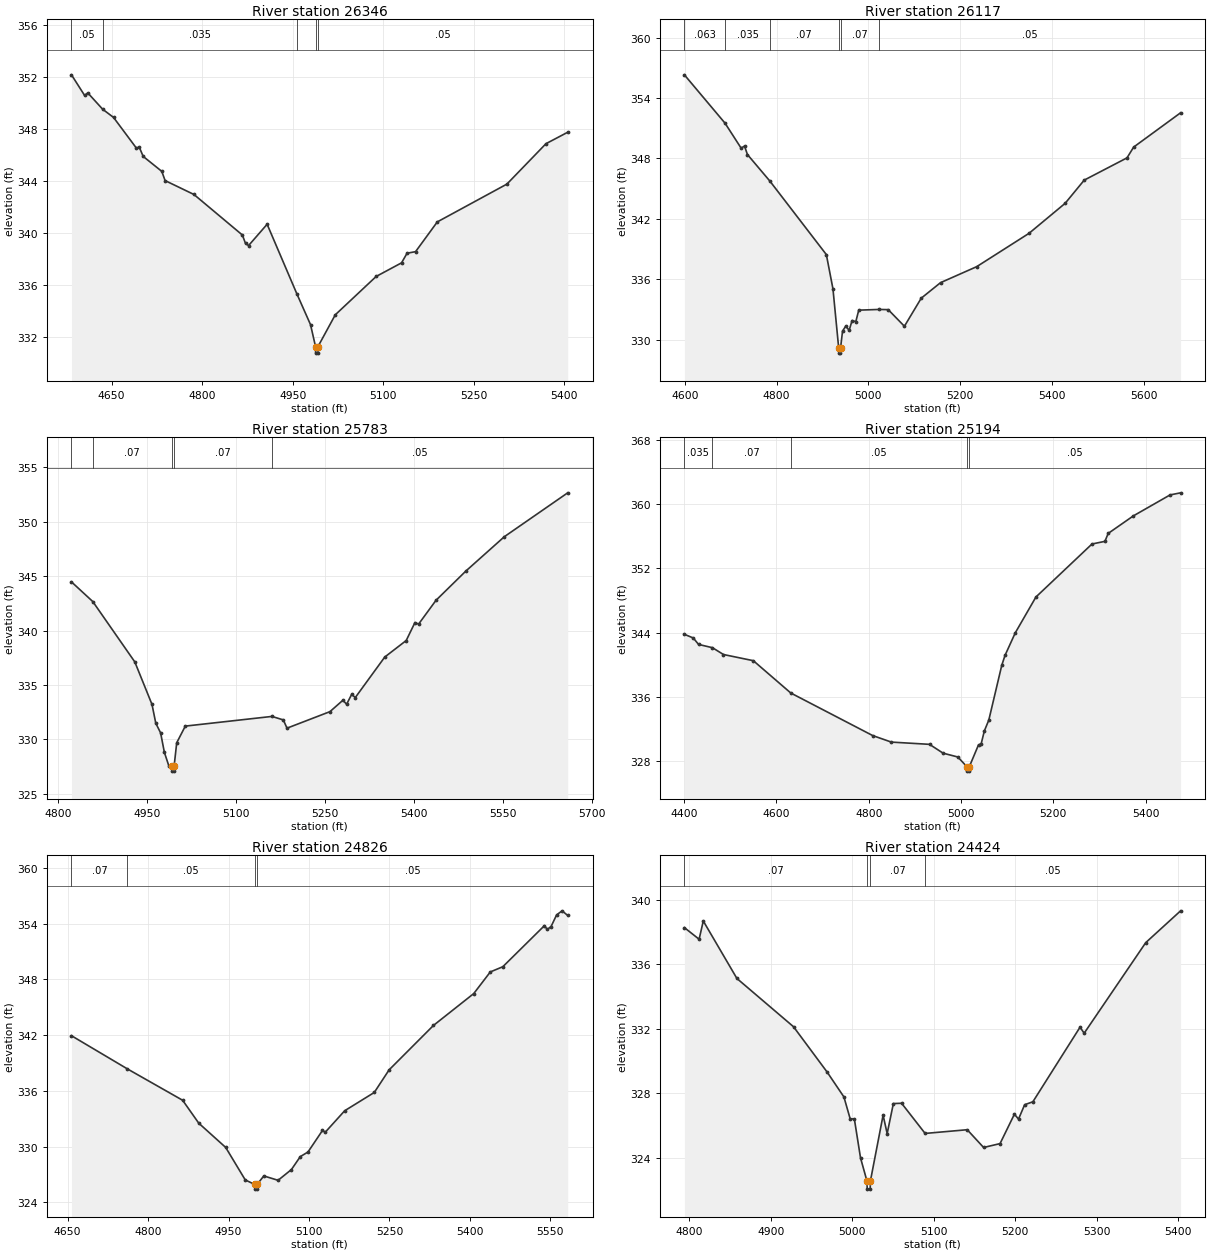
Type RM Length L Ch R = 1,26346,229,229,229
BEGIN DESCRIPTION:
UNNAMED SLOUGH #1 48.0
END DESCRIPTION:
XS GIS Cut Line= 3
      2455230.78     13748434.96      2454741.38     13748548.29
      2454475.01     13748724.99
#Sta/Elev= 30
  4583.5  352.19  4605.3  350.60  4610.5  350.80  4635.2  349.54  4653.2  348.91
  4690.7  346.57  4695.9  346.61  4702.3  345.91  4733.1  344.76  4738.6  344.05
  4786.4  342.98  4866.6  339.86  4871.8  339.21  4876.9  339.05  4907.6  340.69
  4956.7  335.35  4979.5  332.96  4987.8  331.27  4988.0  330.77  4991.5  330.77
  4991.8  331.27  5020.5  333.72  5088.2  336.67  5130.3  337.72  5139.4  338.46
  5153.5  338.58  5189.5  340.87  5304.8  343.78  5369.5  346.89  5405.5  347.77
#Mann=5,-1,0
  4583.5    0.05       0  4635.2   0.035       0  4956.7    0.05       0
  4987.8    0.05       0  4991.8    0.05       0
Bank Sta=4987.8,4991.8
Exp/Cntr=0.3,0.1

Type RM Length L Ch R = 1,26117,334,334,334
BEGIN DESCRIPTION:
XS7882
END DESCRIPTION:
XS GIS Cut Line= 2
      2455122.60     13748058.87      2454268.72     13748722.43
#Sta/Elev= 30
  4599.1  356.30  4687.8  351.49  4722.7  349.02  4730.2  349.22  4736.5  348.38
  4785.3  345.75  4908.5  338.44  4922.9  335.03  4935.4  329.15  4935.7  328.65
  4939.2  328.65  4939.4  329.15  4943.8  330.84  4950.7  331.33  4958.2  330.92
  4964.6  331.89  4972.7  331.78  4979.1  332.92  5023.3  332.99  5043.3  332.97
  5078.6  331.32  5115.3  334.11  5157.3  335.65  5236.1  337.24  5350.1  340.55
  5428.8  343.53  5470.5  345.84  5563.7  348.05  5578.2  349.12  5680.5  352.53
#Mann=6,-1,0
  4599.1   0.063       0  4687.8   0.035       0  4785.3    0.07       0
  4935.4    0.05       0  4939.4    0.07       0  5023.3    0.05       0
Bank Sta=4935.4,4939.4
Exp/Cntr=0.3,0.1

Type RM Length L Ch R = 1,25783,589,589,589
BEGIN DESCRIPTION:
UNNAMED SLOUGH #1 47.0
END DESCRIPTION:
XS GIS Cut Line= 3
      2454675.03     13747974.96      2454550.75     13748136.13
      2454180.37     13748650.55
#Sta/Elev= 30
  4822.2  344.47  4858.2  342.66  4929.1  337.11  4958.1  333.20  4964.5  331.47
  4972.6  330.59  4979.0  328.79  4986.4  327.57  4991.4  327.57  4991.7  327.07
  4995.2  327.07  4995.5  327.57  4999.8  329.68  5014.3  331.21  5160.5  332.10
  5179.7  331.78  5185.9  331.02  5258.4  332.54  5280.3  333.59  5286.5  333.22
  5295.0  334.12  5301.2  333.84  5350.9  337.56  5387.1  339.08  5401.8  340.73
  5408.0  340.59  5437.4  342.78  5487.8  345.47  5552.8  348.63  5659.6  352.66
#Mann=5,-1,0
  4822.2   0.035       0  4858.2    0.07       0  4991.4    0.05       0
  4995.5    0.07       0  5160.5    0.05       0
Bank Sta=4991.4,4995.5
Exp/Cntr=0.3,0.1

Type RM Length L Ch R = 1,25194,368,368,368
BEGIN DESCRIPTION:
XS7881
END DESCRIPTION:
XS GIS Cut Line= 3
      2454643.49     13747960.96      2454159.20     13748156.74
      2453664.64     13748404.02
#Sta/Elev= 30
  4400.6  343.79  4419.9  343.33  4431.3  342.53  4461.4  342.12  4485.3  341.27
  4550.0  340.50  4631.2  336.47  4808.8  331.16  4849.1  330.35  4931.8  330.07
  4961.2  328.97  4993.2  328.49  5013.6  327.23  5013.8  326.73  5017.4  326.73
  5017.7  327.23  5038.0  330.01  5043.6  330.10  5050.6  331.74  5060.3  333.10
  5088.3  339.91  5095.4  341.16  5117.7  343.98  5162.4  348.44  5283.9  355.05
  5311.9  355.38  5319.0  356.37  5373.4  358.55  5453.1  361.17  5475.9  361.43
#Mann=5,-1,0
  4400.6   0.035       0  4461.4    0.07       0  4631.2    0.05       0
  5013.6    0.05       0  5017.7    0.05       0
Bank Sta=5013.6,5017.7
Exp/Cntr=0.3,0.1

Type RM Length L Ch R = 1,24826,402,402,402
BEGIN DESCRIPTION:
UNNAMED SLOUGH #1 46.0
END DESCRIPTION:
XS GIS Cut Line= 3
      2454581.67     13747940.35      2454257.09     13747914.59
      2453674.90     13747770.33
#Sta/Elev= 30
  4657.1  341.94  4761.3  338.37  4864.4  334.99  4894.5  332.52  4944.7  329.91
  4981.2  326.41  4999.0  325.92  4999.3  325.42  5002.9  325.42  5003.2  325.92
  5015.8  326.84  5042.4  326.37  5067.3  327.53  5083.8  328.92  5098.2  329.42
  5125.2  331.74  5130.4  331.55  5166.6  333.86  5221.8  335.83  5249.4  338.26
  5332.2  343.05  5407.3  346.48  5438.2  348.81  5461.5  349.37  5539.2  353.80
  5544.3  353.38  5551.5  353.70  5561.8  354.95  5572.1  355.39  5582.5  354.89
#Mann=4,-1,0
  4657.1    0.07       0  4761.3    0.05       0  4999.0    0.05       0
  5003.2    0.05       0
Bank Sta=4999,5003.2
Exp/Cntr=0.3,0.1

Type RM Length L Ch R = 1,24424,421,421,421
BEGIN DESCRIPTION:
UNNAMED SLOUGH #1 45.0
END DESCRIPTION:
XS GIS Cut Line= 3
      2454625.03     13747625.01      2454425.00     13747575.00
      2454025.00     13747625.00
#Sta/Elev= 30
  4793.8  338.26  4811.9  337.54  4817.0  338.67  4858.3  335.11  4927.8  332.12
  4969.1  329.31  4989.7  327.77  4997.4  326.41  5002.5  326.41  5010.1  323.99
  5018.0  322.56  5018.3  322.06  5021.9  322.06  5022.2  322.56  5037.8  326.64
  5042.8  325.50  5050.4  327.36  5060.5  327.38  5089.4  325.51  5141.1  325.74
  5161.2  324.64  5181.4  324.88  5199.0  326.70  5204.1  326.40  5211.6  327.29
  5221.7  327.47  5279.6  332.09  5284.7  331.72  5360.3  337.33  5403.1  339.30
#Mann=4,-1,0
  4793.8    0.07       0  5018.0    0.05       0  5022.2    0.07       0
  5089.4    0.05       0
Bank Sta=5018,5022.2
Exp/Cntr=0.3,0.1

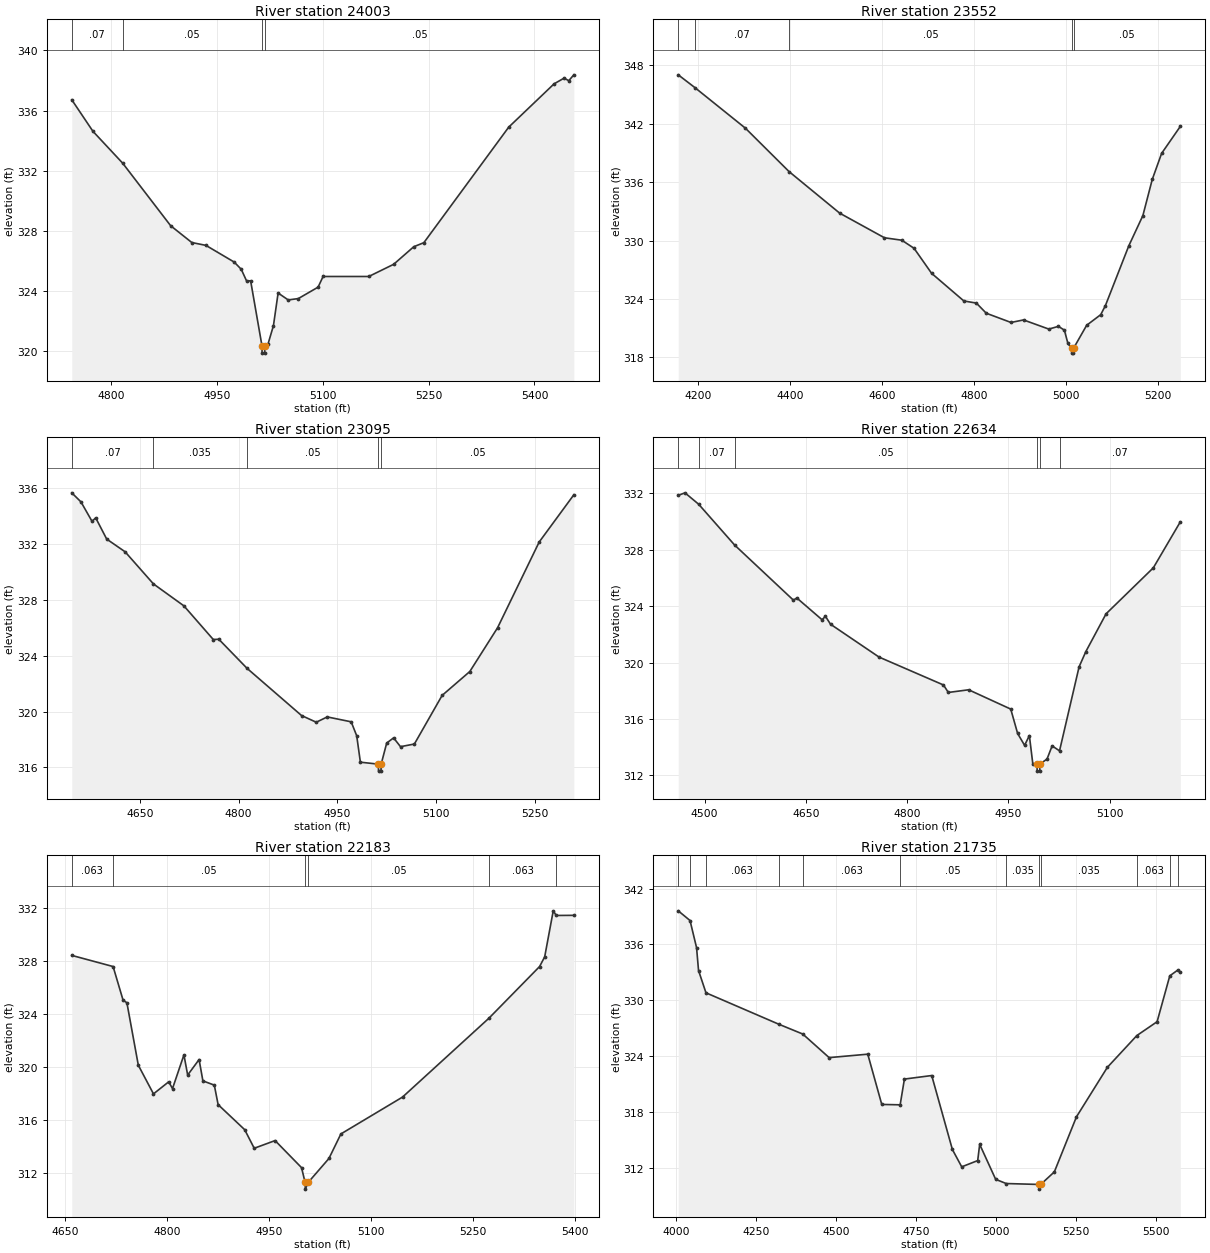
Type RM Length L Ch R = 1,24003,451,451,451
BEGIN DESCRIPTION:
UNNAMED SLOUGH #1 44.0
END DESCRIPTION:
XS GIS Cut Line= 3
      2454624.98     13747275.00      2454375.00     13747275.00
      2454024.97     13747575.03
#Sta/Elev= 30
  4744.8  336.72  4774.8  334.62  4816.9  332.50  4884.8  328.34  4914.8  327.22
  4934.8  327.03  4974.8  325.92  4984.8  325.44  4992.3  324.67  4998.1  324.67
  5014.1  320.36  5014.3  319.86  5018.0  319.86  5018.3  320.36  5022.8  320.48
  5030.4  321.69  5037.0  323.86  5051.3  323.40  5065.6  323.49  5093.6  324.25
  5100.7  324.96  5165.4  324.96  5200.6  325.77  5229.1  326.94  5243.4  327.21
  5363.6  334.90  5427.8  337.78  5442.0  338.16  5448.6  337.99  5455.8  338.38
#Mann=4,-1,0
  4744.8    0.07       0  4816.9    0.05       0  5014.1    0.05       0
  5018.3    0.05       0
Bank Sta=5014.1,5018.3
Exp/Cntr=0.3,0.1

Type RM Length L Ch R = 1,23552,457,457,457
BEGIN DESCRIPTION:
UNNAMED SLOUGH #1 43.0
END DESCRIPTION:
XS GIS Cut Line= 3
      2454875.04     13747275.01      2454075.00     13747025.00
      2453825.04     13746975.01
#Sta/Elev= 30
  4156.5  347.02  4192.7  345.71  4302.7  341.54  4397.8  337.08  4508.0  332.81
  4605.5  330.28  4643.2  330.03  4669.9  329.20  4708.1  326.63  4778.3  323.79
  4805.6  323.57  4827.1  322.53  4881.0  321.58  4908.3  321.84  4963.3  320.90
  4984.2  321.18  4997.2  320.79  5004.9  319.42  5012.9  318.93  5013.2  318.43
  5016.9  318.43  5017.2  318.93  5045.7  321.29  5076.3  322.38  5086.5  323.31
  5137.5  329.46  5168.1  332.56  5188.5  336.27  5208.9  338.95  5249.6  341.72
#Mann=5,-1,0
  4156.5    0.05       0  4192.7    0.07       0  4397.8    0.05       0
  5012.9    0.05       0  5017.2    0.05       0
Bank Sta=5012.9,5017.2
Exp/Cntr=0.3,0.1

Type RM Length L Ch R = 1,23095,461,461,461
BEGIN DESCRIPTION:
UNNAMED SLOUGH #1 42.0
END DESCRIPTION:
XS GIS Cut Line= 3
      2454725.02     13746975.01      2454325.00     13746775.00
      2454024.97     13746674.99
#Sta/Elev= 30
  4546.2  335.66  4560.2  335.01  4577.0  333.62  4582.6  333.87  4599.3  332.35
  4627.3  331.44  4670.4  329.14  4716.7  327.57  4761.4  325.16  4769.8  325.18
  4812.7  323.10  4895.6  319.72  4918.0  319.24  4934.7  319.62  4971.1  319.27
  4979.5  318.27  4985.1  316.38  5012.4  316.24  5012.7  315.74  5016.4  315.74
  5016.7  316.24  5025.1  317.75  5035.6  318.12  5046.1  317.49  5067.2  317.68
  5109.4  321.16  5151.5  322.87  5193.7  326.00  5257.0  332.14  5309.7  335.52
#Mann=5,-1,0
  4546.2    0.07       0  4670.4   0.035       0  4812.7    0.05       0
  5012.4    0.05       0  5016.7    0.05       0
Bank Sta=5012.4,5016.7
Exp/Cntr=0.3,0.1

Type RM Length L Ch R = 1,22634,451,451,451
BEGIN DESCRIPTION:
UNNAMED SLOUGH #1 41.0
END DESCRIPTION:
XS GIS Cut Line= 3
      2454854.75     13746549.30      2454325.00     13746425.00
      2454125.03     13746425.00
#Sta/Elev= 30
  4460.8  331.86  4470.8  332.04  4491.1  331.23  4544.3  328.34  4631.4  324.43
  4636.6  324.58  4673.9  323.04  4679.0  323.28  4686.5  322.72  4758.4  320.39
  4853.9  318.41  4861.1  317.88  4891.2  318.07  4953.6  316.70  4963.8  314.97
  4974.1  314.13  4981.2  314.82  4986.3  312.82  4992.5  312.80  4992.8  312.30
  4996.6  312.30  4996.9  312.80  5007.4  313.16  5014.9  314.09  5025.9  313.74
  5054.9  319.70  5064.9  320.78  5094.9  323.46  5164.9  326.72  5204.9  329.98
#Mann=6,-1,0
  4460.8   0.035       0  4491.1    0.07       0  4544.3    0.05       0
  4992.5    0.05       0  4996.9    0.05       0  5025.9    0.07       0
Bank Sta=4992.5,4996.9
Exp/Cntr=0.3,0.1

Type RM Length L Ch R = 1,22183,448,448,448
BEGIN DESCRIPTION:
UNNAMED SLOUGH #1 40.0
END DESCRIPTION:
XS GIS Cut Line= 3
      2454675.02     13746375.04      2454525.00     13746075.00
      2454124.96     13746025.00
#Sta/Elev= 30
  4659.8  328.41  4720.6  327.57  4735.3  325.03  4740.9  324.84  4757.7  320.13
  4780.0  317.97  4802.4  318.88  4808.0  318.37  4824.8  320.91  4830.3  319.39
  4847.1  320.56  4852.7  318.95  4869.5  318.63  4875.1  317.16  4914.2  315.27
  4928.2  313.87  4958.9  314.45  4997.8  312.41  5003.1  311.29  5003.4  310.79
  5007.5  311.29  5038.1  313.10  5055.7  314.95  5146.4  317.73  5273.6  323.68
  5348.0  327.57  5355.5  328.30  5368.1  331.77  5372.5  331.42  5398.4  331.43
#Mann=6,-1,0
  4659.8   0.063       0  4720.6    0.05       0  5003.1    0.05       0
  5007.5    0.05       0  5273.6   0.063       0  5372.5   0.094       0
Bank Sta=5003.1,5007.5
Exp/Cntr=0.3,0.1

Type RM Length L Ch R = 1,21735,471,471,471
BEGIN DESCRIPTION:
UNNAMED SLOUGH #1 39.0
END DESCRIPTION:
XS GIS Cut Line= 3
      2455275.00     13746474.99      2454675.00     13745675.00
      2454124.98     13745825.01
#Sta/Elev= 30
  4005.5  339.61  4042.4  338.57  4062.8  335.66  4069.0  333.21  4092.2  330.82
  4319.4  327.46  4394.9  326.40  4477.4  323.87  4598.2  324.24  4642.0  318.85
  4699.5  318.81  4712.8  321.57  4798.2  321.95  4862.8  314.02  4892.0  312.16
  4942.0  312.83  4948.2  314.57  4998.2  310.82  5031.1  310.37  5134.5  310.27
  5134.8  309.77  5139.0  310.27  5181.7  311.62  5250.8  317.52  5347.5  322.83
  5439.8  326.24  5503.0  327.72  5542.7  332.64  5567.4  333.25  5575.6  333.00
#Mann=12,-1,0
  4005.5    0.05       0  4042.4   0.035       0  4092.2   0.063       0
  4319.4   0.094       0  4394.9   0.063       0  4699.5    0.05       0
  5031.1   0.035       0  5134.5    0.05       0  5139.0   0.035       0
  5439.8   0.063       0  5542.7   0.035       0  5567.4   0.094       0
Bank Sta=5134.5,5139
Exp/Cntr=0.3,0.1

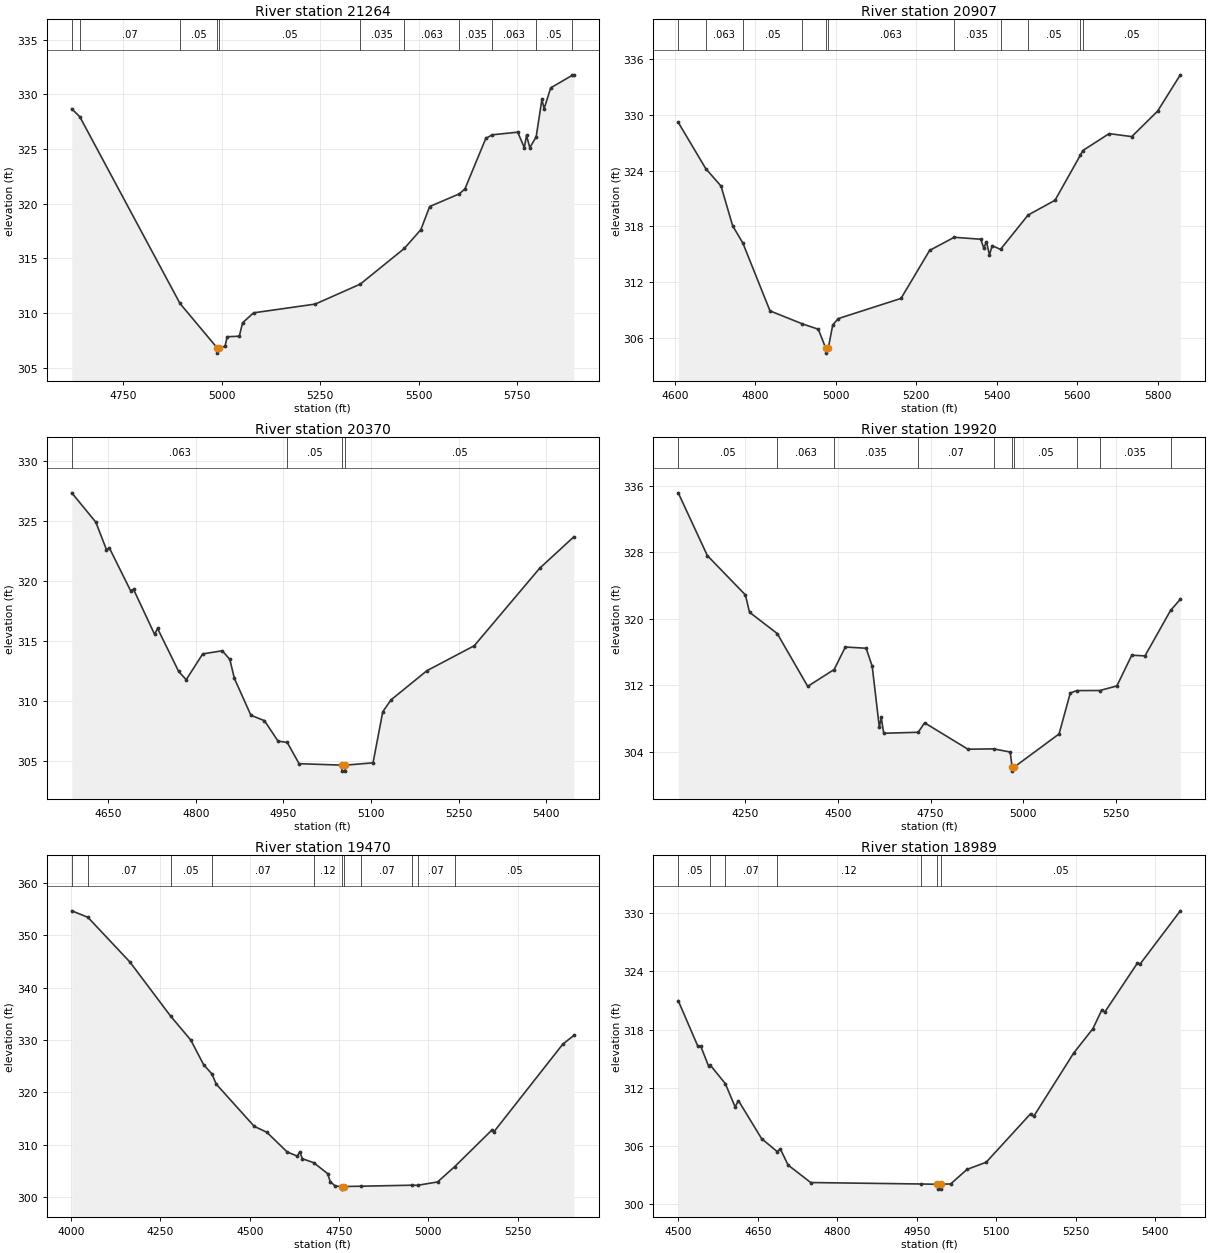
Type RM Length L Ch R = 1,21264,357,357,357
BEGIN DESCRIPTION:
UNNAMED SLOUGH #1 38.0
END DESCRIPTION:
XS GIS Cut Line= 3
      2455024.99     13744975.01      2454875.00     13745325.00
      2454075.00     13745725.00
#Sta/Elev= 30
  4618.9  328.69  4639.3  327.96  4893.7  310.87  4987.7  306.82  4988.2  306.32
  4993.6  306.82  5008.1  306.94  5013.6  307.82  5044.4  307.87  5052.8  309.10
  5080.7  310.01  5237.3  310.81  5351.7  312.64  5463.4  315.90  5505.6  317.63
  5527.9  319.74  5603.0  320.90  5617.4  321.35  5670.5  325.98  5686.8  326.31
  5751.6  326.55  5768.3  325.13  5773.9  326.25  5782.3  325.13  5798.4  326.12
  5813.0  329.55  5818.6  328.70  5835.4  330.61  5889.3  331.74  5894.1  331.80
#Mann=11,-1,0
  4618.9    0.05       0  4639.3    0.07       0  4893.7    0.05       0
  4987.7    0.05       0  4993.6    0.05       0  5351.7   0.035       0
  5463.4   0.063       0  5603.0   0.035       0  5686.8   0.063       0
  5798.4    0.05       0  5889.3   0.035       0
Bank Sta=4987.7,4993.6
Exp/Cntr=0.3,0.1

Type RM Length L Ch R = 1,20907,537,537,537
BEGIN DESCRIPTION:
UNNAMED SLOUGH #1 37.0
END DESCRIPTION:
XS GIS Cut Line= 3
      2454925.00     13744875.00      2454674.40     13745075.81
      2453984.01     13745694.08
#Sta/Elev= 30
  4608.8  329.18  4677.2  324.21  4715.2  322.33  4744.0  318.07  4769.5  316.20
  4836.9  308.92  4917.6  307.52  4956.9  306.95  4975.7  304.88  4976.1  304.38
  4981.6  304.88  4992.9  307.43  5007.1  308.10  5162.5  310.26  5233.6  315.42
  5294.7  316.83  5360.7  316.62  5368.2  315.67  5374.9  316.35  5382.4  314.93
  5389.1  315.93  5409.8  315.53  5478.3  319.22  5545.3  320.81  5608.5  325.67
  5613.9  326.14  5679.9  327.97  5736.0  327.65  5800.3  330.39  5856.7  334.29
#Mann=11,-1,0
  4608.8    0.05       0  4677.2   0.063       0  4769.5    0.05       0
  4917.6   0.063       0  4975.7    0.05       0  4981.6   0.063       0
  5294.7   0.035       0  5409.8   0.063       0  5478.3    0.05       0
  5608.5   0.035       0  5613.9    0.05       0
Bank Sta=4975.7,4981.6
Exp/Cntr=0.3,0.1

Type RM Length L Ch R = 1,20370,450,450,450
BEGIN DESCRIPTION:
UNNAMED SLOUGH #1 36.0
END DESCRIPTION:
XS GIS Cut Line= 3
      2454875.05     13744775.01      2454475.00     13744675.00
      2454074.98     13744875.01
#Sta/Elev= 30
  4587.8  327.34  4629.1  324.89  4647.1  322.62  4652.3  322.74  4688.4  319.20
  4693.5  319.31  4729.6  315.56  4734.7  316.05  4770.8  312.47  4783.7  311.78
  4812.0  313.93  4845.5  314.19  4858.4  313.47  4866.2  311.89  4894.5  308.82
  4917.7  308.37  4940.9  306.67  4956.7  306.56  4977.0  304.79  5050.2  304.67
  5050.7  304.17  5055.8  304.17  5056.3  304.67  5103.6  304.86  5120.3  309.12
  5134.3  310.10  5195.8  312.53  5276.9  314.61  5388.7  321.05  5447.4  323.68
#Mann=4,-1,0
  4587.8   0.063       0  4956.7    0.05       0  5050.2    0.05       0
  5056.3    0.05       0
Bank Sta=5050.2,5056.3
Exp/Cntr=0.3,0.1

Type RM Length L Ch R = 1,19920,450,450,450
BEGIN DESCRIPTION:
UNNAMED SLOUGH #1 35.0
END DESCRIPTION:
XS GIS Cut Line= 3
      2455320.88     13744043.59      2454425.00     13744275.00
      2454024.99     13744425.00
#Sta/Elev= 30
  4070.2  335.17  4148.6  327.61  4251.2  322.87  4262.2  320.79  4336.9  318.22
  4419.0  311.86  4490.2  313.89  4520.4  316.60  4576.4  316.45  4592.7  314.28
  4611.9  306.94  4617.1  308.11  4623.7  306.21  4716.6  306.33  4733.9  307.47
  4850.6  304.29  4919.8  304.33  4964.5  303.95  4969.5  302.15  4970.0  301.65
  4975.6  302.15  5096.1  306.13  5126.3  311.06  5143.8  311.35  5205.9  311.36
  5251.8  311.91  5291.9  315.61  5327.5  315.53  5396.5  321.01  5422.7  322.35
#Mann=10,-1,0
  4070.2    0.05       0  4336.9   0.063       0  4490.2   0.035       0
  4716.6    0.07       0  4919.8    0.05       0  4969.5    0.05       0
  4975.6    0.05       0  5143.8    0.07       0  5205.9   0.035       0
  5396.5    0.05       0
Bank Sta=4969.5,4975.6
Exp/Cntr=0.3,0.1

Type RM Length L Ch R = 1,19470,481,481,481
BEGIN DESCRIPTION:
UNNAMED SLOUGH #1 34.0
END DESCRIPTION:
XS GIS Cut Line= 3
      2455025.02     13743224.98      2454275.00     13743875.00
      2453875.01     13743775.00
#Sta/Elev= 30
  4002.1  354.71  4047.1  353.48  4165.0  344.91  4278.6  334.59  4335.0  330.02
  4371.1  325.30  4394.4  323.52  4406.2  321.60  4512.6  313.52  4547.7  312.40
  4604.7  308.63  4633.2  307.83  4639.9  308.65  4647.5  307.32  4679.0  306.58
  4717.7  304.50  4725.4  302.94  4739.6  302.10  4756.9  302.02  4757.4  301.52
  4764.1  302.02  4812.6  302.08  4953.5  302.27  4969.5  302.25  5025.5  302.89
  5073.8  305.84  5177.6  312.81  5182.7  312.43  5376.0  329.23  5406.9  330.90
#Mann=11,-1,0
  4002.1   0.035       0  4047.1    0.07       0  4278.6    0.05       0
  4394.4    0.07       0  4679.0    0.12       0  4756.9    0.05       0
  4764.1    0.12       0  4812.6    0.07       0  4953.5    0.05       0
  4969.5    0.07       0  5073.8    0.05       0
Bank Sta=4756.9,4764.1
Exp/Cntr=0.3,0.1

Type RM Length L Ch R = 1,18989,464,464,464
BEGIN DESCRIPTION:
UNNAMED SLOUGH #1 33.0
END DESCRIPTION:
XS GIS Cut Line= 3
      2454675.01     13743124.99      2454275.00     13743425.00
      2453875.02     13743624.99
#Sta/Elev= 30
  4500.1  320.98  4536.6  316.34  4542.8  316.25  4557.4  314.22  4560.8  314.31
  4588.9  312.42  4607.4  310.02  4613.7  310.66  4657.4  306.74  4686.6  305.41
  4692.8  305.67  4707.4  304.01  4750.1  302.21  4958.3  302.06  4989.2  302.03
  4989.7  301.53  4995.9  301.53  4996.4  302.03  5014.1  302.07  5044.8  303.56
  5081.2  304.31  5165.0  309.32  5170.6  309.03  5246.1  315.57  5282.4  318.09
  5299.2  320.02  5304.8  319.80  5366.3  324.85  5371.9  324.79  5447.3  330.25
#Mann=7,-1,0
  4500.1    0.05       0  4560.8    0.12       0  4588.9    0.07       0
  4686.6    0.12       0  4958.3    0.05       0  4989.2    0.05       0
  4996.4    0.05       0
Bank Sta=4989.2,4996.4
Exp/Cntr=0.3,0.1

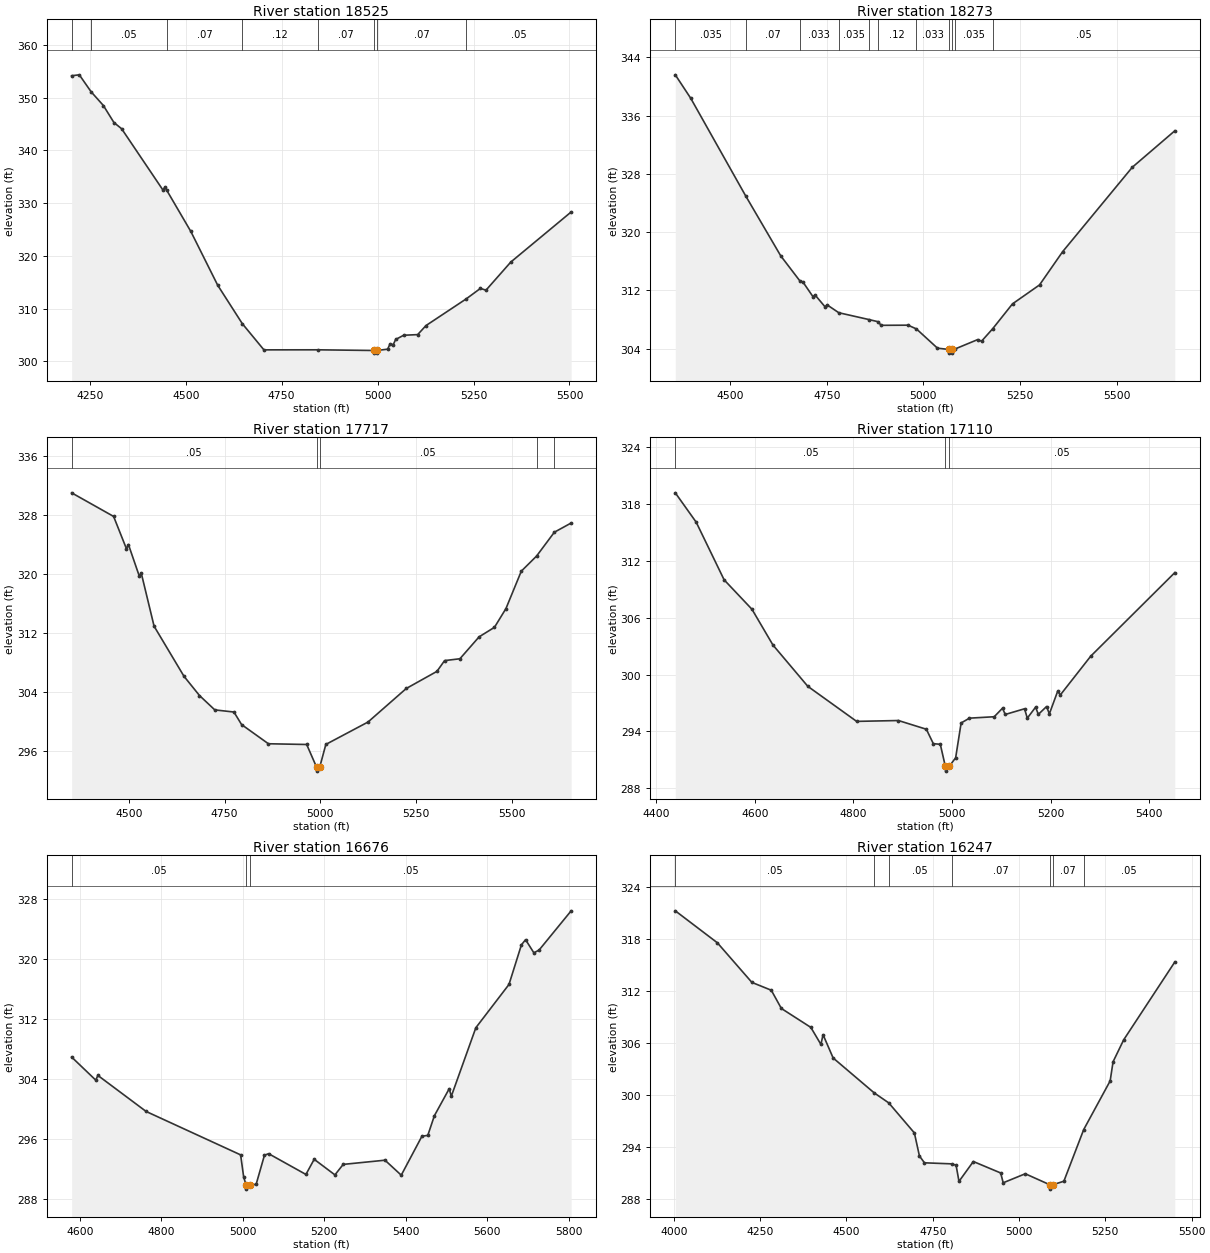
Type RM Length L Ch R = 1,18525,252,252,252
BEGIN DESCRIPTION:
UNNAMED SLOUGH #1 32.0
END DESCRIPTION:
XS GIS Cut Line= 3
      2454975.01     13743075.00      2454175.00     13743025.00
      2453774.97     13743325.02
#Sta/Elev= 30
  4202.8  354.18  4222.8  354.35  4253.6  351.13  4285.5  348.53  4313.0  345.30
  4333.1  344.12  4440.8  332.49  4445.8  333.06  4450.5  332.47  4513.4  324.64
  4583.5  314.43  4647.5  307.16  4703.8  302.19  4844.4  302.20  4990.5  302.07
  4991.0  301.57  4997.6  301.57  4998.1  302.07  5026.2  302.32  5032.5  303.32
  5040.8  303.18  5047.1  304.16  5067.9  304.96  5104.4  305.08  5126.2  306.80
  5230.8  311.85  5267.9  313.84  5282.5  313.51  5347.1  318.84  5504.4  328.34
#Mann=8,-1,0
  4202.8   0.035       0  4253.6    0.05       0  4450.5    0.07       0
  4647.5    0.12       0  4844.4    0.07       0  4990.5    0.05       0
  4998.1    0.07       0  5230.8    0.05       0
Bank Sta=4990.5,4998.1
Exp/Cntr=0.3,0.1

Type RM Length L Ch R = 1,18273,556,556,556
BEGIN DESCRIPTION:
UNNAMED SLOUGH #1 31.0
END DESCRIPTION:
XS GIS Cut Line= 4
      2454843.08     13742916.34      2454420.74     13742772.50
      2454188.13     13742793.93      2453574.98     13742775.00
#Sta/Elev= 30
  4357.7  341.61  4397.9  338.37  4539.8  324.99  4630.6  316.75  4680.1  313.31
  4688.0  313.16  4714.1  311.14  4719.4  311.38  4745.4  309.74  4750.7  310.01
  4781.0  308.93  4860.0  307.98  4883.0  307.69  4890.3  307.20  4960.3  307.22
  4982.1  306.70  5036.5  304.06  5066.8  303.88  5067.3  303.38  5073.9  303.38
  5074.4  303.88  5081.0  303.93  5140.6  305.24  5150.6  305.02  5179.4  306.73
  5230.7  310.15  5300.7  312.75  5360.7  317.33  5540.8  328.91  5650.9  333.92
#Mann=11,-1,0
  4357.7   0.035       0  4539.8    0.07       0  4680.1   0.033       0
  4781.0   0.035       0  4860.0   0.033       0  4883.0    0.12       0
  4982.1   0.033       0  5066.8   0.033       0  5074.4   0.033       0
  5081.0   0.035       0  5179.4    0.05       0
Bank Sta=5066.8,5074.4
Exp/Cntr=0.3,0.1

Type RM Length L Ch R = 1,17717,607,607,607
BEGIN DESCRIPTION:
UNNAMED SLOUGH #1 30.0
END DESCRIPTION:
XS GIS Cut Line= 4
      2454916.54     13742460.30      2454622.75     13742374.62
      2454028.98     13742374.62      2453624.94     13742396.04
#Sta/Elev= 30
  4350.6  331.02  4460.2  327.82  4493.7  323.44  4498.9  324.01  4527.2  319.74
  4532.4  320.14  4565.9  312.94  4643.9  306.16  4684.4  303.55  4724.4  301.60
  4774.4  301.31  4794.4  299.61  4864.4  297.01  4964.4  296.91  4990.5  293.80
  4991.0  293.30  4998.2  293.80  5014.4  296.92  5124.4  299.95  5224.4  304.50
  5304.5  306.82  5324.5  308.28  5364.5  308.53  5414.6  311.50  5454.7  312.79
  5484.7  315.33  5524.8  320.40  5564.7  322.45  5611.1  325.68  5655.0  326.93
#Mann=5,-1,0
  4350.6    0.05       0  4990.5    0.05       0  4998.2    0.05       0
  5564.7   0.035       0  5611.1    0.05       0
Bank Sta=4990.5,4998.2
Exp/Cntr=0.3,0.1

Type RM Length L Ch R = 1,17110,434,434,434
BEGIN DESCRIPTION:
UNNAMED SLOUGH #1 29.0
END DESCRIPTION:
XS GIS Cut Line= 3
      2454824.98     13742224.98      2454425.00     13741825.00
      2454024.97     13741624.99
#Sta/Elev= 30
  4439.0  319.18  4481.4  316.08  4538.0  310.00  4594.5  306.89  4637.0  303.12
  4707.7  298.76  4806.7  295.06  4891.5  295.15  4948.1  294.23  4962.2  292.71
  4976.4  292.64  4986.6  290.31  4987.1  289.81  4994.4  290.31  5007.5  291.22
  5018.6  294.89  5035.4  295.40  5085.7  295.55  5102.5  296.45  5108.1  295.79
  5147.2  296.39  5152.8  295.40  5169.6  296.56  5175.2  295.80  5191.9  296.63
  5197.5  295.85  5214.3  298.23  5219.9  297.86  5281.4  301.94  5451.9  310.76
#Mann=3,-1,0
  4439.0    0.05       0  4986.6    0.05       0  4994.4    0.05       0
Bank Sta=4986.6,4994.4
Exp/Cntr=0.3,0.1

Type RM Length L Ch R = 1,16676,429,429,429
BEGIN DESCRIPTION:
UNNAMED SLOUGH #1 28.0
END DESCRIPTION:
XS GIS Cut Line= 3
      2455024.96     13741624.99      2454625.00     13741525.00
      2453825.01     13741375.00
#Sta/Elev= 30
  4579.8  306.93  4639.0  303.85  4644.2  304.48  4762.7  299.67  4994.6  293.88
  5002.2  290.89  5008.4  289.81  5008.9  289.31  5016.5  289.81  5032.8  289.97
  5053.1  293.83  5063.3  294.04  5154.9  291.27  5175.2  293.29  5226.1  291.21
  5246.4  292.61  5349.0  293.17  5388.9  291.17  5439.7  296.37  5454.1  296.48
  5470.3  299.11  5506.7  302.71  5511.8  301.70  5572.0  310.84  5653.4  316.62
  5683.9  321.90  5694.1  322.59  5714.4  320.84  5727.2  321.20  5806.0  326.44
#Mann=3,-1,0
  4579.8    0.05       0  5008.4    0.05       0  5016.5    0.05       0
Bank Sta=5008.4,5016.5
Exp/Cntr=0.3,0.1

Type RM Length L Ch R = 1,16247,435,435,435
BEGIN DESCRIPTION:
UNNAMED SLOUGH #1 27.0
END DESCRIPTION:
XS GIS Cut Line= 3
      2455325.00     13741775.00      2454525.00     13741175.00
      2454125.01     13740975.00
#Sta/Elev= 30
  4004.0  321.20  4125.9  317.52  4225.9  312.96  4282.1  312.06  4311.3  309.96
  4396.7  307.78  4425.9  305.82  4432.1  306.94  4461.3  304.26  4580.3  300.24
  4622.4  299.09  4696.7  295.63  4711.3  292.98  4725.9  292.19  4804.5  292.07
  4817.5  291.92  4825.9  290.05  4867.5  292.34  4946.7  291.02  4954.0  289.89
  5018.0  290.93  5089.3  289.66  5089.8  289.16  5097.5  289.66  5129.8  290.07
  5187.3  296.02  5263.9  301.62  5272.3  303.82  5303.1  306.35  5451.2  315.31
#Mann=7,-1,0
  4004.0    0.05       0  4580.3    0.07       0  4622.4    0.05       0
  4804.5    0.07       0  5089.3    0.05       0  5097.5    0.07       0
  5187.3    0.05       0
Bank Sta=5089.3,5097.5
Exp/Cntr=0.3,0.1

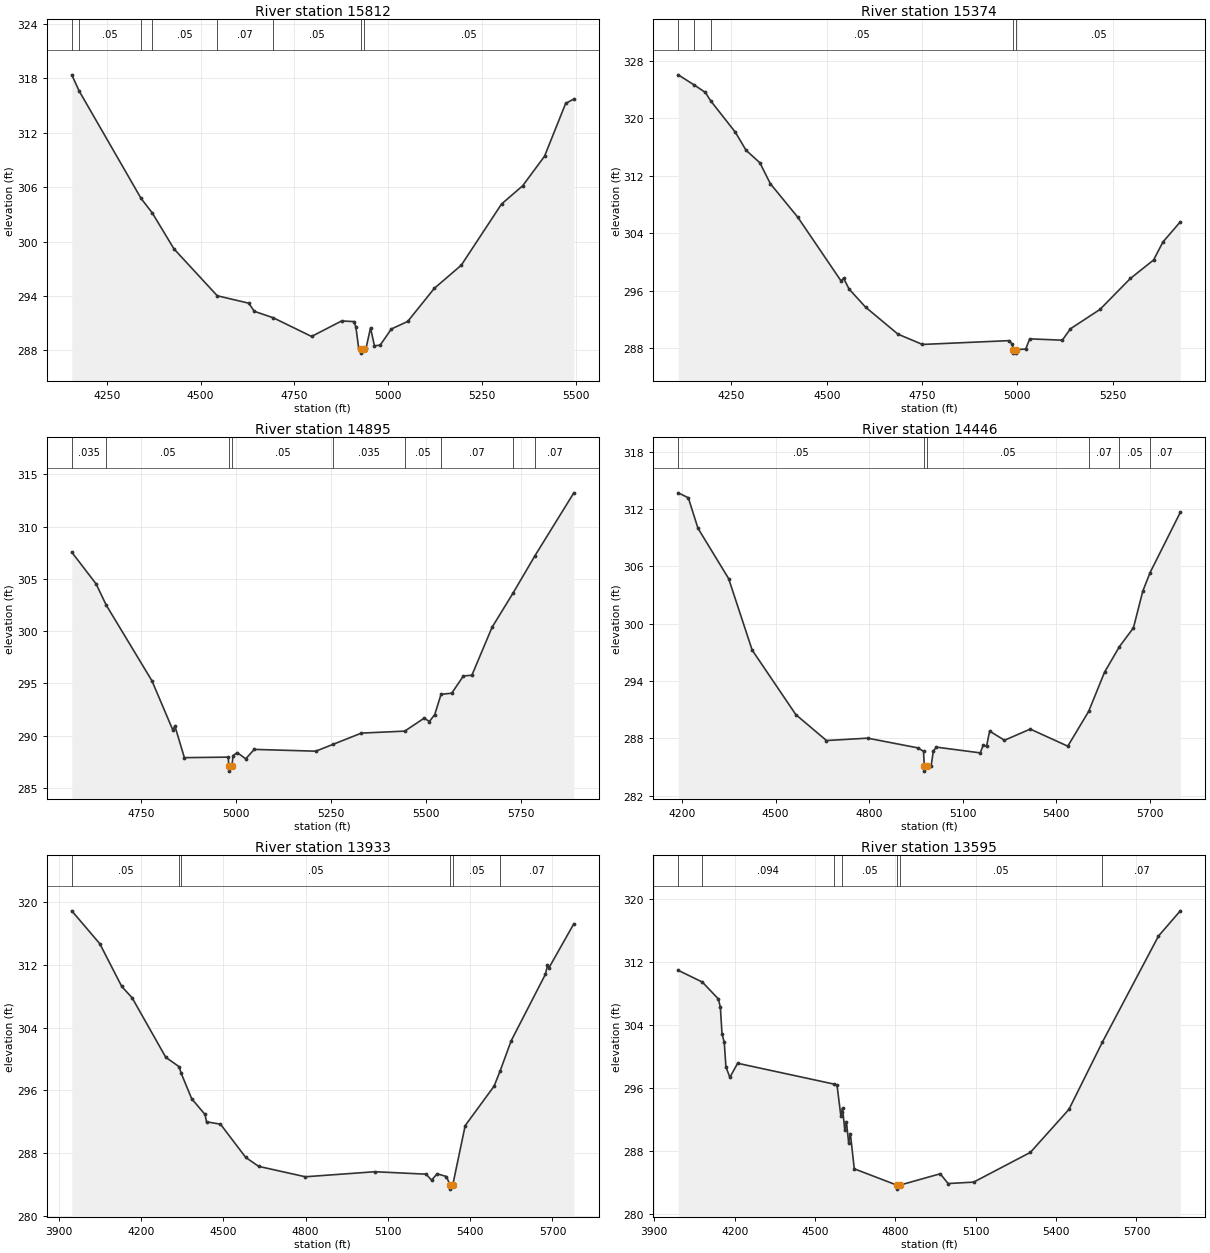
Type RM Length L Ch R = 1,15812,438,438,438
BEGIN DESCRIPTION:
UNNAMED SLOUGH #1 26.0
END DESCRIPTION:
XS GIS Cut Line= 3
      2455525.00     13741125.00      2454725.00     13740875.00
      2454325.04     13740575.03
#Sta/Elev= 30
  4156.6  318.39  4176.4  316.60  4341.4  304.75  4371.1  303.16  4429.0  299.19
  4544.3  294.02  4628.1  293.20  4643.2  292.30  4693.6  291.59  4795.7  289.53
  4875.8  291.24  4908.3  291.17  4913.6  290.62  4921.4  288.21  4927.8  288.19
  4928.3  287.69  4936.0  288.19  4940.8  288.22  4952.8  290.47  4963.3  288.50
  4978.5  288.57  5008.3  290.35  5052.0  291.19  5122.9  294.84  5194.7  297.39
  5302.0  304.14  5358.3  306.15  5416.6  309.41  5472.9  315.24  5494.7  315.72
#Mann=8,-1,0
  4156.6    0.07       0  4176.4    0.05       0  4341.4    0.07       0
  4371.1    0.05       0  4544.3    0.07       0  4693.6    0.05       0
  4927.8    0.05       0  4936.0    0.05       0
Bank Sta=4927.8,4936
Exp/Cntr=0.3,0.1

Type RM Length L Ch R = 1,15374,479,479,479
BEGIN DESCRIPTION:
UNNAMED SLOUGH #1 25.0
END DESCRIPTION:
XS GIS Cut Line= 3
      2455675.00     13741125.00      2454975.00     13740575.00
      2454575.02     13740425.01
#Sta/Elev= 30
  4110.3  326.03  4152.8  324.60  4181.7  323.57  4195.0  322.44  4260.3  318.03
  4288.3  315.52  4324.5  313.79  4351.9  310.88  4423.9  306.21  4537.8  297.31
  4544.1  297.72  4558.6  296.20  4601.9  293.68  4686.9  289.92  4751.1  288.49
  4978.8  289.02  4986.9  288.51  4989.1  287.78  4989.6  287.28  4996.9  287.28
  4997.4  287.78  5021.9  287.84  5032.6  289.27  5118.0  289.08  5139.4  290.67
  5216.8  293.36  5296.9  297.69  5357.4  300.24  5382.3  302.77  5427.7  305.56
#Mann=5,-1,0
  4110.3    0.05       0  4152.8    0.07       0  4195.0    0.05       0
  4989.1    0.05       0  4997.4    0.05       0
Bank Sta=4989.1,4997.4
Exp/Cntr=0.3,0.1

Type RM Length L Ch R = 1,14895,449,449,449
BEGIN DESCRIPTION:
UNNAMED SLOUGH #1 24.0
END DESCRIPTION:
XS GIS Cut Line= 3
      2455675.03     13740475.01      2455275.00     13740325.00
      2454474.96     13739924.98
#Sta/Elev= 30
  4567.6  307.55  4631.7  304.51  4658.2  302.49  4778.6  295.24  4833.7  290.52
  4839.1  290.91  4864.0  287.88  4979.7  287.93  4980.8  287.09  4981.3  286.59
  4989.2  287.09  4992.2  288.08  5003.2  288.36  5025.6  287.77  5047.9  288.67
  5210.1  288.50  5256.5  289.17  5330.2  290.23  5444.2  290.42  5495.2  291.66
  5509.1  291.34  5523.1  292.01  5539.7  293.94  5567.8  294.05  5598.6  295.70
  5620.9  295.77  5674.0  300.36  5729.0  303.62  5787.1  307.22  5889.3  313.23
#Mann=9,-1,0
  4567.6   0.035       0  4658.2    0.05       0  4980.8    0.05       0
  4989.2    0.05       0  5256.5   0.035       0  5444.2    0.05       0
  5539.7    0.07       0  5729.0    0.05       0  5787.1    0.07       0
Bank Sta=4980.8,4989.2
Exp/Cntr=0.3,0.1

Type RM Length L Ch R = 1,14446,513,513,513
BEGIN DESCRIPTION:
UNNAMED SLOUGH #1 23.0
END DESCRIPTION:
XS GIS Cut Line= 3
      2456075.00     13739625.00      2455325.00     13739925.00
      2454525.03     13739875.00
#Sta/Elev= 30
  4187.9  313.68  4220.2  313.16  4251.2  309.97  4349.5  304.70  4424.8  297.23
  4564.9  290.47  4663.1  287.76  4795.1  288.01  4956.6  286.99  4974.1  286.63
  4976.7  285.06  4977.2  284.56  4985.1  285.06  4998.2  285.07  5005.7  286.67
  5015.7  287.07  5156.0  286.47  5166.0  287.32  5176.0  287.14  5186.0  288.75
  5233.6  287.79  5316.3  288.96  5436.5  287.17  5503.4  290.81  5554.3  294.91
  5601.9  297.58  5646.9  299.55  5677.0  303.40  5700.4  305.34  5797.2  311.64
#Mann=6,-1,0
  4187.9    0.05       0  4976.7    0.05       0  4985.1    0.05       0
  5503.4    0.07       0  5601.9    0.05       0  5700.4    0.07       0
Bank Sta=4976.7,4985.1
Exp/Cntr=0.3,0.1

Type RM Length L Ch R = 1,13933,338,338,338
BEGIN DESCRIPTION:
UNNAMED SLOUGH #1 22.0
END DESCRIPTION:
XS GIS Cut Line= 3
      2456166.49     13739265.60      2455229.19     13739601.80
      2454424.97     13739825.01
#Sta/Elev= 30
  3947.6  318.82  4049.8  314.64  4129.8  309.21  4167.5  307.78  4290.4  300.21
  4338.3  299.04  4346.6  298.18  4384.8  294.95  4433.5  292.95  4438.9  292.02
  4489.7  291.72  4582.0  287.49  4629.1  286.36  4799.1  285.04  5052.8  285.68
  5239.6  285.37  5259.1  284.61  5279.8  285.42  5313.4  285.07  5327.1  283.97
  5327.6  283.47  5336.4  283.97  5381.9  291.54  5487.4  296.56  5509.3  298.49
  5549.6  302.32  5674.2  310.75  5681.9  311.88  5687.1  311.57  5778.0  317.18
#Mann=6,-1,0
  3947.6    0.05       0  4338.3   0.063       0  4346.6    0.05       0
  5327.1    0.05       0  5336.4    0.05       0  5509.3    0.07       0
Bank Sta=5327.1,5336.4
Exp/Cntr=0.3,0.1

Type RM Length L Ch R = 1,13595,482,482,482
BEGIN DESCRIPTION:
UNNAMED SLOUGH #1 21.0
END DESCRIPTION:
XS GIS Cut Line= 3
      2455924.98     13738725.02      2455125.00     13739325.00
      2454375.01     13739774.99
#Sta/Elev= 30
  3989.2  310.90  4079.2  309.41  4139.2  307.26  4146.5  306.19  4152.7  302.83
  4161.0  301.75  4167.3  298.64  4181.9  297.30  4211.0  299.09  4571.6  296.44
  4581.9  296.35  4596.5  292.37  4599.4  292.85  4602.7  293.40  4611.0  290.61
  4617.3  291.64  4625.6  288.93  4631.9  290.15  4646.5  285.68  4806.2  283.60
  4806.7  283.10  4815.8  283.60  4967.3  285.05  4996.9  283.81  5092.2  283.99
  5304.0  287.77  5447.9  293.23  5572.6  301.76  5782.2  315.25  5863.8  318.46
#Mann=7,-1,0
  3989.2   0.035       0  4079.2   0.094       0  4571.6   0.063       0
  4599.4    0.05       0  4806.2    0.05       0  4815.8    0.05       0
  5572.6    0.07       0
Bank Sta=4806.2,4815.8
Exp/Cntr=0.3,0.1