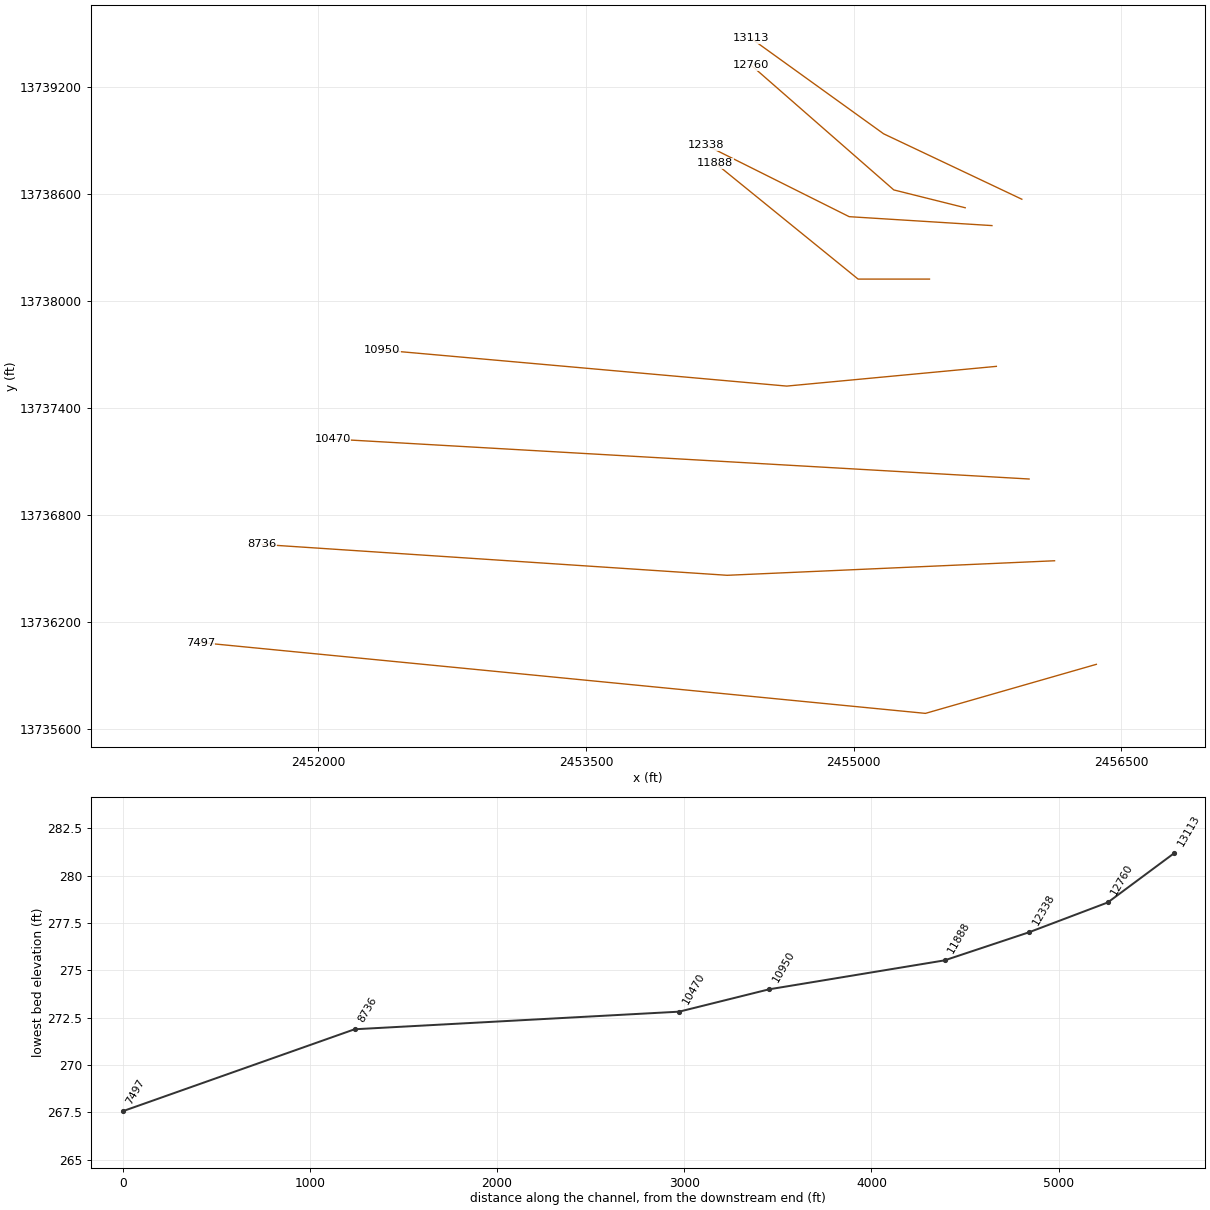
HEC-RAS study UNNAMED SLOUGH 1.prj: UNNAMED SLOUGH 1 Base Level Engineering

--- UNNAMED SLOUGH 1.g01 (geometry) --- (continued)

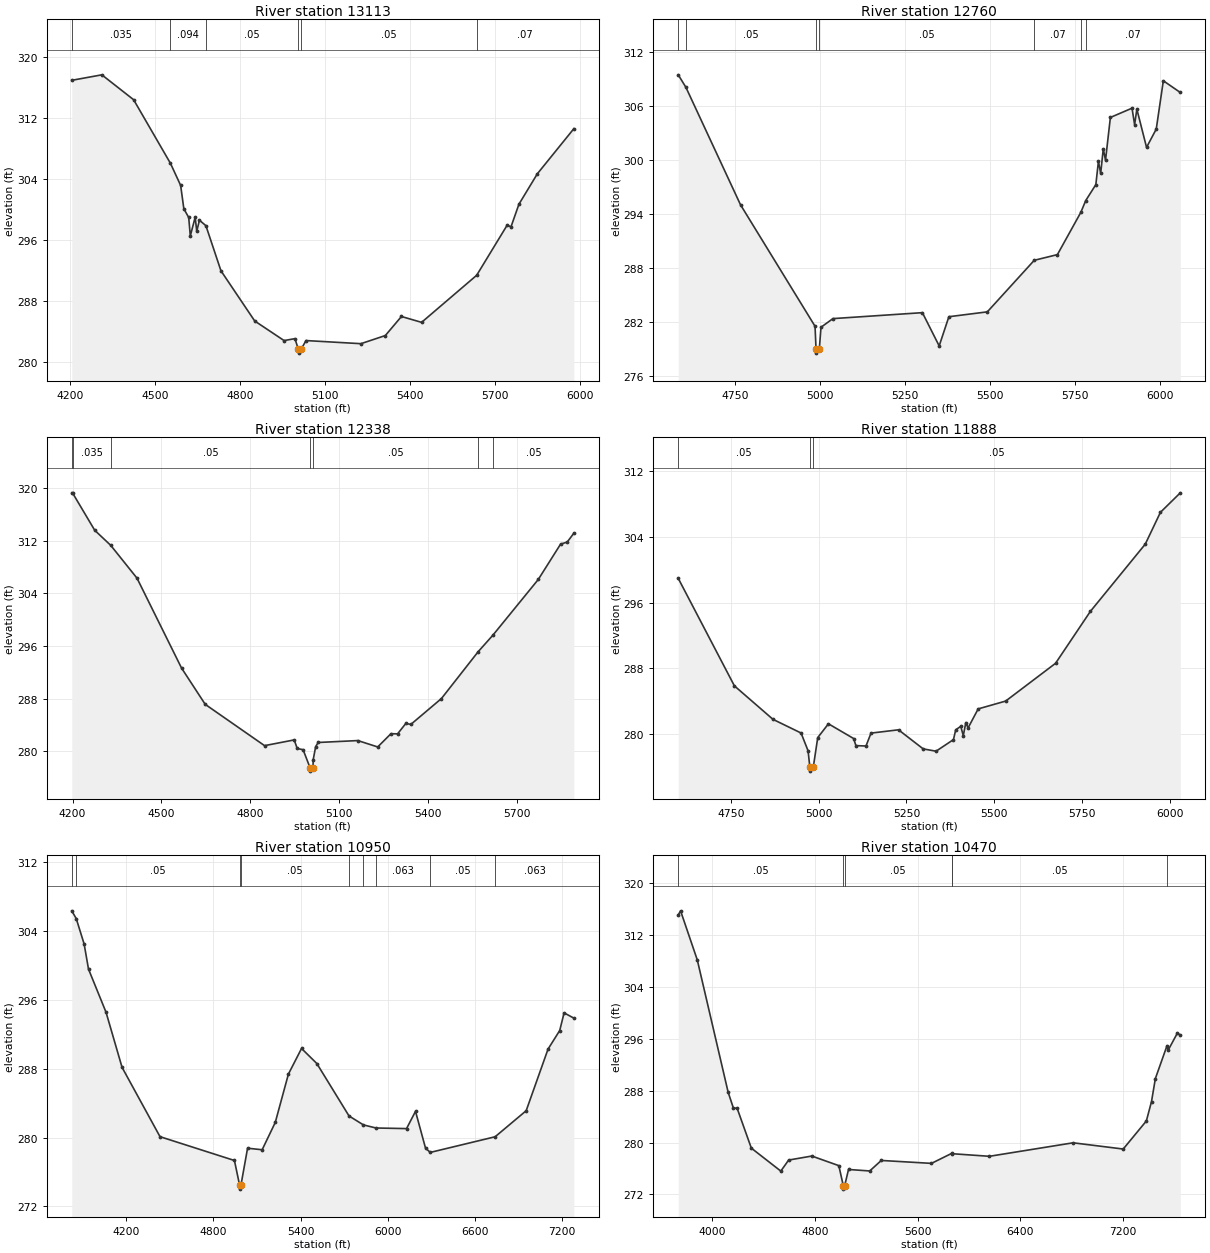
Type RM Length L Ch R = 1,13113,353,353,353
BEGIN DESCRIPTION:
UNNAMED SLOUGH #1 20.0
END DESCRIPTION:
XS GIS Cut Line= 3
      2455942.37     13738572.84      2455168.07     13738939.61
      2454425.02     13739474.98
#Sta/Elev= 30
  4206.7  317.00  4312.9  317.72  4425.1  314.45  4555.1  306.10  4591.1  303.20
  4602.4  300.13  4619.6  298.99  4625.2  296.57  4642.4  299.02  4647.9  297.19
  4657.5  298.63  4680.3  297.91  4733.4  291.99  4852.6  285.40  4956.2  282.83
  4994.6  283.08  5006.7  281.68  5007.2  281.18  5016.3  281.68  5033.7  282.83
  5227.5  282.42  5313.8  283.49  5370.6  285.99  5441.8  285.22  5636.2  291.40
  5743.7  297.97  5757.5  297.77  5785.4  300.73  5850.5  304.73  5979.3  310.65
#Mann=6,-1,0
  4206.7   0.035       0  4555.1   0.094       0  4680.3    0.05       0
  5006.7    0.05       0  5016.3    0.05       0  5636.2    0.07       0
Bank Sta=5006.7,5016.3
Exp/Cntr=0.3,0.1

Type RM Length L Ch R = 1,12760,422,422,422
BEGIN DESCRIPTION:
UNNAMED SLOUGH #1 19.0
END DESCRIPTION:
XS GIS Cut Line= 3
      2455625.03     13738524.99      2455225.00     13738625.00
      2454424.97     13739325.03
#Sta/Elev= 30
  4583.3  309.47  4605.9  308.08  4766.3  295.05  4985.3  281.57  4988.2  279.09
  4988.7  278.59  4998.0  279.09  5002.8  281.46  5037.9  282.42  5300.8  283.08
  5350.1  279.39  5378.6  282.63  5491.6  283.17  5629.5  288.89  5697.5  289.52
  5766.5  294.22  5780.8  295.52  5810.5  297.29  5818.1  299.88  5824.7  298.53
  5832.3  301.26  5838.9  300.00  5853.2  304.74  5916.8  305.77  5924.4  303.94
  5931.0  305.66  5959.5  301.42  5988.0  303.45  6008.8  308.81  6058.7  307.51
#Mann=7,-1,0
  4583.3   0.035       0  4605.9    0.05       0  4988.2    0.05       0
  4998.0    0.05       0  5629.5    0.07       0  5766.5    0.05       0
  5780.8    0.07       0
Bank Sta=4988.2,4998
Exp/Cntr=0.3,0.1

Type RM Length L Ch R = 1,12338,450,450,450
BEGIN DESCRIPTION:
UNNAMED SLOUGH #1 18.0
END DESCRIPTION:
XS GIS Cut Line= 3
      2455774.97     13738425.00      2454975.00     13738475.00
      2454174.96     13738875.02
#Sta/Elev= 30
  4197.2  319.27  4200.4  319.21  4274.8  313.58  4328.7  311.30  4417.6  306.31
  4567.9  292.67  4648.0  287.15  4848.4  280.88  4948.6  281.75  4958.7  280.45
  4978.7  280.26  5002.2  277.51  5002.7  277.01  5012.1  277.51  5012.7  278.74
  5021.1  280.73  5029.5  281.36  5163.6  281.65  5230.7  280.68  5275.4  282.69
  5297.8  282.67  5325.8  284.26  5342.5  284.10  5445.9  288.03  5570.1  295.15
  5619.5  297.64  5773.0  306.11  5848.4  311.48  5870.8  311.79  5893.2  313.14
#Mann=7,-1,0
  4197.2   0.094       0  4200.4   0.035       0  4328.7    0.05       0
  5002.2    0.05       0  5012.1    0.05       0  5570.1    0.07       0
  5619.5    0.05       0
Bank Sta=5002.2,5012.1
Exp/Cntr=0.3,0.1

Type RM Length L Ch R = 1,11888,938,938,938
BEGIN DESCRIPTION:
UNNAMED SLOUGH #1 17.0
END DESCRIPTION:
XS GIS Cut Line= 3
      2455424.97     13738125.00      2455025.00     13738125.00
      2454225.04     13738774.97
#Sta/Elev= 30
  4599.8  298.95  4759.8  285.89  4869.8  281.82  4949.8  280.16  4969.8  278.00
  4974.8  276.03  4975.3  275.53  4984.7  276.03  4997.3  279.60  5027.8  281.28
  5099.6  279.49  5106.1  278.63  5134.8  278.58  5149.2  280.15  5227.5  280.55
  5297.9  278.23  5334.5  277.95  5384.1  279.36  5390.5  280.55  5404.9  280.97
  5412.1  279.84  5419.3  281.43  5425.7  280.78  5454.5  283.09  5532.8  284.04
  5675.0  288.63  5774.1  294.93  5930.7  303.11  5973.8  306.97  6030.5  309.34
#Mann=3,-1,0
  4599.8    0.05       0  4974.8    0.05       0  4984.7    0.05       0
Bank Sta=4974.8,4984.7
Exp/Cntr=0.3,0.1

Type RM Length L Ch R = 1,10950,480,480,480
BEGIN DESCRIPTION:
UNNAMED SLOUGH #1 16.0
END DESCRIPTION:
XS GIS Cut Line= 3
      2455799.68     13737635.60      2454625.00     13737525.00
      2452358.17     13737727.12
#Sta/Elev= 30
  3825.0  306.37  3855.9  305.46  3910.1  302.51  3940.2  299.59  4060.7  294.58
  4171.2  288.16  4432.4  280.10  4944.6  277.33  4979.7  274.50  4980.2  274.00
  4989.8  274.50  5035.0  278.76  5135.4  278.58  5225.7  281.76  5316.1  287.38
  5406.5  290.36  5511.7  288.61  5733.3  282.51  5832.4  281.47  5919.1  281.11
  6129.3  281.04  6190.9  283.05  6259.8  278.77  6292.5  278.27  6738.9  280.09
  6952.6  283.12  7103.2  290.29  7183.5  292.45  7213.6  294.50  7280.7  293.89
#Mann=9,-1,0
  3825.0   0.035       0  3855.9    0.05       0  4979.7    0.05       0
  4989.8    0.05       0  5733.3   0.063       0  5832.4   0.094       0
  5919.1   0.063       0  6292.5    0.05       0  6738.9   0.063       0
Bank Sta=4979.7,4989.8
Exp/Cntr=0.3,0.1

Type RM Length L Ch R = 1,10470,1734,1734,1734
BEGIN DESCRIPTION:
XS7880
END DESCRIPTION:
XS GIS Cut Line= 2
      2455983.08     13737003.97      2452081.22     13737228.10
#Sta/Elev= 30
  3736.0  315.08  3754.1  315.72  3884.3  308.15  4124.7  287.74  4164.8  285.35
  4194.9  285.26  4305.0  279.14  4534.5  275.60  4595.5  277.30  4775.8  277.92
  4986.1  276.44  5021.2  273.32  5021.7  272.82  5031.3  273.32  5061.5  275.85
  5226.5  275.62  5316.7  277.24  5707.3  276.79  5864.7  278.33  5867.9  278.28
  6158.1  277.88  6809.9  279.96  7199.8  279.00  7380.1  283.33  7420.1  286.32
  7450.2  289.87  7541.0  294.94  7550.4  294.26  7620.5  296.84  7644.3  296.60
#Mann=6,-1,0
  3736.0    0.05       0  5021.2    0.05       0  5031.3    0.05       0
  5864.7   0.094       0  5867.9    0.05       0  7541.0   0.045       0
Bank Sta=5021.2,5031.3
Exp/Cntr=0.3,0.1

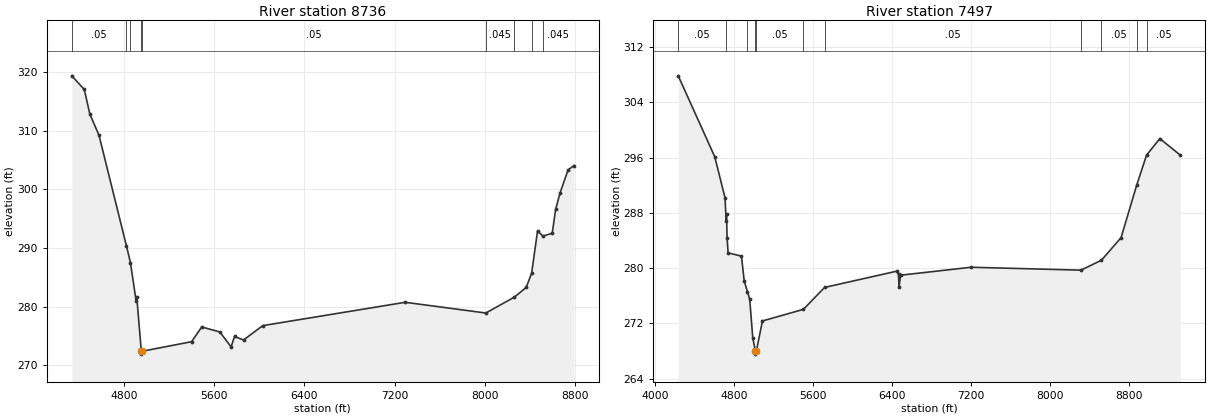
Type RM Length L Ch R = 1,8736,1239,1239,1239
BEGIN DESCRIPTION:
XS7879
END DESCRIPTION:
XS GIS Cut Line= 3
      2456125.73     13736545.53      2454291.93     13736464.03
      2451683.88     13736637.22
#Sta/Elev= 30
  4339.1  319.35  4449.9  317.02  4500.0  312.78  4580.1  309.23  4824.1  290.31
  4858.9  287.51  4909.7  280.91  4914.7  281.70  4955.3  272.39  4955.8  271.89
  4965.6  272.39  5400.9  274.01  5491.0  276.52  5651.1  275.67  5751.2  273.12
  5781.3  274.90  5861.3  274.30  6031.5  276.75  7294.1  280.73  8008.6  278.90
  8262.2  281.62  8366.5  283.27  8414.8  285.72  8466.7  292.89  8513.7  292.02
  8597.0  292.51  8627.0  296.57  8667.1  299.43  8737.3  303.30  8788.5  304.04
#Mann=9,-1,0
  4339.1    0.05       0  4824.1    0.07       0  4858.9    0.05       0
  4955.3    0.05       0  4965.6    0.05       0  8008.6   0.045       0
  8262.2    0.05       0  8414.8   0.035       0  8513.7   0.045       0
Bank Sta=4955.3,4965.6
Exp/Cntr=0.3,0.1

Type RM Length L Ch R = 1,7497,0,0,0
BEGIN DESCRIPTION:
XS7878
END DESCRIPTION:
XS GIS Cut Line= 3
      2456359.98     13735964.83      2455402.38     13735689.77
      2451338.77     13736086.97
#Sta/Elev= 30
  4235.3  307.83  4604.6  296.12  4708.7  290.18  4720.0  286.80  4724.0  287.82
  4729.5  284.36  4739.9  282.21  4875.1  281.74  4903.0  278.11  4935.6  276.61
  4958.4  275.51  4989.6  269.86  5015.3  268.06  5015.8  267.56  5026.3  268.06
  5087.2  272.36  5501.9  274.04  5715.8  277.21  6444.8  279.56  6463.7  279.13
  6468.7  277.23  6484.9  278.98  7198.3  280.13  8309.0  279.71  8517.0  281.15
  8715.5  284.42  8873.7  292.03  8972.9  296.35  9107.4  298.75  9314.6  296.35
#Mann=11,-1,0
  4235.3    0.05       0  4720.0    0.07       0  4935.6    0.05       0
  5015.3    0.05       0  5026.3    0.05       0  5501.9    0.07       0
  5715.8    0.05       0  8309.0   0.045       0  8517.0    0.05       0
  8873.7   0.035       0  8972.9    0.05       0
Bank Sta=5015.3,5026.3
Exp/Cntr=0.3,0.1

Chan Stop Cuts=-1