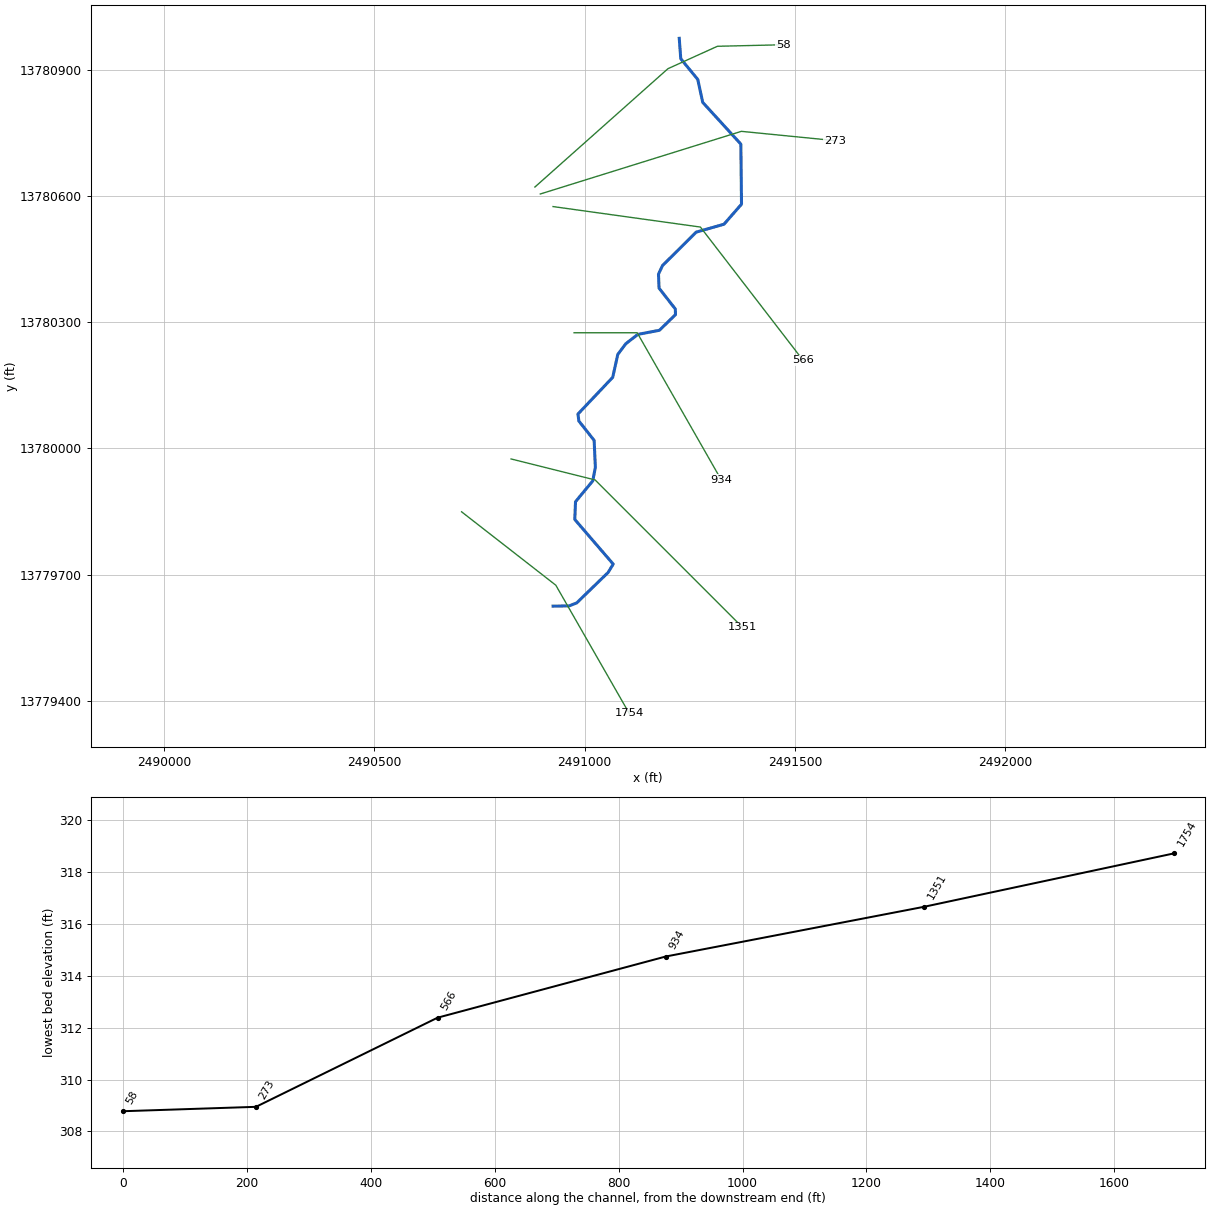
--- BALDRIDGE BRANCH.prj (project) ---

Proj Title=BALDRIDGE BRANCH Base Level Engineering
Current Plan=p01
Default Exp/Contr=0.3,0.1
English Units
Geom File=g01
Flow File=f01
Plan File=p01
BEGIN DESCRIPTION:
BALDRIDGE BRANCH
END DESCRIPTION:

--- BALDRIDGE BRANCH.p01 (plan) ---

Plan Title=Multiple Run
Short Identifier=Multiple
Geom File=g01
Flow File=f01
Subcritical Flow
K Sum by GR= 0
Std Step Tol= 0.01
Critical Tol= 0.01
Num of Std Step Trials= 20
Max Error Tol= 0.3
Flow Tol Ratio= 0.001
Split Flow NTrial= 30
Split Flow Tol= 0.02
Split Flow Ratio= 0.02
Log Output Level= 0
Friction Slope Method= 1
Unsteady Friction Slope Method= 2
Unsteady Bridges Friction Slope Method= 1
Parabolic Critical Depth
Global Vel Dist=  1 , 1 , 1
Global Log Level= 0
CheckData=True
Encroach Param= -1, 0, 0, 0
BEGIN DESCRIPTION:
Multiple Run
END DESCRIPTION:

--- BALDRIDGE BRANCH.f01 (steady flow) ---

Flow Title=Multiple
Number of Profiles=7
Profile Names=10-year,25-year,50-year,1pct_min,100-year,1pct_plu,500-year
River Rch & RM= BALDRIDGE BRANCH,Reach-1,1754
     702    1133    1523     991    1978    3947    3303
Boundary for River Rch & Prof#=BALDRIDGE BRANCH,Reach-1,1
Up Type=0
Dn Type=3
Dn Slope=0.005
Boundary for River Rch & Prof#=BALDRIDGE BRANCH,Reach-1,2
Up Type=0
Dn Type=3
Dn Slope=0.005
Boundary for River Rch & Prof#=BALDRIDGE BRANCH,Reach-1,3
Up Type=0
Dn Type=3
Dn Slope=0.005
Boundary for River Rch & Prof#=BALDRIDGE BRANCH,Reach-1,4
Up Type=0
Dn Type=3
Dn Slope=0.005
Boundary for River Rch & Prof#=BALDRIDGE BRANCH,Reach-1,5
Up Type=0
Dn Type=3
Dn Slope=0.005
Boundary for River Rch & Prof#=BALDRIDGE BRANCH,Reach-1,6
Up Type=0
Dn Type=3
Dn Slope=0.005
Boundary for River Rch & Prof#=BALDRIDGE BRANCH,Reach-1,7
Up Type=0
Dn Type=3
Dn Slope=0.005

--- BALDRIDGE BRANCH.g01 (geometry) ---

Geom Title=Existing Conditions

River Reach=BALDRIDGE BRANCH,Reach-1
Reach XY= 30
      2490925.00     13779625.00      2490963.18     13779625.59
      2490981.27     13779632.76      2491055.84     13779704.97
      2491067.94     13779724.99      2490976.64     13779831.03
      2490978.35     13779873.25      2491019.27     13779922.68
      2491025.57     13779954.95      2491022.63     13780019.11
      2490986.34     13780065.15      2490984.15     13780081.73
      2491066.80     13780168.97      2491078.89     13780223.57
      2491097.87     13780248.84      2491126.50     13780271.11
      2491177.82     13780280.86      2491215.97     13780317.99
      2491215.73     13780331.40      2491176.99     13780381.04
      2491175.64     13780414.36      2491185.20     13780434.70
      2491265.31     13780514.22      2491331.38     13780533.02
      2491373.03     13780580.68      2491371.46     13780723.53
      2491280.83     13780822.70      2491269.03     13780877.24
      2491228.60     13780926.49      2491225.00     13780975.00

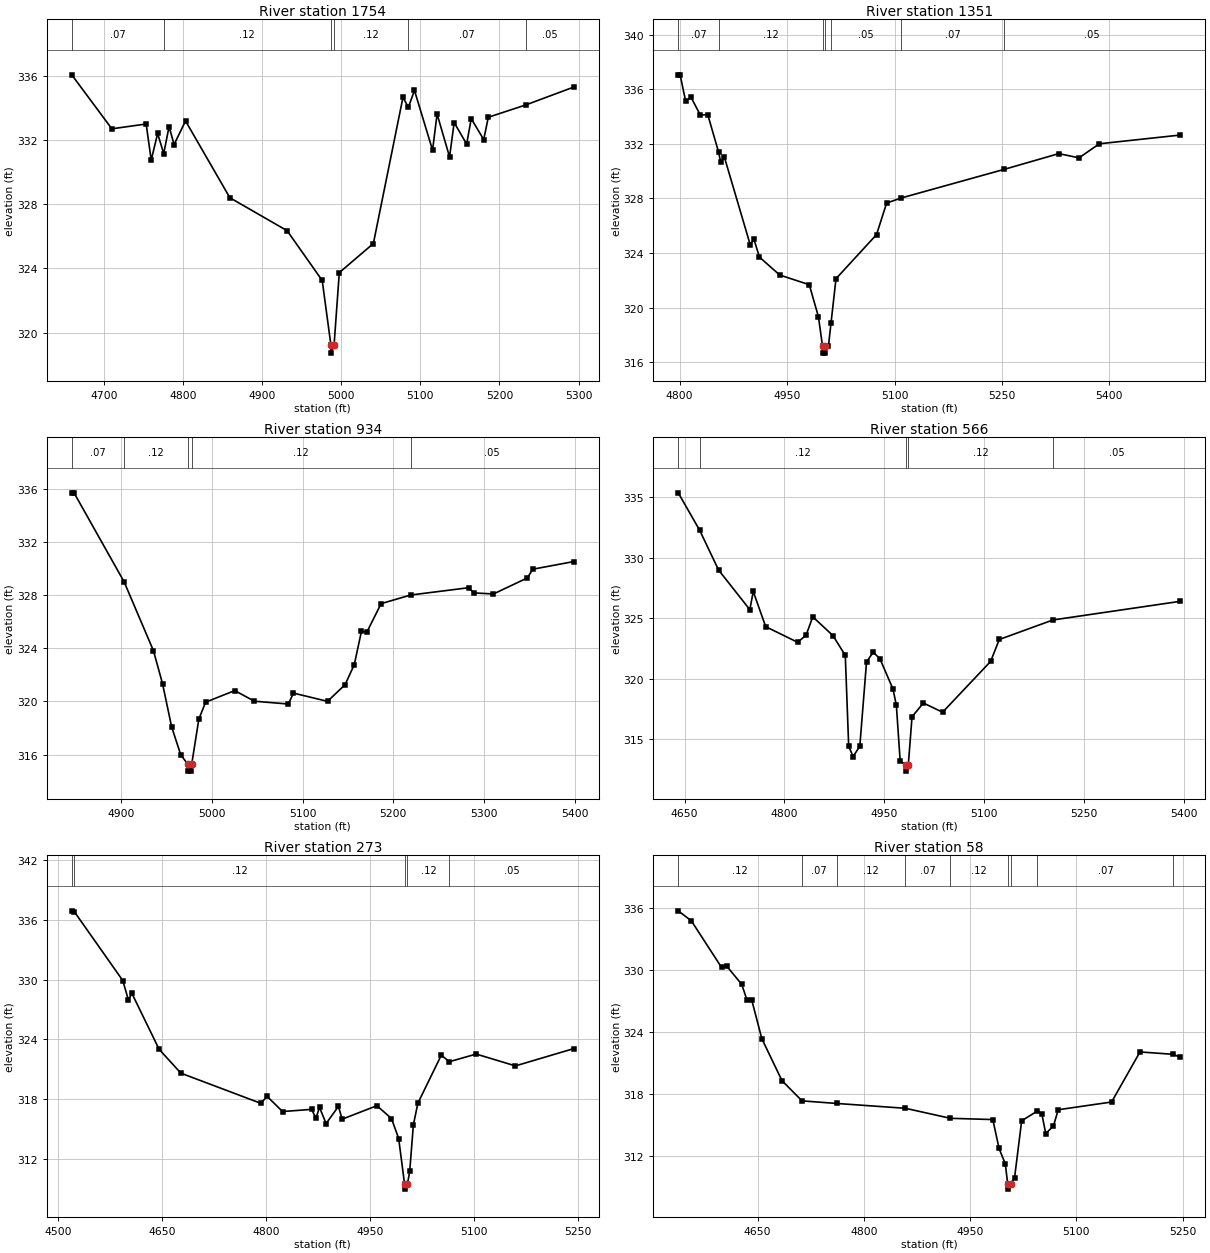
Type RM Length L Ch R = 1,1754,403,403,403
BEGIN DESCRIPTION:
X18071
END DESCRIPTION:
XS GIS Cut Line= 3
      2490707.54     13779849.26      2490931.54     13779674.75
      2491106.04     13779370.03
#Sta/Elev= 30
  4659.0  336.05  4709.7  332.69  4753.1  332.99  4759.5  330.74  4767.6  332.40
  4775.3  331.15  4782.1  332.83  4788.4  331.71  4802.9  333.18  4859.0  328.40
  4931.4  326.35  4975.8  323.25  4986.8  319.23  4987.0  318.73  4990.8  319.23
  4997.4  323.74  5040.5  325.55  5078.0  334.66  5084.7  334.02  5092.5  335.08
  5115.4  331.36  5121.1  333.61  5136.9  330.94  5142.7  333.08  5158.5  331.74
  5164.3  333.32  5180.1  332.02  5185.9  333.41  5233.5  334.18  5294.1  335.29
#Mann=6,-1,0
  4659.0    0.07       0  4775.3    0.12       0  4986.8    0.05       0
  4990.8    0.12       0  5084.7    0.07       0  5233.5    0.05       0
Bank Sta=4986.8,4990.8
Exp/Cntr=0.3,0.1

Type RM Length L Ch R = 1,1351,417,417,417
BEGIN DESCRIPTION:
BALDRIDGE BRANCH 3.0
END DESCRIPTION:
XS GIS Cut Line= 3
      2490825.00     13779975.00      2491025.00     13779925.00
      2491374.98     13779575.02
#Sta/Elev= 30
  4798.0  337.05  4800.6  337.05  4808.3  335.13  4816.0  335.39  4828.9  334.10
  4839.2  334.14  4854.3  331.40  4857.3  330.66  4862.4  331.03  4898.5  324.61
  4903.7  325.01  4911.4  323.70  4939.7  322.39  4981.0  321.68  4993.8  319.33
  4999.5  317.17  4999.8  316.67  5003.3  316.67  5003.6  317.17  5007.7  317.17
  5011.3  318.85  5018.3  322.12  5074.9  325.35  5089.0  327.66  5109.3  328.03
  5252.7  330.12  5329.4  331.28  5357.7  330.97  5386.0  332.00  5499.1  332.64
#Mann=7,-1,0
  4798.0    0.07       0  4854.3    0.12       0  4999.5    0.05       0
  5003.6    0.12       0  5011.3    0.05       0  5109.3    0.07       0
  5252.7    0.05       0
Bank Sta=4999.5,5003.6
Exp/Cntr=0.3,0.1

Type RM Length L Ch R = 1,934,368,368,368
BEGIN DESCRIPTION:
BALDRIDGE BRANCH 2.0
END DESCRIPTION:
XS GIS Cut Line= 3
      2490974.95     13780275.00      2491125.00     13780275.00
      2491325.02     13779924.97
#Sta/Elev= 30
  4845.7  335.69  4848.2  335.69  4903.4  328.99  4935.7  323.81  4945.7  321.33
  4955.7  318.09  4965.7  315.99  4973.7  315.25  4973.9  314.75  4977.5  314.75
  4977.8  315.25  4985.7  318.66  4993.2  319.94  5025.3  320.81  5046.9  320.01
  5084.3  319.80  5090.0  320.62  5127.5  320.00  5146.9  321.26  5157.0  322.77
  5164.9  325.28  5170.7  325.19  5186.5  327.35  5219.0  328.00  5283.0  328.55
  5288.7  328.16  5310.3  328.08  5347.8  329.29  5353.5  329.94  5398.9  330.52
#Mann=5,-1,0
  4845.7    0.07       0  4903.4    0.12       0  4973.7    0.05       0
  4977.8    0.12       0  5219.0    0.05       0
Bank Sta=4973.7,4977.8
Exp/Cntr=0.3,0.1

Type RM Length L Ch R = 1,566,293,293,293
BEGIN DESCRIPTION:
BALDRIDGE BRANCH 1.0
END DESCRIPTION:
XS GIS Cut Line= 3
      2490924.95     13780575.01      2491275.29     13780526.31
      2491519.48     13780209.38
#Sta/Elev= 30
  4640.5  335.35  4672.5  332.28  4701.1  328.98  4748.0  325.71  4753.1  327.21
  4771.8  324.31  4819.7  323.02  4832.4  323.60  4842.5  325.12  4872.8  323.57
  4891.3  321.94  4896.4  314.45  4903.0  313.59  4913.1  314.44  4923.2  321.40
  4933.3  322.21  4943.4  321.65  4963.0  319.15  4968.0  317.81  4973.7  313.23
  4981.8  312.89  4982.0  312.39  4985.9  312.89  4991.5  316.87  5008.5  318.01
  5037.4  317.25  5109.5  321.44  5122.5  323.25  5203.0  324.86  5394.3  326.40
#Mann=5,-1,0
  4640.5    0.07       0  4672.5    0.12       0  4981.8    0.05       0
  4985.9    0.12       0  5203.0    0.05       0
Bank Sta=4981.8,4985.9
Exp/Cntr=0.3,0.1

Type RM Length L Ch R = 1,273,215,215,215
BEGIN DESCRIPTION:
X18070
END DESCRIPTION:
XS GIS Cut Line= 3
      2490894.70     13780604.94      2491372.75     13780753.87
      2491595.25     13780731.81
#Sta/Elev= 30
  4520.1  336.93  4523.8  336.84  4593.7  329.92  4601.7  327.99  4606.9  328.62
  4646.1  323.01  4677.5  320.61  4792.7  317.58  4802.0  318.27  4824.2  316.75
  4866.1  316.97  4872.3  316.09  4877.5  317.17  4887.0  315.54  4904.8  317.27
  4910.1  315.98  4960.3  317.34  4981.3  316.05  4991.7  314.04  5000.2  309.45
  5000.4  308.95  5004.3  309.45  5007.6  310.73  5012.9  315.41  5019.4  317.59
  5053.2  322.42  5064.8  321.76  5103.5  322.53  5160.1  321.34  5244.4  323.08
#Mann=5,-1,0
  4520.1    0.07       0  4523.8    0.12       0  5000.2    0.05       0
  5004.3    0.12       0  5064.8    0.05       0
Bank Sta=5000.2,5004.3
Exp/Cntr=0.3,0.1

Type RM Length L Ch R = 1,58,0,0,0
BEGIN DESCRIPTION:
X18069
END DESCRIPTION:
XS GIS Cut Line= 4
      2490881.88     13780621.52      2491198.09     13780902.80
      2491315.75     13780956.11      2491471.92     13780959.74
#Sta/Elev= 30
  4538.1  335.74  4556.6  334.77  4599.2  330.26  4606.8  330.36  4627.7  328.62
  4635.2  327.08  4641.9  327.08  4656.1  323.35  4684.5  319.29  4712.8  317.33
  4761.6  317.08  4858.8  316.61  4922.1  315.64  4982.1  315.52  4990.9  312.72
  4999.7  311.23  5003.1  309.28  5003.4  308.78  5007.2  309.28  5012.8  309.90
  5022.8  315.40  5045.1  316.35  5051.3  316.05  5056.8  314.16  5067.7  314.91
  5074.4  316.47  5149.7  317.22  5189.8  322.07  5236.6  321.84  5246.7  321.54
#Mann=9,-1,0
  4538.1    0.12       0  4712.8    0.07       0  4761.6    0.12       0
  4858.8    0.07       0  4922.1    0.12       0  5003.1    0.05       0
  5007.2    0.12       0  5045.1    0.07       0  5236.6    0.05       0
Bank Sta=5003.1,5007.2
Exp/Cntr=0.3,0.1

Chan Stop Cuts=-1