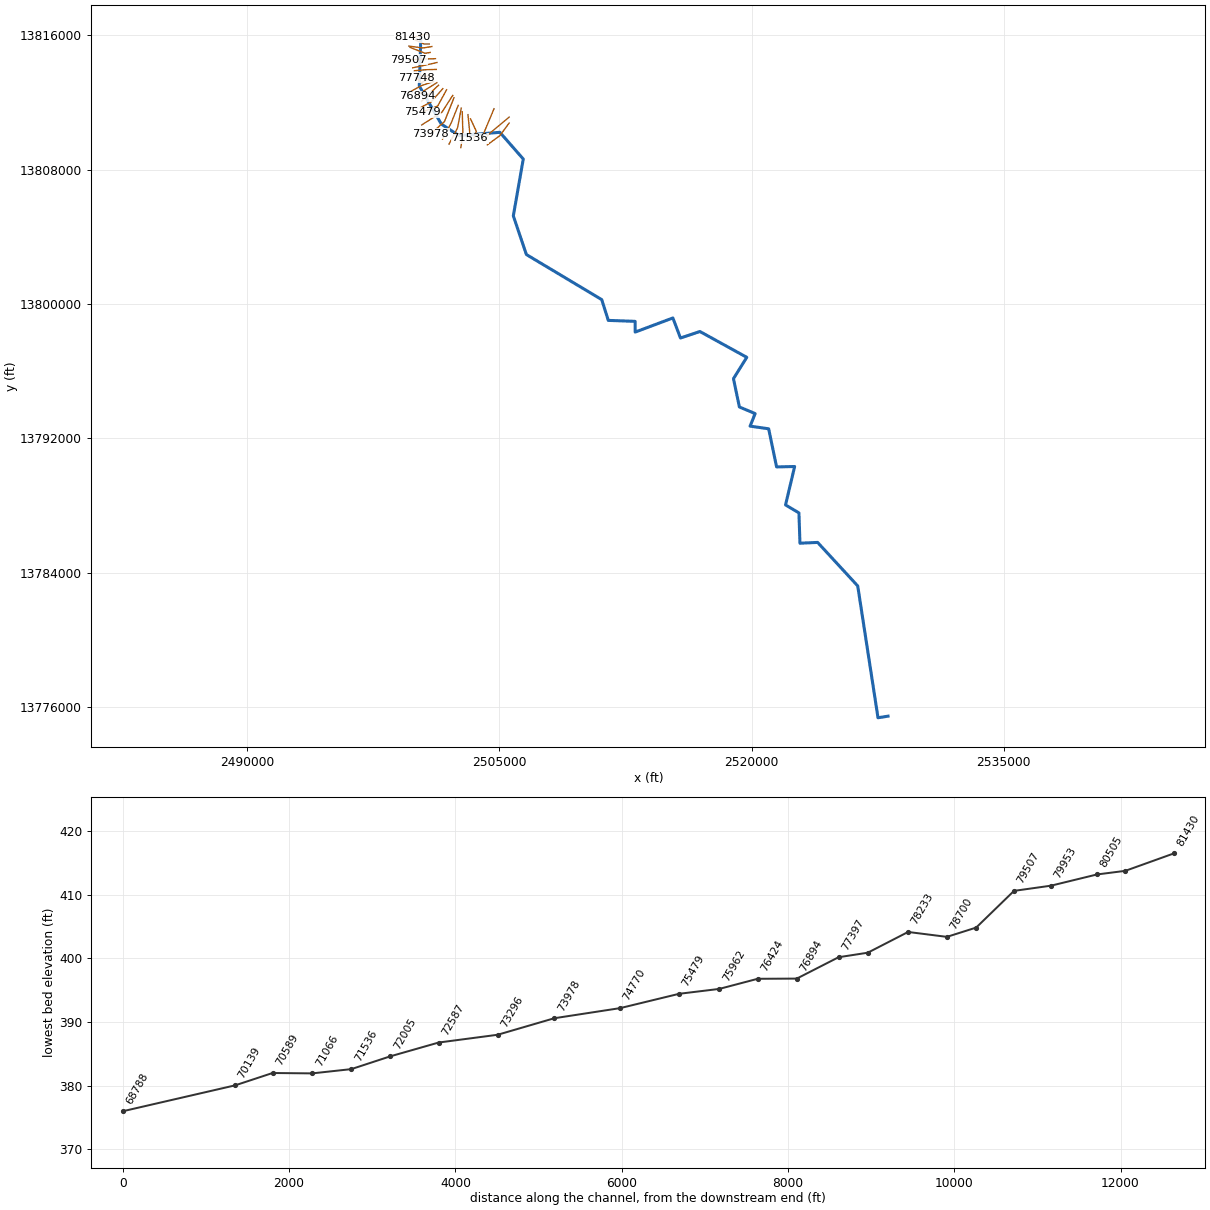
--- BALDRIDGE CREEK.prj (project) ---

Proj Title=BALDRIDGE CREEK Base Level Engineering
Current Plan=p01
Default Exp/Contr=0.3,0.1
English Units
Geom File=g01
Flow File=f01
Plan File=p01
Y Axis Title=Elevation
X Axis Title(PF)=Main Channel Distance
X Axis Title(XS)=Station
BEGIN DESCRIPTION:
BALDRIDGE CREEK
END DESCRIPTION:
DSS Export Rating Curves= 0
DSS Export Rating Curve Sorted= 0
DSS Export Volume Flow Curves= 0
DXF OffsetX= 0
DXF OffsetY= 0
DXF ScaleX= 1
DXF ScaleY= 10

--- BALDRIDGE CREEK.p01 (plan) ---

Plan Title=Multiple Run
Program Version=4.10
Short Identifier=Multiple
Geom File=g01
Flow File=f01
Subcritical Flow
K Sum by GR= 0
Std Step Tol= 0.01
Critical Tol= 0.01
Num of Std Step Trials= 20
Max Error Tol= 0.3
Flow Tol Ratio= 0.001
Split Flow NTrial= 30
Split Flow Tol= 0.02
Split Flow Ratio= 0.02
Log Output Level= 0
Friction Slope Method= 1
Unsteady Friction Slope Method= 2
Unsteady Bridges Friction Slope Method= 1
Parabolic Critical Depth
Global Vel Dist= 1 , 1 , 1
Global Log Level= 0
CheckData=True
Encroach Param=-1 ,0,0, 0
BEGIN DESCRIPTION:
Multiple Run
END DESCRIPTION:
Computation Interval=1HOUR
Output Interval=1HOUR
Run HTab= 0
Run UNet= 0
Run PostProcess= 0
Run WQNet= 0
UNET Theta= 1
UNET Theta Warmup= 1
UNET ZTol= 0.02
UNET ZSATol= 0.05
UNET MxIter= 20
UNET MaxInSteps= 0
UNET DtIC= 0
UNET DtMin= 0
UNET MaxCRTS= 20
UNET WFStab= 2
UNET SFStab= 1
UNET WFX= 1
UNET SFX= 1
UNET DSS MLevel= 4
UNET DZMax Abort= 100
UNET Convert EG Bridges= 0
UNET Use Existing IB Tables=-1
UNET Froude Reduction=False
UNET Froude Limit= 1
UNET Froude Power= 10
UNET Time Slicing=0,0, 5
UNET Junction Losses=0
Instantaneous Interval=1HOUR
Write IC File= 0
Write IC File at Sim End=0
Echo Input=False
Echo Parameters=False
Echo Output=False
Write Detailed= 0
WQ AD Non Conservative
WQ ULTIMATE=-1
WQ Max Comp Step=1HOUR
WQ Output Interval=15MIN
WQ Output Selected Increments= 0
WQ Output face flow=0
WQ Output face velocity=0
WQ Output face area=0
WQ Output face dispersion=0
WQ Output cell volume=0
WQ Output cell surface area=0
WQ Output cell continuity=0
WQ Output cumulative cell continuity=0
WQ Output face conc=0
WQ Output face dconc_dx=0
WQ Output face courant=0
WQ Output face peclet=0
WQ Output face adv mass=0
WQ Output face disp mass=0
WQ Output cell mass=0
WQ Output cell source sink temp=0
WQ Output cell source sink nsm=0
WQ Output MaxMinRange=-1
WQ Daily Max Min Mean=-1
WQ Daily Range=0
WQ Daily Time=0
WQ Create Restart=0
WQ Fixed Restart=0
WQ System Summary=0
WQ Use Fixed Temperature=0
Sorting and Armoring Iterations= 10
XS Update Threshold= 0.02
Hydraulics Update Threshold= 0.02
Energy Slope Method= 1
Volume Change Method= 0
XS Weighting Method= 0
Number of US Weighted Cross Sections= 1
Number of DS Weighted Cross Sections= 1
Upstream XS Weight=0.25
Main XS Weight=0.5
Downstream XS Weight=0.25
Number of DS XS's Weighted with US Boundary= 1
Upstream Boundary Weight= 1
Weight of XSs Associated with US Boundary= 0
Number of US XS's Weighted with DS Boundary= 1
Downstream Boundary Weight= 0.5
Weight of XSs Associated with DS Boundary= 0.5
Sediment Output Level= 4
Mass or Volume Output= 0
Output Increment Type= 1
Profile and TS Output Increment= 10
XS Output Flag= 0
XS Output Increment= 10
Disregard all LS=0
Disregard all Conn=0
Disregard all Breaches=0
Disregard all Pumps=0

--- BALDRIDGE CREEK.f01 (steady flow) ---

Flow Title=Multiple
Number of Profiles=7
Profile Names=10-year,25-year,50-year,1pct_min,100-year,1pct_plu,500-year
River Rch & RM= BALDRIDGE CREEK,Reach-1,81430
     714    1150    1545    1005    2006    4002    3346
River Rch & RM= BALDRIDGE CREEK,Reach-1,77397
    1037    1708    2329    1536    3064    6114    5253
River Rch & RM= BALDRIDGE CREEK,Reach-1,76424
    1117    1831    2486    1631    3254    6492    5521
River Rch & RM= BALDRIDGE CREEK,Reach-1,70589
    1376    2271    3098    2039    4069    8119    6956
River Rch & RM= BALDRIDGE CREEK,Reach-1,67195
    1504    2484    3388    2230    4449    8877    7599
River Rch & RM= BALDRIDGE CREEK,Reach-1,60817
    1932    3226    4434    2938    5863   11697   10154
River Rch & RM= BALDRIDGE CREEK,Reach-1,58846
    2071    3459    4755    3150    6284   12539   10877
River Rch & RM= BALDRIDGE CREEK,Reach-1,53483
    2019    3362    4610    3046    6078   12127   10468
River Rch & RM= BALDRIDGE CREEK,Reach-1,49765
    2092    3480    4769    3148    6281   12531   10795
River Rch & RM= BALDRIDGE CREEK,Reach-1,41014
    2935    4941    6827    4539    9056   18069   15791
River Rch & RM= BALDRIDGE CREEK,Reach-1,33453
    2975    5006    6913    4594    9166   18289   15968
River Rch & RM= BALDRIDGE CREEK,Reach-1,30142
    3310    5583    7722    5138   10251   20454   17899
River Rch & RM= BALDRIDGE CREEK,Reach-1,26335
    3405    5742    7942    5283   10541   21031   18396
River Rch & RM= BALDRIDGE CREEK,Reach-1,19935
    3499    5901    8160    5427   10828   21605   18888
River Rch & RM= BALDRIDGE CREEK,Reach-1,14882
    3583    6040    8352    5553   11080   22107   19319
River Rch & RM= BALDRIDGE CREEK,Reach-1,10882
    3623    6106    8441    5611   11195   22336   19507
River Rch & RM= BALDRIDGE CREEK,Reach-1,7745
    3783    6374    8808    5852   11675   23295   20322
Boundary for River Rch & Prof#=BALDRIDGE CREEK,Reach-1,1
Up Type=0
Dn Type=3
Dn Slope=0.0001
Boundary for River Rch & Prof#=BALDRIDGE CREEK,Reach-1,2
Up Type=0
Dn Type=3
Dn Slope=0.0001
Boundary for River Rch & Prof#=BALDRIDGE CREEK,Reach-1,3
Up Type=0
Dn Type=3
Dn Slope=0.0001
Boundary for River Rch & Prof#=BALDRIDGE CREEK,Reach-1,4
Up Type=0
Dn Type=3
Dn Slope=0.0001
Boundary for River Rch & Prof#=BALDRIDGE CREEK,Reach-1,5
Up Type=0
Dn Type=3
Dn Slope=0.0001
Boundary for River Rch & Prof#=BALDRIDGE CREEK,Reach-1,6
Up Type=0
Dn Type=3
Dn Slope=0.0001
Boundary for River Rch & Prof#=BALDRIDGE CREEK,Reach-1,7
Up Type=0
Dn Type=3
Dn Slope=0.0001

--- BALDRIDGE CREEK.g01 (geometry) ---

Geom Title=Existing Conditions
Program Version=4.10

River Reach=BALDRIDGE CREEK ,Reach-1
Reach XY= 30
        2500325.       13816025.      2500227.04     13812980.85
      2501538.16     13810711.27      2502585.64     13810025.65
      2505023.84     13810221.88      2506416.05     13808631.68
      2505824.36     13805249.62      2506601.54      13802947.7
      2511085.16     13800264.72      2511476.46     13799028.54
      2513073.78     13798971.63       2513074.9     13798332.31
      2515319.55     13799172.96      2515772.26     13797980.34
      2516928.42     13798367.24      2519716.86     13796831.06
      2518925.36     13795559.73      2519278.49     13793876.27
      2520215.89     13793481.73       2519915.2     13792735.48
      2521020.03     13792577.58      2521491.64     13790308.32
      2522566.17       13790332.      2522024.96     13788044.76
      2522821.54     13787573.51      2522882.67     13785768.48
      2523935.18     13785814.68      2526321.55     13783223.75
      2527526.96     13775380.65        2528125.       13775475.

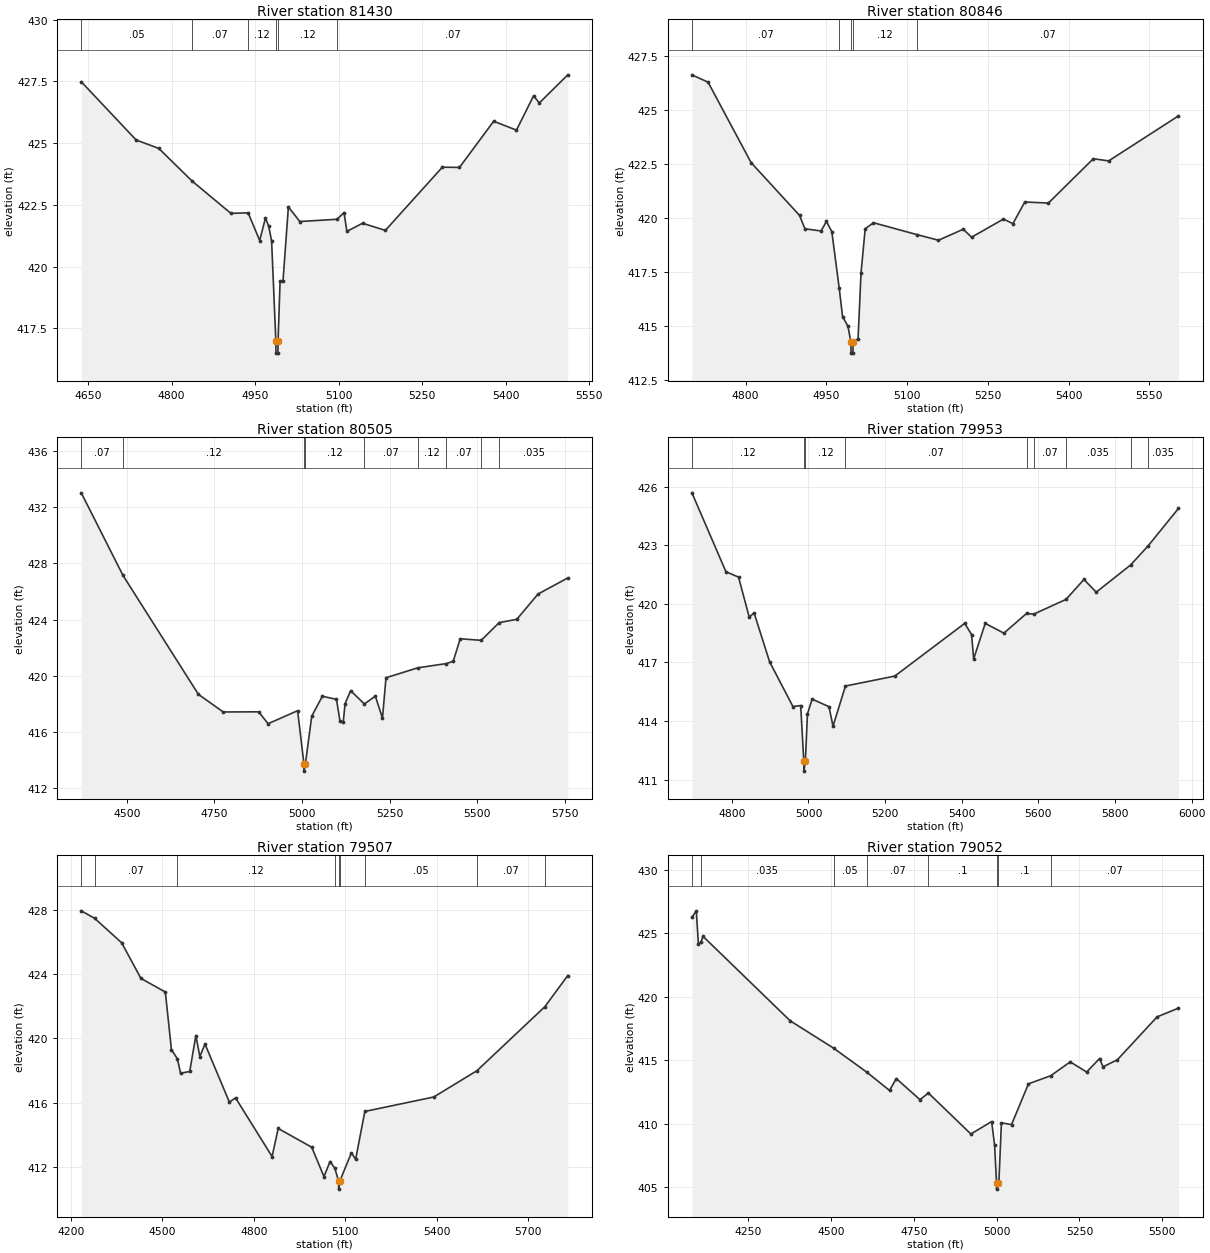
Type RM Length L Ch R = 1 ,81430   ,584,584,584
BEGIN DESCRIPTION:
BALDRIDGE CREEK 87.0
END DESCRIPTION:
XS GIS Cut Line= 3
      2500674.96     13816074.99      2500329.05     13815984.92
      2499825.04     13815875.01
#Sta/Elev= 30
  4637.9  427.49  4736.5  425.13  4777.1  424.79  4836.8  423.47  4906.5  422.16
  4937.5  422.18  4958.2  421.06  4968.5  421.97  4974.4  421.64  4979.6  421.04
  4987.2     417  4987.4   416.5  4990.9   416.5  4991.2     417  4994.8  419.41
    5000  419.41  5009.7  422.42  5030.2  421.83  5096.9  421.92  5109.6  422.19
  5114.7  421.43  5142.8  421.76  5183.7  421.47  5286.1  424.03  5316.8  424.02
  5378.2  425.89  5419.1  425.53  5449.8  426.92  5460.1  426.63  5511.2  427.77
#Mann= 6 ,-1 , 0
  4637.9     .05       0  4836.8     .07       0  4937.5     .12       0
  4987.2     .05       0  4991.2     .12       0  5096.9     .07       0
Bank Sta=4987.2,4991.2
XS Rating Curve= 0 ,0
Exp/Cntr=0.3,0.1

Type RM Length L Ch R = 1 ,80846   ,341,341,341
BEGIN DESCRIPTION:
BALDRIDGE CREEK 86.0
END DESCRIPTION:
XS GIS Cut Line= 3
      2500825.01       13815475.        2500525.       13815475.
      2499974.97     13815725.02
#Sta/Elev= 30
  4700.1  426.63  4730.1  426.29  4810.1  422.57  4900.1  420.13  4910.1  419.51
  4940.1  419.41  4950.1  419.85  4960.1  419.38  4973.8  416.77  4980.1  415.45
  4990.1     415  4995.6  414.26  4995.9  413.76  4999.4  413.76  4999.6  414.26
  5008.9  414.43  5014.4  417.47  5022.1  419.51  5037.5  419.79  5118.5  419.24
  5158.3  418.98  5204.4  419.49  5219.8  419.12  5279.1  419.96  5296.7  419.75
  5318.7  420.75  5362.6   420.7  5446.1  422.75  5474.6  422.65  5604.3  424.73
#Mann= 5 ,-1 , 0
  4700.1     .07       0  4973.8     .12       0  4995.6     .05       0
  4999.6     .12       0  5118.5     .07       0
Bank Sta=4995.6,4999.6
XS Rating Curve= 0 ,0
Exp/Cntr=0.3,0.1

Type RM Length L Ch R = 1 ,80505   ,552,552,552
BEGIN DESCRIPTION:
BALDRIDGE CREEK 85.0
END DESCRIPTION:
XS GIS Cut Line= 3
      2500975.04     13815325.01      2500447.01     13815241.27
      2499600.83      13815354.1
#Sta/Elev= 30
  4370.3  433.04  4489.4  427.15  4704.5  418.67  4775.3  417.41  4876.6  417.42
  4903.4  416.57  4987.7   417.5  5005.8  413.69  5006.1  413.19  5009.8  413.69
    5028  417.11  5058.3  418.53  5098.6  418.31  5108.7  416.74    5118  416.71
  5123.1     418    5139  418.93  5178.1  417.98  5209.6  418.54  5229.8  416.96
  5239.9  419.85  5330.8  420.56  5411.8  420.86  5431.6  421.02  5451.7  422.63
  5511.6  422.52  5562.7  423.78  5613.2  424.02  5673.7  425.82  5758.6  426.97
#Mann= 9 ,-1 , 0
  4370.3     .07       0  4489.4     .12       0  5005.8     .05       0
  5009.8     .12       0  5178.1     .07       0  5330.8     .12       0
  5411.8     .07       0  5511.6     .12       0  5562.7    .035       0
Bank Sta=5005.8,5009.8
XS Rating Curve= 0 ,0
Exp/Cntr=0.3,0.1

Type RM Length L Ch R = 1 ,79953   ,446,446,446
BEGIN DESCRIPTION:
BALDRIDGE CREEK 84.0
END DESCRIPTION:
XS GIS Cut Line= 3
      2500875.04     13814975.01        2500575.       13814925.
      2499675.03     13815274.99
#Sta/Elev= 30
  4695.8  425.69  4784.5  421.65  4817.5  421.37  4845.4  419.32    4858  419.54
  4898.6  417.03  4959.4  414.74  4979.7  414.79  4987.8  411.93  4988.1  411.43
  4991.8  411.93  4997.4  414.37  5009.6  415.12  5053.6  414.73    5064  413.73
  5096.5  415.79  5225.3   416.3  5407.7     419  5425.7  418.43  5431.1  417.18
  5461.3     419    5510   418.5  5569.2  419.51  5587.5  419.47  5672.2  420.23
  5718.9  421.25    5751   420.6  5840.6  421.99  5885.9  422.96  5965.6  424.89
#Mann= 9 ,-1 , 0
  4695.8     .12       0  4987.8     .05       0  4991.8     .12       0
  5096.5     .07       0  5569.2     .05       0  5587.5     .07       0
  5672.2    .035       0  5840.6     .12       0  5885.9    .035       0
Bank Sta=4987.8,4991.8
XS Rating Curve= 0 ,0
Exp/Cntr=0.3,0.1

Type RM Length L Ch R = 1 ,79507   ,455,455,455
BEGIN DESCRIPTION:
BALDRIDGE CREEK 83.0
END DESCRIPTION:
XS GIS Cut Line= 3
      2501190.66     13814605.32        2500425.       13814575.
      2499595.64     13814543.78
#Sta/Elev= 30
  4233.7  427.95  4277.9  427.48  4366.3  425.96  4429.5  423.74  4509.6  422.89
  4529.6   419.3  4549.1  418.73  4559.6  417.83  4589.6  417.94  4609.7  420.18
  4622.8  418.87  4639.7  419.65  4719.7  416.03  4739.8   416.3  4859.8  412.64
  4879.9  414.39  4989.9  413.22    5030  411.39    5050  412.33  5065.6  411.91
    5078  411.11  5078.3  410.61    5082  411.11    5120  412.87    5134  412.47
  5164.1  415.45  5390.2  416.35    5532  417.99  5754.9  421.98  5829.9  423.92
#Mann= 9 ,-1 , 0
  4233.7     .12       0  4277.9     .07       0  4549.1     .12       0
  5065.6     .07       0    5078     .05       0    5082     .07       0
  5164.1     .05       0    5532     .07       0  5754.9    .035       0
Bank Sta=5078,5082
XS Rating Curve= 0 ,0
Exp/Cntr=0.3,0.1

Type RM Length L Ch R = 1 ,79052   ,352,352,352
BEGIN DESCRIPTION:
BALDRIDGE CREEK 82.0
END DESCRIPTION:
XS GIS Cut Line= 3
      2501277.84     13814374.53        2500375.       13814175.
      2499841.84     13814061.69
#Sta/Elev= 30
  4079.3  426.24  4092.5  426.75  4098.9  424.14  4106.1  424.27  4112.9  424.74
  4376.2  418.09  4507.2  415.94  4607.4  414.05  4676.2  412.61  4696.7  413.54
  4768.4  411.88  4793.5  412.41    4922  409.18  4984.7  410.16  4993.7  408.28
  4999.4  405.34  4999.6  404.84  5003.4  405.34  5006.5  405.34  5014.2  410.06
  5044.8  409.92  5095.9  413.13  5163.4  413.77  5222.1  414.86  5271.7  414.06
  5310.6  415.12  5321.3  414.47  5364.7  415.03  5484.4   418.4    5549  419.09
#Mann= 8 ,-1 , 0
  4079.3     .05       0  4106.1    .035       0  4507.2     .05       0
  4607.4     .07       0  4793.5      .1       0  4999.4     .05       0
  5003.4      .1       0  5163.4     .07       0
Bank Sta=4999.4,5003.4
XS Rating Curve= 0 ,0
Exp/Cntr=0.3,0.1

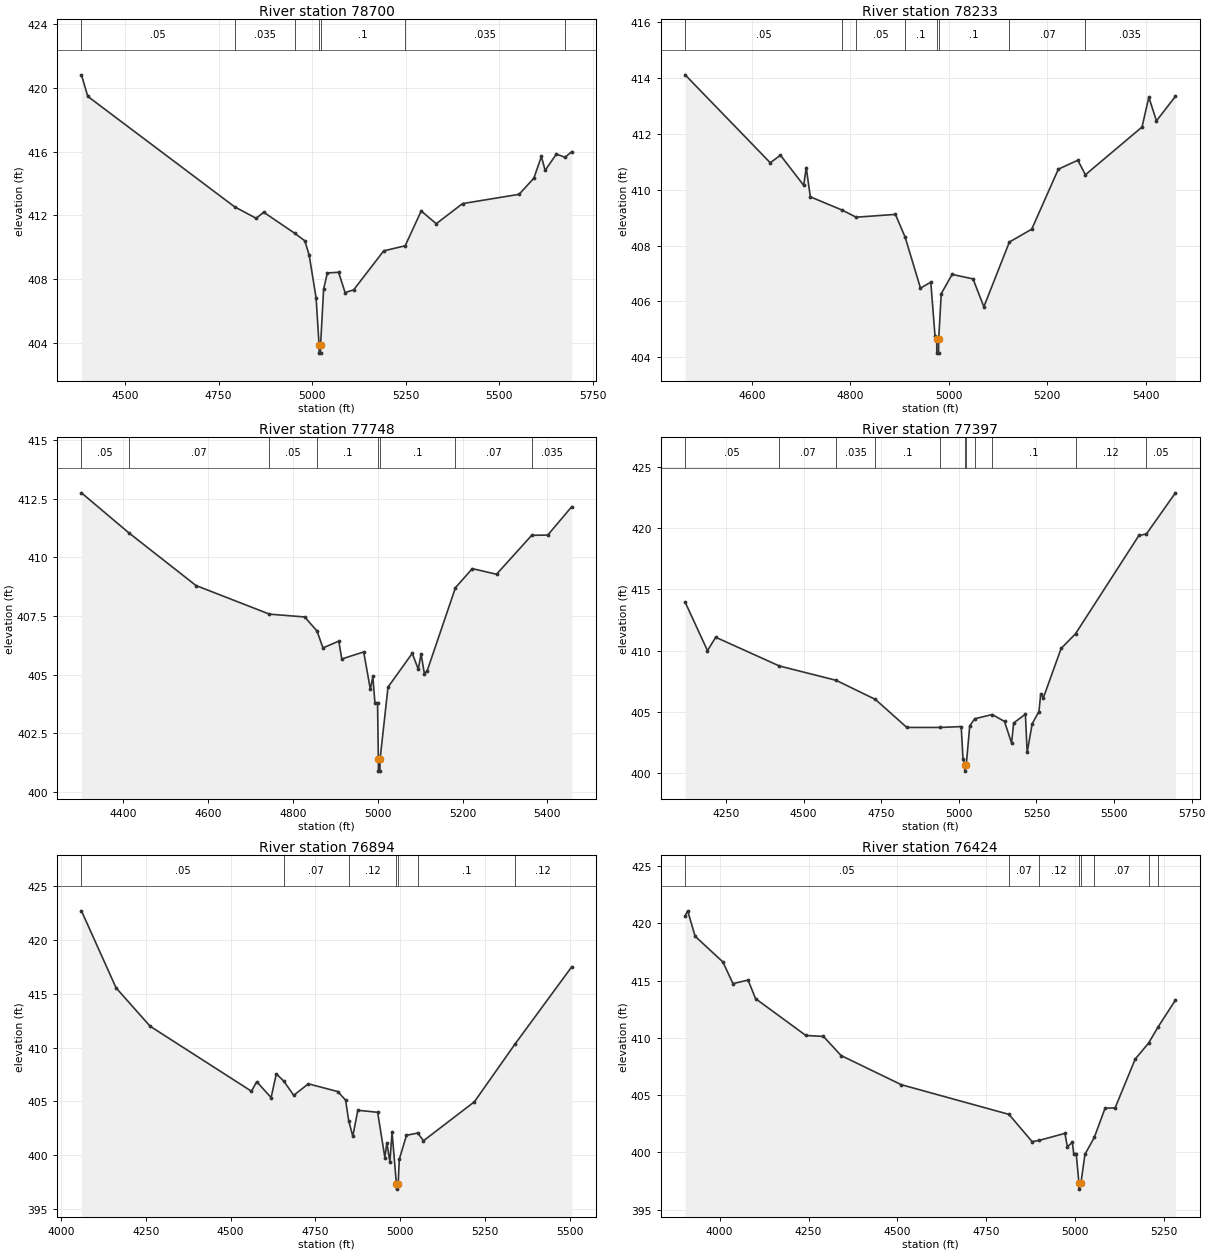
Type RM Length L Ch R = 1 ,78700   ,467,467,467
BEGIN DESCRIPTION:
BALDRIDGE CREEK 81.0
END DESCRIPTION:
XS GIS Cut Line= 3
        2501242.     13813964.24      2500636.77     13813948.86
      2499934.18     13813887.32
#Sta/Elev= 30
  4383.3   420.8  4400.3  419.45  4792.7  412.54  4850.4  411.82  4870.5   412.2
    4953  410.89  4980.5  410.41  4992.1  409.52  5010.6  406.84  5018.6  403.88
  5018.9  403.38  5022.4  403.38  5022.6  403.88  5030.7  407.38  5040.7   408.4
  5070.8  408.44  5088.1  407.17    5111  407.34  5191.3  409.78  5248.8   410.1
  5291.6  412.28  5331.8  411.48  5402.1  412.74  5553.2  413.32  5592.8  414.33
  5612.9  415.69  5622.9  414.82    5653  415.84    5676  415.64    5694  415.99
#Mann= 7 ,-1 , 0
  4383.3     .05       0  4792.7    .035       0    4953      .1       0
  5018.6     .05       0  5022.6      .1       0  5248.8    .035       0
    5676     .07       0
Bank Sta=5018.6,5022.6
XS Rating Curve= 0 ,0
Exp/Cntr=0.3,0.1

Type RM Length L Ch R = 1 ,78233   ,485,485,485
BEGIN DESCRIPTION:
BALDRIDGE CREEK 80.0
END DESCRIPTION:
XS GIS Cut Line= 3
        2501025.       13813625.      2500539.33     13813533.44
      2500075.02     13813724.99
#Sta/Elev= 30
    4464  414.12    4637  410.97  4657.7  411.24    4705  410.16  4710.1   410.8
  4718.4  409.75  4783.6  409.27  4811.5  409.02  4891.4  409.12  4911.2   408.3
  4942.3  406.48  4963.3  406.69  4971.9  404.75  4975.3  404.65  4975.5  404.15
    4979  404.15  4979.3  404.65  4984.5  406.28  5006.6  406.97  5049.1  406.81
  5071.1  405.81    5123  408.13  5168.4  408.59  5222.5  410.74  5262.1  411.06
  5277.5  410.54  5392.6  412.25  5406.4  413.32  5421.9  412.47  5460.5  413.35
#Mann= 8 ,-1 , 0
    4464     .05       0  4783.6     .07       0  4811.5     .05       0
  4911.2      .1       0  4975.3     .05       0  4979.3      .1       0
    5123     .07       0  5277.5    .035       0
Bank Sta=4975.3,4979.3
XS Rating Curve= 0 ,0
Exp/Cntr=0.3,0.1

Type RM Length L Ch R = 1 ,77748   ,351,351,351
BEGIN DESCRIPTION:
BALDRIDGE CREEK 79.0
END DESCRIPTION:
XS GIS Cut Line= 3
        2500975.       13813525.        2500375.       13813175.
        2500025.       13813475.
#Sta/Elev= 30
  4301.8  412.75  4413.2  411.05  4571.8   408.8  4744.9  407.58  4828.1  407.46
    4857  406.86  4871.1  406.14  4908.4  406.43  4915.4  405.67  4967.1  405.97
  4982.8  404.37  4988.6  404.93  4993.5  403.81  4999.7  403.81  5001.6  401.39
  5001.8  400.89  5005.3  400.89  5005.6  401.39  5024.4  404.47  5081.5  405.91
  5095.8  405.23  5102.3  405.89    5110  405.05  5116.6  405.16  5183.4  408.71
  5223.1  409.52  5280.1  409.28  5363.1  410.94  5400.9  410.95  5457.4  412.16
#Mann= 8 ,-1 , 0
  4301.8     .05       0  4413.2     .07       0  4744.9     .05       0
    4857      .1       0  5001.6     .05       0  5005.6      .1       0
  5183.4     .07       0  5363.1    .035       0
Bank Sta=5001.6,5005.6
XS Rating Curve= 0 ,0
Exp/Cntr=0.3,0.1

Type RM Length L Ch R = 1 ,77397   ,503,503,503
BEGIN DESCRIPTION:
X18096
END DESCRIPTION:
XS GIS Cut Line= 3
      2501082.99     13813241.12       2500354.7     13813000.06
      2499641.84      13812610.3
#Sta/Elev= 30
  4118.2  413.95  4190.2     410  4216.7  411.09  4421.7  408.75  4604.8  407.58
  4731.3  406.02  4832.4  403.74  4940.8  403.74  5007.6  403.81  5013.3   401.2
  5019.8  400.68    5020  400.18  5023.8  400.68  5035.1  403.87  5051.3  404.45
  5107.6  404.79  5147.1  404.23  5169.9  402.46  5176.5   404.1  5214.4  404.82
  5220.1   401.7  5236.2  404.04    5258  405.03  5263.7  406.44  5272.5  406.17
  5329.5  410.18    5376  411.38  5580.2  419.39  5604.1   419.5  5697.8  422.86
#Mann= 11 ,-1 , 0
  4118.2     .05       0  4421.7     .07       0  4604.8    .035       0
  4731.3      .1       0  4940.8     .07       0  5019.8     .05       0
  5023.8     .07       0  5051.3     .12       0  5107.6      .1       0
    5376     .12       0  5604.1     .05       0
Bank Sta=5019.8,5023.8
XS Rating Curve= 0 ,0
Exp/Cntr=0.3,0.1

Type RM Length L Ch R = 1 ,76894   ,470,470,470
BEGIN DESCRIPTION:
BALDRIDGE CREEK 78.0
END DESCRIPTION:
XS GIS Cut Line= 3
      2501274.98     13813174.99        2500475.       13812675.
      2500074.98     13812374.99
#Sta/Elev= 30
    4061  422.72    4163  415.55  4263.2  411.98  4561.6  405.93  4576.9  406.82
  4619.4  405.34  4634.7  407.55  4656.8  406.87    4686  405.55    4729  406.62
  4815.7   405.9  4838.7   405.1  4847.9  403.17  4859.9  401.74  4874.7  404.16
    4933  403.97  4954.3  399.76  4960.2  401.14    4969  399.35  4975.5   402.1
  4988.2  397.32  4988.6  396.82  4993.5  397.32  4996.7  399.59  5017.9  401.83
  5051.2  402.04  5067.9  401.32  5217.9  404.95  5337.4  410.32  5504.4  417.51
#Mann= 7 ,-1 , 0
    4061     .05       0  4656.8     .07       0  4847.9     .12       0
  4988.2     .05       0  4993.5     .12       0  5051.2      .1       0
  5337.4     .12       0
Bank Sta=4988.2,4993.5
XS Rating Curve= 0 ,0
Exp/Cntr=0.3,0.1

Type RM Length L Ch R = 1 ,76424   ,462,462,462
BEGIN DESCRIPTION:
BALDRIDGE CREEK 77.0
END DESCRIPTION:
XS GIS Cut Line= 3
      2501375.02     13813025.02        2500575.       13812275.
      2500374.97     13812074.97
#Sta/Elev= 30
  3902.9  420.65    3910   421.1    3931  418.88  4009.2  416.63  4037.5  414.74
    4080  415.05    4101  413.43  4242.6  410.21    4292  410.13  4341.6  408.46
  4511.3  405.91    4814  403.32  4879.1  400.94  4899.3  401.05  4971.4  401.66
  4978.3  400.49  4992.4  400.88  4996.1   399.9  5003.1   399.9    5011  397.29
  5011.4  396.79  5016.3  397.29  5027.8  399.83    5054   401.3  5084.4  403.86
  5112.7  403.89  5169.2  408.15  5206.7  409.54    5233  410.93  5282.4   413.3
#Mann= 8 ,-1 , 0
  3902.9     .05       0    4814     .07       0  4899.3     .12       0
    5011     .05       0  5016.3     .12       0    5054     .07       0
  5206.7      .1       0    5233     .12       0
Bank Sta=5011,5016.3
XS Rating Curve= 0 ,0
Exp/Cntr=0.3,0.1

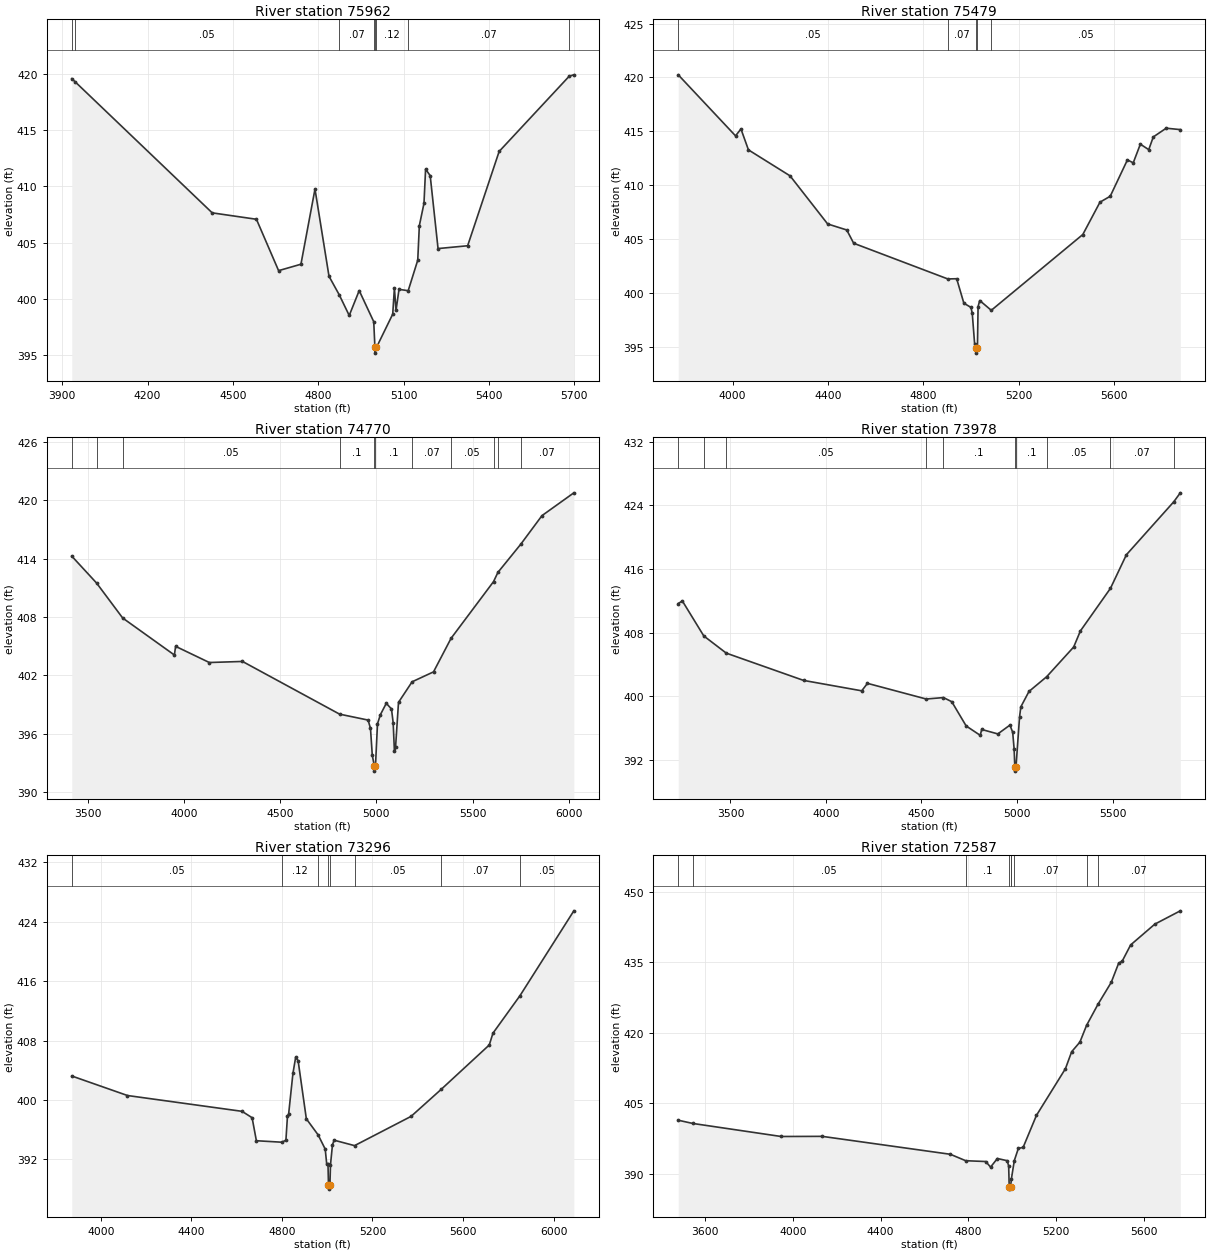
Type RM Length L Ch R = 1 ,75962   ,483,483,483
BEGIN DESCRIPTION:
BALDRIDGE CREEK 76.0
END DESCRIPTION:
XS GIS Cut Line= 3
       2501626.6     13812820.56        2500925.       13812025.
       2500303.4     13811692.25
#Sta/Elev= 30
  3933.3  419.56  3944.8  419.29  4427.2  407.65  4582.8  407.08  4660.7  402.52
  4739.3  403.09  4788.7  409.76    4838  402.02  4874.1  400.37  4909.1  398.54
  4944.2  400.75  4995.3  397.99  4999.5   395.7  4999.9   395.2  5004.8   395.7
  5062.1  398.66    5068  400.97  5073.7  398.99  5084.2  400.86  5116.5  400.74
  5150.1  403.45  5155.7  406.51    5172  408.49  5177.7  411.53  5193.9  410.95
  5221.5  404.48  5325.6  404.73  5436.4   413.1  5682.9  419.78  5699.1   419.9
#Mann= 8 ,-1 , 0
  3933.3     .07       0  3944.8     .05       0  4874.1     .07       0
  4995.3     .12       0  4999.5     .05       0  5004.8     .12       0
  5116.5     .07       0  5682.9     .12       0
Bank Sta=4999.5,5004.8
XS Rating Curve= 0 ,0
Exp/Cntr=0.3,0.1

Type RM Length L Ch R = 1 ,75479   ,709,709,709
BEGIN DESCRIPTION:
X18095
END DESCRIPTION:
XS GIS Cut Line= 3
      2501852.27     13812756.18      2501323.48     13811785.14
      2500391.16     13811419.89
#Sta/Elev= 30
  3771.6  420.24  4012.1  414.58  4034.8  415.22  4066.2  413.28  4240.9  410.87
  4398.6  406.41  4478.9  405.85  4507.8  404.62  4902.9  401.31  4940.1  401.33
  4970.3  399.06  5000.1  398.67  5005.5  398.12  5015.3  395.32  5021.8  394.93
  5022.3  394.43  5027.2  394.93  5029.9  398.74  5036.8  399.31  5085.3   398.4
  5469.4  405.43  5541.5  408.43  5584.5  408.98  5656.6  412.35  5681.1  412.08
  5710.9  413.81  5746.1   413.3  5765.2  414.48  5819.4  415.29  5878.6  415.16
#Mann= 5 ,-1 , 0
  3771.6     .05       0  4902.9     .07       0  5021.8     .05       0
  5027.2     .07       0  5085.3     .05       0
Bank Sta=5021.8,5027.2
XS Rating Curve= 0 ,0
Exp/Cntr=0.3,0.1

Type RM Length L Ch R = 1 ,74770   ,792,792,792
BEGIN DESCRIPTION:
X18094
END DESCRIPTION:
XS GIS Cut Line= 3
      2502217.67     13812419.74      2501583.08     13811429.39
      2500371.66     13810660.23
#Sta/Elev= 30
  3415.8  414.25  3544.8  411.49  3680.5   407.9  3949.5   404.1  3955.9  404.99
  4131.2  403.33  4303.7  403.44  4808.6  398.03    4957  397.42  4969.4  396.56
  4978.7  393.81  4989.7  392.68  4990.2  392.18  4995.2  392.68  5005.8  397.04
    5021  397.98  5051.5  399.14  5078.6  398.56  5087.3  397.16  5093.9  394.21
  5099.8  394.65  5115.1  399.24  5185.8  401.35  5297.2  402.37  5388.3  405.81
  5609.5  411.64    5632  412.58  5750.4  415.46  5861.3  418.41    6027  420.75
#Mann= 11 ,-1 , 0
  3415.8     .05       0  3544.8     .07       0  3680.5     .05       0
  4808.6      .1       0  4989.7     .05       0  4995.2      .1       0
  5185.8     .07       0  5388.3     .05       0  5609.5     .07       0
    5632     .05       0  5750.4     .07       0
Bank Sta=4989.7,4995.2
XS Rating Curve= 0 ,0
Exp/Cntr=0.3,0.1

Type RM Length L Ch R = 1 ,73978   ,682,682,682
BEGIN DESCRIPTION:
BALDRIDGE CREEK 75.0
END DESCRIPTION:
XS GIS Cut Line= 3
      2502294.55     13812285.06       2501727.3     13810862.13
      2500910.06     13810131.42
#Sta/Elev= 30
  3226.8  411.67  3248.4  411.99  3360.6  407.59  3478.2  405.43  3882.7     402
  4187.3  400.69  4217.3  401.63  4524.6  399.66  4615.2  399.84  4658.6  399.32
    4734  396.27  4807.7  395.09  4815.2  395.83  4899.7  395.27  4963.2  396.38
  4977.5  395.47    4985  393.38  4988.7  391.09  4989.2  390.59  4994.7  391.09
  5013.4   397.4  5020.1  398.67  5062.7  400.61  5155.2  402.46  5296.8   406.2
  5331.9  408.22  5489.3  413.58  5572.6   417.8  5820.9  424.47  5854.9  425.59
#Mann= 10 ,-1 , 0
  3226.8     .05       0  3360.6     .07       0  3478.2     .05       0
  4524.6     .07       0  4615.2      .1       0  4988.7     .05       0
  4994.7      .1       0  5155.2     .05       0  5489.3     .07       0
  5820.9     .05       0
Bank Sta=4988.7,4994.7
XS Rating Curve= 0 ,0
Exp/Cntr=0.3,0.1

Type RM Length L Ch R = 1 ,73296   ,709,709,709
BEGIN DESCRIPTION:
BALDRIDGE CREEK 74.0
END DESCRIPTION:
XS GIS Cut Line= 3
      2502544.56     13811823.62        2502125.       13810775.
      2501611.94     13809814.14
#Sta/Elev= 30
  3871.2  403.23  4117.4   400.6  4623.7  398.47  4668.1  397.61    4687  394.51
  4799.6  394.31  4817.5  394.58  4824.3  397.78  4829.7  398.15  4848.5  403.57
  4860.6  405.75  4871.4   405.3  4907.8  397.46  4959.8   395.3  4991.2  393.38
    4998  391.31  5003.5  391.31  5005.7  388.49  5006.2  387.99  5011.9  388.49
  5014.5  391.27  5023.3  393.98  5030.7  394.58  5120.9  393.85  5370.6  397.79
  5503.7  401.43  5716.2  407.41  5732.5     409  5851.9  414.05  6089.9  425.48
#Mann= 8 ,-1 , 0
  3871.2     .05       0  4799.6     .12       0  4959.8      .1       0
  5005.7     .05       0  5011.9      .1       0  5120.9     .05       0
  5503.7     .07       0  5851.9     .05       0
Bank Sta=5005.7,5011.9
XS Rating Curve= 0 ,0
Exp/Cntr=0.3,0.1

Type RM Length L Ch R = 1 ,72587   ,582,582,582
BEGIN DESCRIPTION:
X18093
END DESCRIPTION:
XS GIS Cut Line= 3
      2502727.24     13811660.18      2502506.09     13810487.15
      2501996.49     13809516.03
#Sta/Elev= 30
  3477.2  401.42  3543.9  400.73  3946.8  397.96  4133.7  397.99  4718.5  394.18
  4788.7  392.81    4880  392.64    4902  391.45  4933.1  393.28  4978.2  392.81
  4984.6  391.66  4987.1  387.27  4987.6  386.77  4993.4  387.27    4997  388.95
  5010.4  392.85  5028.7  395.42  5050.7  395.66  5111.3  402.45  5243.6  412.38
  5271.9  415.98  5309.7  418.04  5339.7  421.56  5391.6  426.04  5452.5  430.73
  5486.4  434.81  5502.6  435.25    5541  438.69  5651.3  443.11  5767.6  445.94
#Mann= 9 ,-1 , 0
  3477.2     .07       0  3543.9     .05       0  4788.7      .1       0
  4987.1     .05       0  4993.4      .1       0    4997     .05       0
  5010.4     .07       0  5339.7     .05       0  5391.6     .07       0
Bank Sta=4987.1,4993.4
XS Rating Curve= 0 ,0
Exp/Cntr=0.3,0.1

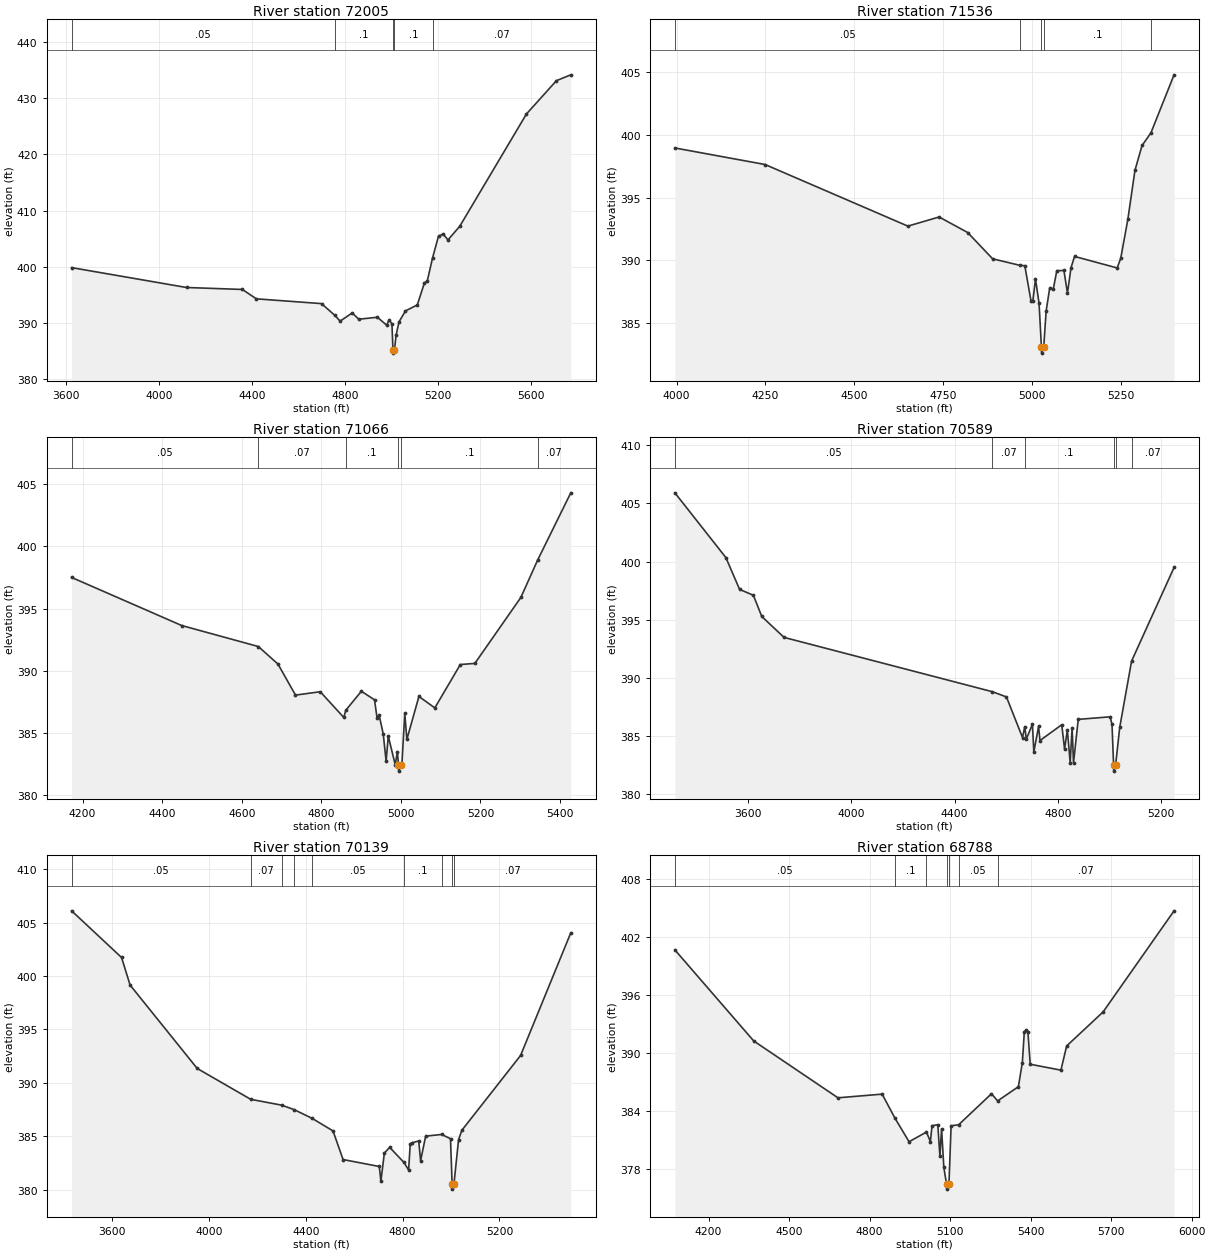
Type RM Length L Ch R = 1 ,72005   ,469,469,469
BEGIN DESCRIPTION:
BALDRIDGE CREEK 73.0
END DESCRIPTION:
XS GIS Cut Line= 3
      2502784.92     13811448.63        2502825.       13810075.
      2502698.39     13809314.18
#Sta/Elev= 30
  3625.7  399.83  4119.5  396.29  4359.6  395.94  4419.7  394.27  4699.8  393.42
  4757.2  391.32  4779.8   390.3  4831.7  391.76  4859.9  390.64  4939.9  390.99
  4979.9  389.58  4989.9  390.53  5002.5  389.82  5006.9   385.1  5007.4   384.6
  5013.3   385.1  5020.2  387.78  5032.9  390.17  5060.7  392.12  5111.4  393.18
  5141.8  397.07  5154.6  397.49    5177  401.56  5202.7  405.44  5222.9  405.82
  5243.2  404.76  5293.9  407.19  5580.7   427.2  5709.5  433.13  5771.2  434.17
#Mann= 5 ,-1 , 0
  3625.7     .05       0  4757.2      .1       0  5006.9     .05       0
  5013.3      .1       0    5177     .07       0
Bank Sta=5006.9,5013.3
XS Rating Curve= 0 ,0
Exp/Cntr=0.3,0.1

Type RM Length L Ch R = 1 ,71536   ,470,470,470
BEGIN DESCRIPTION:
BALDRIDGE CREEK 72.0
END DESCRIPTION:
XS GIS Cut Line= 3
        2503125.       13811275.        2503225.       13810275.
        2503225.     13809874.99
#Sta/Elev= 30
  3995.1  398.97  4248.9  397.65  4650.9  392.73  4738.8  393.46  4819.2  392.22
  4889.5  390.12  4966.2   389.6    4980  389.57  4997.6  386.74  5002.6  386.74
  5010.1  388.51  5020.1  386.57  5026.8  383.09  5027.3  382.59  5033.3  383.09
  5040.1  385.96  5050.1  387.79  5060.1   387.7  5070.1  389.17  5090.1  389.19
  5100.1  387.39  5110.1  389.41  5120.1  390.31  5240.1  389.39  5250.1  390.17
  5270.1  393.28  5290.1  397.19  5310.1  399.17  5334.9  400.17  5400.1  404.81
#Mann= 5 ,-1 , 0
  3995.1     .05       0  4966.2      .1       0  5026.8     .05       0
  5033.3      .1       0  5334.9     .07       0
Bank Sta=5026.8,5033.3
XS Rating Curve= 0 ,0
Exp/Cntr=0.3,0.1

Type RM Length L Ch R = 1 ,71066   ,477,477,477
BEGIN DESCRIPTION:
BALDRIDGE CREEK 71.0
END DESCRIPTION:
XS GIS Cut Line= 3
      2503274.99     13811025.02        2503625.       13810275.
      2503474.99     13809874.98
#Sta/Elev= 30
  4172.4  397.51  4449.1  393.64  4641.7  391.95  4691.1  390.54  4735.2  388.04
  4797.5  388.31  4856.6  386.24  4861.7  386.82  4900.8  388.35  4933.9  387.66
  4940.2  386.21  4945.7   386.4  4955.9  384.89    4963  382.73  4968.5  384.73
  4985.9  382.44  4991.4  383.48  4994.1  382.42  4994.6  381.92  5000.6  382.42
  5002.7  382.42  5009.9  386.57  5015.2  384.47  5045.5  387.93  5085.5  387.01
  5149.6   390.5  5186.1  390.59  5301.8   395.9    5344  398.91  5427.3  404.32
#Mann= 6 ,-1 , 0
  4172.4     .05       0  4641.7     .07       0  4861.7      .1       0
  4994.1     .05       0  5000.6      .1       0    5344     .07       0
Bank Sta=4994.1,5000.6
XS Rating Curve= 0 ,0
Exp/Cntr=0.3,0.1

Type RM Length L Ch R = 1 ,70589   ,450,450,450
BEGIN DESCRIPTION:
BALDRIDGE CREEK 70.0
END DESCRIPTION:
XS GIS Cut Line= 3
        2504675.     13811624.99        2504025.       13810075.
        2504025.     13809824.96
#Sta/Elev= 30
  3318.4  405.91  3515.7  400.34  3568.6  397.61    3622   397.1  3654.5  395.28
  3740.5  393.48  4546.3  388.81  4600.9  388.36    4663  384.87  4671.8  385.81
  4677.6  384.73  4701.4  386.01  4706.8  383.63  4725.2  385.82  4730.6  384.61
  4814.8  385.97  4825.7  383.88  4836.5  385.53  4847.4  382.72  4854.9   385.7
  4860.3  382.69  4878.6  386.43  5001.7  386.65  5009.2  386.01  5015.4  382.48
  5015.9  381.98    5023  382.48  5039.2  385.76  5084.9  391.44  5249.2  399.49
#Mann= 6 ,-1 , 0
  3318.4     .05       0  4546.3     .07       0  4671.8      .1       0
  5015.4     .05       0    5023      .1       0  5084.9     .07       0
Bank Sta=5015.4,5023
XS Rating Curve= 0 ,0
Exp/Cntr=0.3,0.1

Type RM Length L Ch R = 1 ,70139   ,1351,1351,1351
BEGIN DESCRIPTION:
BALDRIDGE CREEK 69.0
END DESCRIPTION:
XS GIS Cut Line= 3
      2505575.02     13811125.01        2504375.       13810125.
      2504074.98     13809724.98
#Sta/Elev= 30
  3432.7   406.1    3639  401.73  3674.2  399.15  3951.5  391.34  4172.5  388.45
    4301   387.9  4351.3  387.49  4426.8  386.66  4512.5  385.49  4554.1  382.81
  4703.8  382.16  4710.3  380.77  4724.7  383.42  4746.8  383.95  4805.5  382.54
  4824.9  381.83  4831.4  384.22  4838.6  384.38  4866.6  384.55  4874.4   382.7
  4895.2     385  4961.2  385.16  4997.9  384.76  5004.5  380.54    5005  380.04
  5012.2  380.54  5031.2  384.67  5044.8  385.55  5287.5  392.56  5494.8  404.04
#Mann= 9 ,-1 , 0
  3432.7     .05       0  4172.5     .07       0    4301     .05       0
  4351.3     .07       0  4426.8     .05       0  4805.5      .1       0
  4961.2     .07       0  5004.5     .05       0  5012.2     .07       0
Bank Sta=5004.5,5012.2
XS Rating Curve= 0 ,0
Exp/Cntr=0.3,0.1

Type RM Length L Ch R = 1 ,68788   ,457,457,457
BEGIN DESCRIPTION:
BALDRIDGE CREEK 68.0
END DESCRIPTION:
XS GIS Cut Line= 3
      2505575.02     13810775.03        2505025.       13810025.
      2504275.04     13809475.03
#Sta/Elev= 30
  4074.3   400.7    4368  391.29    4682  385.41  4846.6  385.79  4893.5  383.35
  4946.9  380.87  5011.8  381.87  5026.4  380.89  5032.6  382.53    5054  382.63
  5061.9  379.37  5068.1  382.21  5076.5  378.22  5086.7  376.47  5087.2  375.97
  5095.6  376.47  5103.6  382.52  5131.5  382.62  5254.1  385.83  5276.9  385.09
  5354.4  386.56  5369.1  389.06  5376.4  392.23  5383.7  392.45  5389.9  392.21
  5398.4  388.88  5512.8  388.27  5534.2  390.77  5670.1  394.29  5934.4  404.74
#Mann= 7 ,-1 , 0
  4074.3     .05       0  4893.5      .1       0  5011.8     .07       0
  5086.7     .05       0  5095.6     .07       0  5131.5     .05       0
  5276.9     .07       0
Bank Sta=5086.7,5095.6
XS Rating Curve= 0 ,0
Exp/Cntr=0.3,0.1