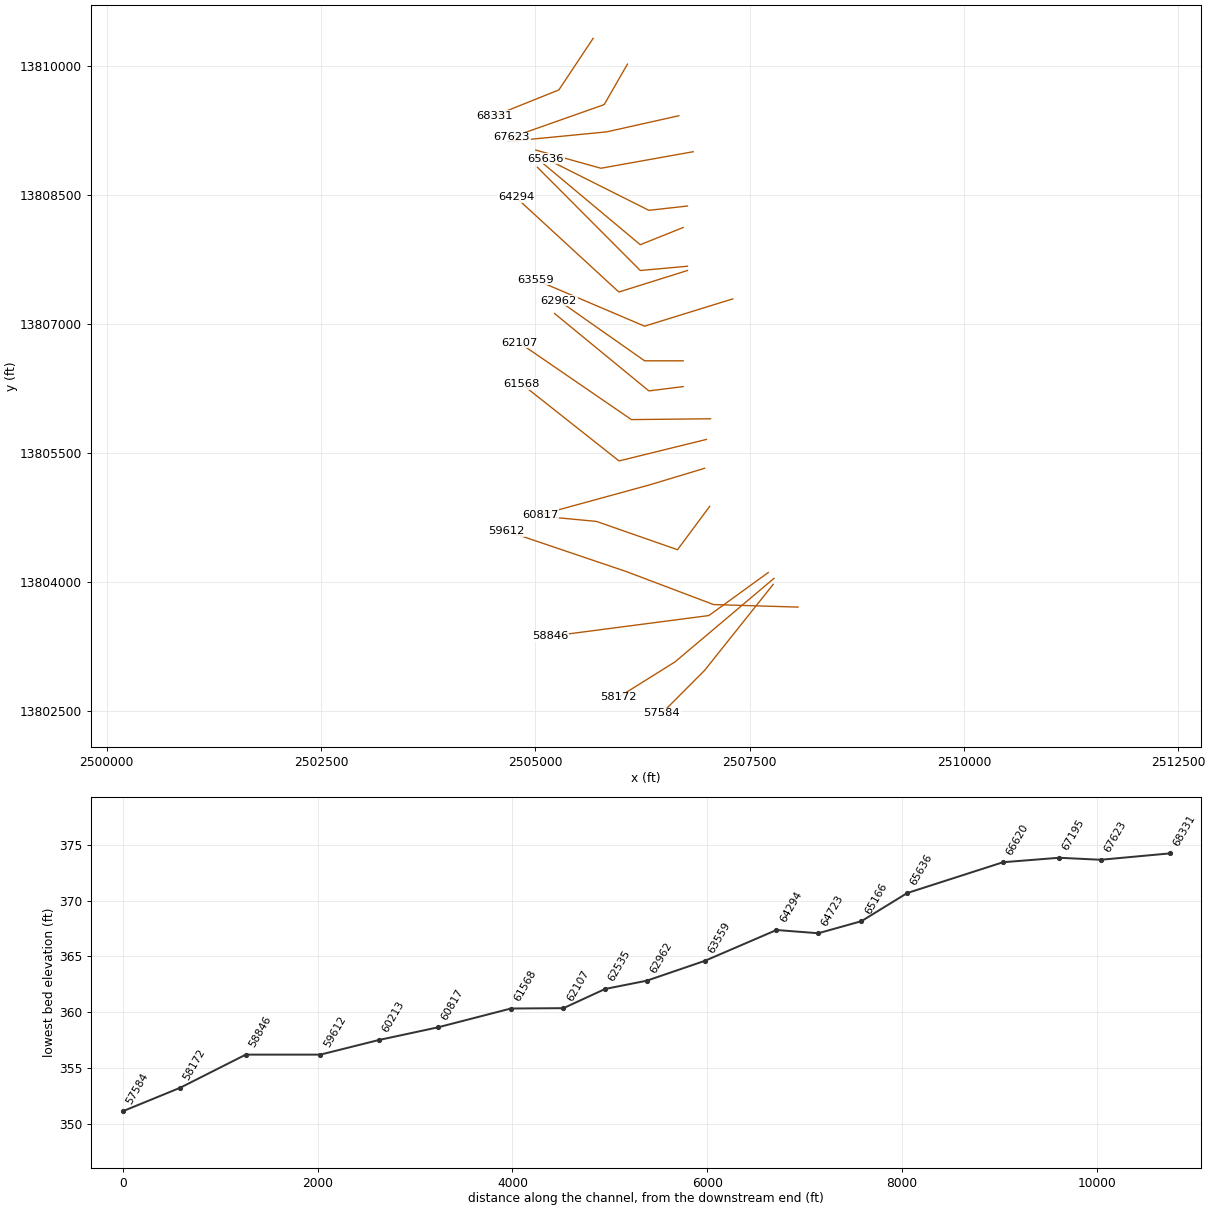
HEC-RAS study BALDRIDGE CREEK.prj: BALDRIDGE CREEK Base Level Engineering

--- BALDRIDGE CREEK.g01 (geometry) --- (continued)

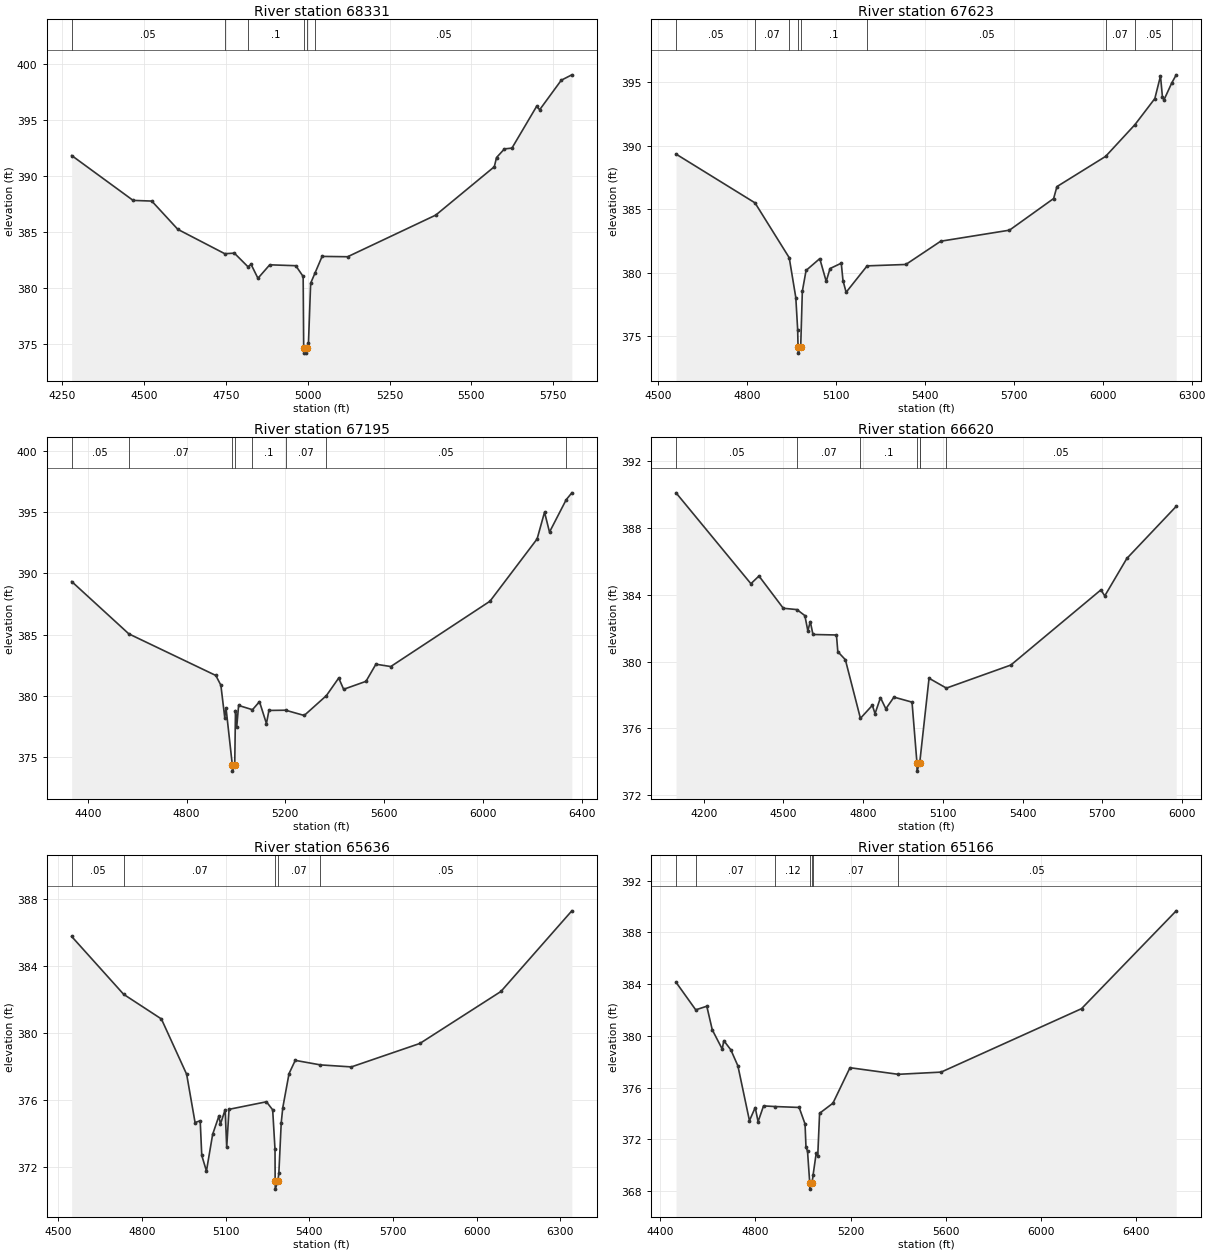
Type RM Length L Ch R = 1 ,68331   ,708,708,708
BEGIN DESCRIPTION:
BALDRIDGE CREEK 67.0
END DESCRIPTION:
XS GIS Cut Line= 3
      2505675.01     13810325.01        2505275.       13809725.
        2504525.       13809425.
#Sta/Elev= 30
  4278.4  391.84  4466.2  387.84  4523.3  387.78  4602.9  385.26  4746.4  383.09
  4775.7  383.14  4817.2  381.93  4826.8  382.14  4847.8   380.9  4883.8   382.1
  4963.5  382.02    4986  381.06  4987.6  374.73  4988.1  374.23    4996  374.23
  4996.5  374.73  5002.2  375.11  5008.9  380.46  5022.1  381.36  5043.9  382.85
    5122  382.82  5391.3  386.53  5570.3  390.84  5577.1  391.66  5601.3  392.43
  5624.2   392.5  5699.6  396.22    5709  395.92    5775  398.55  5807.3  399.03
#Mann= 6 ,-1 , 0
  4278.4     .05       0  4746.4     .07       0  4817.2      .1       0
  4987.6     .05       0  4996.5      .1       0  5022.1     .05       0
Bank Sta=4987.6,4996.5
XS Rating Curve= 0 ,0
Exp/Cntr=0.3,0.1

Type RM Length L Ch R = 1 ,67623   ,428,428,428
BEGIN DESCRIPTION:
BALDRIDGE CREEK 66.0
END DESCRIPTION:
XS GIS Cut Line= 3
      2506074.99     13810024.99      2505803.93     13809554.53
        2504725.       13809175.
#Sta/Elev= 30
  4561.3  389.33  4827.6  385.49    4943  381.17  4965.2  378.03  4971.5  375.48
  4972.7  374.16  4973.2  373.66  4981.7  374.16  4987.2  378.53  4999.8  380.17
    5046   381.1  5067.7  379.31  5080.6  380.32  5118.5  380.74  5124.3  379.37
  5134.9  378.45  5205.7  380.53  5336.3  380.64  5453.8  382.47  5685.7  383.34
  5834.6  385.83  5845.8  386.77    6010  389.15  6108.9  391.65  6175.9   393.7
    6195  395.48  6201.5  393.84  6206.8   393.6  6233.2  394.94    6248  395.57
#Mann= 9 ,-1 , 0
  4561.3     .05       0  4827.6     .07       0    4943      .1       0
  4972.7     .05       0  4981.7      .1       0  5205.7     .05       0
    6010     .07       0  6108.9     .05       0  6233.2     .07       0
Bank Sta=4972.7,4981.7
XS Rating Curve= 0 ,0
Exp/Cntr=0.3,0.1

Type RM Length L Ch R = 1 ,67195   ,575,575,575
BEGIN DESCRIPTION:
BALDRIDGE CREEK 65.0
END DESCRIPTION:
XS GIS Cut Line= 3
      2506674.96     13809424.99      2505832.77     13809237.24
      2504674.96       13809125.
#Sta/Elev= 30
  4334.6  389.34  4566.2  385.06  4918.5  381.66    4939  380.86  4954.7  378.21
  4959.8  379.01  4985.4  374.34  4985.9  373.84  4995.1  374.34  4998.2  378.79
  5003.3  377.48  5010.8  379.21    5067  378.86  5095.4  379.52  5123.5  377.73
  5133.7   378.8  5201.1  378.82  5276.6  378.39  5366.3  380.01  5416.3  381.45
  5436.3  380.53  5526.8  381.18    5567  382.58  5627.2  382.39  6029.1  387.73
    6220  392.82  6250.1  395.01  6270.2  393.38  6337.9  396.03  6360.7  396.59
#Mann= 8 ,-1 , 0
  4334.6     .05       0  4566.2     .07       0  4985.4     .05       0
  4995.1     .07       0    5067      .1       0  5201.1     .07       0
  5366.3     .05       0  6337.9     .07       0
Bank Sta=4985.4,4995.1
XS Rating Curve= 0 ,0
Exp/Cntr=0.3,0.1

Type RM Length L Ch R = 1 ,66620   ,984,984,984
BEGIN DESCRIPTION:
X18092
END DESCRIPTION:
XS GIS Cut Line= 3
      2506842.28     13809006.48      2505765.47      13808814.2
      2505005.92     13809025.72
#Sta/Elev= 30
  4095.9   390.1  4377.6  384.66    4408  385.12  4499.5  383.19  4550.9  383.11
  4580.7  382.75  4591.9  381.84  4601.1  382.39  4611.2  381.62  4699.6  381.59
  4704.7  380.59  4733.1  380.11  4789.8   376.6  4834.7  377.38  4844.8  376.88
  4865.2  377.84  4885.5  377.17    4916  377.87    4984  377.57  5002.5  373.94
    5003  373.44  5012.3  373.94  5013.8  374.06    5048     379  5113.3  378.41
  5355.8  379.79  5694.8  384.29  5709.3  383.93  5792.3  386.17  5978.2  389.29
#Mann= 7 ,-1 , 0
  4095.9     .05       0  4550.9     .07       0  4789.8      .1       0
  5002.5     .05       0  5012.3      .1       0  5013.8     .07       0
  5113.3     .05       0
Bank Sta=5002.5,5012.3
XS Rating Curve= 0 ,0
Exp/Cntr=0.3,0.1

Type RM Length L Ch R = 1 ,65636   ,470,470,470
BEGIN DESCRIPTION:
BALDRIDGE CREEK 64.0
END DESCRIPTION:
XS GIS Cut Line= 3
      2506774.97       13808375.        2506325.       13808325.
      2505124.99     13808925.01
#Sta/Elev= 30
  4547.4  385.75  4733.9   382.3  4869.3  380.83  4959.9  377.53  4990.1  374.65
  5008.5  374.76  5014.1  372.69  5030.9  371.76  5053.2  373.95  5075.6  375.04
  5081.2  374.56    5098  375.42  5103.6  373.17  5111.9  375.44  5246.1  375.89
  5268.5  375.41  5276.9  373.05  5277.4  371.18  5277.9  370.68  5287.4  371.18
  5290.8  371.67  5299.2  374.64  5304.8  375.54  5327.2  377.57  5349.5  378.36
    5440  378.09  5550.8  377.97  5796.7  379.37  6087.4  382.47  6341.8  387.28
#Mann= 5 ,-1 , 0
  4547.4     .05       0  4733.9     .07       0  5277.4     .05       0
  5287.4     .07       0    5440     .05       0
Bank Sta=5277.4,5287.4
XS Rating Curve= 0 ,0
Exp/Cntr=0.3,0.1

Type RM Length L Ch R = 1 ,65166   ,443,443,443
BEGIN DESCRIPTION:
BALDRIDGE CREEK 63.0
END DESCRIPTION:
XS GIS Cut Line= 3
      2506724.99       13808125.        2506225.       13807925.
      2505024.96     13808925.03
#Sta/Elev= 30
  4466.8  384.14  4549.5  382.01    4596  382.29  4618.9  380.47  4660.7  378.98
  4667.4  379.63    4697  378.92  4726.6  377.68  4775.1  373.45  4799.3  374.46
  4811.4  373.37  4834.3  374.59  4883.5  374.54  4983.8  374.47  5008.6  373.19
  5012.5  371.41    5019  371.09  5028.2  368.66  5028.7  368.16  5038.3  368.66
  5042.2  369.23  5055.4  370.93  5061.9  370.72  5069.7  374.02  5125.7   374.8
  5197.3  377.54  5399.8  377.03    5580   377.2  6169.7   382.1  6567.4  389.66
#Mann= 7 ,-1 , 0
  4466.8     .05       0  4549.5     .07       0  4883.5     .12       0
  5028.2     .05       0  5038.3     .12       0  5042.2     .07       0
  5399.8     .05       0
Bank Sta=5028.2,5038.3
XS Rating Curve= 0 ,0
Exp/Cntr=0.3,0.1

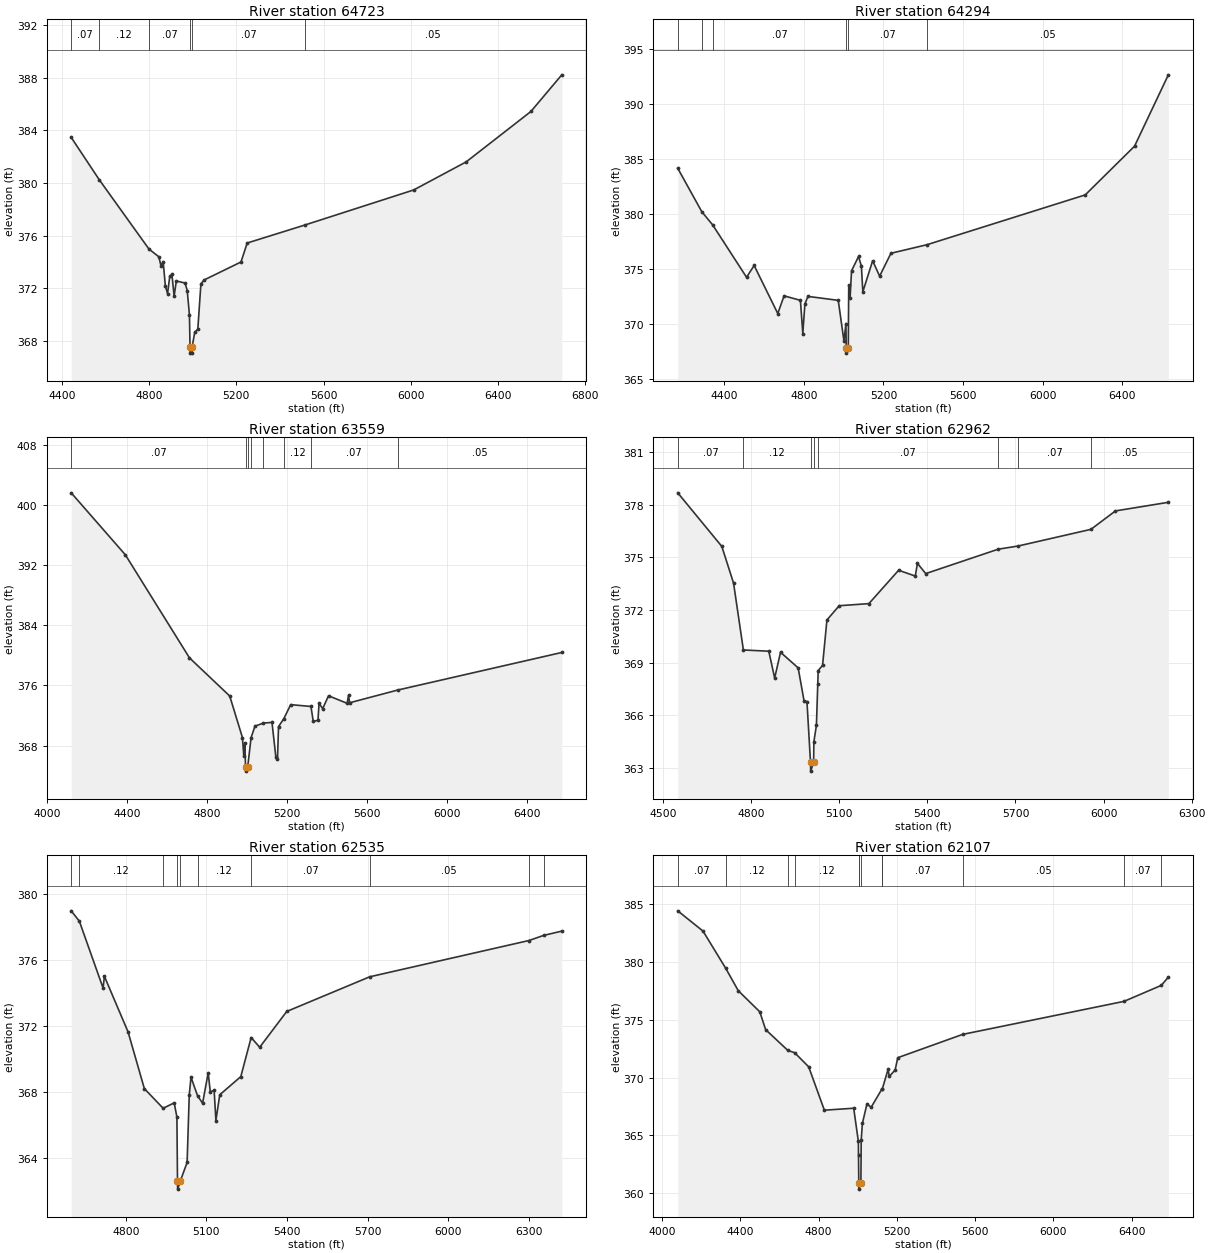
Type RM Length L Ch R = 1 ,64723   ,429,429,429
BEGIN DESCRIPTION:
BALDRIDGE CREEK 62.0
END DESCRIPTION:
XS GIS Cut Line= 3
      2506774.96       13807675.        2506225.       13807625.
      2505024.99     13808825.01
#Sta/Elev= 30
    4443  383.46    4571  380.26  4799.6  374.98  4844.6   374.4  4854.7  373.71
  4864.7  374.03  4874.7  372.18  4884.8   371.6  4894.8   372.9  4904.9  373.06
  4914.9   371.4  4924.9  372.56  4965.1   372.4  4975.1  371.82  4985.2  369.97
  4987.7  367.58  4988.2  367.08  4997.3  367.08  4997.8  367.58  5009.4  368.66
  5023.5  368.89  5037.7  372.33  5051.8  372.63  5221.5     374  5249.8  375.44
  5513.1   376.8  6013.5  379.47  6253.9   381.6  6550.9  385.43  6692.3  388.21
#Mann= 6 ,-1 , 0
    4443     .07       0    4571     .12       0  4799.6     .07       0
  4987.7     .05       0  4997.8     .07       0  5513.1     .05       0
Bank Sta=4987.7,4997.8
XS Rating Curve= 0 ,0
Exp/Cntr=0.3,0.1

Type RM Length L Ch R = 1 ,64294   ,735,735,735
BEGIN DESCRIPTION:
BALDRIDGE CREEK 61.0
END DESCRIPTION:
XS GIS Cut Line= 3
      2506775.03     13807625.01        2505975.       13807375.
      2504774.98     13808475.02
#Sta/Elev= 30
  4166.1  384.18  4287.7  380.21  4341.7  379.03  4511.9  374.27  4550.1  375.34
    4669  370.97  4700.5  372.58  4782.7  372.17  4794.7  369.15  4805.2  371.83
  4820.4  372.53  4972.9  372.17  5001.7  368.45  5011.4  370.06    5013  367.87
  5013.5  367.37  5023.3  367.87  5025.6  373.56  5032.3  372.35  5039.7  374.85
  5074.9  376.16  5089.1  375.29  5096.5  372.95  5145.8  375.77  5180.9  374.37
  5237.7  376.45  5418.8  377.23  6214.4  381.76  6462.3  386.19  6632.2  392.68
#Mann= 6 ,-1 , 0
  4166.1     .07       0  4287.7     .12       0  4341.7     .07       0
    5013     .05       0  5023.3     .07       0  5418.8     .05       0
Bank Sta=5013,5023.3
XS Rating Curve= 0 ,0
Exp/Cntr=0.3,0.1

Type RM Length L Ch R = 1 ,63559   ,597,597,597
BEGIN DESCRIPTION:
X18091
END DESCRIPTION:
XS GIS Cut Line= 3
      2507303.82     13807295.08      2506275.05     13806977.79
      2505005.93     13807516.21
#Sta/Elev= 30
  4120.8  401.62  4391.7  393.38  4712.8  379.67  4914.1   374.6  4977.7  369.08
  4984.6  366.63  4989.8  368.37  4993.4  365.11  4993.9  364.61  5003.9  365.11
  5021.1  369.07  5040.5  370.59  5082.9     371  5125.7  371.09  5145.1  366.45
  5153.2  366.22  5158.4  370.53    5185  371.59  5219.2  373.45  5320.7  373.21
  5332.1  371.23  5355.8  371.37  5361.2  373.62  5379.5  372.93  5408.6  374.63
  5501.6  373.63  5508.7  374.69  5514.1   373.7  5754.6  375.39    6576  380.39
#Mann= 8 ,-1 , 0
  4120.8     .07       0  4993.4     .05       0  5003.9     .07       0
  5021.1     .12       0  5082.9     .07       0    5185     .12       0
  5320.7     .07       0  5754.6     .05       0
Bank Sta=4993.4,5003.9
XS Rating Curve= 0 ,0
Exp/Cntr=0.3,0.1

Type RM Length L Ch R = 1 ,62962   ,427,427,427
BEGIN DESCRIPTION:
BALDRIDGE CREEK 60.0
END DESCRIPTION:
XS GIS Cut Line= 3
      2506724.97       13806575.        2506275.       13806575.
      2505275.02     13807274.99
#Sta/Elev= 30
    4550  378.68    4700  375.63    4740  373.54  4773.5  369.73    4860  369.66
    4880  368.13    4900   369.6    4960  368.71    4980  366.84    4990  366.79
  5002.1  363.33  5002.6  362.83  5012.7  363.33  5013.5   364.5  5022.2  365.44
  5026.8  367.79  5028.3  368.56  5043.1  368.85    5058  371.44  5099.8  372.25
  5200.9  372.37  5302.1  374.27  5358.8  373.94  5366.2  374.66  5394.5  374.08
  5641.3  375.47  5708.9  375.65    5957   376.6  6040.6  377.65  6220.6  378.14
#Mann= 8 ,-1 , 0
    4550     .07       0  4773.5     .12       0  5002.1     .05       0
  5012.7     .12       0  5026.8     .07       0  5641.3     .05       0
  5708.9     .07       0    5957     .05       0
Bank Sta=5002.1,5012.7
XS Rating Curve= 0 ,0
Exp/Cntr=0.3,0.1

Type RM Length L Ch R = 1 ,62535   ,428,428,428
BEGIN DESCRIPTION:
BALDRIDGE CREEK 59.0
END DESCRIPTION:
XS GIS Cut Line= 3
      2506725.04       13806275.        2506325.       13806225.
      2505225.01     13807124.99
#Sta/Elev= 30
  4597.3  378.96  4627.7  378.33  4715.8  374.28  4720.8  374.99    4809  371.61
  4869.4  368.18  4939.3  366.99  4980.3  367.32  4990.4  366.46  4992.6  362.59
  4993.1  362.09  5003.3  362.59  5028.4  363.71  5036.3  367.79  5042.8  368.88
  5067.1  367.75  5085.9   367.3  5106.7  369.13  5114.6  367.99  5128.9  368.08
  5135.4  366.25  5149.8  367.81    5228  368.91  5266.5  371.28  5298.3  370.69
  5398.8  372.86  5707.2  374.96  6299.5  377.16  6354.2  377.47  6421.7  377.73
#Mann= 10 ,-1 , 0
  4597.3     .07       0  4627.7     .12       0  4939.3     .07       0
  4992.6     .05       0  5003.3     .07       0  5067.1     .12       0
  5266.5     .07       0  5707.2     .05       0  6299.5     .07       0
  6354.2     .05       0
Bank Sta=4992.6,5003.3
XS Rating Curve= 0 ,0
Exp/Cntr=0.3,0.1

Type RM Length L Ch R = 1 ,62107   ,539,539,539
BEGIN DESCRIPTION:
X18090
END DESCRIPTION:
XS GIS Cut Line= 3
      2507044.18     13805900.94      2506121.22     13805891.33
      2504813.62     13806785.49
#Sta/Elev= 30
  4080.6  384.38  4209.8  382.63  4325.5  379.43  4389.8  377.49  4499.8  375.67
  4529.8  374.13  4643.7  372.33    4678  372.14  4749.8  370.92  4829.8  367.18
  4979.8  367.35  5003.6  364.48  5004.3  363.33  5005.8  360.87  5006.3  360.37
  5016.5  360.87  5018.1  364.58  5024.1  366.04  5047.5  367.72  5068.9  367.43
  5122.8  368.97  5125.2  368.97  5155.6  370.71  5161.6  370.09  5191.5  370.65
    5205  371.71  5536.6  373.72  6361.3  376.57  6551.8  377.95  6587.7  378.66
#Mann= 12 ,-1 , 0
  4080.6     .07       0  4325.5     .12       0  4643.7     .07       0
    4678     .12       0  5004.3     .07       0  5005.8     .05       0
  5016.5     .07       0  5122.8     .12       0  5125.2     .07       0
  5536.6     .05       0  6361.3     .07       0  6551.8     .05       0
Bank Sta=5005.8,5016.5
XS Rating Curve= 0 ,0
Exp/Cntr=0.3,0.1

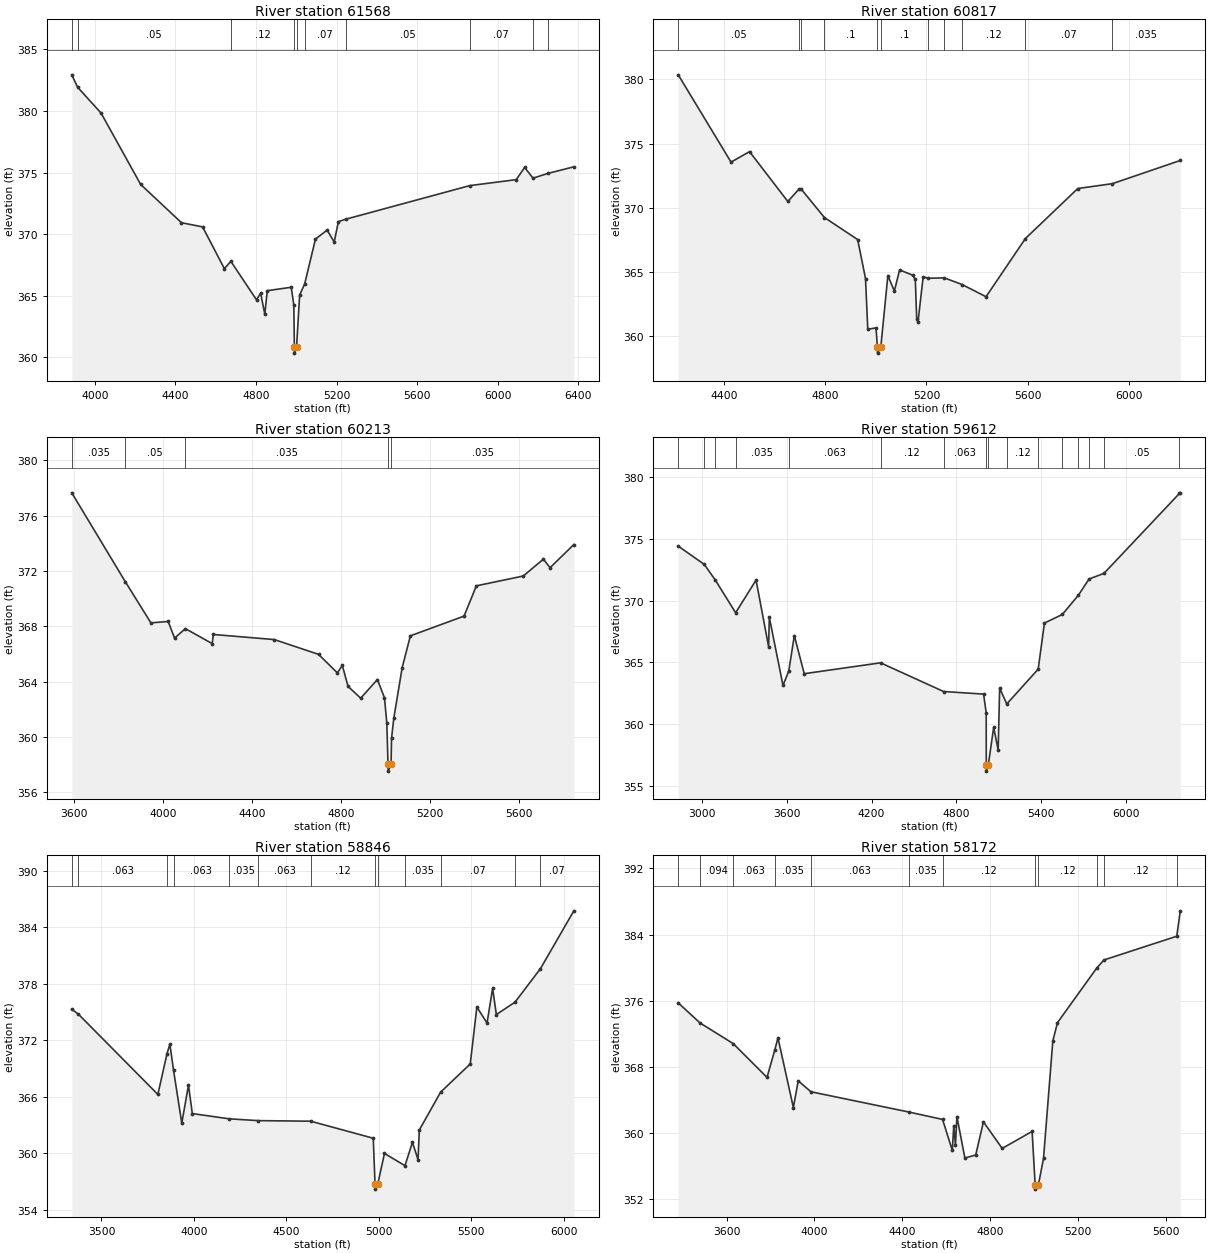
Type RM Length L Ch R = 1 ,61568   ,751,751,751
BEGIN DESCRIPTION:
BALDRIDGE CREEK 58.0
END DESCRIPTION:
XS GIS Cut Line= 3
      2506996.16     13805660.58      2505976.99      13805410.6
      2504842.48     13806304.75
#Sta/Elev= 30
  3884.8  382.94    3914  381.93  4030.1  379.84    4227  374.04  4429.8  370.93
  4534.7  370.59  4642.8   367.2  4674.9   367.8  4802.4  364.67    4823  365.21
  4843.6   363.5  4855.9  365.41  4974.9  365.69  4987.8  364.24  4990.5  360.84
    4991  360.34  5001.4  360.84  5016.7  365.06  5041.5  365.95  5095.3   369.6
  5153.1  370.33  5188.4  369.37  5209.2  371.02  5244.6  371.21  5860.8  373.94
  6092.7  374.43  6134.3  375.42  6175.8  374.55  6251.4  374.94  6378.7  375.47
#Mann= 10 ,-1 , 0
  3884.8     .12       0    3914     .05       0  4674.9     .12       0
  4990.5     .05       0  5001.4     .12       0  5041.5     .07       0
  5244.6     .05       0  5860.8     .07       0  6175.8     .05       0
  6251.4     .07       0
Bank Sta=4990.5,5001.4
XS Rating Curve= 0 ,0
Exp/Cntr=0.3,0.1

Type RM Length L Ch R = 1 ,60817   ,604,604,604
BEGIN DESCRIPTION:
BALDRIDGE CREEK 57.0
END DESCRIPTION:
XS GIS Cut Line= 3
      2506975.02     13805325.01      2506332.74     13805131.77
      2505063.61     13804785.65
#Sta/Elev= 30
  4218.2  380.36  4427.1  373.55  4500.2  374.37  4651.8  370.48  4695.2  371.43
  4704.8  371.44  4796.4  369.23    4928  367.51  4959.1  364.47    4968  360.51
  5000.6  360.62  5006.1  359.15  5006.6  358.65  5019.7  359.15  5047.5   364.7
  5073.2  363.49  5093.9  365.14  5145.7  364.73  5156.1   364.4  5161.5  361.34
  5166.7  361.08  5187.2  364.61  5205.5  364.49  5270.7  364.52  5341.4     364
  5435.9  363.05  5591.6  367.59  5798.7  371.49  5935.8  371.87  6204.4  373.68
#Mann= 11 ,-1 , 0
  4218.2     .05       0  4695.2    .063       0  4704.8     .05       0
  4796.4      .1       0  5006.1     .05       0  5019.7      .1       0
  5205.5     .12       0  5270.7      .1       0  5341.4     .12       0
  5591.6     .07       0  5935.8    .035       0
Bank Sta=5006.1,5019.7
XS Rating Curve= 0 ,0
Exp/Cntr=0.3,0.1

Type RM Length L Ch R = 1 ,60213   ,601,601,601
BEGIN DESCRIPTION:
BA21633
END DESCRIPTION:
XS GIS Cut Line= 4
      2507034.51      13804882.8      2506659.19      13804378.2
      2505712.56     13804707.65      2505088.56     13804765.89
#Sta/Elev= 30
  3590.5  377.66  3830.8  371.24  3946.4  368.25    4024  368.35  4052.8  367.15
  4101.5  367.83  4222.1  366.75    4227  367.41  4501.5  367.04  4700.3  365.97
    4785  364.63  4807.2  365.17    4833  363.65  4889.9   362.8    4965  364.15
  4996.7  362.83  5007.3     361  5012.7  358.02  5013.2  357.52  5026.4  358.02
  5028.5   359.9  5039.1  361.39  5076.4  365.01  5113.2  367.31  5354.7  368.74
  5410.1  370.93    5621  371.64  5711.4  372.86  5741.5  372.24  5848.4  373.92
#Mann= 5 ,-1 , 0
  3590.5    .035       0  3830.8     .05       0  4101.5    .035       0
  5012.7    .035       0  5026.4    .035       0
Bank Sta=5012.7,5026.4
XS Rating Curve= 0 ,0
Exp/Cntr=0.3,0.1

Type RM Length L Ch R = 1 ,59612   ,766,766,766
BEGIN DESCRIPTION:
BA13179
END DESCRIPTION:
XS GIS Cut Line= 4
      2508064.59     13803710.97      2507080.38     13803740.17
      2506062.85     13804123.82      2504665.88     13804595.04
#Sta/Elev= 30
  2834.7  374.41  3018.8  372.93  3096.3  371.67  3240.1  369.02  3384.5  371.66
    3473  366.28    3478  368.65  3574.6  363.14  3615.4   364.3  3654.6  367.17
  3724.7  364.09  4263.8  364.97  4708.9  362.65  4991.5  362.44  5010.1  360.91
  5010.6  356.71  5011.1  356.21  5024.8  356.71  5062.8  359.75  5094.5  357.92
    5105  362.93  5155.2  361.64  5377.2  364.46  5421.5  368.19  5547.6  368.88
  5661.3  370.44  5736.5  371.75  5841.5   372.2  6374.8  378.67  6381.1  378.72
#Mann= 16 ,-1 , 0
  2834.7    .094       0  3018.8    .063       0  3096.3    .094       0
  3240.1    .035       0  3615.4    .063       0  4263.8     .12       0
  4708.9    .063       0  5010.6    .063       0  5024.8    .063       0
  5155.2     .12       0  5377.2    .063       0  5547.6     .07       0
  5661.3    .035       0  5736.5     .07       0  5841.5     .05       0
  6374.8    .035       0
Bank Sta=5010.6,5024.8
XS Rating Curve= 0 ,0
Exp/Cntr=0.3,0.1

Type RM Length L Ch R = 1 ,58846   ,674,674,674
BEGIN DESCRIPTION:
X18088
END DESCRIPTION:
XS GIS Cut Line= 3
      2507717.24     13804112.61        2507025.     13803612.65
      2505179.49     13803372.35
#Sta/Elev= 30
  3339.6   375.3    3375  374.79  3805.1  366.26  3854.4  370.57  3870.1   371.6
  3889.8  368.84  3934.5  363.21  3970.7  367.24  3991.5  364.23  4191.4  363.67
  4348.7  363.48  4631.3  363.42    4970  361.61  4979.6  356.71  4980.1  356.21
    4994  356.71  5030.5     360  5141.4   358.7  5181.8  361.18    5212  359.33
    5219  362.49  5334.4  366.51  5494.4   369.5  5530.2  375.54  5585.2  373.84
  5615.4  377.52  5635.6  374.74  5736.7  376.06  5873.9  379.61  6054.6  385.75
#Mann= 13 ,-1 , 0
  3339.6    .094       0    3375    .063       0  3854.4    .035       0
  3889.8    .063       0  4191.4    .035       0  4348.7    .063       0
  4631.3     .12       0  4979.6     .05       0    4994     .12       0
  5141.4    .035       0  5334.4     .07       0  5736.7     .05       0
  5873.9     .07       0
Bank Sta=4979.6,4994
XS Rating Curve= 0 ,0
Exp/Cntr=0.3,0.1

Type RM Length L Ch R = 1 ,58172   ,588,588,588
BEGIN DESCRIPTION:
BALDRIDGE CREEK 55.0
END DESCRIPTION:
XS GIS Cut Line= 3
      2507784.55      13804045.3      2506630.79     13803074.23
      2505968.67      13802661.6
#Sta/Elev= 30
  3379.2  375.74  3478.7  373.31  3629.8  370.82  3783.8  366.74  3819.3  370.05
  3833.7  371.51  3903.9   363.1    3926  366.32  3984.3     365  4430.9  362.55
  4583.8  361.66  4628.3  357.92  4634.9  360.92  4642.6  358.56  4649.2  362.01
  4685.5     357    4735  357.36  4770.1  361.37  4855.6  358.16    4992  360.21
  5005.9  353.74  5006.4  353.24  5020.5  353.74  5043.9  356.94  5086.4  371.14
  5107.6  373.35  5286.8  379.96  5319.9  380.93  5651.1  383.79  5667.4  386.86
#Mann= 12 ,-1 , 0
  3379.2    .063       0  3478.7    .094       0  3629.8    .063       0
  3819.3    .035       0  3984.3    .063       0  4430.9    .035       0
  4583.8     .12       0  5005.9     .05       0  5020.5     .12       0
  5286.8    .035       0  5319.9     .12       0  5651.1     .07       0
Bank Sta=5005.9,5020.5
XS Rating Curve= 0 ,0
Exp/Cntr=0.3,0.1

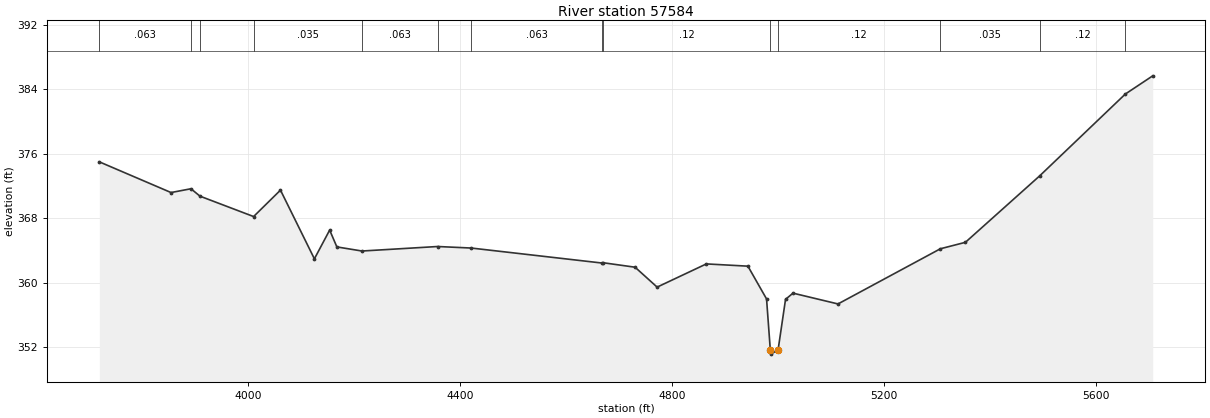
Type RM Length L Ch R = 1 ,57584   ,423,423,423
BEGIN DESCRIPTION:
BALDRIDGE CREEK 54.0
END DESCRIPTION:
XS GIS Cut Line= 3
        2507775.     13803975.01        2506975.       13802975.
      2506475.03     13802475.03
#Sta/Elev= 30
  3719.4  375.01  3854.7   371.2  3892.3  371.67  3909.3  370.75  4010.5  368.22
  4061.2   371.5  4125.2  362.97    4154  366.54  4167.6  364.45    4215  363.94
  4357.7   364.5  4421.2  364.31  4667.7  362.45  4670.7  362.48  4730.3  361.93
  4771.9  359.46  4864.8  362.34  4943.2  362.06  4978.4  357.99  4985.5  351.64
    4986  351.14  5000.1  351.64  5014.2  357.94  5028.3  358.71  5113.2  357.37
  5306.4  364.22  5353.6  365.02  5493.6  373.26  5655.4  383.43  5707.1  385.69
#Mann= 14 ,-1 , 0
  3719.4    .063       0  3892.3    .094       0  3909.3    .063       0
  4010.5    .035       0    4215    .063       0  4357.7    .035       0
  4421.2    .063       0  4667.7    .035       0  4670.7     .12       0
  4985.5     .05       0  5000.1     .12       0  5306.4    .035       0
  5493.6     .12       0  5655.4     .07       0
Bank Sta=4985.5,5000.1
XS Rating Curve= 0 ,0
Exp/Cntr=0.3,0.1