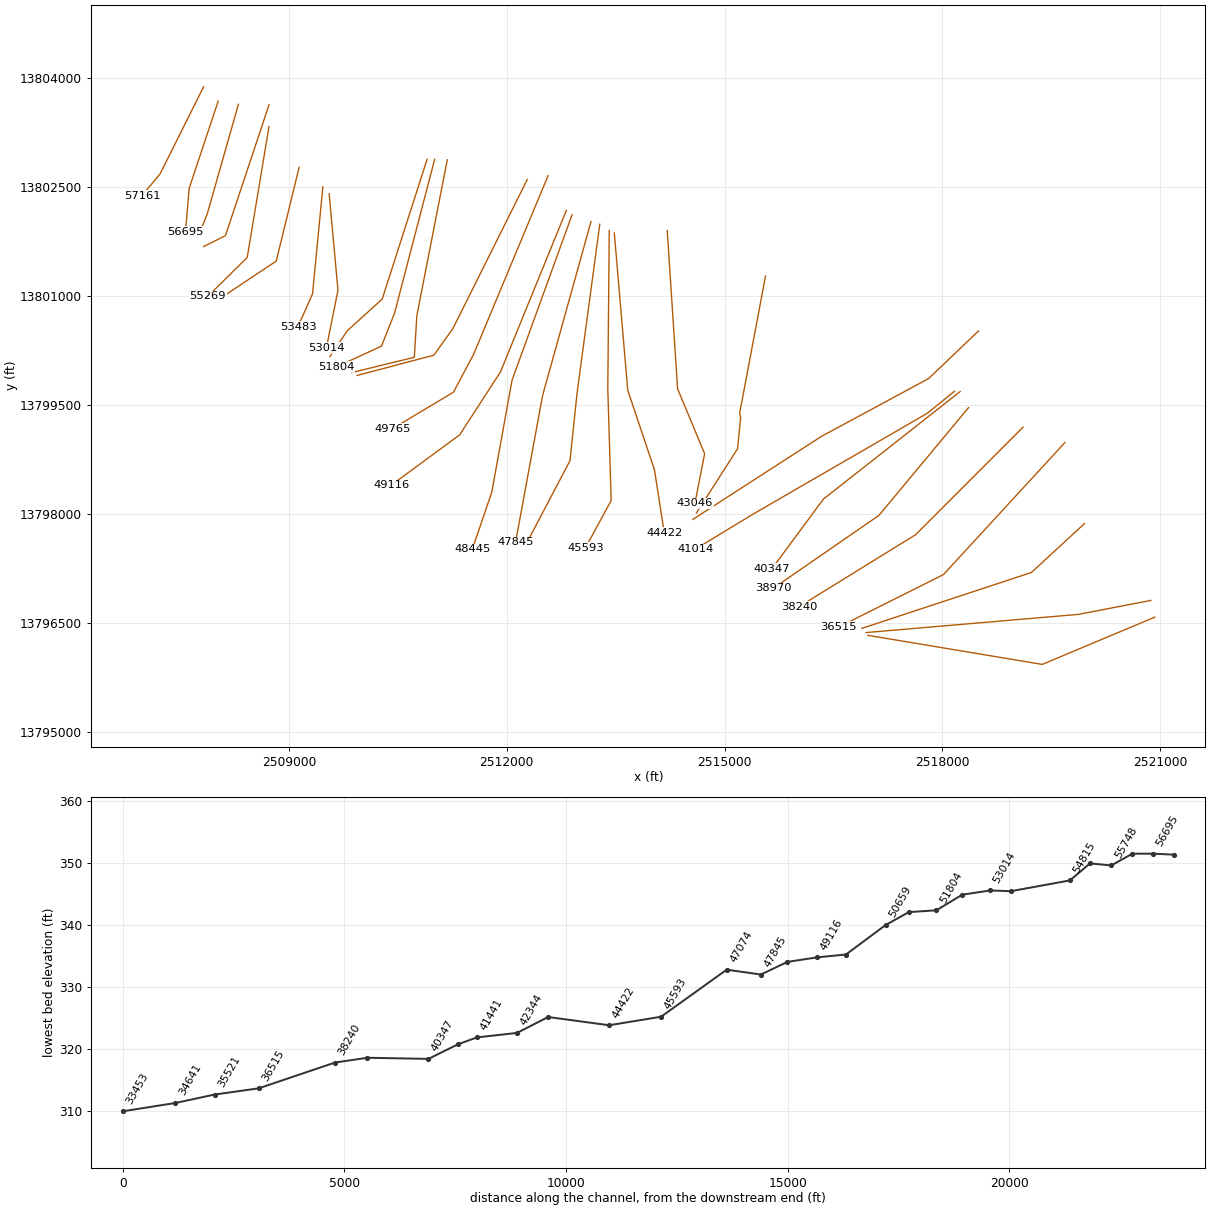
HEC-RAS study BALDRIDGE CREEK.prj: BALDRIDGE CREEK Base Level Engineering

--- BALDRIDGE CREEK.g01 (geometry) --- (continued)

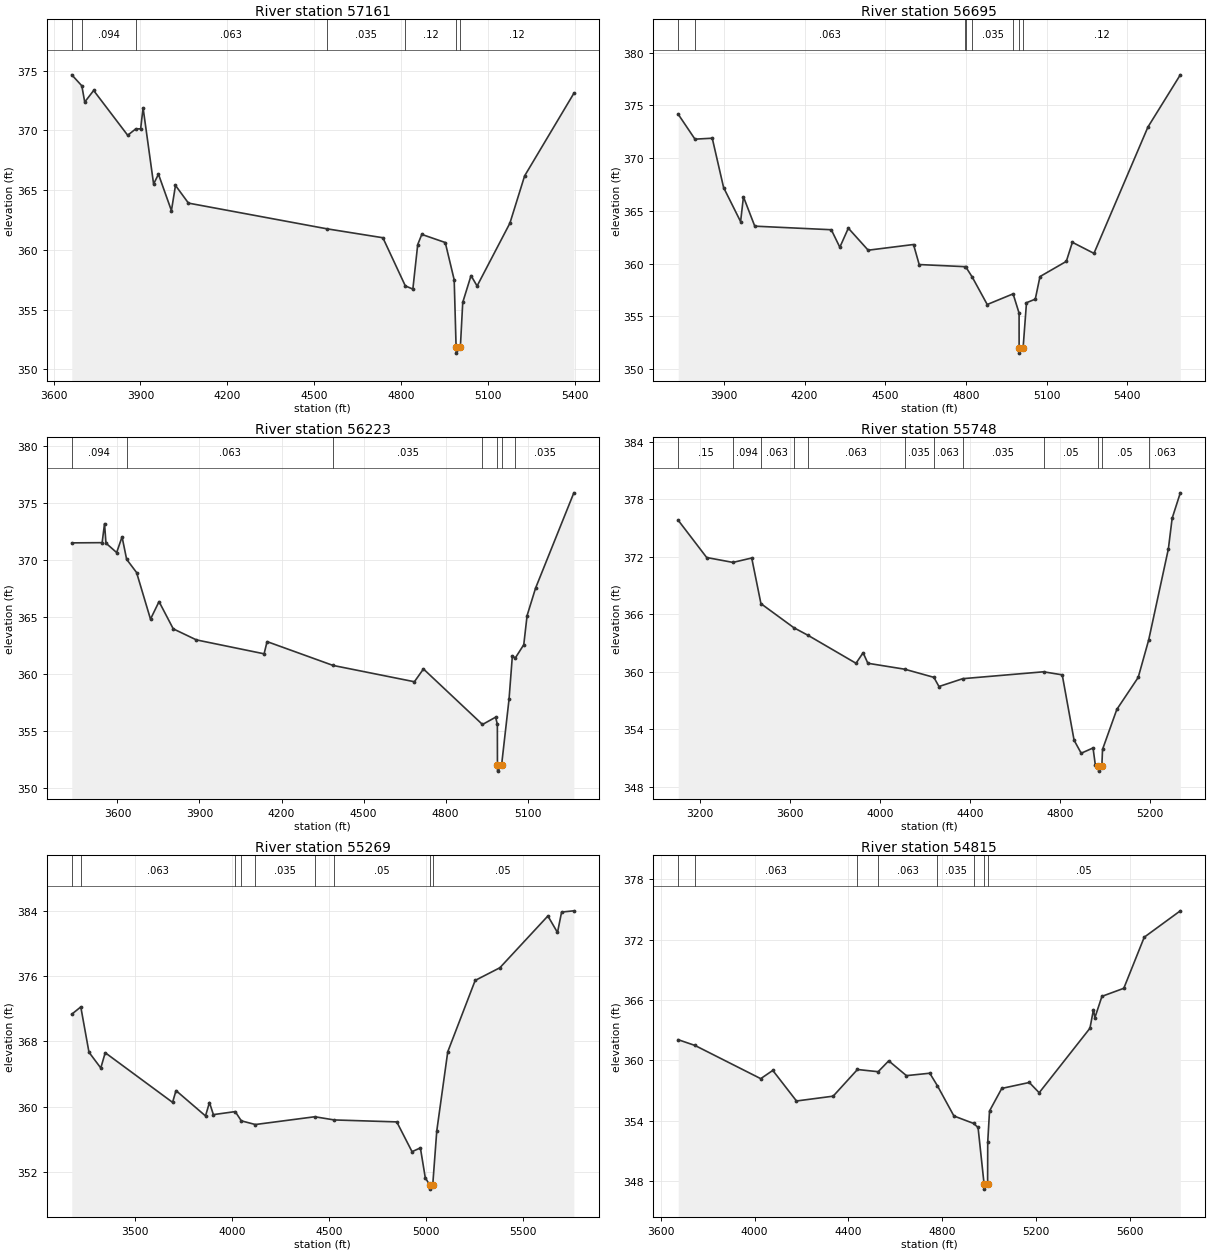
Type RM Length L Ch R = 1 ,57161   ,466,466,466
BEGIN DESCRIPTION:
BALDRIDGE CREEK 53.0
END DESCRIPTION:
XS GIS Cut Line= 3
        2507825.       13803875.        2507225.       13802675.
      2506975.03     13802375.04
#Sta/Elev= 30
  3662.9  374.65  3697.6  373.73  3707.6  372.37  3738.4  373.34  3855.8  369.59
  3883.5  370.12  3900.5  370.13  3908.9  371.89  3945.2  365.51    3962  366.33
  4006.7  363.28  4020.7  365.39  4065.4  363.91  4542.7  361.76  4736.2  361.01
  4813.6  356.98  4839.6  356.71  4856.4  360.44  4870.4  361.29  4951.4  360.61
  4982.2  357.49  4988.8  351.85  4989.3  351.35  5003.5  351.85  5011.7   355.6
  5040.3  357.84  5061.2  356.97  5174.4  362.23  5225.2  366.19    5395   373.1
#Mann= 7 ,-1 , 0
  3662.9    .063       0  3697.6    .094       0  3883.5    .063       0
  4542.7    .035       0  4813.6     .12       0  4988.8     .05       0
  5003.5     .12       0
Bank Sta=4988.8,5003.5
XS Rating Curve= 0 ,0
Exp/Cntr=0.3,0.1

Type RM Length L Ch R = 1 ,56695   ,472,472,472
BEGIN DESCRIPTION:
BALDRIDGE CREEK 52.0
END DESCRIPTION:
XS GIS Cut Line= 3
      2508025.01     13803675.03        2507625.       13802475.
        2507575.     13801875.03
#Sta/Elev= 30
  3730.2  374.16  3792.4   371.8  3856.7  371.89  3898.9  367.21  3962.1  363.98
  3972.7  366.33  4014.8  363.55  4299.4  363.21  4331.1  361.55  4362.7  363.36
  4436.5  361.27  4605.1  361.81  4626.2  359.91    4795  359.71  4800.6  359.64
  4823.3  358.73  4879.2  356.12  4975.4  357.13  4997.7   355.3  4997.8  352.01
  4998.3  351.51  5012.6  352.01  5025.2  356.29  5057.9  356.63  5075.4  358.77
  5173.3  360.21  5195.8  362.02  5276.1  360.97  5476.8  372.95  5597.2   377.9
#Mann= 8 ,-1 , 0
  3730.2    .094       0  3792.4    .063       0    4795    .035       0
  4800.6     .12       0  4823.3    .035       0  4975.4     .12       0
  4997.8     .05       0  5012.6     .12       0
Bank Sta=4997.8,5012.6
XS Rating Curve= 0 ,0
Exp/Cntr=0.3,0.1

Type RM Length L Ch R = 1 ,56223   ,475,475,475
BEGIN DESCRIPTION:
BALDRIDGE CREEK 51.0
END DESCRIPTION:
XS GIS Cut Line= 3
      2508303.76      13803631.9        2507875.       13802125.
      2507774.99     13801874.97
#Sta/Elev= 30
    3433  371.52  3544.1  371.54  3552.8  373.21    3558   371.5  3597.1  370.67
  3616.9  372.05  3633.6  370.08    3670  368.92  3720.9  364.83  3752.1  366.37
  3804.1  363.98  3888.8  363.01  4136.3  361.79  4147.2  362.86  4388.5  360.77
  4685.9  359.34    4719  360.46  4934.9  355.59  4982.8  356.23  4989.3  355.61
  4989.6     352  4990.1   351.5  5004.6     352    5032   357.8  5044.1  361.59
  5054.8  361.42  5085.9  362.59    5098  365.14    5129  367.55    5269  375.91
#Mann= 7 ,-1 , 0
    3433    .094       0  3633.6    .063       0  4388.5    .035       0
  4934.9     .12       0  4989.6     .05       0  5004.6     .12       0
  5054.8    .035       0
Bank Sta=4989.6,5004.6
XS Rating Curve= 0 ,0
Exp/Cntr=0.3,0.1

Type RM Length L Ch R = 1 ,55748   ,479,479,479
BEGIN DESCRIPTION:
BALDRIDGE CREEK 50.0
END DESCRIPTION:
XS GIS Cut Line= 3
      2508725.01     13803625.03        2508125.       13801825.
      2507825.01       13801675.
#Sta/Elev= 30
  3102.5  375.82    3229  371.93  3345.8  371.42  3429.3  371.88  3470.3  367.11
    3617  364.59  3679.8   363.8  3893.1  360.88  3924.7  361.98  3945.8  360.88
  4109.6  360.26  4239.4  359.41    4262  358.45  4367.8  359.27    4727  359.99
  4810.2  359.67  4862.9  352.84  4894.5  351.48  4947.2  352.03  4957.7   350.2
  4971.3  350.11  4971.8  349.61  4986.3  350.11  4989.4  351.88    5053  356.06
    5148   359.4  5194.7  363.32  5282.2  372.83    5299  376.03  5335.3  378.69
#Mann= 12 ,-1 , 0
  3102.5     .15       0  3345.8    .094       0  3470.3    .063       0
    3617    .094       0  3679.8    .063       0  4109.6    .035       0
  4239.4    .063       0  4367.8    .035       0    4727     .05       0
  4971.3     .05       0  4986.3     .05       0  5194.7    .063       0
Bank Sta=4971.3,4986.3
XS Rating Curve= 0 ,0
Exp/Cntr=0.3,0.1

Type RM Length L Ch R = 1 ,55269   ,454,454,454
BEGIN DESCRIPTION:
BALDRIDGE CREEK 49.0
END DESCRIPTION:
XS GIS Cut Line= 3
      2508725.01     13803325.03        2508425.       13801525.
      2507881.83     13800988.95
#Sta/Elev= 30
  3174.9  371.33  3221.4  372.22  3263.6  366.68  3324.5  364.75  3347.3  366.62
  3694.5  360.55  3712.2  361.99  3864.3  358.89  3884.6  360.53  3904.9  359.05
  4017.5  359.42  4048.8  358.29  4121.3  357.84  4427.6  358.79  4527.9   358.4
  4850.2  358.16  4928.8  354.52  4971.9  354.98  4997.2  351.32  5020.5  350.44
    5021  349.94  5035.5  350.44  5056.3  357.05  5112.9  366.73  5254.3  375.46
  5381.6  377.01  5629.1  383.34  5678.6  381.32  5699.8  383.82  5762.9  383.97
#Mann= 9 ,-1 , 0
  3174.9    .094       0  3221.4    .063       0  4017.5    .035       0
  4048.8    .063       0  4121.3    .035       0  4427.6    .063       0
  4527.9     .05       0  5020.5     .05       0  5035.5     .05       0
Bank Sta=5020.5,5035.5
XS Rating Curve= 0 ,0
Exp/Cntr=0.3,0.1

Type RM Length L Ch R = 1 ,54815   ,1332,1332,1332
BEGIN DESCRIPTION:
BALDRIDGE CREEK 48.0
END DESCRIPTION:
XS GIS Cut Line= 3
      2509140.24      13802766.6        2508825.       13801475.
      2508149.92      13801026.3
#Sta/Elev= 30
  3674.5  362.04  3745.9  361.47  4026.1  358.17  4077.6  358.99  4178.5  355.95
  4334.9  356.43  4438.4  359.08  4526.7  358.86  4571.7  359.94  4647.2  358.47
  4746.7  358.71  4779.3  357.46  4849.6  354.46  4933.3  353.72  4952.5  353.32
  4978.2  347.69  4978.7  347.19  4993.2  347.69  4993.7  351.85  5001.4  354.96
  5053.6   357.2  5170.9  357.79    5213  356.77  5429.4  363.18  5444.4  365.03
  5450.5  364.23  5480.5  366.35  5573.7  367.15  5660.9  372.23  5814.6  374.85
#Mann= 8 ,-1 , 0
  3674.5    .035       0  3745.9    .063       0  4438.4    .035       0
  4526.7    .063       0  4779.3    .035       0  4933.3     .05       0
  4978.2     .05       0  4993.2     .05       0
Bank Sta=4978.2,4993.2
XS Rating Curve= 0 ,0
Exp/Cntr=0.3,0.1

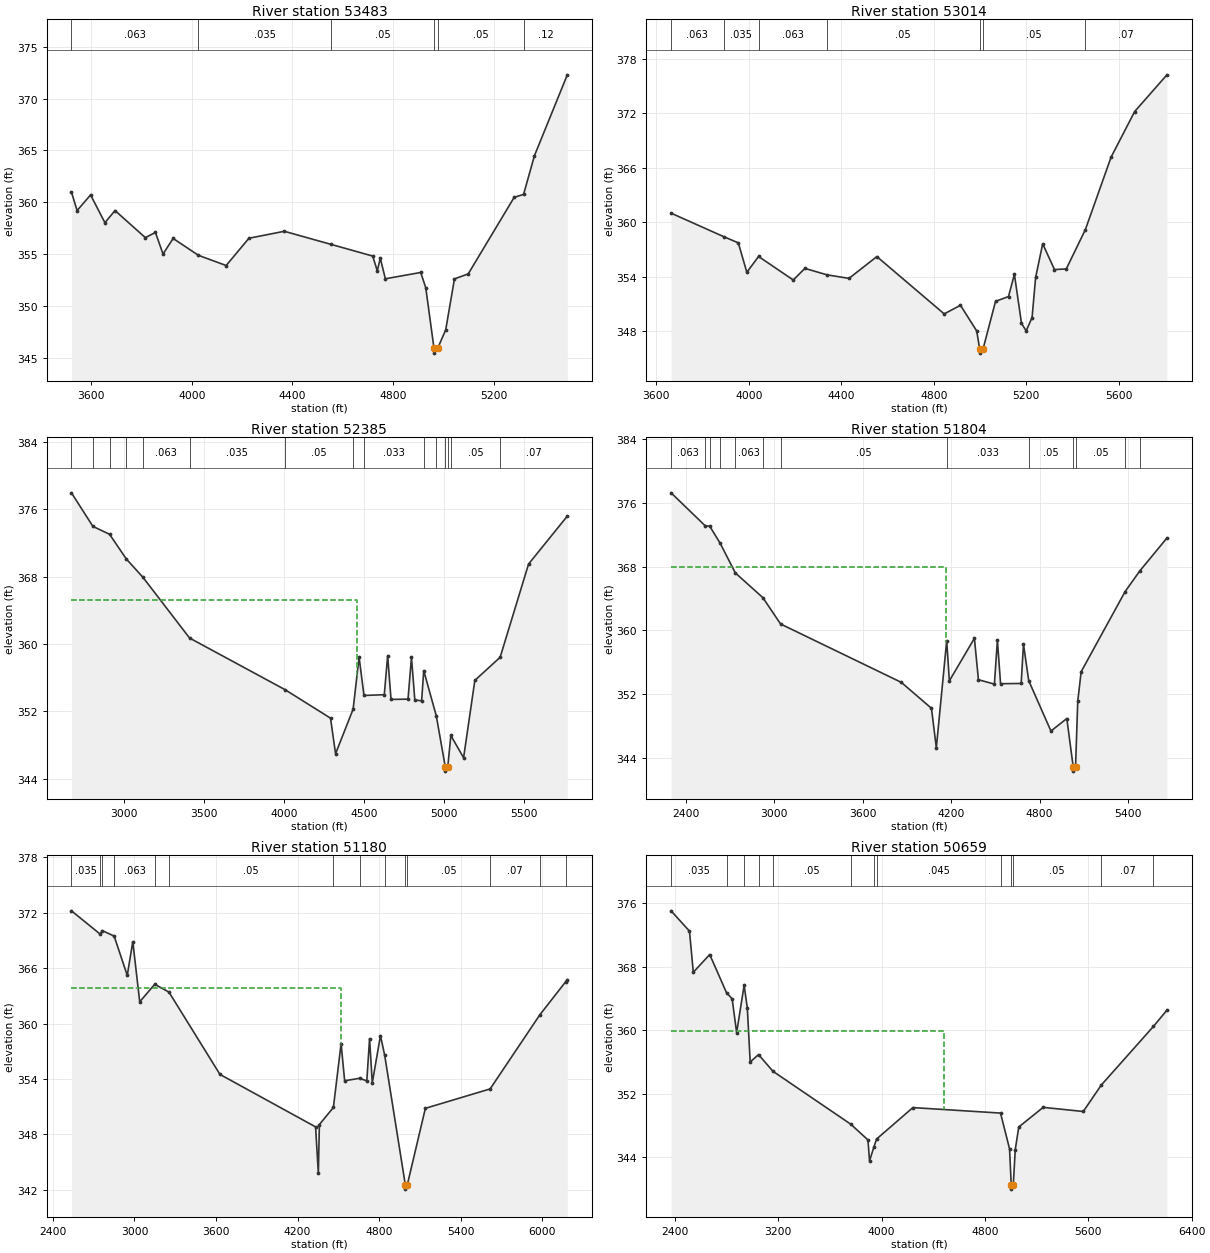
Type RM Length L Ch R = 1 ,53483   ,469,469,469
BEGIN DESCRIPTION:
BALDRIDGE CREEK 47.0
END DESCRIPTION:
XS GIS Cut Line= 3
      2509467.13     13802497.39        2509325.       13801025.
      2509124.99     13800574.98
#Sta/Elev= 30
  3521.2  360.98  3543.7   359.2  3597.2  360.71  3654.2  358.03  3694.4   359.2
    3815  356.59  3855.1  357.09  3885.3  355.01  3925.5  356.51  4026.3  354.88
  4136.4   353.9  4226.9  356.53  4367.5   357.2  4553.3  355.94  4719.1  354.81
  4737.2  353.39  4749.3   354.6  4769.4  352.62    4910  353.23  4930.1  351.75
  4962.6  345.95  4963.1  345.45    4978  345.95  5009.3  347.69  5044.2  352.61
  5098.9  353.09  5281.5  360.47    5319  360.76  5362.2  364.49  5492.9  372.29
#Mann= 6 ,-1 , 0
  3521.2    .063       0  4026.3    .035       0  4553.3     .05       0
  4962.6     .05       0    4978     .05       0    5319     .12       0
Bank Sta=4962.6,4978
XS Rating Curve= 0 ,0
Exp/Cntr=0.3,0.1

Type RM Length L Ch R = 1 ,53014   ,629,629,629
BEGIN DESCRIPTION:
BALDRIDGE CREEK 46.0
END DESCRIPTION:
XS GIS Cut Line= 3
      2509553.66     13802401.19        2509675.       13801075.
      2509515.58     13800278.22
#Sta/Elev= 30
  3663.7  360.98  3891.6  358.39  3954.4  357.71  3991.3  354.47  4042.1  356.21
  4192.1  353.62  4242.3   354.9  4337.8  354.19  4433.1   353.8  4553.6   356.2
  4844.8  349.89  4915.1  350.84  4985.4  348.01  4997.9  346.07  4998.4  345.57
  5013.3  346.07  5066.8  351.27  5122.9   351.8  5148.4  354.25    5179  348.85
  5199.4  348.02  5224.8  349.49  5240.2   353.9  5270.7  357.61  5321.7  354.77
  5372.7  354.84  5455.3  359.17  5566.5  367.15  5668.5  372.17    5808  376.21
#Mann= 7 ,-1 , 0
  3663.7    .063       0  3891.6    .035       0  4042.1    .063       0
  4337.8     .05       0  4997.9     .05       0  5013.3     .05       0
  5455.3     .07       0
Bank Sta=4997.9,5013.3
XS Rating Curve= 0 ,0
Exp/Cntr=0.3,0.1

Type RM Length L Ch R = 1 ,52385   ,581,581,581
BEGIN DESCRIPTION:
X18087
END DESCRIPTION:
XS GIS Cut Line= 4
      2510902.78     13802876.67      2510284.27       13800952.
      2509803.64     13800516.72      2509563.27     13800160.96
#Sta/Elev= 30
  2669.4  377.98  2803.4  373.99  2907.7  373.05    3012  370.12  3116.3  367.93
  3407.7  360.71  4005.2  354.56  4288.7  351.18  4320.2  346.95    4430  352.25
  4467.3  358.43  4497.8  353.88  4624.8  353.97  4645.8  358.62  4666.9  353.41
  4773.1  353.44  4794.7  358.41  4815.7  353.33  4858.3  353.25  4871.3  356.84
    4950  351.44  5006.1  345.38  5006.6  344.88  5021.5  345.38  5040.9  349.12
  5120.5  346.47  5190.8  355.67  5348.9  358.42  5526.6  369.51  5768.8  375.21
#Mann= 15 ,-1 , 0
  2669.4    .063       0  2803.4    .094       0  2907.7    .063       0
    3012    .035       0  3116.3    .063       0  3407.7    .035       0
  4005.2     .05       0    4430    .045       0  4497.8    .033       0
  4871.3     .05       0    4950    .033       0  5006.1    .033       0
  5021.5    .033       0  5040.9     .05       0  5348.9     .07       0
#XS Ineff= 2 , 0
       0  4451.3  365.19               0
Permanent Ineff=
       F       F
Bank Sta=5006.1,5021.5
XS Rating Curve= 0 ,0
Exp/Cntr=0.3,0.1

Type RM Length L Ch R = 1 ,51804   ,624,624,624
BEGIN DESCRIPTION:
BALDRIDGE CREEK 45.0
END DESCRIPTION:
XS GIS Cut Line= 4
      2511006.96     13802876.69      2510454.01     13800757.57
      2510274.76      13800305.2      2509649.87     13800016.78
#Sta/Elev= 30
  2299.8  377.23  2530.8  373.11  2562.3  373.04  2633.3   370.9  2735.7   367.2
  2922.7   364.1  3043.1   360.8  3862.1  353.49  4066.8  350.24  4099.8  345.29
  4170.2  358.71  4188.3  353.68  4358.2  359.01  4385.5  353.82  4493.9  353.27
  4514.2  358.77  4535.7  353.32  4675.5  353.35  4691.2  358.26  4726.8   353.7
  4877.6  347.39  4985.3  348.96  5028.9  342.87  5029.4  342.37  5044.4  342.87
  5059.6  351.14  5082.6  354.82  5380.9  364.86  5480.7  367.45  5664.7  371.57
#Mann= 13 ,-1 , 0
  2299.8    .063       0  2530.8    .094       0  2562.3    .063       0
  2633.3    .035       0  2735.7    .063       0  2922.7    .035       0
  3043.1     .05       0  4170.2    .033       0  4726.8     .05       0
  5028.9     .05       0  5044.4     .05       0  5380.9     .12       0
  5480.7     .07       0
#XS Ineff= 2 , 0
       0  4168.8  367.91               0
Permanent Ineff=
       F       F
Bank Sta=5028.9,5044.4
XS Rating Curve= 0 ,0
Exp/Cntr=0.3,0.1

Type RM Length L Ch R = 1 ,51180   ,521,521,521
BEGIN DESCRIPTION:
X18086
END DESCRIPTION:
XS GIS Cut Line= 4
      2511180.56     13802867.96      2510761.36     13800724.04
      2510726.65     13800151.36      2509861.66     13799939.92
#Sta/Elev= 30
  2536.5   372.2  2748.4  369.67  2763.3  370.06  2850.7  369.46  2947.1  365.21
  2987.8  368.86  3038.8  362.35  3149.5  364.25    3254   363.4  3629.2  354.49
  4332.8  348.81  4353.2  343.79  4360.8  349.06    4464  350.91  4520.5  357.82
  4546.8   353.8  4656.4  354.07  4709.8  353.79  4730.1  358.36  4750.1  353.57
  4810.2  358.69  4841.4  356.56  4992.8  342.57  4993.3  342.07  5008.3  342.57
  5140.8  350.82  5617.3  352.92  5982.9  360.94  6174.1  364.54  6185.2  364.73
#Mann= 14 ,-1 , 0
  2536.5    .035       0  2748.4    .063       0  2763.3    .094       0
  2850.7    .063       0  3149.5    .035       0    3254     .05       0
    4464    .045       0  4656.4    .033       0  4841.4     .05       0
  4992.8     .05       0  5008.3     .05       0  5617.3     .07       0
  5982.9     .12       0  6174.1     .07       0
#XS Ineff= 2 , 0
       0  4518.6  363.82               0
Permanent Ineff=
       F       F
Bank Sta=4992.8,5008.3
XS Rating Curve= 0 ,0
Exp/Cntr=0.3,0.1

Type RM Length L Ch R = 1 ,50659   ,894,894,894
BEGIN DESCRIPTION:
X18085
END DESCRIPTION:
XS GIS Cut Line= 4
        2512283.     13802598.91      2511258.52     13800547.92
      2510995.86      13800180.2      2509939.08      13799901.6
#Sta/Elev= 30
  2371.2  375.01  2513.7  372.45  2543.2  367.28  2670.3  369.51  2800.3   364.7
  2843.7  363.94  2878.6  359.68  2936.5  365.64  2961.1   362.8  2983.5  355.99
  3048.1  356.92  3159.6  354.82  3761.8  348.16  3894.9  346.18    3907  343.55
  3940.7  345.28  3961.3  346.29  4242.3  350.25  4920.8  349.56  4990.6  345.06
  5003.8  340.49  5004.3  339.99  5019.3  340.49  5034.9  344.97  5061.9  347.81
    5251  350.28  5561.3  349.76  5700.2  353.08  6104.4  360.47  6208.6  362.51
#Mann= 13 ,-1 , 0
  2371.2    .035       0  2800.3     .12       0  2936.5     .07       0
  3048.1    .035       0  3159.6     .05       0  3761.8     .12       0
  3940.7     .07       0  3961.3    .045       0  4920.8     .05       0
  5003.8     .05       0  5019.3     .05       0  5700.2     .07       0
  6104.4     .12       0
#XS Ineff= 2 , 0
       0  4483.9  359.94               0
Permanent Ineff=
       F       F
Bank Sta=5003.8,5019.3
XS Rating Curve= 0 ,0
Exp/Cntr=0.3,0.1

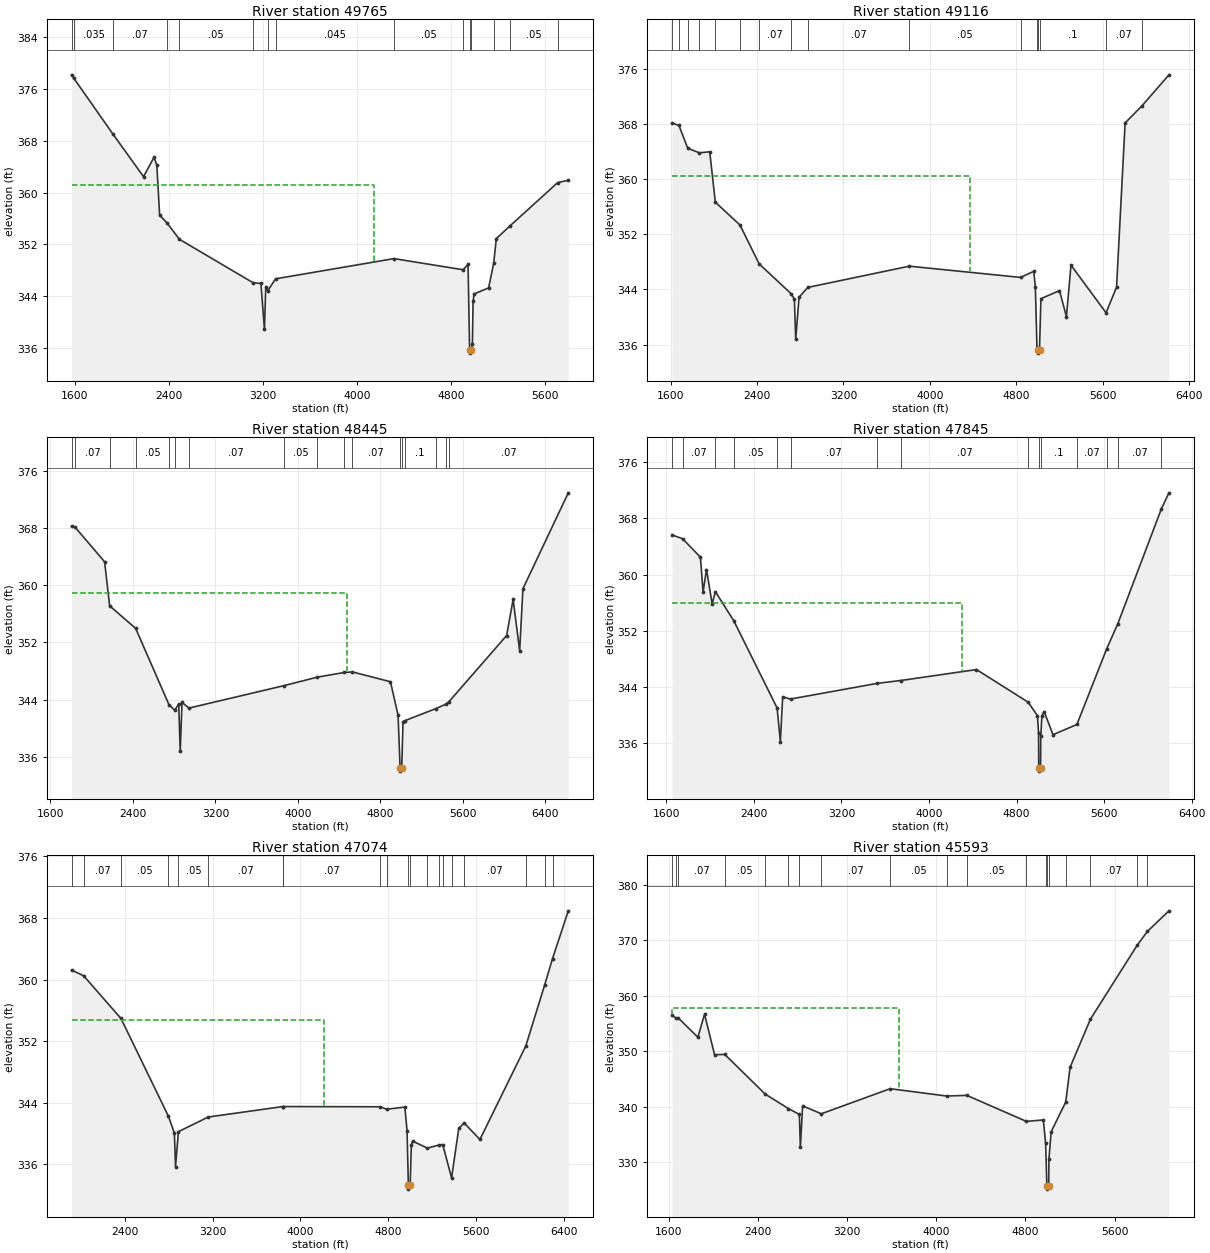
Type RM Length L Ch R = 1 ,49765   ,649,649,649
BEGIN DESCRIPTION:
X18084
END DESCRIPTION:
XS GIS Cut Line= 4
      2512569.47     13802651.01      2511544.81     13800195.13
      2511265.07     13799670.63      2510429.29     13799171.08
#Sta/Elev= 30
  1571.7  378.19  1592.7  377.63  1926.1     369    2185  362.47  2274.3  365.47
  2298.1  364.25    2322  356.52  2382.5  355.38  2490.4   352.8  3117.1   346.1
  3183.9  345.98  3214.4  338.93  3225.2  345.51    3242  344.84  3308.7   346.7
  4316.9  349.82  4905.4   348.1  4947.5  348.93  4960.9  335.73  4961.4  335.23
  4976.8  335.73  4984.5  336.59  4990.4  343.33    5000  344.37  5122.6   345.3
  5166.5  349.17  5188.4  352.91    5304  354.86  5710.3  361.55  5800.9  361.91
#Mann= 15 ,-1 , 0
  1571.7     .05       0  1592.7    .035       0  1926.1     .07       0
  2382.5    .035       0  2490.4     .05       0  3117.1     .07       0
    3242     .12       0  3308.7    .045       0  4316.9     .05       0
  4905.4      .1       0  4960.9     .05       0  4976.8      .1       0
  5166.5     .07       0    5304     .05       0  5710.3     .07       0
#XS Ineff= 2 , 0
       0  4147.3  361.11               0
Permanent Ineff=
       F       F
Bank Sta=4960.9,4976.8
XS Rating Curve= 0 ,0
Exp/Cntr=0.3,0.1

Type RM Length L Ch R = 1 ,49116   ,671,671,671
BEGIN DESCRIPTION:
X18083
END DESCRIPTION:
XS GIS Cut Line= 4
      2512821.19     13802173.54      2511912.99      13799949.2
      2511351.61     13799084.13      2510409.66     13798392.09
#Sta/Elev= 30
  1612.8  368.14  1676.2  367.79  1756.9  364.48  1865.2  363.82  1961.1  363.97
  2012.8  356.66  2241.3  353.35    2419  347.71  2716.9  343.36  2745.4  342.59
  2757.5  336.78  2788.6  342.87  2869.4   344.3  3810.2  347.38  4840.5  345.75
    4963  346.63  4978.1  344.36  4992.9  335.53  5000.4  335.27  5000.9  334.77
  5016.3  335.27  5029.5  342.67  5201.6  343.83  5265.8  340.07  5308.1  347.53
  5633.1  340.62  5730.2  344.34  5809.6  368.16  5965.6  370.63  6215.5  375.13
#Mann= 16 ,-1 , 0
  1612.8    .063       0  1676.2     .07       0  1756.9     .12       0
  1865.2     .07       0  2012.8    .035       0  2241.3     .05       0
    2419     .07       0  2716.9     .12       0  2869.4     .07       0
  3810.2     .05       0  4840.5     .07       0  4992.9      .1       0
  5000.4     .05       0  5016.3      .1       0  5633.1     .07       0
  5965.6     .05       0
#XS Ineff= 2 , 0
       0  4376.7  360.42               0
Permanent Ineff=
       F       F
Bank Sta=5000.4,5016.3
XS Rating Curve= 0 ,0
Exp/Cntr=0.3,0.1

Type RM Length L Ch R = 1 ,48445   ,600,600,600
BEGIN DESCRIPTION:
X18082
END DESCRIPTION:
XS GIS Cut Line= 4
       2512899.3     13802112.75      2512071.78     13799833.45
      2511793.88     13798295.72      2511525.12     13797508.65
#Sta/Elev= 30
  1804.5  368.24  1841.3  368.06  2125.7  363.26  2174.4  357.12    2427  353.96
  2751.2  343.28    2806  342.55  2844.7  343.41    2859   336.8  2876.6  343.63
  2943.9  342.84  3861.6  345.96  4189.8  347.16  4450.4  347.81  4528.9  347.89
  4898.5  346.52  4972.5  341.85    4992  334.54  4992.5  334.04  5008.2  334.54
  5020.4  340.94  5036.2  341.07  5337.7  342.76  5438.2   343.4  5465.3  343.72
  6025.6  352.97  6088.6  358.01    6152  350.84  6183.7   359.5  6623.7  372.89
#Mann= 17 ,-1 , 0
  1804.5    .035       0  1841.3     .07       0  2174.4    .035       0
    2427     .05       0  2751.2     .07       0    2806     .12       0
  2943.9     .07       0  3861.6     .05       0  4189.8     .07       0
  4450.4     .05       0  4528.9     .07       0    4992     .05       0
  5008.2     .07       0  5036.2      .1       0  5337.7     .07       0
  5438.2     .12       0  5465.3     .07       0
#XS Ineff= 2 , 0
       0  4475.3   358.9               0
Permanent Ineff=
       F       F
Bank Sta=4992,5008.2
XS Rating Curve= 0 ,0
Exp/Cntr=0.3,0.1

Type RM Length L Ch R = 1 ,47845   ,771,771,771
BEGIN DESCRIPTION:
X18081
END DESCRIPTION:
XS GIS Cut Line= 3
      2513159.73      13802017.3      2512493.69      13799626.5
      2512120.77     13797603.42
#Sta/Elev= 30
  1653.3  365.64  1749.4  365.11  1911.6  362.48    1936  357.52  1967.1  360.72
    2019  355.82    2048  357.57    2216  353.44  2612.2     341  2641.9  336.22
  2663.1  342.58  2734.7  342.27  3525.7   344.5  3740.6  344.91    4434  346.47
  4906.3  341.82  4990.8  339.91    5001  337.47    5003   332.5  5003.5     332
  5019.3   332.5  5021.3  336.96  5031.5   339.9  5051.8  340.49  5133.2  337.19
  5351.6  338.65  5624.2  349.45  5724.8  352.98  6122.4  369.33  6192.3  371.65
#Mann= 15 ,-1 , 0
  1653.3    .035       0  1749.4     .07       0    2048    .035       0
    2216     .05       0  2612.2     .12       0  2734.7     .07       0
  3525.7     .05       0  3740.6     .07       0  4906.3      .1       0
    5003     .05       0  5019.3      .1       0  5351.6     .07       0
  5624.2     .12       0  5724.8     .07       0  6122.4     .12       0
#XS Ineff= 2 , 0
       0  4301.6  355.97               0
Permanent Ineff=
       F       F
Bank Sta=5003,5019.3
XS Rating Curve= 0 ,0
Exp/Cntr=0.3,0.1

Type RM Length L Ch R = 1 ,47074   ,1481,1481,1481
BEGIN DESCRIPTION:
X18080
END DESCRIPTION:
XS GIS Cut Line= 4
      2513281.25     13801982.54      2512968.83     13799664.85
      2512870.73     13798728.39      2512293.83     13797632.27
#Sta/Elev= 30
  1917.1  361.25  2027.4   360.5  2367.4  354.95  2799.3  342.23    2853  340.06
  2863.1  335.71  2889.7  340.25  3161.3  342.15  3841.4  343.51  3842.4  343.51
  4726.2  343.48    4783  343.16  4949.4  343.44  4969.5  340.35  4981.4  333.28
  4981.9  332.78  4997.7  333.28  5008.5  338.54  5019.8  339.02  5154.5  338.11
  5261.5  338.52  5293.8  338.57  5374.4  334.25  5439.6  340.66  5488.9  341.38
  5632.3  339.23  6049.5  351.38  6221.1   359.3  6292.7  362.74    6436  368.94
#Mann= 20 ,-1 , 0
  1917.1    .035       0  2027.4     .07       0  2367.4     .05       0
  2799.3     .12       0  2889.7     .05       0  3161.3     .07       0
  3841.4     .05       0  3842.4     .07       0  4726.2     .05       0
    4783     .07       0  4981.4     .05       0  4997.7     .07       0
  5154.5    .035       0  5261.5      .1       0  5293.8    .035       0
  5374.4      .1       0  5488.9     .07       0  6049.5     .12       0
  6221.1     .07       0  6292.7     .12       0
#XS Ineff= 2 , 0
       0  4217.8  354.73               0
Permanent Ineff=
       F       F
Bank Sta=4981.4,4997.7
XS Rating Curve= 0 ,0
Exp/Cntr=0.3,0.1

Type RM Length L Ch R = 1 ,45593   ,1171,1171,1171
BEGIN DESCRIPTION:
X18079
END DESCRIPTION:
XS GIS Cut Line= 4
      2513411.46     13801895.73      2513391.43     13799716.86
        2513438.     13798180.35       2513083.2      13797528.3
#Sta/Elev= 30
  1629.5  356.51  1661.7  356.03  1684.7  356.02  1860.2  352.56  1920.2   356.7
  2010.2  349.41  2101.5  349.46  2465.3   342.3  2672.8   339.7  2771.2  338.64
  2780.3  332.72  2800.3  340.19  2968.1  338.76  3586.2  343.28  4093.8  341.96
  4273.9  342.08  4808.8  337.39  4960.8  337.65  4981.4  333.41  4992.7  325.68
  4993.2  325.18  5009.1  325.68  5010.9  330.58  5030.9  335.52  5161.6  340.86
    5201  347.14  5383.6  355.82  5805.8  369.22  5895.2  371.64    6088  375.34
#Mann= 19 ,-1 , 0
  1629.5     .07       0  1661.7    .035       0  1684.7     .07       0
  2101.5     .05       0  2465.3     .07       0  2672.8     .12       0
  2771.2     .05       0  2968.1     .07       0  3586.2     .05       0
  4093.8    .035       0  4273.9     .05       0  4808.8     .07       0
  4981.4      .1       0  4992.7     .05       0  5009.1      .1       0
  5161.6     .12       0  5383.6     .07       0  5805.8    .035       0
  5895.2     .07       0
#XS Ineff= 2 , 0
       0  3665.9  357.78               0
Permanent Ineff=
       F       F
Bank Sta=4992.7,5009.1
XS Rating Curve= 0 ,0
Exp/Cntr=0.3,0.1

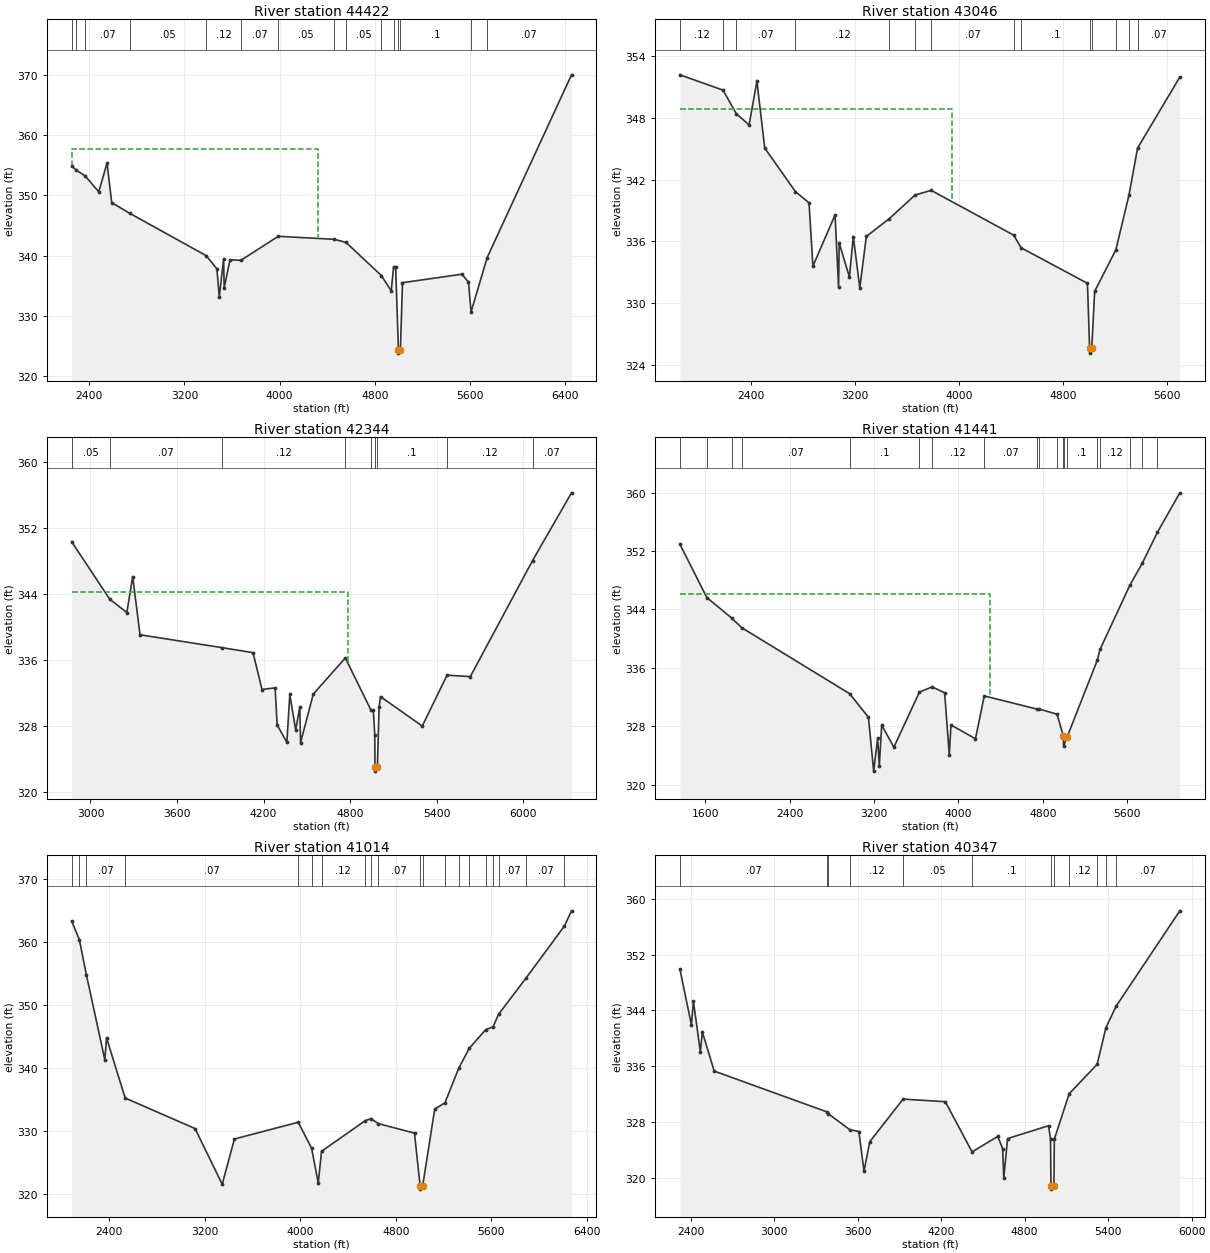
Type RM Length L Ch R = 1 ,44422   ,1376,1376,1376
BEGIN DESCRIPTION:
X18078
END DESCRIPTION:
XS GIS Cut Line= 4
      2513480.91     13801861.08      2513666.25     13799697.76
      2514034.11     13798603.39      2514168.56     13797739.07
#Sta/Elev= 30
  2252.3  354.89    2291  354.19  2365.5  353.22  2480.1  350.58  2549.5  355.35
  2588.9  348.79  2738.9  347.03  3382.9  339.99  3472.8  337.81  3492.9  333.18
  3529.2  339.42  3534.2  334.68  3583.2   339.3    3674  339.21  3988.6   343.2
    4459   342.7  4557.5  342.19  4854.6  336.69  4937.8  334.16  4957.4  338.08
    4975  338.15  4998.4  324.31  4998.9  323.81    5015  324.31  5032.4   335.5
  5531.4  336.91  5586.6  335.62  5608.8  330.65  5743.6  339.65  6452.8     370
#Mann= 15 ,-1 , 0
  2252.3     .07       0    2291    .035       0  2365.5     .07       0
  2738.9     .05       0  3382.9     .12       0    3674     .07       0
  3988.6     .05       0    4459    .035       0  4557.5     .05       0
  4854.6     .07       0  4957.4      .1       0  4998.4     .05       0
    5015      .1       0  5608.8     .12       0  5743.6     .07       0
#XS Ineff= 2 , 0
       0  4319.3  357.73               0
Permanent Ineff=
       F       F
Bank Sta=4998.4,5015
XS Rating Curve= 0 ,0
Exp/Cntr=0.3,0.1

Type RM Length L Ch R = 1 ,43046   ,702,702,702
BEGIN DESCRIPTION:
BALDRIDGE CREEK 42.0
END DESCRIPTION:
XS GIS Cut Line= 4
      2514210.08     13801895.76      2514352.87     13799717.13
        2514725.       13798825.      2514591.76     13798141.91
#Sta/Elev= 30
  1854.2  352.17  2185.9  350.68  2287.3  348.39  2386.1  347.31  2446.2  351.56
  2506.4  345.06  2742.8  340.82  2847.1  339.74  2877.1   333.6  3047.5  338.56
  3074.4  331.56  3079.4  335.84  3157.7  332.54  3187.8  336.45  3237.9  331.48
    3288  336.47  3465.7  338.21  3662.5  340.49  3786.9  340.95  4421.8   336.6
  4479.2  335.37  4989.5  331.92    5006  325.64  5006.5  325.14  5022.6  325.64
  5044.9  331.14  5207.7  335.16  5308.6  340.47  5375.2  345.06  5700.1  351.95
#Mann= 14 ,-1 , 0
  1854.2     .12       0  2185.9    .035       0  2287.3     .07       0
  2742.8     .12       0  3465.7    .035       0  3662.5     .12       0
  3786.9     .07       0  4421.8     .12       0  4479.2      .1       0
    5006     .05       0  5022.6      .1       0  5207.7     .07       0
  5308.6     .12       0  5375.2     .07       0
#XS Ineff= 2 , 0
       0  3943.5  348.81               0
Permanent Ineff=
       F       F
Bank Sta=5006,5022.6
XS Rating Curve= 0 ,0
Exp/Cntr=0.3,0.1

Type RM Length L Ch R = 1 ,42344   ,903,903,903
BEGIN DESCRIPTION:
X18077
END DESCRIPTION:
XS GIS Cut Line= 5
      2515564.24     13801270.78      2515208.34     13799387.08
      2515220.71      13799316.4      2515178.25     13798891.84
      2514611.84     13798008.61
#Sta/Elev= 30
  2869.6  350.31  3133.5  343.37    3252  341.75  3292.7   346.1  3343.6  339.06
  3910.4  337.51  4126.7   336.9  4189.3  332.44  4279.9  332.65    4294  328.15
  4361.3  326.06  4381.7  331.84  4422.4  327.55  4451.2  330.35  4456.2  326.02
  4544.5  331.89  4766.5  336.26  4944.7  329.93  4960.3  329.98  4970.7  326.92
    4972  323.07  4972.5  322.57  4988.7  323.07  5000.5  330.27  5010.5  331.58
  5299.7  328.02  5471.8  334.18  5632.8     334  6064.3  348.04  6334.3  356.23
#Mann= 9 ,-1 , 0
  2869.6     .05       0  3133.5     .07       0  3910.4     .12       0
  4766.5     .07       0  4944.7      .1       0    4972     .05       0
  4988.7      .1       0  5471.8     .12       0  6064.3     .07       0
#XS Ineff= 2 , 0
       0  4785.5  344.19               0
Permanent Ineff=
       F       F
Bank Sta=4972,4988.7
XS Rating Curve= 0 ,0
Exp/Cntr=0.3,0.1

Type RM Length L Ch R = 1 ,41441   ,427,427,427
BEGIN DESCRIPTION:
BA13166
END DESCRIPTION:
XS GIS Cut Line= 4
      2518497.75     13800514.13      2517811.23      13799859.3
      2516332.64     13799061.92      2514563.62      13797921.3
#Sta/Elev= 30
  1362.6  352.91    1617  345.62  1853.4   342.8  1945.3  341.51  2968.9  332.46
  3147.4  329.23  3196.8  321.85  3234.9  326.37  3250.1  322.53  3272.8  328.16
  3388.2  325.13  3630.3  332.68  3750.9  333.39  3869.1  332.58  3912.9  324.09
  3929.1  328.17  4160.9  326.28  4244.1  332.15  4744.5  330.34  4765.3  330.35
  4934.4  329.64  4992.6  326.65  4995.5  325.31  5028.9  326.52  5314.2  337.02
  5340.8  338.52  5624.1  347.34  5741.6  350.35    5884  354.55  6096.1  359.96
#Mann= 19 ,-1 , 0
  1362.6     .07       0    1617     .05       0  1853.4    .035       0
  1945.3     .07       0  2968.9      .1       0  3630.3     .07       0
  3750.9     .12       0  4244.1     .07       0  4744.5    .035       0
  4765.3     .07       0  4934.4    .035       0  4992.6     .05       0
  4995.5     .05       0  5028.9      .1       0  5314.2    .035       0
  5340.8     .12       0  5624.1    .035       0  5741.6     .12       0
    5884    .035       0
#XS Ineff= 2 , 0
       0  4295.3  346.08               0
Permanent Ineff=
       F       F
Bank Sta=4992.6,5028.9
XS Rating Curve= 0 ,0
Exp/Cntr=0.3,0.1

Type RM Length L Ch R = 1 ,41014   ,667,667,667
BEGIN DESCRIPTION:
BA21632
END DESCRIPTION:
XS GIS Cut Line= 4
      2518166.24     13799684.15      2517790.55     13799380.01
      2515393.46     13797993.64      2514597.42     13797510.65
#Sta/Elev= 30
  2086.7  363.26  2151.2  360.32  2210.6  354.69  2364.2  341.26  2378.6  344.73
  2534.7  335.19  3119.4  330.35  3346.9  321.51  3448.8  328.69  3982.8  331.35
  4094.7  327.24  4150.7  321.72    4178  326.74  4542.5  331.58  4591.3  331.92
  4654.5  331.13  4956.2  329.62  5003.3  321.24  5003.8  320.74  5024.6  321.24
  5125.2  333.43  5211.2  334.44  5326.2  339.92  5414.9  343.09  5552.6  346.05
  5613.8  346.48  5659.5  348.47  5892.4  354.29  6210.7  362.47  6270.3  364.89
#Mann= 20 ,-1 , 0
  2086.7     .07       0  2151.2     .15       0  2210.6     .07       0
  2534.7     .07       0  3982.8     .12       0  4094.7     .07       0
    4178     .12       0  4542.5     .07       0  4591.3     .12       0
  4654.5     .07       0  5003.3     .05       0  5024.6     .07       0
  5211.2     .12       0  5326.2     .07       0  5414.9     .12       0
  5552.6     .07       0  5613.8     .12       0  5659.5     .07       0
  5892.4     .07       0  6210.7     .12       0
Bank Sta=5003.3,5024.6
XS Rating Curve= 0 ,0
Exp/Cntr=0.3,0.1

Type RM Length L Ch R = 1 ,40347   ,1377,1377,1377
BEGIN DESCRIPTION:
BALDRIDGE CREEK 41.0
END DESCRIPTION:
XS GIS Cut Line= 3
      2518245.38     13799680.27      2516360.86     13798199.58
       2515650.4      13797239.5
#Sta/Elev= 30
  2324.3  349.89  2406.6  341.93    2421  345.33  2470.7  338.07  2485.2  340.92
  2570.2  335.31  3378.6  329.47  3388.6  329.21  3544.6   326.9  3609.5  326.64
  3646.5  320.96  3688.1  325.19  3927.3  331.29  4230.4  330.92  4422.9  323.72
  4607.3  325.94  4642.5   324.2  4650.6     320  4677.8  325.63  4971.9  327.47
  4986.5  325.59  4989.6  318.88  4990.1  318.38    5011  318.88  5013.6  325.54
  5120.6  332.06  5321.5  336.28  5384.5  341.54  5458.5  344.64  5915.3  358.29
#Mann= 12 ,-1 , 0
  2324.3     .07       0  3378.6     .12       0  3388.6     .07       0
  3544.6     .12       0  3927.3     .05       0  4422.9      .1       0
  4989.6     .05       0    5011      .1       0  5120.6     .12       0
  5321.5     .07       0  5384.5     .12       0  5458.5     .07       0
Bank Sta=4989.6,5011
XS Rating Curve= 0 ,0
Exp/Cntr=0.3,0.1

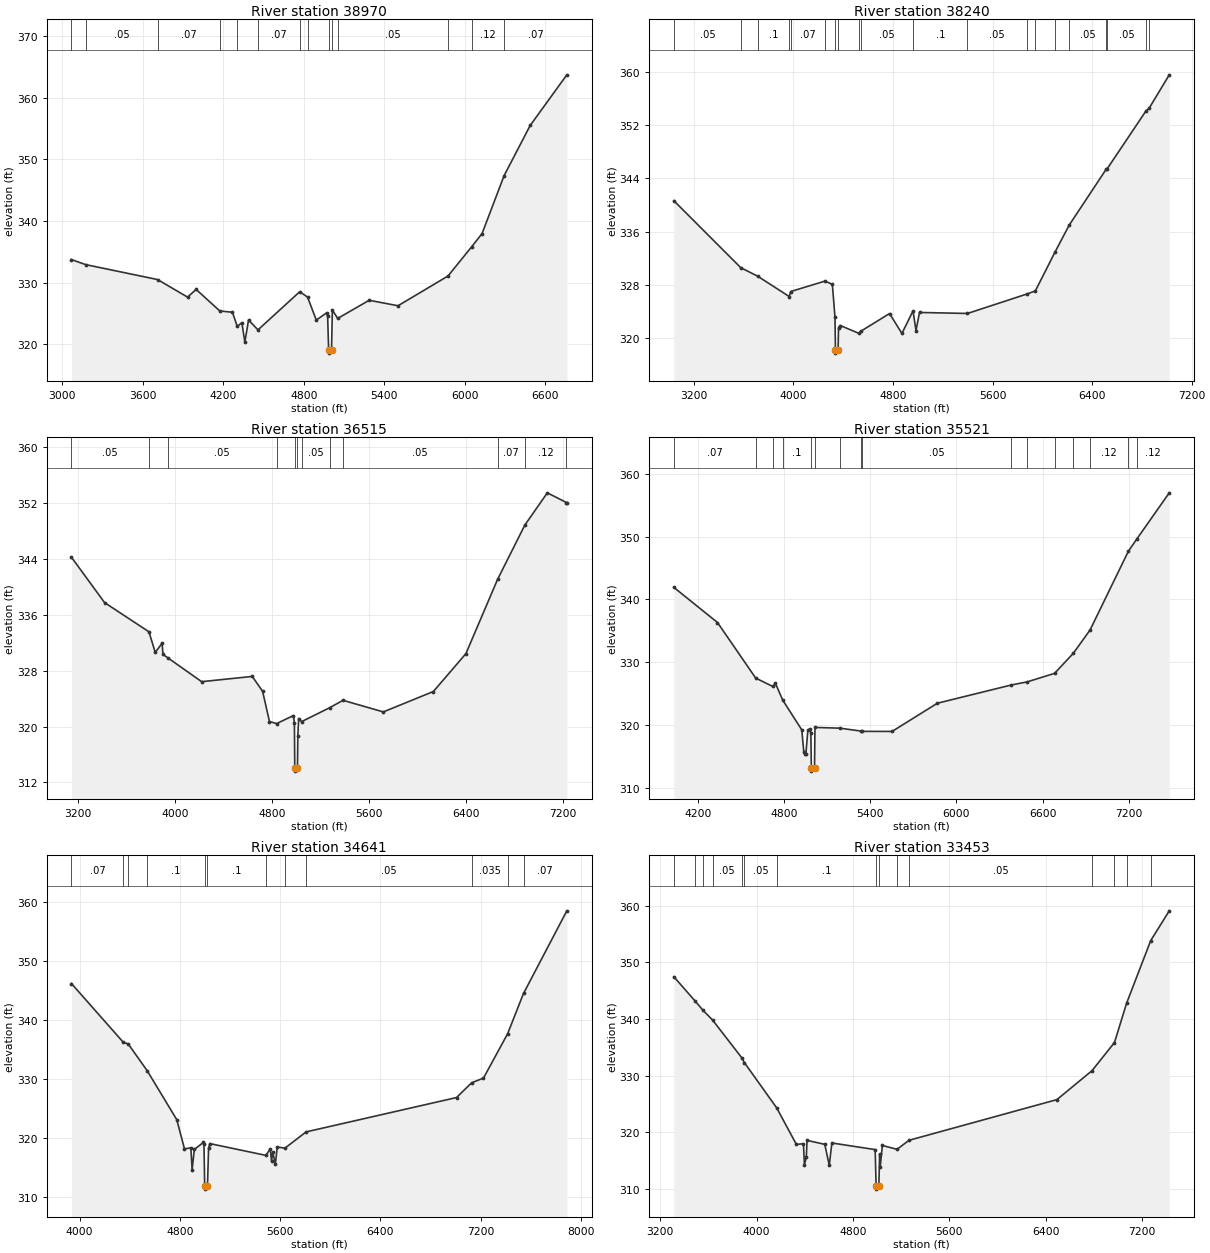
Type RM Length L Ch R = 1 ,38970   ,730,730,730
BEGIN DESCRIPTION:
BALDRIDGE CREEK 40.0
END DESCRIPTION:
XS GIS Cut Line= 3
      2518360.72      13799459.1        2517125.       13797975.
        2515675.       13796975.
#Sta/Elev= 30
  3068.8  333.73    3175  332.91  3710.5  330.49  3934.5  327.64  3998.3  328.89
  4175.1  325.39    4269  325.19  4304.4  322.91  4339.3  323.49  4361.5  320.34
  4388.8  323.93  4459.3  322.33  4770.6  328.52  4828.9  327.64  4893.9  323.92
    4972   325.1  4978.5  324.53    4986  319.06  4986.5  318.56  5007.5  319.06
  5013.5  325.54  5053.9  324.19  5288.1  327.13  5503.1  326.24  5875.5  331.06
  6053.5  335.84  6129.7  337.95    6294  347.34  6488.2  355.47  6761.4  363.68
#Mann= 14 ,-1 , 0
  3068.8     .07       0    3175     .05       0  3710.5     .07       0
  4175.1      .1       0  4304.4     .12       0  4459.3     .07       0
  4770.6     .05       0  4828.9     .07       0    4986     .05       0
  5007.5     .07       0  5053.9     .05       0  5875.5     .07       0
  6053.5     .12       0    6294     .07       0
Bank Sta=4986,5007.5
XS Rating Curve= 0 ,0
Exp/Cntr=0.3,0.1

Type RM Length L Ch R = 1 ,38240   ,1725,1725,1725
BEGIN DESCRIPTION:
BALDRIDGE CREEK 39.0
END DESCRIPTION:
XS GIS Cut Line= 3
      2519110.65     13799189.88        2517630.     13797709.23
      2516025.24     13796719.47
#Sta/Elev= 30
  3040.2  340.65  3577.7  330.61  3713.2  329.33  3967.1  326.28  3978.7  327.03
  4254.8   328.6  4313.4   328.1  4334.6  323.14    4338  318.29  4338.5  317.79
  4359.5  318.29  4362.9  321.62    4377  321.93    4526  320.76  4539.9  321.05
    4773  323.73    4872  320.74  4961.3  324.13  4985.1  321.18  5013.4  323.89
  5398.7  323.74  5874.7  326.65  5943.8  327.12  6102.2  332.96  6215.9     337
  6511.7  345.34  6518.9  345.39  6832.7  354.13  6857.6  354.52  7019.6  359.54
#Mann= 20 ,-1 , 0
  3040.2     .05       0  3577.7     .07       0  3713.2      .1       0
  3967.1     .12       0  3978.7     .07       0  4254.8      .1       0
    4338     .05       0  4359.5      .1       0    4526     .12       0
  4539.9     .05       0  4961.3      .1       0  5398.7     .05       0
  5874.7     .07       0  5943.8     .05       0  6102.2     .07       0
  6215.9     .05       0  6511.7     .07       0  6518.9     .05       0
  6832.7     .07       0  6857.6     .05       0
Bank Sta=4338,4359.5
XS Rating Curve= 0 ,0
Exp/Cntr=0.3,0.1

Type RM Length L Ch R = 1 ,36515   ,994,994,994
BEGIN DESCRIPTION:
X18075
END DESCRIPTION:
XS GIS Cut Line= 3
      2519687.52     13798978.35      2518014.59     13797161.19
      2516572.39     13796440.09
#Sta/Elev= 30
  3148.7  344.25  3421.9  337.75  3787.4  333.57  3839.3  330.62    3896  331.94
  3902.8  330.34  3944.2  329.83  4221.5  326.43  4638.9  327.18    4724  325.05
  4780.7  320.72  4839.8  320.43  4978.6  321.58    4986  320.48  4989.1  314.12
  4989.6  313.62  5011.3  314.12  5014.4  318.65  5021.2  321.15  5045.7  320.71
  5277.8  322.71  5386.6  323.76  5718.8   322.1  6131.3  325.02  6399.6  330.45
  6659.9  341.06  6885.1  348.85  7070.4  353.47  7228.2  352.08  7231.1  352.08
#Mann= 12 ,-1 , 0
  3148.7     .05       0  3787.4     .07       0  3944.2     .05       0
  4839.8      .1       0  4989.1     .05       0  5011.3      .1       0
  5045.7     .05       0  5277.8     .12       0  5386.6     .05       0
  6659.9     .07       0  6885.1     .12       0  7228.2     .07       0
Bank Sta=4989.1,5011.3
XS Rating Curve= 0 ,0
Exp/Cntr=0.3,0.1

Type RM Length L Ch R = 1 ,35521   ,880,880,880
BEGIN DESCRIPTION:
BALDRIDGE CREEK 38.0
END DESCRIPTION:
XS GIS Cut Line= 3
      2519956.76     13797863.07      2519226.04     13797190.04
      2516889.83     13796420.91
#Sta/Elev= 30
  4030.2  341.92  4334.2  336.32  4600.5  327.46  4719.8  326.12    4738  326.62
  4788.9  323.95  4921.7   319.2  4935.9  315.67  4943.3  315.43  4950.1  315.32
  4964.3  319.17  4978.4  319.35  4985.2   318.7  4988.3  313.12  4988.8  312.62
  5010.6  313.12  5013.6  319.59  5187.9  319.47    5336     319  5342.3  318.96
  5551.1  318.95    5867  323.45  6383.1  326.36  6494.1  326.86  6683.6  328.21
  6814.4  331.41  6931.2  335.13  7198.5   347.7    7259   349.7  7483.2     357
#Mann= 16 ,-1 , 0
  4030.2     .07       0  4600.5     .05       0  4719.8     .07       0
  4788.9      .1       0  4988.3     .05       0  5010.6      .1       0
  5187.9     .05       0    5336     .07       0  5342.3     .05       0
  6383.1    .035       0  6494.1     .05       0  6683.6     .07       0
  6814.4    .035       0  6931.2     .12       0  7198.5     .07       0
    7259     .12       0
Bank Sta=4988.3,5010.6
XS Rating Curve= 0 ,0
Exp/Cntr=0.3,0.1

Type RM Length L Ch R = 1 ,34641   ,1188,1188,1188
BEGIN DESCRIPTION:
BALDRIDGE CREEK 37.0
END DESCRIPTION:
XS GIS Cut Line= 3
      2520870.13     13796805.44      2519870.22     13796613.15
      2516948.71     13796363.29
#Sta/Elev= 30
  3935.5  346.21  4349.5  336.21  4387.5  335.96  4539.7  331.39  4775.7  323.06
  4836.8  318.11  4887.8  318.28  4897.9  314.56  4915.3  318.01  4987.4  319.19
  4992.4  318.93    4998  311.76  4998.5  311.26  5020.3  311.76  5029.2  318.26
  5039.3     319  5485.6     317    5521  318.11    5531  316.05  5541.1  317.59
  5561.2  315.47  5576.8  318.41  5638.4  318.23  5806.8  320.99  7006.4  326.83
    7127  329.34  7221.3  330.14  7413.4  337.66  7540.4  344.52  7885.9  358.57
#Mann= 12 ,-1 , 0
  3935.5     .07       0  4349.5     .12       0  4387.5     .05       0
  4539.7      .1       0    4998     .05       0  5020.3      .1       0
  5485.6     .12       0  5638.4     .07       0  5806.8     .05       0
    7127    .035       0  7413.4     .12       0  7540.4     .07       0
Bank Sta=4998,5020.3
XS Rating Curve= 0 ,0
Exp/Cntr=0.3,0.1

Type RM Length L Ch R = 1 ,33453   ,853,853,853
BEGIN DESCRIPTION:
BALDRIDGE CREEK 36.0
END DESCRIPTION:
XS GIS Cut Line= 3
      2520924.96     13796574.98        2519375.       13795925.
      2516975.04     13796324.99
#Sta/Elev= 30
  3313.7  347.47  3488.8  343.21  3556.6  341.52  3635.2  339.82  3877.7  333.14
    3900  332.27  4167.4  324.29  4331.3  317.82  4389.7  317.96    4398   314.2
  4413.5  315.58  4419.7  318.54  4566.9  317.84  4604.1  314.14  4625.7  318.08
  4985.3  316.91  4993.2  310.42  4993.7  309.92  5015.9  310.42  5022.3  316.13
  5027.4  313.87  5045.1  317.64  5166.8  316.96  5267.1  318.56  6494.8  325.75
  6786.2  330.87  6972.5  335.84  7072.8  342.77  7273.5  353.87  7427.5  359.13
#Mann= 15 ,-1 , 0
  3313.7     .07       0  3488.8     .12       0  3556.6     .07       0
  3635.2     .05       0  3877.7     .07       0    3900     .05       0
  4167.4      .1       0  4993.2     .05       0  5015.9      .1       0
  5166.8     .07       0  5267.1     .05       0  6786.2    .035       0
  6972.5     .07       0  7072.8     .12       0  7273.5     .07       0
Bank Sta=4993.2,5015.9
XS Rating Curve= 0 ,0
Exp/Cntr=0.3,0.1