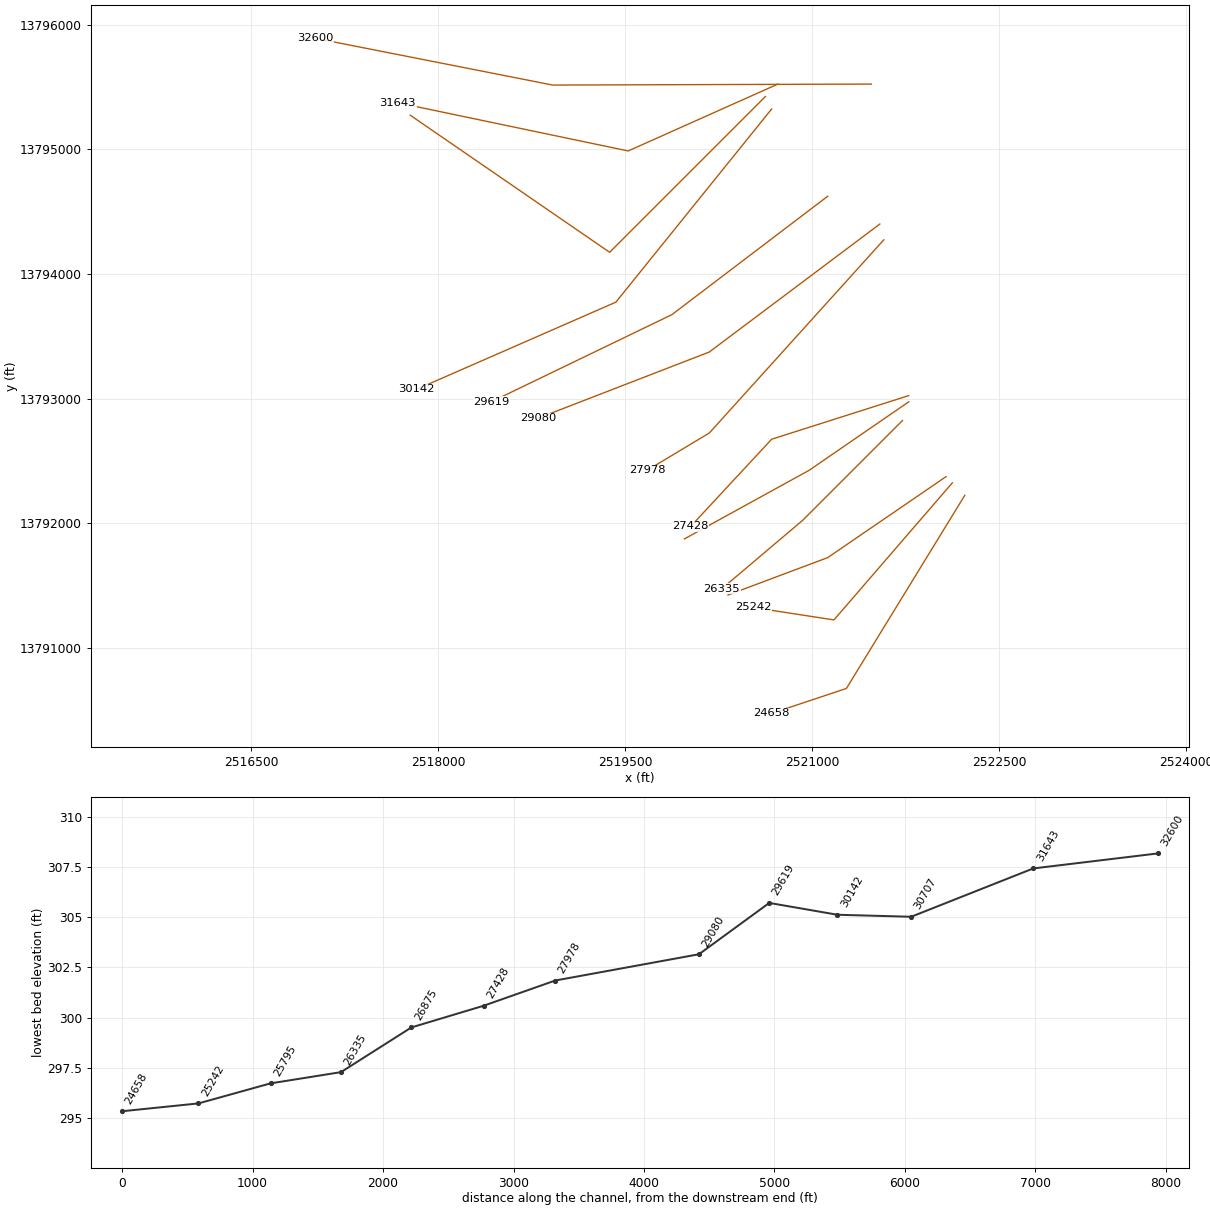
HEC-RAS study BALDRIDGE CREEK.prj: BALDRIDGE CREEK Base Level Engineering

--- BALDRIDGE CREEK.g01 (geometry) --- (continued)

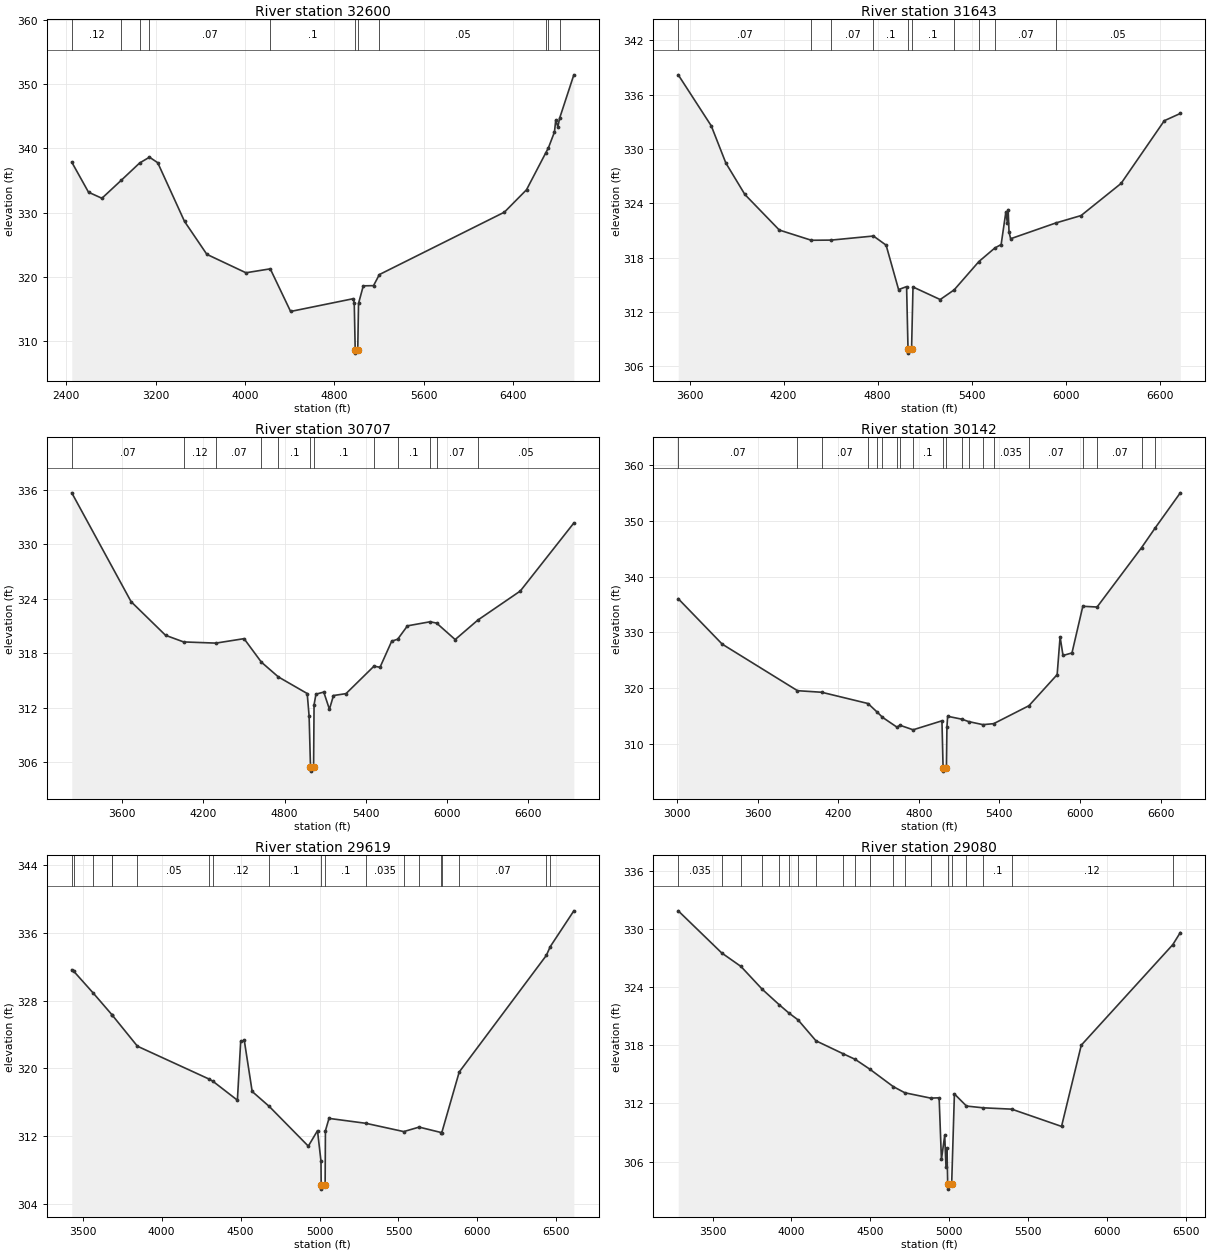
Type RM Length L Ch R = 1 ,32600   ,957,957,957
BEGIN DESCRIPTION:
BALDRIDGE CREEK 35.0
END DESCRIPTION:
XS GIS Cut Line= 3
      2521474.96       13795525.      2518918.37     13795517.08
      2517014.65     13795892.05
#Sta/Elev= 30
  2449.2  337.85  2599.2  333.18  2719.2  332.24  2892.3  335.03  3057.2  337.72
  3145.2  338.62  3219.2  337.76  3459.2  328.64  3659.2  323.53  4009.2  320.67
    4227  321.28  4409.2  314.66  4969.2  316.64  4979.2  316.04  4987.8  308.69
  4988.3  308.19  5010.6  308.69  5017.6   315.9  5060.2  318.64  5151.9  318.67
  5204.2  320.39    6324  330.08  6522.1  333.56  6695.7  339.33  6718.3  340.07
  6772.5  342.53    6784  344.37  6803.1  343.34  6819.2   344.7  6946.1  351.41
#Mann= 11 ,-1 , 0
  2449.2     .12       0  2892.3     .07       0  3057.2     .12       0
  3145.2     .07       0    4227      .1       0  4987.8     .05       0
  5010.6      .1       0  5204.2     .05       0  6695.7    .035       0
  6718.3     .05       0  6819.2     .07       0
Bank Sta=4987.8,5010.6
XS Rating Curve= 0 ,0
Exp/Cntr=0.3,0.1

Type RM Length L Ch R = 1 ,31643   ,936,936,936
BEGIN DESCRIPTION:
BALDRIDGE CREEK 34.0
END DESCRIPTION:
XS GIS Cut Line= 3
        2520725.       13795525.      2519524.09     13794988.27
      2517674.99       13795375.
#Sta/Elev= 30
  3527.5  338.19  3738.4  332.55  3831.3  328.45  3952.8  324.97  4172.6  321.04
  4377.2  319.91  4504.8  319.93  4773.4  320.38  4854.3  319.37  4933.9  314.46
    4985  314.79    4994  307.94  4994.5  307.44  5016.8  307.94  5025.9  314.75
  5199.5  313.36  5288.6  314.43  5446.5  317.56  5547.8  319.05  5588.5  319.44
  5618.4  323.02  5628.2  321.86  5633.3   323.3  5638.8  320.81  5649.1  320.08
  5938.9  321.83  6098.6  322.64    6354  326.19  6629.8  333.12    6732  333.92
#Mann= 10 ,-1 , 0
  3527.5     .07       0  4377.2     .12       0  4504.8     .07       0
  4773.4      .1       0    4994     .05       0  5016.8      .1       0
  5288.6     .12       0  5446.5     .05       0  5547.8     .07       0
  5938.9     .05       0
Bank Sta=4994,5016.8
XS Rating Curve= 0 ,0
Exp/Cntr=0.3,0.1

Type RM Length L Ch R = 1 ,30707   ,565,565,565
BEGIN DESCRIPTION:
BALDRIDGE CREEK 33.0
END DESCRIPTION:
XS GIS Cut Line= 3
      2520624.98     13795424.98        2519375.       13794175.
      2517774.99     13795275.01
#Sta/Elev= 30
  3228.3  335.66  3666.7  323.68  3921.2  319.98  4054.7  319.25  4293.3  319.12
  4501.1  319.61  4629.4  317.02  4754.6   315.4  4967.8  313.57  4981.9  311.06
    4992  305.53  4992.5  305.03  5014.9  305.53  5018.4  312.33  5032.4   313.5
  5090.1  313.73    5132  311.84  5161.8  313.35  5254.5  313.56    5461  316.58
  5505.7  316.46    5592  319.33  5636.2  319.55  5708.4  321.02  5875.7  321.47
  5923.9  321.32  6060.9  319.51  6227.9  321.65  6541.9  324.85  6937.7  332.34
#Mann= 12 ,-1 , 0
  3228.3     .07       0  4054.7     .12       0  4293.3     .07       0
  4629.4     .12       0  4754.6      .1       0    4992     .05       0
  5014.9      .1       0    5461     .07       0  5636.2      .1       0
  5875.7     .05       0  5923.9     .07       0  6227.9     .05       0
Bank Sta=4992,5014.9
XS Rating Curve= 0 ,0
Exp/Cntr=0.3,0.1

Type RM Length L Ch R = 1 ,30142   ,523,523,523
BEGIN DESCRIPTION:
BALDRIDGE CREEK 32.0
END DESCRIPTION:
XS GIS Cut Line= 3
      2520674.99     13795324.98        2519425.       13793775.
      2517825.03     13793075.01
#Sta/Elev= 30
    3009  336.04  3336.1   327.9  3896.8  319.55  4076.7  319.27  4421.7  317.25
  4486.4  315.79  4529.5  314.78    4638     313  4658.8  313.36  4757.5  312.54
  4972.2  314.15  4980.7  305.63  4981.2  305.13  5005.4  305.63  5009.2  313.03
  5014.6  314.96  5120.4  314.44  5171.3  314.01  5277.5  313.46  5357.4  313.64
  5619.9  316.86  5829.8  322.43  5851.6  329.21  5873.4  325.86  5940.1  326.32
  6020.8  334.68    6127  334.55    6458  345.19  6561.7   348.8  6746.6  355.02
#Mann= 20 ,-1 , 0
    3009     .07       0  3896.8     .12       0  4076.7     .07       0
  4421.7     .12       0  4486.4      .1       0  4529.5     .12       0
    4638     .07       0  4658.8     .12       0  4757.5      .1       0
  4980.7     .05       0  5005.4      .1       0  5120.4     .12       0
  5171.3      .1       0  5277.5     .12       0  5357.4    .035       0
  5619.9     .07       0  6020.8    .035       0    6127     .07       0
    6458     .12       0  6561.7     .07       0
Bank Sta=4980.7,5005.4
XS Rating Curve= 0 ,0
Exp/Cntr=0.3,0.1

Type RM Length L Ch R = 1 ,29619   ,539,539,539
BEGIN DESCRIPTION:
BALDRIDGE CREEK 31.0
END DESCRIPTION:
XS GIS Cut Line= 3
      2521125.02     13794625.01        2519875.       13793675.
      2518424.98     13792974.99
#Sta/Elev= 30
  3430.6  331.64  3444.5  331.44  3565.7  328.91    3686  326.31  3687.6  326.27
  3846.5  322.61  4301.1  318.72  4325.1  318.46  4479.7  316.23  4500.6  323.19
  4523.4  323.29  4573.3  317.26  4681.7  315.49  4928.9   310.8  4987.1  312.63
  5009.2  309.01  5010.4  306.22  5010.9  305.72  5035.4  306.22  5037.3  312.62
  5059.9  314.08  5293.1   313.5  5533.5  312.52  5630.7  313.05  5772.3   312.4
  5773.9  312.37  5884.7  319.56  6436.5  333.34  6461.4  334.38  6610.8  338.61
#Mann= 19 ,-1 , 0
  3430.6     .07       0  3444.5    .035       0  3565.7     .07       0
    3686     .05       0  3687.6     .07       0  3846.5     .05       0
  4301.1     .07       0  4325.1     .12       0  4681.7      .1       0
  5010.4     .05       0  5035.4      .1       0  5293.1    .035       0
  5533.5      .1       0  5630.7     .12       0  5772.3      .1       0
  5773.9     .12       0  5884.7     .07       0  6436.5    .035       0
  6461.4     .07       0
Bank Sta=5010.4,5035.4
XS Rating Curve= 0 ,0
Exp/Cntr=0.3,0.1

Type RM Length L Ch R = 1 ,29080   ,1102,1102,1102
BEGIN DESCRIPTION:
BALDRIDGE CREEK 30.0
END DESCRIPTION:
XS GIS Cut Line= 3
      2521543.15     13794401.75        2520175.       13793375.
      2518802.97     13792844.19
#Sta/Elev= 30
  3282.8  331.87  3558.7  327.52  3680.4  326.13    3815  323.78  3921.5   322.2
  3985.3  321.31  4042.1  320.62  4155.7  318.46    4326  317.14  4403.9  316.55
  4496.4  315.54  4645.1  313.74  4718.8   313.1  4882.3  312.55  4936.1  312.58
  4950.7  306.22  4971.5  308.71  4979.8  305.42  4986.1   307.4  4990.5  303.66
    4991  303.16  5015.5  303.66  5032.9  312.98  5109.5  311.73    5214  311.55
    5396  311.41  5711.8  309.63  5836.9  318.01  6416.8  328.38  6464.5  329.63
#Mann= 20 ,-1 , 0
  3282.8    .035       0  3558.7     .07       0  3680.4     .05       0
    3815     .07       0  3921.5    .035       0  3985.3     .07       0
  4042.1     .05       0  4155.7     .07       0    4326     .05       0
  4403.9    .035       0  4496.4     .07       0  4645.1    .035       0
  4718.8     .12       0  4882.3      .1       0  4990.5     .05       0
  5015.5      .1       0  5109.5     .12       0    5214      .1       0
    5396     .12       0  6416.8     .07       0
Bank Sta=4990.5,5015.5
XS Rating Curve= 0 ,0
Exp/Cntr=0.3,0.1

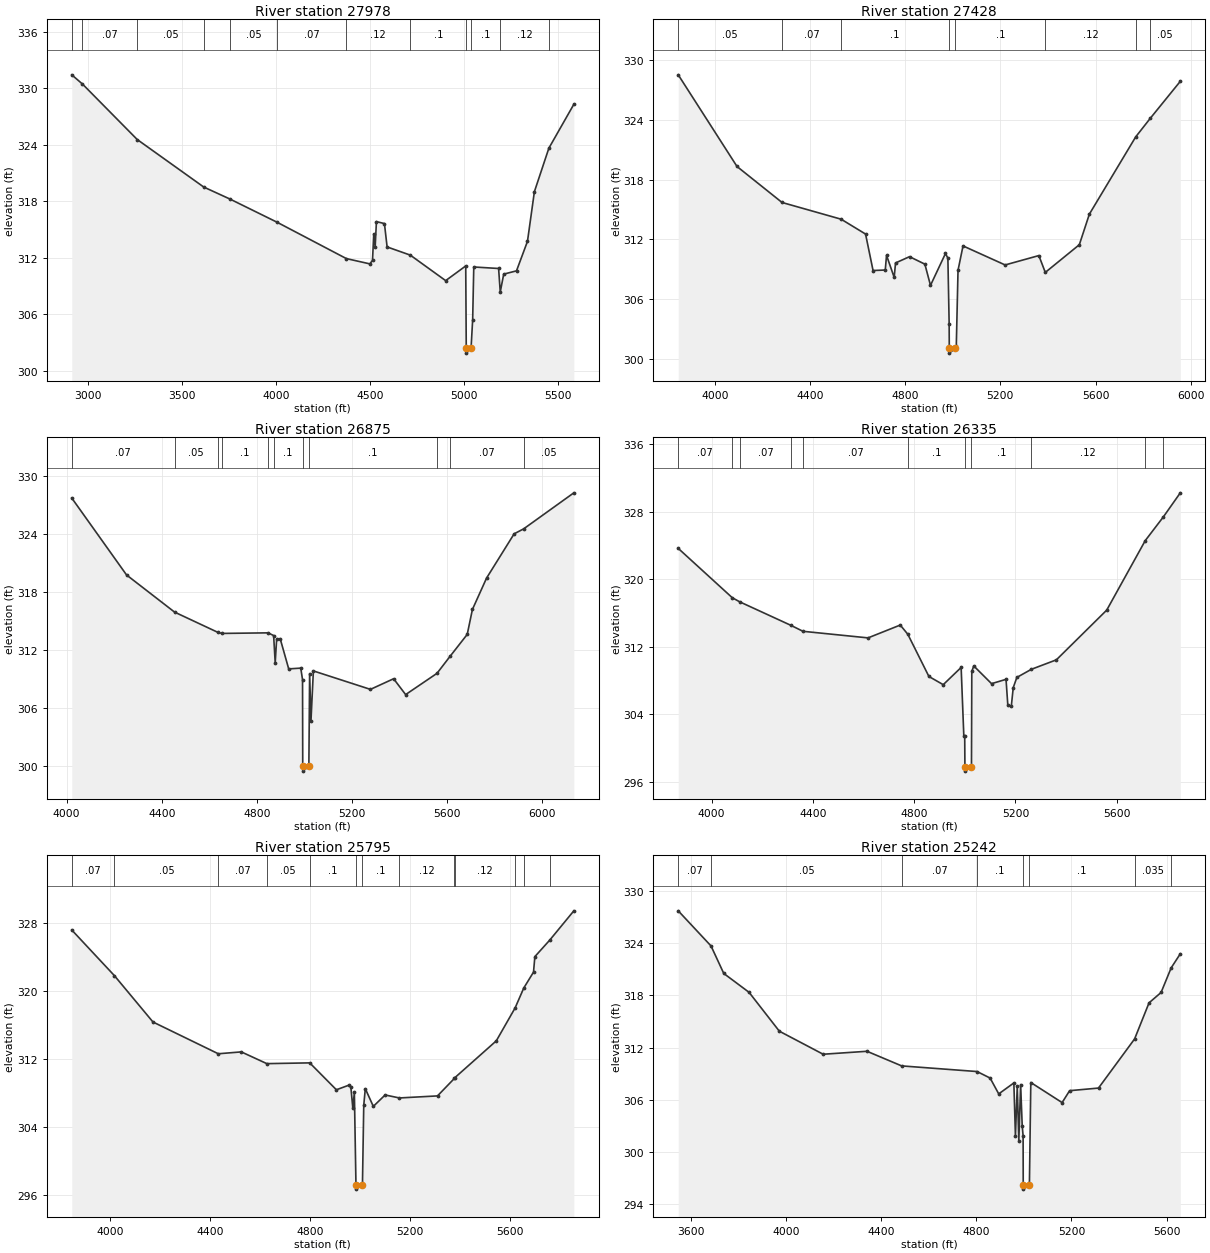
Type RM Length L Ch R = 1 ,27978   ,550,550,550
BEGIN DESCRIPTION:
BALDRIDGE CREEK 29.0
END DESCRIPTION:
XS GIS Cut Line= 3
      2521574.97     13794274.97        2520175.       13792725.
      2519675.01     13792425.01
#Sta/Elev= 30
  2911.9  331.41  2968.9  330.43  3260.1  324.54  3614.2  319.49  3753.2  318.22
  4004.7  315.75  4373.3  311.89    4498  311.33  4512.2  311.69  4518.9  314.52
  4526.4  313.15  4533.1  315.82  4575.7  315.61  4589.9  313.13  4713.3  312.26
  4901.5  309.55  5008.3  311.11  5011.1  302.35  5011.6  301.85  5036.6  302.35
  5045.2  305.41  5051.1     311  5183.2  310.84    5192  308.34  5210.4  310.24
  5278.5  310.59  5336.8  313.72  5373.7     319  5450.7  323.62  5583.6  328.28
#Mann= 12 ,-1 , 0
  2911.9    .035       0  2968.9     .07       0  3260.1     .05       0
  3614.2     .07       0  3753.2     .05       0  4004.7     .07       0
  4373.3     .12       0  4713.3      .1       0  5011.1     .05       0
  5036.6      .1       0    5192     .12       0  5450.7     .07       0
Bank Sta=5011.1,5036.6
XS Rating Curve= 0 ,0
Exp/Cntr=0.3,0.1

Type RM Length L Ch R = 1 ,27428   ,553,553,553
BEGIN DESCRIPTION:
BALDRIDGE CREEK 28.0
END DESCRIPTION:
XS GIS Cut Line= 3
      2521775.03     13793025.01        2520675.       13792675.
      2520025.01     13791975.01
#Sta/Elev= 30
  3846.7  328.52  4093.7  319.32  4282.8  315.71  4531.2  314.03  4633.8  312.54
  4665.3  308.88  4716.6  308.93  4721.9   310.4  4754.1  308.19  4759.7  309.64
  4818.5  310.27    4883  309.52  4906.6  307.39  4969.6  310.59  4979.7  310.12
    4985  303.56  4985.6  301.09  4986.1  300.59  5011.2  301.09    5015  301.27
  5022.3   308.9  5043.3  311.35  5220.2  309.44  5361.9  310.38    5389  308.69
    5532  311.47  5574.2  314.54  5768.8  322.29  5829.6  324.14  5956.3  327.87
#Mann= 8 ,-1 , 0
  3846.7     .05       0  4282.8     .07       0  4531.2      .1       0
  4985.6     .05       0  5011.2      .1       0    5389     .12       0
  5768.8     .07       0  5829.6     .05       0
Bank Sta=4985.6,5011.2
XS Rating Curve= 0 ,0
Exp/Cntr=0.3,0.1

Type RM Length L Ch R = 1 ,26875   ,540,540,540
BEGIN DESCRIPTION:
BALDRIDGE CREEK 27.0
END DESCRIPTION:
XS GIS Cut Line= 3
      2521774.97     13792974.98        2520975.       13792425.
      2519974.96     13791874.98
#Sta/Elev= 30
  4021.6  327.77  4252.1  319.81  4453.9  315.97  4636.3  313.87  4653.3  313.76
  4847.7  313.82  4870.8  313.54  4877.4  310.73  4883.4  313.14  4898.3  313.22
  4934.2  310.09  4984.9  310.17  4992.4  308.97  4993.2  300.01  4993.7  299.51
    5019  300.01  5022.2   309.6  5027.9  304.73    5038  309.88    5278  307.97
  5375.5  309.07  5426.1  307.43    5558  309.63  5612.7  311.38  5685.2  313.66
    5707  316.24  5766.6  319.49  5882.6  324.07  5922.5  324.58  6133.7  328.31
#Mann= 11 ,-1 , 0
  4021.6     .07       0  4453.9     .05       0  4636.3     .07       0
  4653.3      .1       0  4847.7     .07       0  4870.8      .1       0
  4993.2     .05       0    5019      .1       0    5558     .12       0
  5612.7     .07       0  5922.5     .05       0
Bank Sta=4993.2,5019
XS Rating Curve= 0 ,0
Exp/Cntr=0.3,0.1

Type RM Length L Ch R = 1 ,26335   ,540,540,540
BEGIN DESCRIPTION:
BALDRIDGE CREEK 26.0
END DESCRIPTION:
XS GIS Cut Line= 3
      2521725.03     13792825.03        2520925.       13792025.
      2520274.98     13791474.99
#Sta/Elev= 30
  3868.4  323.66  4081.7  317.82  4111.9  317.32  4313.8  314.54    4361  313.84
    4618  313.06  4745.2  314.58  4775.1  313.49  4858.4  308.49    4915  307.52
  4985.7  309.56  4996.3  301.45  4999.8  301.45  5000.6  297.78  5001.1  297.28
  5026.5  297.78  5027.8  309.08  5035.5  309.74  5105.8  307.64    5163  308.15
  5170.1  305.08  5183.8  304.96  5191.5  307.17  5205.8  308.38  5263.1  309.34
  5361.8  310.46  5560.7  316.35  5712.8  324.58  5783.6  327.36  5851.3  330.24
#Mann= 11 ,-1 , 0
  3868.4     .07       0  4081.7     .05       0  4111.9     .07       0
  4313.8     .05       0    4361     .07       0  4775.1      .1       0
  5000.6     .05       0  5026.5      .1       0  5263.1     .12       0
  5712.8    .035       0  5783.6     .07       0
Bank Sta=5000.6,5026.5
XS Rating Curve= 0 ,0
Exp/Cntr=0.3,0.1

Type RM Length L Ch R = 1 ,25795   ,553,553,553
BEGIN DESCRIPTION:
BALDRIDGE CREEK 25.0
END DESCRIPTION:
XS GIS Cut Line= 3
      2522075.04     13792375.03        2521125.       13791725.
      2520325.03     13791425.01
#Sta/Elev= 30
  3848.5  327.16    4019  321.79  4172.9  316.35  4433.8  312.62  4525.7  312.84
  4627.7  311.46    4799  311.55  4905.5  308.39  4956.3  308.94  4963.3   308.7
  4971.2  306.22  4977.3   308.1  4983.7  297.22  4984.2  296.72  5009.6  297.22
  5014.8  306.57    5021  308.52    5053  306.44  5100.2  307.78  5157.2  307.43
  5309.4  307.67  5376.7  309.72  5378.7  309.81  5544.3  314.14  5619.5  318.01
  5653.9  320.34  5692.9  322.21  5698.3  324.03    5758  325.98    5854  329.41
#Mann= 13 ,-1 , 0
  3848.5     .07       0    4019     .05       0  4433.8     .07       0
  4627.7     .05       0    4799      .1       0  4983.7     .05       0
  5009.6      .1       0  5157.2     .12       0  5376.7      .1       0
  5378.7     .12       0  5619.5      .1       0  5653.9    .035       0
    5758     .07       0
Bank Sta=4983.7,5009.6
XS Rating Curve= 0 ,0
Exp/Cntr=0.3,0.1

Type RM Length L Ch R = 1 ,25242   ,584,584,584
BEGIN DESCRIPTION:
BALDRIDGE CREEK 24.0
END DESCRIPTION:
XS GIS Cut Line= 3
        2522125.       13792325.        2521175.       13791225.
      2520524.99       13791325.
#Sta/Elev= 30
  3546.7  327.72  3684.6  323.68  3738.1  320.52  3844.5  318.35  3971.8  313.88
  4156.1  311.23  4340.4  311.57  4486.1  309.89  4803.3  309.24  4858.1  308.49
  4894.3  306.67  4957.9  307.93  4964.5  301.86  4972.2  307.53  4978.8  301.31
  4986.4  307.74    4993     303  4996.8  301.85  4997.3  296.22  4997.8  295.72
  5023.3  296.22  5029.2  307.98  5160.8  305.67  5192.4  307.04  5313.8  307.34
  5465.6  312.99  5526.3  317.14  5576.9  318.33  5619.3  321.16  5657.8  322.78
#Mann= 8 ,-1 , 0
  3546.7     .07       0  3684.6     .05       0  4486.1     .07       0
  4803.3      .1       0  4997.3     .05       0  5023.3      .1       0
  5465.6    .035       0  5619.3     .12       0
Bank Sta=4997.3,5023.3
XS Rating Curve= 0 ,0
Exp/Cntr=0.3,0.1

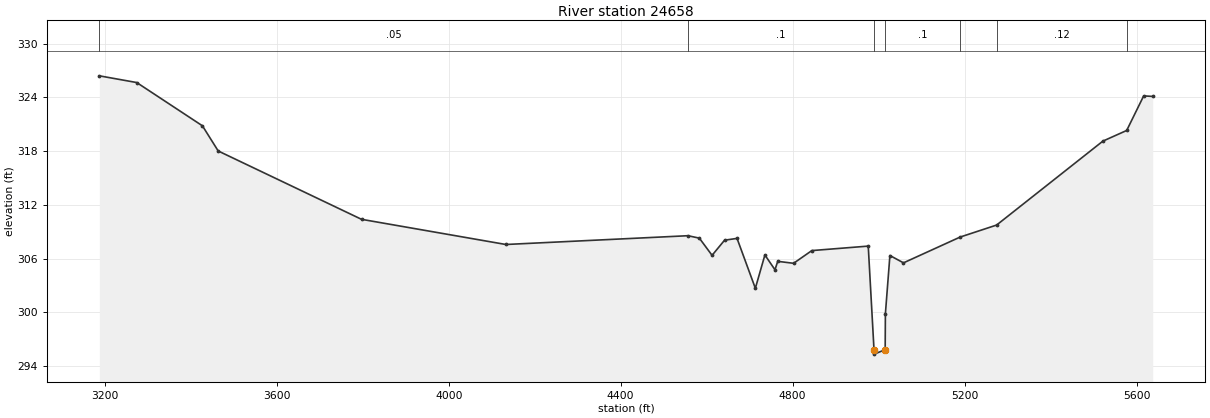
Type RM Length L Ch R = 1 ,24658   ,564,564,564
BEGIN DESCRIPTION:
BALDRIDGE CREEK 23.0
END DESCRIPTION:
XS GIS Cut Line= 3
      2522224.99     13792224.98        2521275.       13790675.
        2520675.       13790475.
#Sta/Elev= 30
  3187.3   326.4  3274.3  325.65  3427.1  320.82  3463.8  318.01  3797.2  310.38
    4133  307.57  4556.4  308.55    4583  308.28  4612.6  306.36  4641.7  308.05
  4670.7  308.25  4713.3  302.68  4735.5   306.4  4758.9  304.75  4765.4  305.69
  4802.2  305.47  4844.7  306.89  4975.9  307.39  4989.3  295.83  4989.8  295.33
  5015.3  295.83  5015.8  299.84  5026.3  306.34  5057.9  305.52  5189.7   308.4
  5274.5  309.74  5521.7  319.11  5577.1   320.3  5616.6  324.16  5637.7   324.1
#Mann= 7 ,-1 , 0
  3187.3     .05       0  4556.4      .1       0  4989.3     .05       0
  5015.3      .1       0  5189.7    .035       0  5274.5     .12       0
  5577.1     .07       0
Bank Sta=4989.3,5015.3
XS Rating Curve= 0 ,0
Exp/Cntr=0.3,0.1