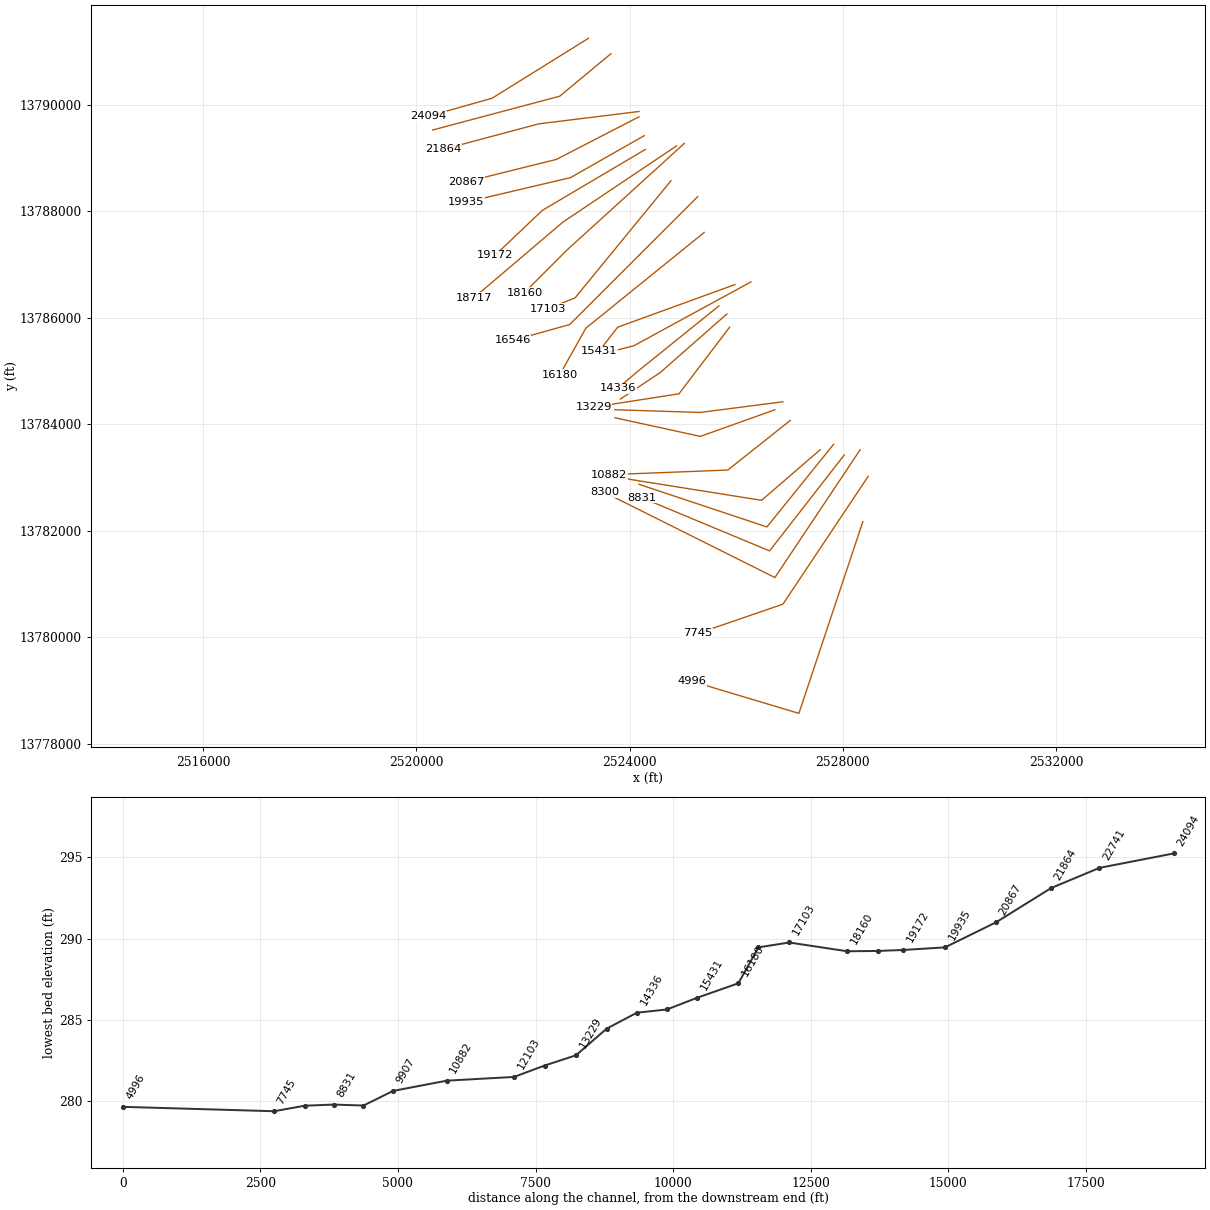
HEC-RAS study BALDRIDGE CREEK.prj: BALDRIDGE CREEK Base Level Engineering

--- BALDRIDGE CREEK.g01 (geometry) --- (continued)

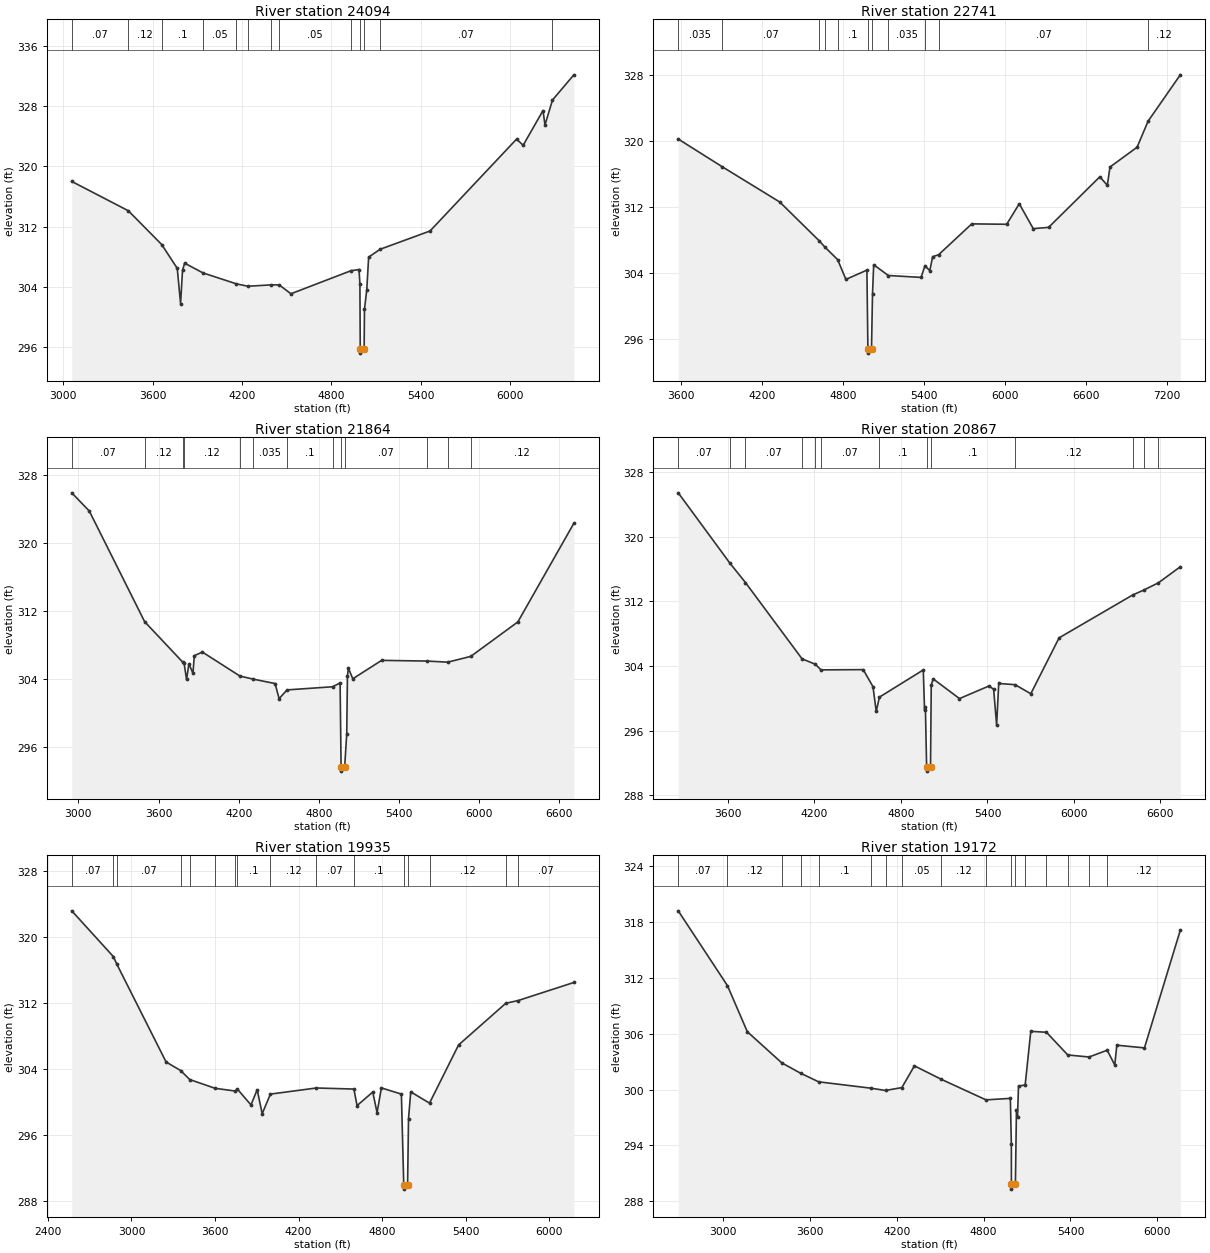
Type RM Length L Ch R = 1 ,24094   ,1353,1353,1353
BEGIN DESCRIPTION:
X18074
END DESCRIPTION:
XS GIS Cut Line= 3
      2523225.75     13791248.16      2521418.19     13790123.24
      2520225.99     13789786.73
#Sta/Elev= 30
  3058.4  318.01  3437.9  314.12  3661.7  309.64    3766  306.48  3788.3  301.81
  3801.3  306.22  3815.5  307.17  3938.6  305.88  4162.3  304.43  4239.8  304.11
  4394.9  304.29  4450.2  304.29  4528.4  303.11  4931.2  306.17  4985.2  306.33
  4991.1  304.46  4993.5  295.74    4994  295.24  5019.5  295.74  5021.8  301.05
  5037.2  303.65  5049.8  307.97  5126.3  309.01  5461.6  311.44  6041.8  323.62
  6086.2  322.81  6219.4  327.41  6232.6   325.5    6283  328.81  6426.2  332.15
#Mann= 13 ,-1 , 0
  3058.4     .07       0  3437.9     .12       0  3661.7      .1       0
  3938.6     .05       0  4162.3     .07       0  4239.8     .05       0
  4394.9     .07       0  4450.2     .05       0  4931.2    .035       0
  4993.5    .035       0  5019.5    .035       0  5126.3     .07       0
    6283     .12       0
Bank Sta=4993.5,5019.5
XS Rating Curve= 0 ,0
Exp/Cntr=0.3,0.1

Type RM Length L Ch R = 1 ,22741   ,877,877,877
BEGIN DESCRIPTION:
BALDRIDGE CREEK 22.0
END DESCRIPTION:
XS GIS Cut Line= 3
      2523648.78      13790959.7      2522687.33      13790161.7
      2520302.91     13789527.13
#Sta/Elev= 30
  3579.9  320.22    3905  316.88  4331.5  312.61  4624.4  307.91  4667.1  307.14
    4760  305.65  4821.1  303.26  4976.7  304.38    4984  294.85  4984.5  294.35
  5010.7  294.85  5018.1   301.5  5026.8  305.03  5135.2  303.73  5377.7   303.5
  5406.2   304.9  5442.3  304.32  5463.2     306  5507.4  306.24  5752.8  309.97
  6011.5  309.92  6104.6   312.4  6208.1  309.39  6321.9  309.55    6701  315.66
  6756.5  314.63  6776.1  316.84  6976.8  319.23  7058.2  322.38  7296.8  327.98
#Mann= 11 ,-1 , 0
  3579.9    .035       0    3905     .07       0  4624.4    .035       0
  4667.1     .07       0    4760      .1       0    4984     .05       0
  5010.7      .1       0  5135.2    .035       0  5406.2      .1       0
  5507.4     .07       0  7058.2     .12       0
Bank Sta=4984,5010.7
XS Rating Curve= 0 ,0
Exp/Cntr=0.3,0.1

Type RM Length L Ch R = 1 ,21864   ,997,997,997
BEGIN DESCRIPTION:
BALDRIDGE CREEK 21.0
END DESCRIPTION:
XS GIS Cut Line= 3
      2524175.03       13789875.      2522293.13      13789642.5
       2520495.2     13789161.77
#Sta/Elev= 30
  2950.9   325.9  3081.9  323.76  3496.2  310.72  3783.7  305.91  3790.8  305.89
  3809.9  303.91  3827.5  305.75  3857.8  304.64  3867.8  306.71  3928.3  307.14
  4209.4  304.31  4308.3  303.95  4472.4  303.43  4502.6  301.65  4561.6  302.68
  4902.9  303.05    4959   303.5  4966.3  293.61  4966.8  293.11  4993.2  293.61
  5008.6  297.54  5013.8  304.28  5021.1  305.24  5053.9  303.99  5269.6  306.16
  5606.9  306.08  5764.7  305.95    5937  306.63  6289.2  310.69  6708.2  322.31
#Mann= 13 ,-1 , 0
  2950.9     .07       0  3496.2     .12       0  3783.7     .07       0
  3790.8     .12       0  4209.4     .07       0  4308.3    .035       0
  4561.6      .1       0  4902.9     .07       0  4966.3     .05       0
  4993.2     .07       0  5606.9     .12       0  5764.7      .1       0
    5937     .12       0
Bank Sta=4966.3,4993.2
XS Rating Curve= 0 ,0
Exp/Cntr=0.3,0.1

Type RM Length L Ch R = 1 ,20867   ,932,932,932
BEGIN DESCRIPTION:
BALDRIDGE CREEK 20.0
END DESCRIPTION:
XS GIS Cut Line= 3
      2524175.04     13789775.02        2522625.       13788975.
      2520938.71     13788556.35
#Sta/Elev= 30
  3255.7  325.42  3613.8  316.73  3721.8  314.33  4114.5  304.89  4205.9  304.23
  4245.4  303.53  4538.6  303.56  4606.2  301.45  4628.7   298.4  4650.8  300.16
    4955  303.52    4964  298.52  4969.6  298.98  4978.3  291.51  4978.8  291.01
  5005.2  291.51  5010.3  301.65  5023.3  302.42  5206.1  299.98  5412.2  301.55
  5443.1  301.11  5463.7   296.7  5478.2  301.85    5591   301.7  5700.7  300.58
    5897  307.49  6406.2  312.78  6484.4   313.4  6585.2  314.29  6737.5  316.28
#Mann= 13 ,-1 , 0
  3255.7     .07       0  3613.8     .12       0  3721.8     .07       0
  4114.5    .035       0  4205.9     .12       0  4245.4     .07       0
  4650.8      .1       0  4978.3     .05       0  5005.2      .1       0
    5591     .12       0  6406.2    .035       0  6484.4     .12       0
  6585.2     .07       0
Bank Sta=4978.3,5005.2
XS Rating Curve= 0 ,0
Exp/Cntr=0.3,0.1

Type RM Length L Ch R = 1 ,19935   ,763,763,763
BEGIN DESCRIPTION:
X18073
END DESCRIPTION:
XS GIS Cut Line= 3
      2524273.74     13789421.36      2522889.24     13788632.96
      2520928.91     13788171.71
#Sta/Elev= 30
  2570.9  323.14  2869.7   317.6    2893  316.74  3248.4  304.85  3353.2  303.81
  3418.6  302.72  3601.3  301.66  3746.4  301.33  3760.7  301.57  3858.3  299.65
    3903  301.49  3938.9  298.59    3998  300.96  4328.2   301.7  4597.9  301.57
  4620.5  299.57  4733.5  301.21  4764.3   298.7  4795.2  301.71    4939  300.96
    4956  289.96  4956.5  289.46  4983.5  289.96  4990.3     298  5006.2  301.23
  5141.2  299.87  5349.9  306.91    5689  311.95  5777.2  312.28    6178  314.47
#Mann= 16 ,-1 , 0
  2570.9     .07       0  2869.7     .12       0    2893     .07       0
  3353.2    .035       0  3418.6     .07       0  3601.3     .12       0
  3746.4     .07       0  3760.7      .1       0    3998     .12       0
  4328.2     .07       0  4597.9      .1       0    4956     .05       0
  4983.5      .1       0  5141.2     .12       0    5689    .035       0
  5777.2     .07       0
Bank Sta=4956,4983.5
XS Rating Curve= 0 ,0
Exp/Cntr=0.3,0.1

Type RM Length L Ch R = 1 ,19172   ,455,455,455
BEGIN DESCRIPTION:
BALDRIDGE CREEK 19.0
END DESCRIPTION:
XS GIS Cut Line= 3
      2524292.98     13789161.77      2522360.43     13788017.62
      2521475.02     13787175.02
#Sta/Elev= 30
  2690.8  319.23  3030.9  311.18    3168  306.23    3406  302.88  3535.6  301.77
  3660.7  300.84  4019.9  300.16  4122.8  299.91  4235.4  300.22  4322.3  302.56
  4509.2   301.1  4816.7   298.9  4984.9  299.06  4991.8  294.14  4992.2   289.8
  4992.7   289.3  5019.7   289.8    5027  297.79  5034.3  297.07  5041.2  300.38
  5087.1   300.5  5126.1  306.27  5234.2  306.17  5381.4  303.73  5528.5  303.51
  5653.9  304.24  5706.1  302.65  5720.3  304.78  5911.2  304.49  6158.9  317.15
#Mann= 17 ,-1 , 0
  2690.8     .07       0  3030.9     .12       0    3406    .035       0
  3535.6     .12       0  3660.7      .1       0  4019.9     .07       0
  4122.8     .12       0  4235.4     .05       0  4509.2     .12       0
  4816.7      .1       0  4992.2     .05       0  5019.7      .1       0
  5087.1     .12       0  5234.2     .07       0  5381.4    .035       0
  5528.5     .07       0  5653.9     .12       0
Bank Sta=4992.2,5019.7
XS Rating Curve= 0 ,0
Exp/Cntr=0.3,0.1

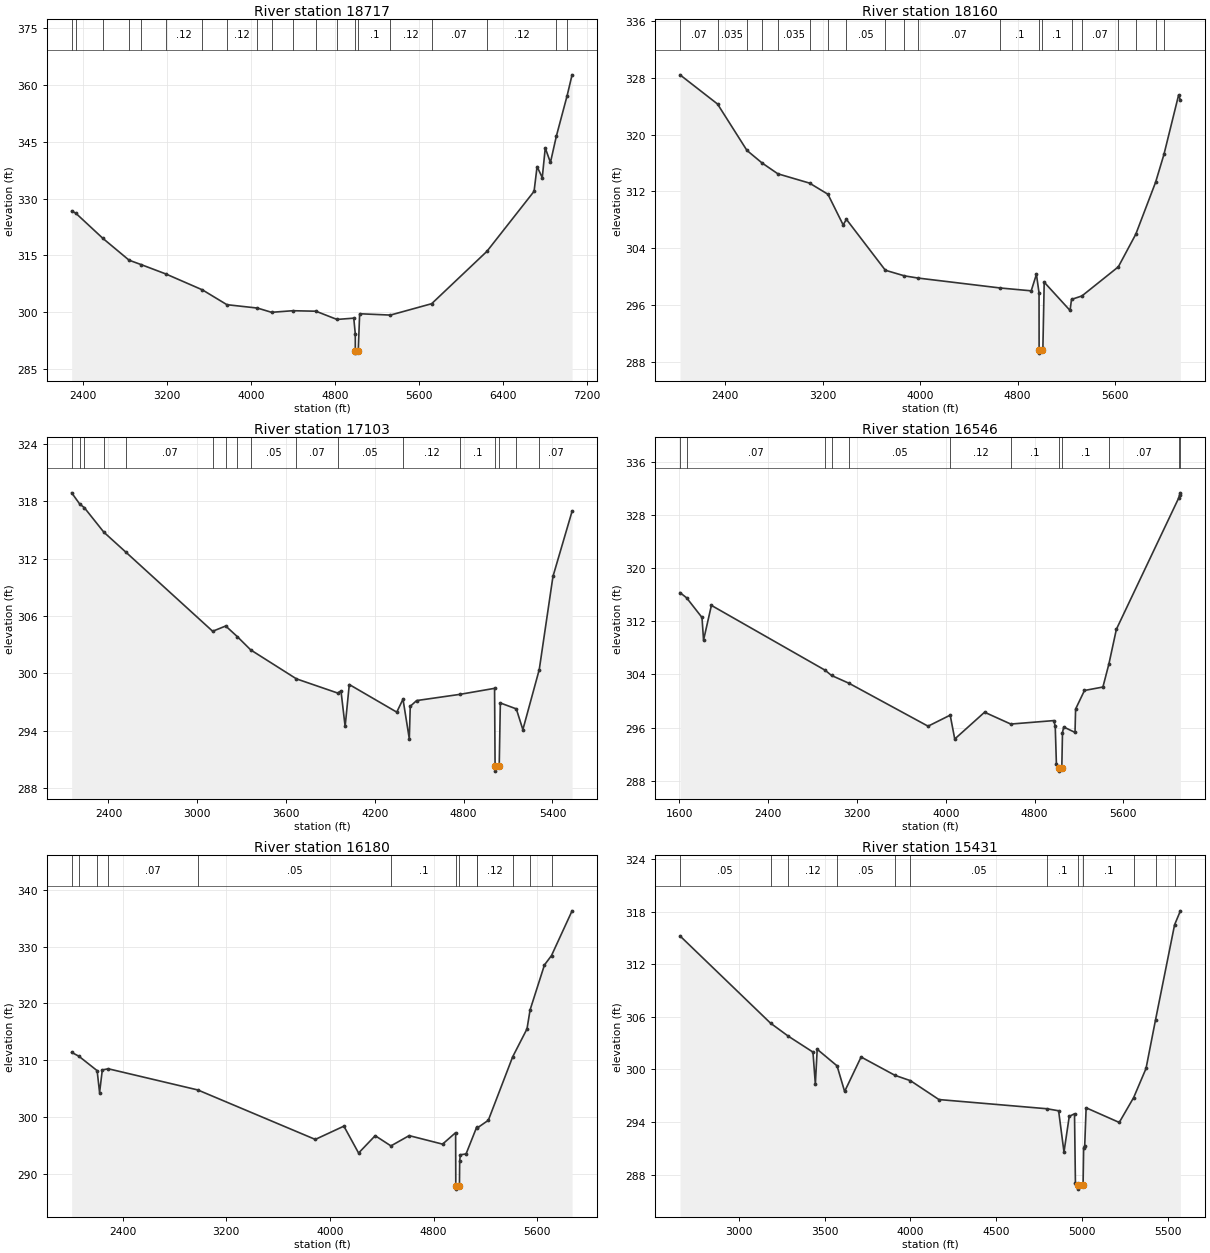
Type RM Length L Ch R = 1 ,18717   ,557,557,557
BEGIN DESCRIPTION:
BALDRIDGE CREEK 18.0
END DESCRIPTION:
XS GIS Cut Line= 3
       2524879.5     13789229.09      2522745.02     13787796.48
      2521075.04     13786375.03
#Sta/Elev= 30
  2293.3  326.73  2332.4  326.13  2590.5  319.49  2839.9  313.74  2956.3  312.56
  3189.1  310.12  3538.3  305.91  3771.2  302.01  4061.5  301.12  4196.3     300
  4397.9  300.42  4618.1  300.29  4818.9  298.12  4978.8  298.46  4993.1  294.32
  4993.6  289.74  4994.1  289.24  5021.1  289.74  5034.8  299.62  5327.5  299.27
  5720.3  302.27  6245.9  316.06  6695.2   331.9  6723.8  338.41  6773.2  335.52
  6801.7  343.32  6851.1   339.5  6907.1  346.42    7010  357.12    7057  362.61
#Mann= 20 ,-1 , 0
  2293.3     .07       0  2332.4     .12       0  2590.5    .035       0
  2839.9     .07       0  2956.3     .05       0  3189.1     .12       0
  3538.3     .05       0  3771.2     .12       0  4061.5     .05       0
  4196.3     .07       0  4397.9     .05       0  4618.1     .12       0
  4818.9      .1       0  4993.6     .05       0  5021.1      .1       0
  5327.5     .12       0  5720.3     .07       0  6245.9     .12       0
  6907.1     .07       0    7010    .035       0
Bank Sta=4993.6,5021.1
XS Rating Curve= 0 ,0
Exp/Cntr=0.3,0.1

Type RM Length L Ch R = 1 ,18160   ,1057,1057,1057
BEGIN DESCRIPTION:
BALDRIDGE CREEK 17.0
END DESCRIPTION:
XS GIS Cut Line= 3
      2525024.97     13789274.97        2522825.       13787275.
      2522025.03     13786475.03
#Sta/Elev= 30
  2031.1  328.44  2338.7  324.33    2580  317.79    2704  316.02  2833.8  314.49
  3093.6  313.18  3244.5  311.61    3369   307.3  3396.4  308.07  3715.4   300.9
    3872  300.11  3983.1   299.8  4658.1   298.4    4912     298  4954.6  300.33
  4976.2  297.71  4976.7  289.72  4977.2  289.22  5004.2  289.72  5007.8  290.01
  5018.4  299.22  5230.5  295.23  5242.5  296.79    5328  297.28  5626.5  301.38
  5769.7  305.98  5932.1   313.3  6000.6  317.22  6121.5  325.63  6135.6  324.84
#Mann= 20 ,-1 , 0
  2031.1     .07       0  2338.7    .035       0    2580     .07       0
    2704    .035       0  2833.8    .035       0  3093.6    .035       0
  3244.5    .035       0  3396.4     .05       0  3715.4     .07       0
    3872     .05       0  3983.1     .07       0  4658.1      .1       0
  4976.7     .05       0  5004.2      .1       0  5242.5     .12       0
    5328     .07       0  5626.5     .07       0  5769.7     .07       0
  5932.1    .035       0  6000.6     .07       0
Bank Sta=4976.7,5004.2
XS Rating Curve= 0 ,0
Exp/Cntr=0.3,0.1

Type RM Length L Ch R = 1 ,17103   ,557,557,557
BEGIN DESCRIPTION:
BALDRIDGE CREEK 16.0
END DESCRIPTION:
XS GIS Cut Line= 3
      2524774.97     13788574.96        2522975.       13786375.
        2522475.       13786175.
#Sta/Elev= 30
  2151.4  318.87    2206  317.69  2236.2  317.33  2368.9  314.75  2519.3  312.64
    3104  304.39  3192.1  304.94  3271.1  303.82    3361  302.44  3670.2  299.41
  3948.2  297.93    3971  298.15    3999  294.43    4027  298.82  4347.9  295.93
    4390  297.29  4432.6  293.14    4439  296.54  4482.1  297.14  4774.6  297.79
  5008.7  298.42  5012.2  290.26  5012.7  289.76  5040.1  290.26  5047.7  296.89
  5155.6  296.27  5199.9   294.1  5310.6  300.38  5403.2  310.12  5532.4  316.94
#Mann= 17 ,-1 , 0
  2151.4     .07       0    2206     .05       0  2236.2     .07       0
  2368.9     .05       0  2519.3     .07       0    3104    .035       0
  3192.1     .05       0  3271.1    .035       0    3361     .05       0
  3670.2     .07       0  3948.2     .05       0    4390     .12       0
  4774.6      .1       0  5012.2     .05       0  5040.1      .1       0
  5155.6     .12       0  5310.6     .07       0
Bank Sta=5012.2,5040.1
XS Rating Curve= 0 ,0
Exp/Cntr=0.3,0.1

Type RM Length L Ch R = 1 ,16546   ,366,366,366
BEGIN DESCRIPTION:
BALDRIDGE CREEK 15.0
END DESCRIPTION:
XS GIS Cut Line= 3
      2525274.98     13788274.98        2522875.       13785875.
      2521802.73     13785575.48
#Sta/Elev= 30
  1605.8  316.31  1665.2  315.53  1803.8  312.57  1817.9  309.17  1888.6  314.39
  2912.7  304.64  2970.6  303.85  3128.8  302.67  3840.2  296.22  4039.6  297.88
  4080.6  294.29  4349.3  298.32  4585.4  296.54  4971.6  297.06  4985.7  296.26
  4996.3  290.56    5017  289.96  5017.5  289.46    5045  289.96  5051.1  295.27
  5062.2   296.1    5164  295.28  5169.2   298.8  5249.1  301.59  5415.2  302.11
  5468.9  305.56  5536.7   310.8  6096.5  330.49  6105.3  330.94  6113.2  331.32
#Mann= 12 ,-1 , 0
  1605.8    .035       0  1665.2     .07       0  2912.7     .05       0
  2970.6     .07       0  3128.8     .05       0  4039.6     .12       0
  4585.4      .1       0    5017     .05       0    5045      .1       0
  5468.9     .07       0  6096.5     .12       0  6105.3     .07       0
Bank Sta=5017,5045
XS Rating Curve= 0 ,0
Exp/Cntr=0.3,0.1

Type RM Length L Ch R = 1 ,16180   ,749,749,749
BEGIN DESCRIPTION:
BALDRIDGE CREEK 14.0
END DESCRIPTION:
XS GIS Cut Line= 3
      2525398.69      13787604.2      2523177.68     13785806.24
      2522687.34     13784931.32
#Sta/Elev= 30
  2007.7  311.35  2063.5  310.67  2204.1  308.13  2222.9  304.26    2244  308.26
  2290.3  308.46  2980.7  304.73  3887.1  296.01  4107.7  298.35  4221.2  293.61
  4349.2  296.67  4470.6  294.87  4611.4  296.68  4868.8  295.18  4969.8   297.2
  4971.1  287.75  4971.6  287.25  4999.2  287.75  5001.1  292.28  5006.8  293.31
  5050.2  293.45  5131.3  298.12    5136  298.02    5222  299.38  5409.9  310.57
  5520.4  315.49  5544.3  318.84  5655.1  326.76  5709.5  328.42  5868.2   336.3
#Mann= 13 ,-1 , 0
  2007.7     .05       0  2063.5     .07       0  2204.1     .12       0
  2290.3     .07       0  2980.7     .05       0  4470.6      .1       0
  4971.1     .05       0  4999.2      .1       0  5131.3     .07       0
    5136     .12       0  5409.9     .07       0  5544.3     .12       0
  5709.5     .07       0
Bank Sta=4971.1,4999.2
XS Rating Curve= 0 ,0
Exp/Cntr=0.3,0.1

Type RM Length L Ch R = 1 ,15431   ,549,549,549
BEGIN DESCRIPTION:
BALDRIDGE CREEK 13.0
END DESCRIPTION:
XS GIS Cut Line= 3
      2525975.03     13786625.01        2523775.       13785825.
      2523424.98     13785374.97
#Sta/Elev= 30
  2659.3  315.22  3185.8  305.28  3289.5  303.79  3432.8  301.98  3446.7  298.32
  3457.4   302.3    3573  300.41    3617  297.49  3712.8  301.42  3909.9  299.33
    4000  298.72  4165.6  296.57  4794.4  295.52  4861.9  295.29  4893.2  290.59
  4923.8  294.65  4954.4  294.95  4959.7  287.08  4976.2  286.86  4976.7  286.36
  5004.3  286.86  5007.5  291.09  5013.8  291.32    5022  295.63  5214.7  293.96
  5298.6   296.8  5370.4  300.11  5426.1  305.69  5536.6  316.49  5570.4  318.08
#Mann= 12 ,-1 , 0
  2659.3     .05       0  3185.8    .035       0  3289.5     .12       0
    3573     .05       0  3909.9     .07       0    4000     .05       0
  4794.4      .1       0  4976.2     .05       0  5004.3      .1       0
  5298.6     .12       0  5426.1     .07       0  5536.6     .12       0
Bank Sta=4976.2,5004.3
XS Rating Curve= 0 ,0
Exp/Cntr=0.3,0.1

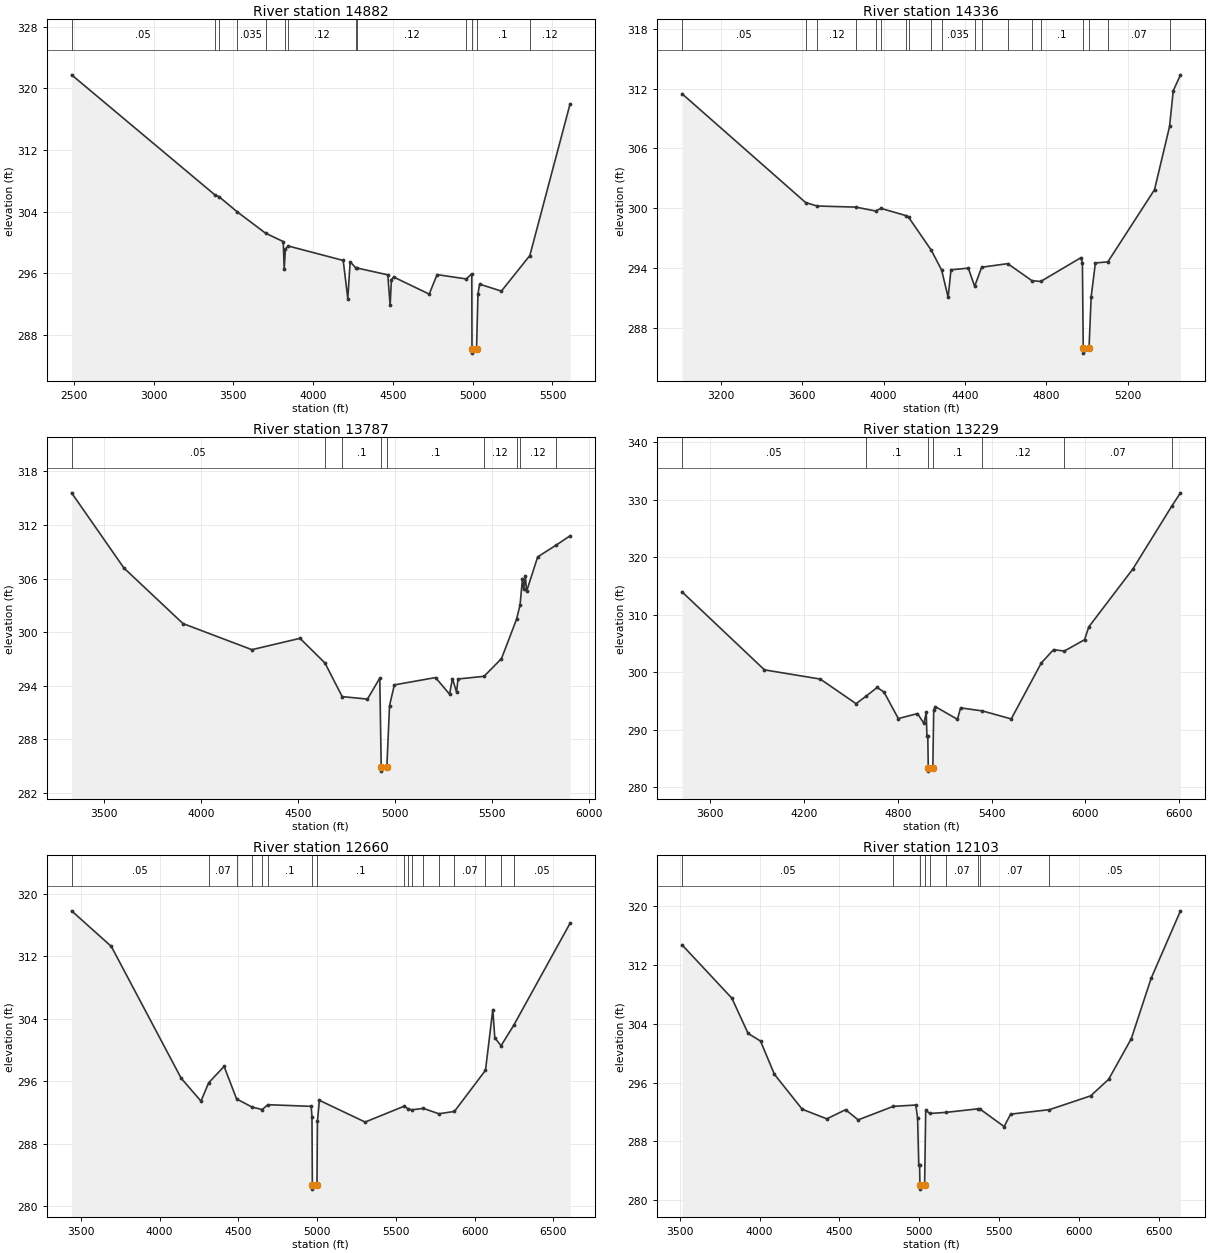
Type RM Length L Ch R = 1 ,14882   ,546,546,546
BEGIN DESCRIPTION:
BALDRIDGE CREEK 12.0
END DESCRIPTION:
XS GIS Cut Line= 3
        2526275.       13786675.        2524075.       13785475.
      2523474.96     13785324.99
#Sta/Elev= 30
  2485.9  321.76  3384.7  306.17  3409.7  305.95  3524.5  303.97  3701.6  301.21
  3812.5  300.12  3818.6  296.56  3825.9   299.1  3843.1  299.55  4188.4  297.67
  4217.3  292.71    4232   297.5  4268.6  296.67  4276.5  296.68  4467.9   295.8
  4482.6  291.83  4490.7  295.16  4504.5  295.52  4727.5   293.3  4776.9  295.83
  4959.5  295.27  4994.5  295.94  4995.7  286.14  4996.2  285.64  5024.1  286.14
  5033.1  293.32  5043.4  294.59    5180  293.69  5358.3  298.31  5610.4  317.98
#Mann= 13 ,-1 , 0
  2485.9     .05       0  3384.7     .12       0  3409.7     .05       0
  3524.5    .035       0  3701.6     .12       0  3825.9     .05       0
  3843.1     .12       0  4268.6     .07       0  4276.5     .12       0
  4959.5      .1       0  4995.7     .05       0  5024.1      .1       0
  5358.3     .12       0
Bank Sta=4995.7,5024.1
XS Rating Curve= 0 ,0
Exp/Cntr=0.3,0.1

Type RM Length L Ch R = 1 ,14336   ,549,549,549
BEGIN DESCRIPTION:
BALDRIDGE CREEK 11.0
END DESCRIPTION:
XS GIS Cut Line= 3
      2525675.01     13786225.01        2524125.       13784975.
      2523775.02     13784675.01
#Sta/Elev= 30
  3008.2   311.5  3616.2  300.57  3672.6  300.22  3863.6  300.11  3960.5  299.72
  3987.3  299.98    4111  299.25  4122.9  299.09  4234.7  295.77  4285.4  293.78
  4317.3  291.05  4331.4  293.81  4416.5  293.98  4447.8  292.15  4482.2  294.07
  4610.3  294.43  4729.6  292.72  4772.7  292.64  4971.4  295.04  4977.9  294.46
    4982  285.94  4982.5  285.44  5010.5  285.94  5020.8  291.07  5041.7   294.5
  5103.1  294.61  5332.6  301.86  5406.6  308.21  5424.7   311.8  5460.4   313.4
#Mann= 19 ,-1 , 0
  3008.2     .05       0  3616.2    .035       0  3672.6     .12       0
  3863.6    .035       0  3960.5     .12       0  3987.3    .035       0
    4111     .12       0  4122.9    .035       0  4234.7     .12       0
  4285.4    .035       0  4447.8     .12       0  4482.2    .035       0
  4610.3     .12       0  4729.6    .035       0  4772.7      .1       0
    4982     .05       0  5010.5      .1       0  5103.1     .07       0
  5406.6     .12       0
Bank Sta=4982,5010.5
XS Rating Curve= 0 ,0
Exp/Cntr=0.3,0.1

Type RM Length L Ch R = 1 ,13787   ,558,558,558
BEGIN DESCRIPTION:
BALDRIDGE CREEK 10.0
END DESCRIPTION:
XS GIS Cut Line= 3
      2525825.01     13786075.01        2524575.       13784975.
      2523824.98     13784474.99
#Sta/Elev= 30
  3335.2   315.6  3604.2   307.2  3908.8  300.97  4263.6  298.05  4511.2  299.32
  4639.7  296.56  4728.4   292.8  4858.5  292.52    4922  294.87  4929.3  284.96
  4929.8  284.46  4958.4  284.96  4972.3   291.8    4997  294.11  5209.1  294.93
  5281.2  293.07  5296.2  294.81  5317.3  293.31  5324.8  294.77  5458.9  295.07
  5548.6  297.05  5626.3  301.46  5644.1  303.03  5656.8  306.01  5662.8  304.81
  5671.8  306.28  5677.8  304.58  5734.9  308.43  5829.4  309.74  5901.7  310.79
#Mann= 9 ,-1 , 0
  3335.2     .05       0  4639.7     .12       0  4728.4      .1       0
  4929.3     .05       0  4958.4      .1       0  5458.9     .12       0
  5626.3     .07       0  5644.1     .12       0  5829.4     .07       0
Bank Sta=4929.3,4958.4
XS Rating Curve= 0 ,0
Exp/Cntr=0.3,0.1

Type RM Length L Ch R = 1 ,13229   ,569,569,569
BEGIN DESCRIPTION:
BALDRIDGE CREEK 9.0
END DESCRIPTION:
XS GIS Cut Line= 3
      2525875.01     13785825.01        2524925.       13784575.
      2523324.96     13784324.99
#Sta/Elev= 30
  3419.5     314    3947  300.43  4304.3  298.83  4533.1  294.55    4596  295.83
  4668.3  297.37  4711.9  296.57  4803.5  291.96  4926.1  292.83  4967.7  291.11
  4982.3  293.06  4986.4  288.93  4992.1  288.93  4995.2  283.32  4995.7  282.82
  5024.3  283.32    5030  293.47  5040.1  294.04  5181.8  291.83  5202.1  293.82
  5341.7  293.29    5526   291.9  5718.3  301.63  5796.7  303.95  5865.6   303.7
  5995.1  305.67  6021.9  307.89  6305.3  318.02  6554.2  328.95    6609  331.22
#Mann= 7 ,-1 , 0
  3419.5     .05       0    4596      .1       0  4995.2     .05       0
  5024.3      .1       0  5341.7     .12       0  5865.6     .07       0
  6554.2     .05       0
Bank Sta=4995.2,5024.3
XS Rating Curve= 0 ,0
Exp/Cntr=0.3,0.1

Type RM Length L Ch R = 1 ,12660   ,557,557,557
BEGIN DESCRIPTION:
BALDRIDGE CREEK 8.0
END DESCRIPTION:
XS GIS Cut Line= 3
      2526874.97       13784425.        2525325.       13784225.
      2523725.01       13784275.
#Sta/Elev= 30
  3441.7  317.79  3693.7  313.24  4137.4  296.37  4262.8  293.45  4311.8   295.8
  4409.6  297.89    4489  293.72  4587.9  292.68  4651.7  292.37  4686.9  292.99
  4962.3  292.78  4967.3  291.46  4969.8  282.69  4970.3  282.19  4998.9  282.69
    5002   290.9  5014.5  293.55  5304.7  290.77  5553.8  292.81  5575.5  292.48
  5599.8  292.33  5674.1  292.52  5772.7  291.83  5871.3  292.13  6068.5  297.39
  6115.1  305.16  6127.6  301.56  6167.2  300.53  6247.7  303.15  6605.3   316.2
#Mann= 17 ,-1 , 0
  3441.7     .05       0  4311.8     .07       0    4489     .05       0
  4587.9      .1       0  4651.7     .07       0  4686.9      .1       0
  4969.8     .05       0  4998.9      .1       0  5553.8     .12       0
  5575.5     .07       0  5599.8     .12       0  5674.1     .07       0
  5772.7     .12       0  5871.3     .07       0  6068.5     .12       0
  6167.2     .07       0  6247.7     .05       0
Bank Sta=4969.8,4998.9
XS Rating Curve= 0 ,0
Exp/Cntr=0.3,0.1

Type RM Length L Ch R = 1 ,12103   ,1221,1221,1221
BEGIN DESCRIPTION:
BALDRIDGE CREEK 7.0
END DESCRIPTION:
XS GIS Cut Line= 3
      2526724.95     13784274.98        2525325.       13783775.
      2523724.99       13784125.
#Sta/Elev= 30
  3513.4  314.75  3826.1  307.48  3927.5  302.69  4005.5  301.65  4092.6  297.12
  4266.7  292.37  4420.7  291.06  4538.6   292.3  4617.7  290.92  4837.5  292.76
  4978.7  292.94  4989.9  291.21  4997.3  284.72  5002.5  284.72  5004.7  281.99
  5005.2  281.49  5033.9  281.99  5040.9  292.21    5067  291.79  5168.4  291.94
  5371.3  292.43  5379.9  292.41  5532.3  290.01  5573.2   291.7  5816.6  292.31
  6074.8  294.19  6187.4  296.44  6329.6  301.98  6453.5  310.18  6637.8  319.38
#Mann= 9 ,-1 , 0
  3513.4     .05       0  4837.5      .1       0  5004.7     .05       0
  5033.9      .1       0    5067     .12       0  5168.4     .07       0
  5371.3     .12       0  5379.9     .07       0  5816.6     .05       0
Bank Sta=5004.7,5033.9
XS Rating Curve= 0 ,0
Exp/Cntr=0.3,0.1

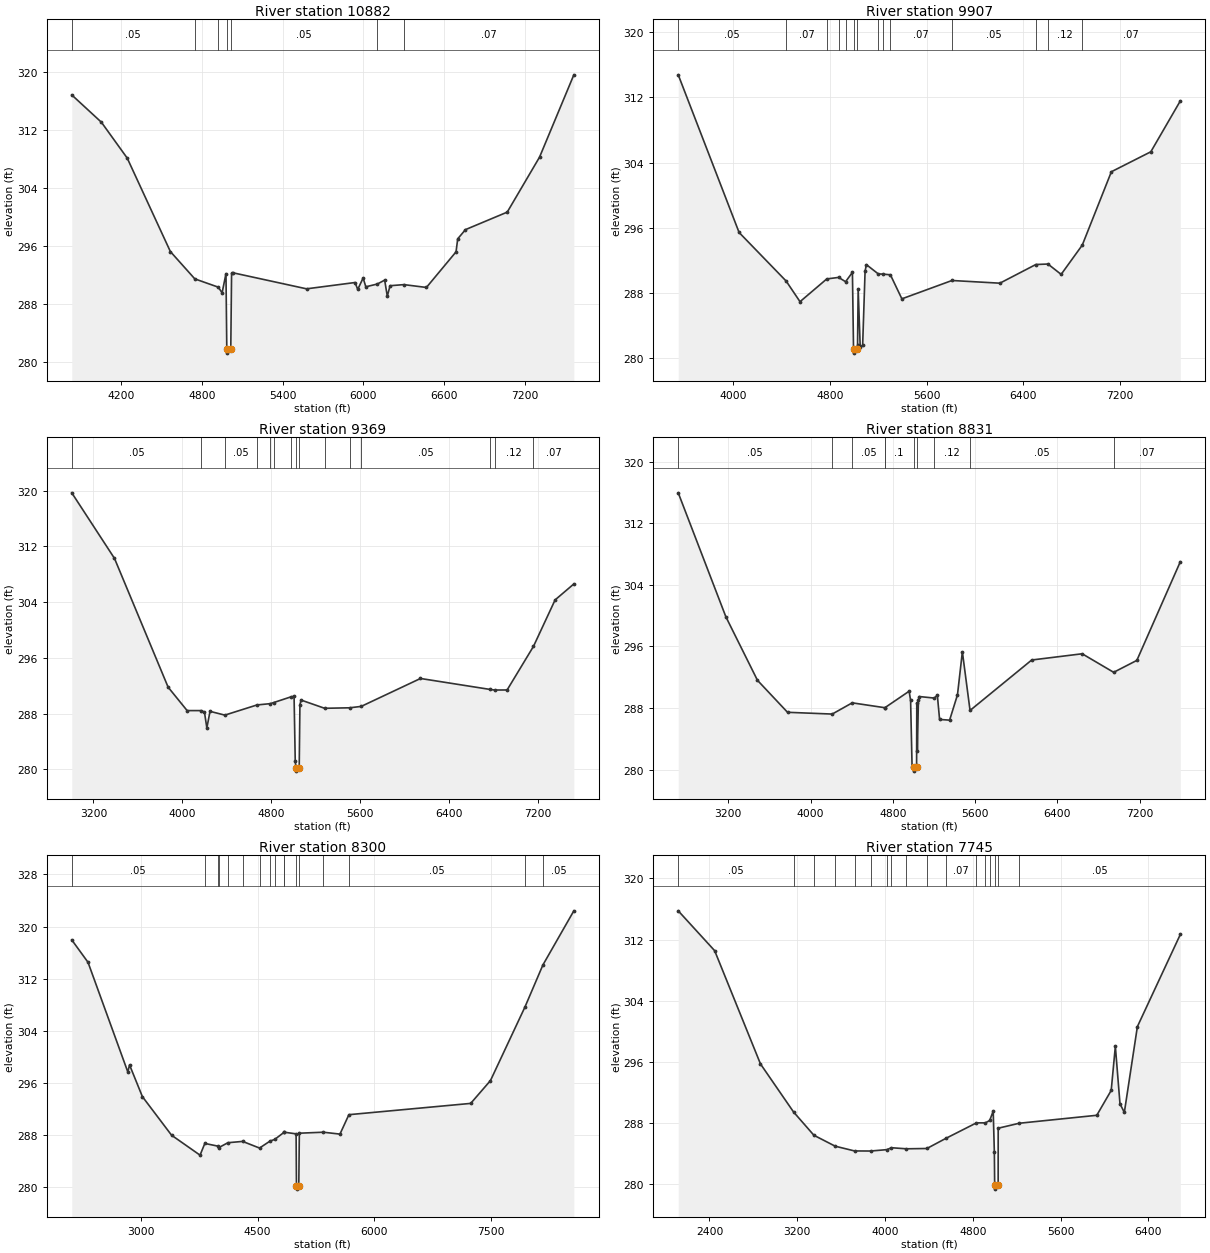
Type RM Length L Ch R = 1 ,10882   ,975,975,975
BEGIN DESCRIPTION:
X18072
END DESCRIPTION:
XS GIS Cut Line= 3
      2527013.91     13784075.58      2525840.95     13783142.97
      2523610.36     13783056.44
#Sta/Elev= 30
  3833.3  316.84  4053.3  313.08  4245.5  308.13  4565.9  295.26  4747.7  291.49
    4922  290.35  4950.4  289.57  4979.2  292.22  4985.3  281.76  4985.8  281.26
  5014.8  281.76  5020.8  292.24  5028.9  292.34    5578  290.12  5938.2  290.99
  5958.3  290.04  5998.3  291.62  6018.3   290.4  6103.4  290.78  6158.4  291.32
  6177.9   289.1  6198.4  290.55  6301.5   290.7  6468.6  290.31  6688.8  295.22
  6701.1  297.01  6758.9  298.28  7069.1  300.69  7309.3  308.27  7564.1  319.61
#Mann= 7 ,-1 , 0
  3833.3     .05       0  4747.7     .07       0    4922     .05       0
  4985.3     .05       0  5014.8     .05       0  6103.4     .12       0
  6301.5     .07       0
Bank Sta=4985.3,5014.8
XS Rating Curve= 0 ,0
Exp/Cntr=0.3,0.1

Type RM Length L Ch R = 1 ,9907    ,538,538,538
BEGIN DESCRIPTION:
BALDRIDGE CREEK 6.0
END DESCRIPTION:
XS GIS Cut Line= 3
        2527575.       13783525.        2526475.       13782575.
      2523812.25     13782998.75
#Sta/Elev= 30
  3546.6  314.77  4049.6  295.43  4438.6  289.47  4553.1  286.94  4774.1  289.73
  4872.4  289.92  4929.7  289.39  4986.3  290.54  4995.4  281.13  4995.9  280.63
  5024.9  281.13  5028.6   281.6  5033.7  288.53  5050.7  281.35  5070.9  281.64
  5090.8  290.65  5101.3  291.49  5199.9  290.35  5240.5  290.32  5300.1  290.24
    5395  287.29  5809.1  289.54    6205  289.21  6502.1   291.5  6602.3  291.56
  6711.3  290.29    6886  293.88  7126.5  302.88  7452.6  305.33  7696.3  311.57
#Mann= 14 ,-1 , 0
  3546.6     .05       0  4438.6     .07       0  4774.1     .05       0
  4872.4     .07       0  4929.7     .05       0  4995.4     .05       0
  5024.9     .05       0  5199.9     .07       0  5240.5     .05       0
  5300.1     .07       0  5809.1     .05       0  6502.1     .07       0
  6602.3     .12       0    6886     .07       0
Bank Sta=4995.4,5024.9
XS Rating Curve= 0 ,0
Exp/Cntr=0.3,0.1

Type RM Length L Ch R = 1 ,9369    ,538,538,538
BEGIN DESCRIPTION:
BALDRIDGE CREEK 5.0
END DESCRIPTION:
XS GIS Cut Line= 3
        2527825.       13783625.        2526575.       13782075.
      2524174.96     13782875.01
#Sta/Elev= 30
  3004.9  319.68  3389.5  310.27  3872.6  291.78  4043.7  288.42  4168.7  288.42
  4199.6  288.21  4221.2  285.94    4250  288.31  4383.3  287.77    4673  289.23
  4794.3  289.42  4824.6  289.58  4976.2  290.38  5006.7  290.47  5017.2  281.19
  5023.5  280.23    5024  279.73    5053  280.23  5059.4  289.27  5069.9  289.93
    5282  288.75  5506.3  288.82  5611.1  289.02  6145.1  293.03  6774.4  291.45
  6813.8  291.37  6925.1  291.38  7162.5  297.64  7357.3  304.31    7526   306.6
#Mann= 15 ,-1 , 0
  3004.9     .05       0  4168.7     .07       0  4383.3     .05       0
    4673     .07       0  4794.3     .05       0  4824.6     .07       0
  4976.2      .1       0  5023.5     .05       0    5053      .1       0
    5282     .12       0  5506.3     .07       0  5611.1     .05       0
  6774.4     .07       0  6813.8     .12       0  7162.5     .07       0
Bank Sta=5023.5,5053
XS Rating Curve= 0 ,0
Exp/Cntr=0.3,0.1

Type RM Length L Ch R = 1 ,8831    ,531,531,531
BEGIN DESCRIPTION:
BALDRIDGE CREEK 4.0
END DESCRIPTION:
XS GIS Cut Line= 3
      2528025.02     13783425.02        2526625.       13781625.
      2524224.98     13782625.01
#Sta/Elev= 30
  2713.4  315.98  3176.7  299.85  3483.5   291.6  3775.8  287.44  4210.2  287.21
  4404.6  288.67  4720.1  288.04  4722.5  288.04  4957.6  290.18  4972.1  288.99
  4986.5  280.33  5000.5  280.29    5001  279.79  5030.3  280.29  5032.2  288.66
  5037.7  282.38  5047.9  289.02  5056.1  289.49  5202.9  289.29  5232.1  289.66
  5253.8  286.51  5351.3  286.42  5427.7  289.71  5475.3  295.31  5549.9  287.68
  6149.2  294.24  6639.9  295.05    6946  292.64  7171.3  294.19  7593.8  307.02
#Mann= 10 ,-1 , 0
  2713.4     .05       0  4210.2     .07       0  4404.6     .05       0
  4720.1     .12       0  4722.5      .1       0  5000.5     .05       0
  5030.3      .1       0  5202.9     .12       0  5549.9     .05       0
    6946     .07       0
Bank Sta=5000.5,5030.3
XS Rating Curve= 0 ,0
Exp/Cntr=0.3,0.1

Type RM Length L Ch R = 1 ,8300    ,555,555,555
BEGIN DESCRIPTION:
BALDRIDGE CREEK 3.0
END DESCRIPTION:
XS GIS Cut Line= 3
      2528325.03     13783525.04        2526725.       13781125.
        2523525.       13782725.
#Sta/Elev= 30
  2108.5  317.95  2317.4  314.52  2829.7   297.7  2852.2  298.77  3017.4  293.91
    3393  287.99  3759.6  284.93    3821  286.73  3991.3  286.31  3997.8  286.07
  4118.4  286.84  4307.9  287.04  4525.1  286.02  4660.2  287.09  4721.1  287.35
  4841.6  288.44  4843.1  288.45  4995.8   288.2  5000.5  280.22    5001  279.72
  5030.3  280.22  5037.7   288.3  5346.7  288.45  5560.4  288.16  5675.4  291.14
    7243  292.87  7497.4  296.37  7940.8  307.64  8172.6  314.11  8570.7  322.41
#Mann= 17 ,-1 , 0
  2108.5     .05       0    3821     .07       0  3991.3     .12       0
  3997.8     .07       0  4118.4     .05       0  4307.9     .12       0
  4525.1     .07       0  4660.2     .12       0  4721.1     .07       0
  4841.6     .12       0  4843.1      .1       0  5000.5     .05       0
  5030.3      .1       0  5346.7     .12       0  5675.4     .05       0
  7940.8     .07       0  8172.6     .05       0
Bank Sta=5000.5,5030.3
XS Rating Curve= 0 ,0
Exp/Cntr=0.3,0.1

Type RM Length L Ch R = 1 ,7745    ,2749,2749,2749
BEGIN DESCRIPTION:
BALDRIDGE CREEK 2.0
END DESCRIPTION:
XS GIS Cut Line= 3
      2528475.01     13783025.01        2526875.       13780625.
      2525275.04     13780075.01
#Sta/Elev= 30
  2115.4  315.75  2447.4  310.54  2865.1  295.74  3166.6  289.46    3352  286.42
  3546.3  284.99  3722.3  284.37  3869.3  284.36  4017.1  284.54    4059  284.79
  4194.1  284.65  4381.9  284.69  4553.1     286  4833.7  288.04  4914.8  288.04
  4954.2  288.35  4986.3  289.58  4996.8  284.19  4999.6  279.88  5000.1  279.38
  5031.4  279.88  5031.6  287.34  5223.6  287.99  5930.4  289.03  6061.8  292.28
  6099.6  298.04  6141.9  290.53  6181.5   289.4  6300.5  300.62  6691.7  312.66
#Mann= 17 ,-1 , 0
  2115.4     .05       0  3166.6     .07       0    3352     .05       0
  3546.3     .07       0  3722.3     .05       0  3869.3     .12       0
  4017.1     .07       0    4059     .12       0  4194.1     .07       0
  4381.9     .12       0  4553.1     .07       0  4833.7     .12       0
  4914.8     .07       0  4954.2      .1       0  4999.6     .05       0
  5031.4      .1       0  5223.6     .05       0
Bank Sta=4999.6,5031.4
XS Rating Curve= 0 ,0
Exp/Cntr=0.3,0.1

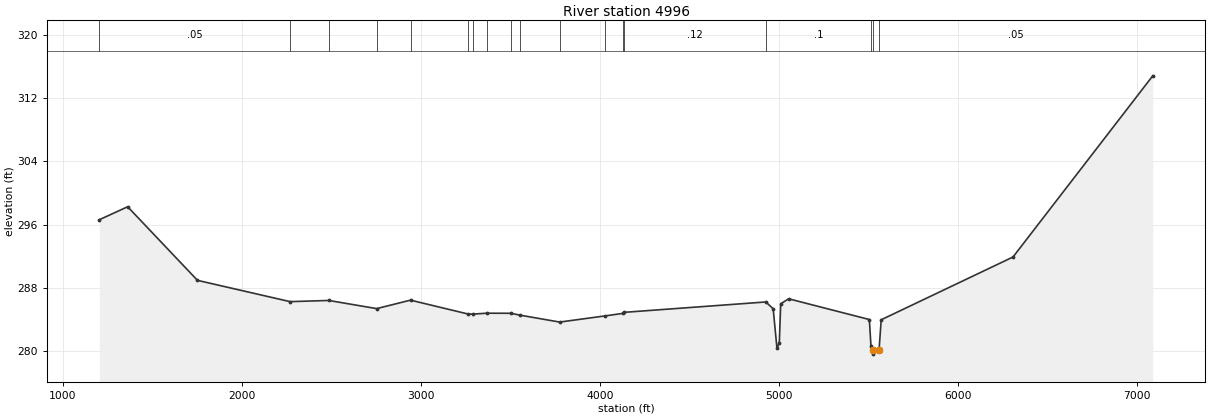
Type RM Length L Ch R = 1 ,4996    ,0,0,0
BEGIN DESCRIPTION:
BALDRIDGE CREEK 1.0
END DESCRIPTION:
XS GIS Cut Line= 3
        2528375.     13782174.99        2527175.       13778575.
      2525174.99       13779175.
#Sta/Elev= 30
  1205.3  296.63  1363.4  298.27  1753.4  288.97  2270.8  286.28  2486.6  286.43
    2754   285.4    2943  286.47  3265.8  284.71  3293.8  284.71    3369  284.82
  3503.2  284.81    3553  284.58  3776.2   283.7  4026.9  284.47  4127.4  284.79
  4136.2  284.93  4927.3  286.24  4968.4  285.38  4989.5   280.4  5002.6  281.05
  5010.5  286.01  5054.8  286.64  5505.5  284.02  5514.5  280.66  5527.9  280.15
  5528.4  279.65  5559.7  280.15  5571.6  283.99  6307.7  291.92  7088.1  314.81
#Mann= 18 ,-1 , 0
  1205.3     .05       0  2270.8     .12       0  2486.6     .07       0
    2754     .12       0    2943      .1       0  3265.8     .12       0
  3293.8     .07       0    3369     .12       0  3503.2     .07       0
    3553     .12       0  3776.2      .1       0  4026.9     .07       0
  4127.4      .1       0  4136.2     .12       0  4927.3      .1       0
  5514.5     .05       0  5527.9     .05       0  5559.7     .05       0
Bank Sta=5527.9,5559.7
XS Rating Curve= 0 ,0
Exp/Cntr=0.3,0.1

Chan Stop Cuts=-1
Use User Specified Reach Order=0
Composite Channel Slope=5