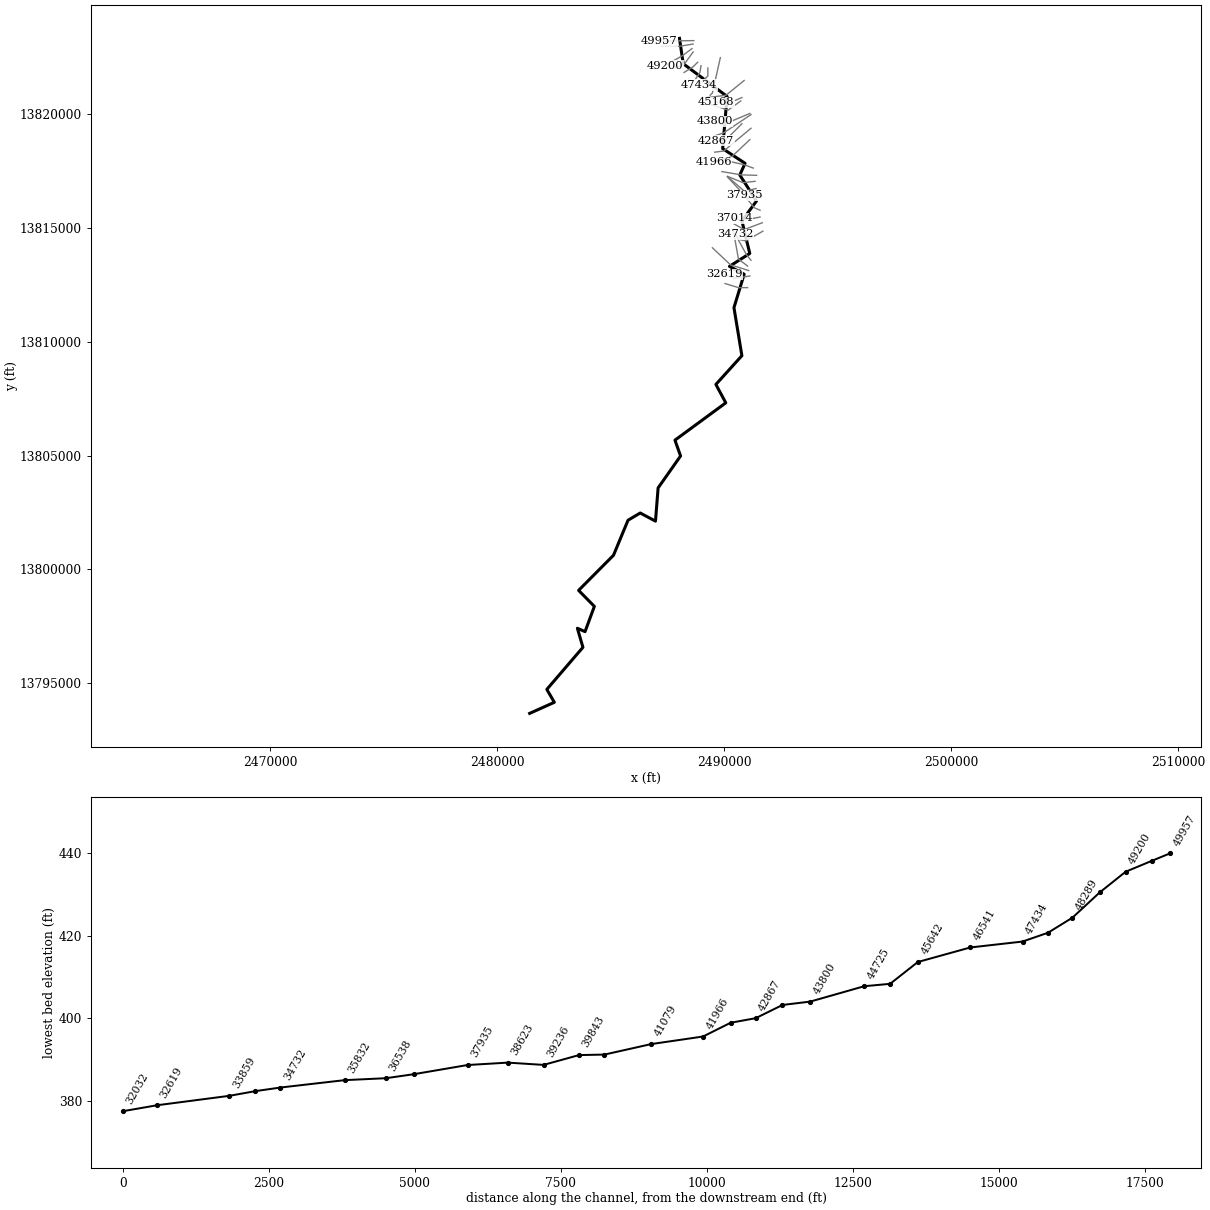
--- BEE BRANCH.prj (project) ---

Proj Title=BEE BRANCH Base Level Engineering
Current Plan=p01
Default Exp/Contr=0.3,0.1
English Units
Geom File=g01
Flow File=f01
Plan File=p01
Y Axis Title=Elevation
X Axis Title(PF)=Main Channel Distance
X Axis Title(XS)=Station
BEGIN DESCRIPTION:
BEE BRANCH
END DESCRIPTION:
DSS Export Rating Curves= 0
DSS Export Rating Curve Sorted= 0
DSS Export Volume Flow Curves= 0
DXF OffsetX= 0
DXF OffsetY= 0
DXF ScaleX= 1
DXF ScaleY= 10

--- BEE BRANCH.p01 (plan) ---

Plan Title=Multiple Run
Short Identifier=Multiple
Geom File=g01
Flow File=f01
Subcritical Flow
K Sum by GR= 0
Std Step Tol= 0.01
Critical Tol= 0.01
Num of Std Step Trials= 20
Max Error Tol= 0.3
Flow Tol Ratio= 0.001
Split Flow NTrial= 30
Split Flow Tol= 0.02
Split Flow Ratio= 0.02
Log Output Level= 0
Friction Slope Method= 1
Unsteady Friction Slope Method= 2
Unsteady Bridges Friction Slope Method= 1
Parabolic Critical Depth
Global Vel Dist=  1 , 1 , 1
Global Log Level= 0
CheckData=True
Encroach Param= -1, 0, 0, 0
BEGIN DESCRIPTION:
Multiple Run
END DESCRIPTION:

--- BEE BRANCH.f01 (steady flow) ---

Flow Title=Multiple
Number of Profiles=7
Profile Names=10-year,25-year,50-year,1pct_min,100-year,1pct_plu,500-year
River Rch & RM= BEE BRANCH,Reach-1,49957
     854    1390    1879    1230    2454    4896    4141
River Rch & RM= BEE BRANCH,Reach-1,45642
    1118    1840    2505    1649    3289    6563    5617
River Rch & RM= BEE BRANCH,Reach-1,41079
    1300    2152    2941    1941    3874    7729    6657
River Rch & RM= BEE BRANCH,Reach-1,37014
    1478    2457    3368    2229    4447    8873    7681
River Rch & RM= BEE BRANCH,Reach-1,34732
    2088    3514    4855    3235    6454   12878   11301
River Rch & RM= BEE BRANCH,Reach-1,27925
    2287    3860    5345    3567    7117   14201   12506
River Rch & RM= BEE BRANCH,Reach-1,23860
    2404    4063    5630    3759    7500   14965   13190
River Rch & RM= BEE BRANCH,Reach-1,21505
    3147    5371    7491    5032   10039   20031   17866
River Rch & RM= BEE BRANCH,Reach-1,17637
    3181    5426    7566    5079   10135   20221   18020
River Rch & RM= BEE BRANCH,Reach-1,14562
    3519    6012    8391    5637   11247   22441   20022
River Rch & RM= BEE BRANCH,Reach-1,8403
    3511    5996    8364    5614   11201   22349   19911
Boundary for River Rch & Prof#=BEE BRANCH,Reach-1,1
Up Type=0
Dn Type=3
Dn Slope=0.0001
Boundary for River Rch & Prof#=BEE BRANCH,Reach-1,2
Up Type=0
Dn Type=3
Dn Slope=0.0001
Boundary for River Rch & Prof#=BEE BRANCH,Reach-1,3
Up Type=0
Dn Type=3
Dn Slope=0.0001
Boundary for River Rch & Prof#=BEE BRANCH,Reach-1,4
Up Type=0
Dn Type=3
Dn Slope=0.0001
Boundary for River Rch & Prof#=BEE BRANCH,Reach-1,5
Up Type=0
Dn Type=3
Dn Slope=0.0001
Boundary for River Rch & Prof#=BEE BRANCH,Reach-1,6
Up Type=0
Dn Type=3
Dn Slope=0.0001
Boundary for River Rch & Prof#=BEE BRANCH,Reach-1,7
Up Type=0
Dn Type=3
Dn Slope=0.0001

--- BEE BRANCH.g01 (geometry) ---

Geom Title=Existing Conditions
Program Version=4.10

River Reach=BEE BRANCH      ,Reach-1
Reach XY= 30
        2488025.       13823325.      2488188.47     13822211.43
      2490121.47     13820773.55       2489926.8     13818481.11
      2490914.05     13817835.02      2490682.48     13817321.43
       2491417.5     13816178.58      2490775.01     13815309.59
      2491121.39     13813876.03      2490225.38     13813309.84
      2490874.02     13812964.76      2490424.64     13811495.15
      2490774.08     13809385.48      2489628.47      13808123.5
       2490064.7      13807314.9        2487825.       13805675.
      2488072.86     13804980.97      2487083.02     13803578.31
      2486967.33     13802118.47      2486295.14     13802475.71
      2485757.94     13802158.97      2485117.14     13800618.83
      2483580.36      13799077.7        2484275.       13798375.
      2483864.22     13797264.55      2483526.51     13797413.56
      2483771.48     13796576.46      2482180.45     13794728.01
      2482511.84     13794161.27        2481425.       13793675.

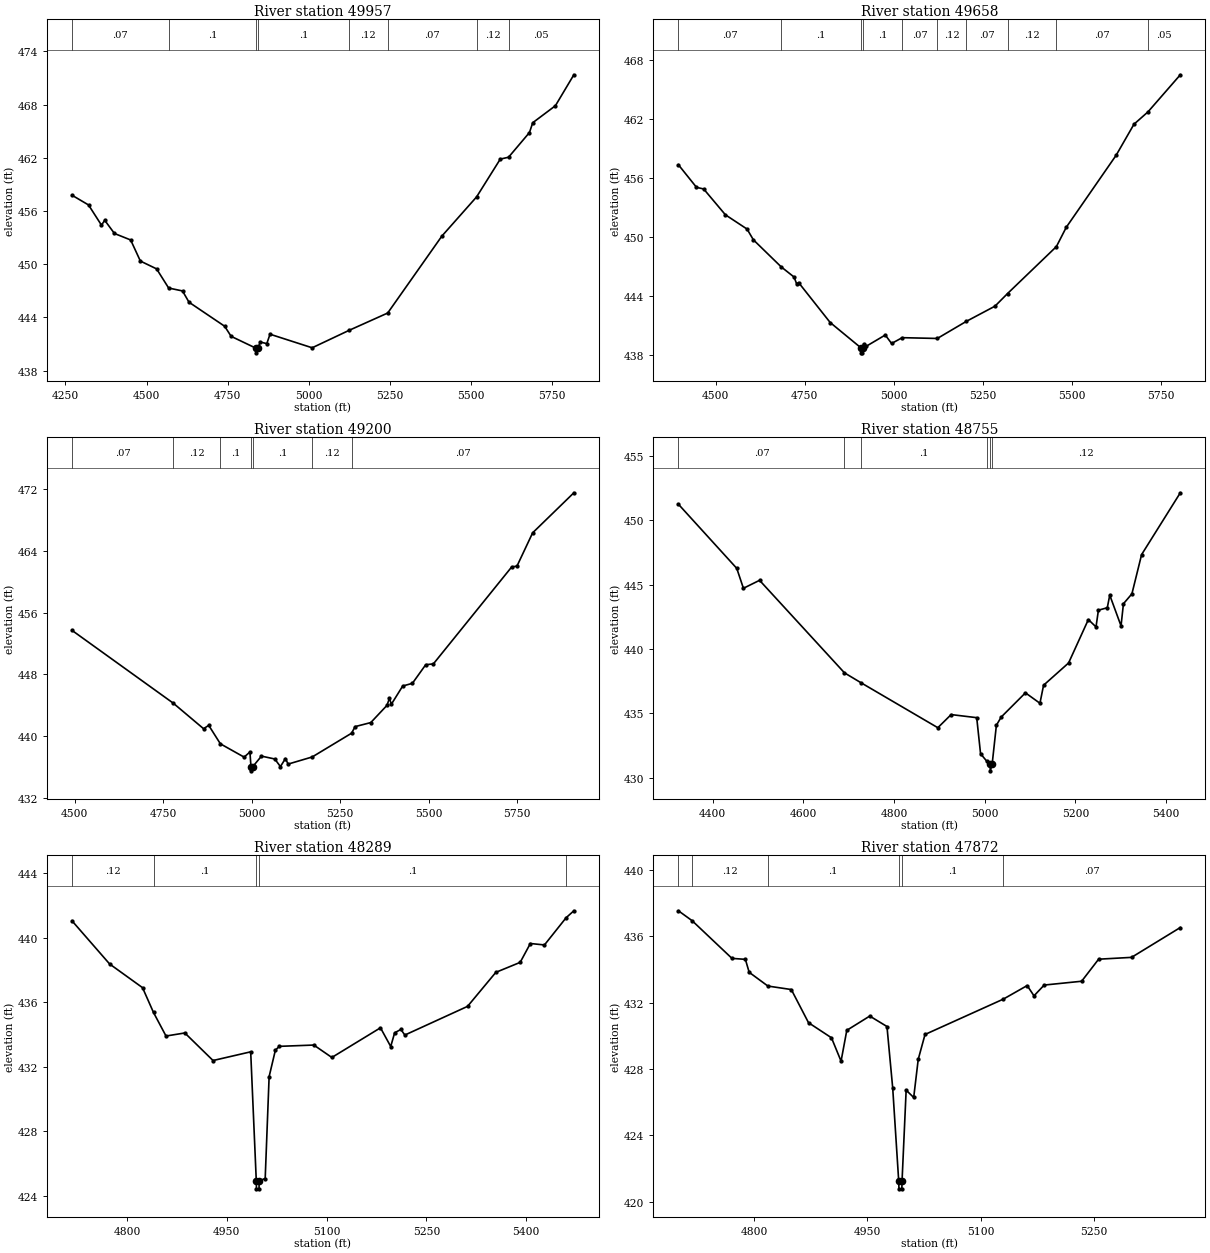
Type RM Length L Ch R = 1 ,49957   ,299,299,299
BEGIN DESCRIPTION:
X18183
END DESCRIPTION:
XS GIS Cut Line= 3
      2488656.09     13823224.74      2487839.08     13823214.84
      2487108.16     13823190.15
#Sta/Elev= 30
    4270  457.78  4321.1  456.68  4361.1   454.4  4371.1  454.95  4401.1  453.46
  4451.1  452.73  4481.1  450.35  4531.1  449.47  4568.3  447.31  4611.1  446.98
  4631.1  445.71  4741.1     443  4761.1  441.86    4839   440.5  4839.3     440
  4843.2   440.5  4851.1  441.22  4871.1  441.04  4881.1   442.1  5011.1  440.57
  5124.6  442.53  5244.1  444.49  5411.3  453.17  5518.4  457.59  5591.4  461.85
  5616.9  462.06  5681.5  464.85  5691.5  465.95  5761.5  467.87  5818.4  471.36
#Mann= 8 ,-1 , 0
    4270     .07       0  4568.3      .1       0    4839     .05       0
  4843.2      .1       0  5124.6     .12       0  5244.1     .07       0
  5518.4     .12       0  5616.9     .05       0
Bank Sta=4839,4843.2
XS Rating Curve= 0 ,0
Exp/Cntr=0.3,0.1

Type RM Length L Ch R = 1 ,49658   ,458,458,458
BEGIN DESCRIPTION:
BEE BRANCH 68.0
END DESCRIPTION:
XS GIS Cut Line= 3
      2488624.97     13823074.99        2488025.       13822975.
      2487225.04       13822975.
#Sta/Elev= 30
  4395.9  457.36  4446.6  455.07  4466.8   454.9  4527.7  452.28  4588.5  450.83
  4606.2  449.74  4684.3  446.99  4720.3  445.96  4727.9  445.24    4733   445.4
  4821.7  441.34  4908.3  438.76  4908.6  438.26  4912.2  438.26  4912.5  438.76
  4915.4  439.18    4923  438.93  4976.3  440.07    4994  439.21  5023.8   439.8
  5122.3  439.72  5203.9  441.46  5284.1     443  5319.3  444.28  5456.4  449.05
  5484.1  451.01  5624.1  458.33  5674.1  461.48  5713.3  462.73  5804.1   466.5
#Mann= 10 ,-1 , 0
  4395.9     .07       0  4684.3      .1       0  4908.3     .05       0
  4912.5      .1       0  5023.8     .07       0  5122.3     .12       0
  5203.9     .07       0  5319.3     .12       0  5456.4     .07       0
  5713.3     .05       0
Bank Sta=4908.3,4912.5
XS Rating Curve= 0 ,0
Exp/Cntr=0.3,0.1

Type RM Length L Ch R = 1 ,49200   ,445,445,445
BEGIN DESCRIPTION:
BEE BRANCH 67.0
END DESCRIPTION:
XS GIS Cut Line= 3
      2488574.98     13822874.98        2488175.       13822575.
      2487374.96     13822124.98
#Sta/Elev= 30
  4492.4   453.7  4778.8  444.29  4864.2     441  4878.8  441.43  4911.7  439.05
  4978.8  437.33  4995.2  437.99  4998.2  436.06  4998.5  435.56  5002.5  436.06
  5027.8  437.46  5065.4  437.09  5081.3  436.11  5095.6  437.15    5103  436.43
  5171.1  437.35  5282.4  440.42  5292.3  441.27  5336.6  441.79  5382.5  444.02
  5389.2  444.92  5394.9  444.17  5426.8  446.51  5454.2  446.86  5491.8  449.26
  5513.5  449.37  5734.6  461.88  5749.6  461.99  5793.9  466.29  5910.3  471.46
#Mann= 7 ,-1 , 0
  4492.4     .07       0  4778.8     .12       0  4911.7      .1       0
  4998.2     .05       0  5002.5      .1       0  5171.1     .12       0
  5282.4     .07       0
Bank Sta=4998.2,5002.5
XS Rating Curve= 0 ,0
Exp/Cntr=0.3,0.1

Type RM Length L Ch R = 1 ,48755   ,466,466,466
BEGIN DESCRIPTION:
BEE BRANCH 66.0
END DESCRIPTION:
XS GIS Cut Line= 3
      2488625.03     13822725.04        2488225.       13822175.
      2487825.02     13822025.01
#Sta/Elev= 30
  4324.2  451.24  4452.9  446.26  4467.6  444.71  4503.2  445.33  4690.6  438.14
  4726.7  437.38  4896.5  433.88  4925.9   434.9  4982.3  434.66  4990.8  431.86
  5004.2  431.29  5011.9  431.03  5012.2  430.53  5016.3  431.03  5025.7  434.07
  5036.4  434.71  5089.8  436.59  5121.8  435.78  5129.8  437.18    5185  438.91
  5228.6  442.28  5245.5  441.71  5250.8  443.01  5270.4   443.2  5275.8  444.18
  5300.7  441.79    5306  443.51  5324.7  444.28  5346.1  447.33  5431.5  452.13
#Mann= 6 ,-1 , 0
  4324.2     .07       0  4690.6     .12       0  4726.7      .1       0
  5004.2     .12       0  5011.9     .05       0  5016.3     .12       0
Bank Sta=5011.9,5016.3
XS Rating Curve= 0 ,0
Exp/Cntr=0.3,0.1

Type RM Length L Ch R = 1 ,48289   ,417,417,417
BEGIN DESCRIPTION:
BEE BRANCH 65.0
END DESCRIPTION:
XS GIS Cut Line= 3
      2488824.99     13822274.99        2488625.       13822075.
      2488225.03     13821825.02
#Sta/Elev= 30
  4717.2  441.05  4773.8  438.37  4823.3   436.9  4839.8  435.36  4858.6   433.9
  4886.9  434.09  4929.3  432.38  4985.9  432.92  4994.3  424.92  4994.6  424.42
  4998.4  424.42  4998.7  424.92  5007.7  425.06  5013.6  431.38    5023  433.02
  5028.9  433.26  5080.8  433.34  5107.9  432.57    5181  434.41  5196.4  433.25
  5202.3   434.1  5211.7  434.31  5217.6  433.96  5311.9  435.74  5354.4  437.85
    5391  438.47  5406.3  439.64  5427.5  439.55  5460.1  441.24  5471.7  441.67
#Mann= 5 ,-1 , 0
  4717.2     .12       0  4839.8      .1       0  4994.3     .05       0
  4998.7      .1       0  5460.1     .12       0
Bank Sta=4994.3,4998.7
XS Rating Curve= 0 ,0
Exp/Cntr=0.3,0.1

Type RM Length L Ch R = 1 ,47872   ,438,438,438
BEGIN DESCRIPTION:
BEE BRANCH 64.0
END DESCRIPTION:
XS GIS Cut Line= 3
        2488975.     13822124.97        2488925.       13821825.
      2488724.98     13821524.97
#Sta/Elev= 30
  4699.9  437.54  4718.1  436.94  4770.8  434.67  4788.6  434.61  4793.6  433.83
  4818.4     433  4849.4  432.79  4872.2  430.79  4902.6  429.88  4915.3  428.47
  4922.9  430.33  4953.3  431.19  4976.1  430.56  4983.7  426.85  4991.6  421.27
    4992  420.77  4995.8  420.77  4996.1  421.27  5001.5  426.72  5011.5  426.28
  5017.5  428.58  5026.5  430.08  5130.1  432.21  5161.8  433.03  5170.8  432.41
  5184.3  433.06  5233.9  433.29  5256.4  434.62    5300  434.73  5364.6  436.53
#Mann= 6 ,-1 , 0
  4699.9     .05       0  4718.1     .12       0  4818.4      .1       0
  4991.6     .05       0  4996.1      .1       0  5130.1     .07       0
Bank Sta=4991.6,4996.1
XS Rating Curve= 0 ,0
Exp/Cntr=0.3,0.1

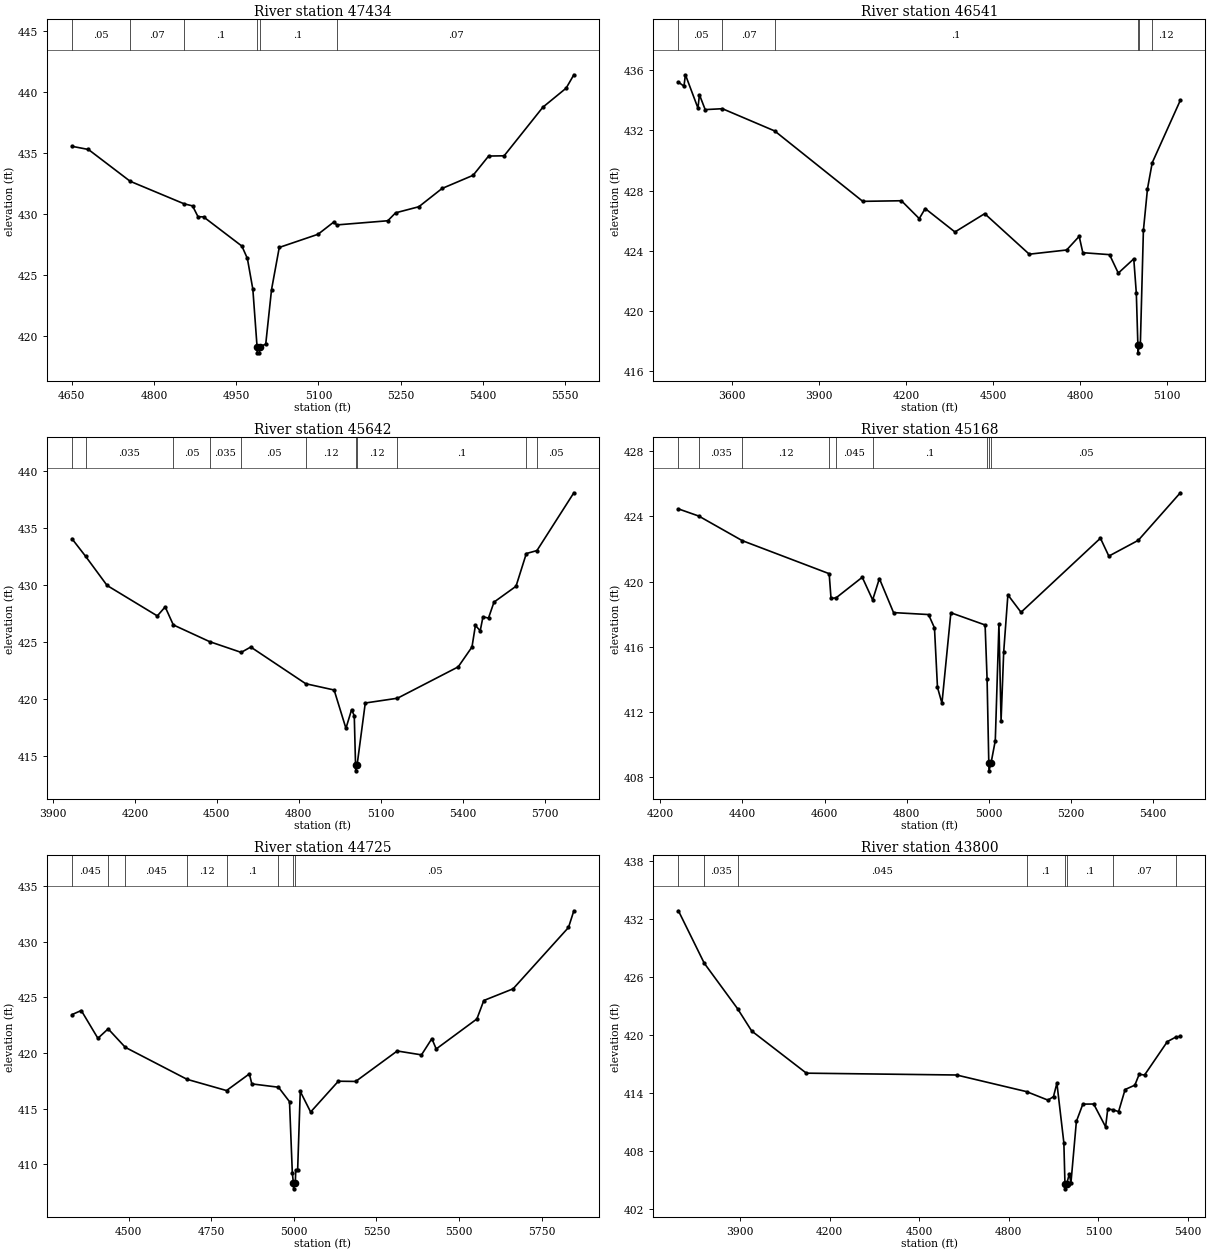
Type RM Length L Ch R = 1 ,47434   ,893,893,893
BEGIN DESCRIPTION:
BEE BRANCH 63.0
END DESCRIPTION:
XS GIS Cut Line= 3
        2489275.     13822024.95        2489275.       13821675.
      2488875.03     13821275.03
#Sta/Elev= 30
  4650.4  435.57  4680.4  435.31  4756.6   432.7    4855  430.85  4870.4  430.68
  4880.4  429.79  4890.4  429.78  4960.4  427.38  4970.4  426.37  4980.4  423.84
  4988.1  419.12  4988.4  418.62  4992.3  418.62  4992.6  419.12  5003.9  419.33
  5014.5  423.81  5028.6  427.27  5099.3  428.35  5127.6  429.34    5134  429.12
  5226.6  429.46  5240.8  430.11  5283.2  430.61  5325.6  432.11  5382.2  433.19
  5410.5  434.77  5438.8  434.79  5509.5  438.78  5551.9  440.34    5566  441.44
#Mann= 6 ,-1 , 0
  4650.4     .05       0  4756.6     .07       0    4855      .1       0
  4988.1     .05       0  4992.6      .1       0    5134     .07       0
Bank Sta=4988.1,4992.6
XS Rating Curve= 0 ,0
Exp/Cntr=0.3,0.1

Type RM Length L Ch R = 1 ,46541   ,899,899,899
BEGIN DESCRIPTION:
BEE BRANCH 62.0
END DESCRIPTION:
XS GIS Cut Line= 3
      2489825.01     13822475.03        2489475.       13820925.
      2489374.98     13820824.98
#Sta/Elev= 30
  3414.4  435.22  3433.5  434.95  3438.6  435.71  3481.8  433.49  3486.9  434.38
  3506.7  433.39  3566.1  433.45  3746.2  431.97    4050  427.28  4183.3  427.32
  4244.8  426.13  4265.3   426.8  4367.8  425.24  4470.4  426.46  4624.1  423.76
    4753  424.04  4796.2  424.95  4808.7  423.86  4900.9  423.73    4931   422.5
  4984.4  423.45  4993.2  421.16  4998.6  417.69  4998.9  417.19  5003.2  417.69
    5007  417.69  5017.6  425.34  5031.7  428.12    5048  429.85  5144.9  434.01
#Mann= 6 ,-1 , 0
  3414.4     .05       0  3566.1     .07       0  3746.2      .1       0
  4998.6     .05       0  5003.2      .1       0    5048     .12       0
Bank Sta=4998.6,5003.2
XS Rating Curve= 0 ,0
Exp/Cntr=0.3,0.1

Type RM Length L Ch R = 1 ,45642   ,474,474,474
BEGIN DESCRIPTION:
BEE BRANCH 61.0
END DESCRIPTION:
XS GIS Cut Line= 3
      2490874.98     13821474.98        2490075.       13820825.
      2489274.98       13820725.
#Sta/Elev= 30
  3969.7  434.02  4019.3  432.49  4098.3  429.92  4282.1  427.25  4310.9  428.04
  4340.7  426.46  4473.9  424.99  4589.1  424.05  4624.1  424.52  4825.5   421.3
  4929.3  420.75  4972.5  417.39  4993.3  419.03    5003  418.49  5007.7  414.16
  5008.2  413.66  5013.3  414.16  5043.3  419.61  5161.2  420.03  5383.4  422.78
  5433.8  424.52  5446.4  426.41    5464  425.95  5474.1  427.17  5494.3  427.06
  5514.4  428.46    5595  429.85  5632.7  432.72  5671.6  432.98  5806.7  438.05
#Mann= 11 ,-1 , 0
  3969.7     .07       0  4019.3    .035       0  4340.7     .05       0
  4473.9    .035       0  4589.1     .05       0  4825.5     .12       0
  5007.7     .05       0  5013.3     .12       0  5161.2      .1       0
  5632.7     .12       0  5671.6     .05       0
Bank Sta=5007.7,5013.3
XS Rating Curve= 0 ,0
Exp/Cntr=0.3,0.1

Type RM Length L Ch R = 1 ,45168   ,443,443,443
BEGIN DESCRIPTION:
BEE BRANCH 60.0
END DESCRIPTION:
XS GIS Cut Line= 3
      2490774.97     13820724.99        2490075.       13820425.
      2489625.02       13820525.
#Sta/Elev= 30
    4244  424.46  4293.6  424.02  4399.5  422.51  4611.2  420.48  4615.7  418.96
  4628.2     419  4691.8  420.26  4717.1  418.87  4733.5  420.18    4768  418.09
  4853.2  417.97  4867.7  417.15    4875   413.5  4885.9  412.52  4907.6  418.08
    4991  417.33  4995.8  414.04    5000  408.87  5000.5  408.37  5005.6  408.87
  5015.8  410.22  5024.7  417.38  5029.9  411.45  5036.3  415.67  5046.5  419.18
  5078.5  418.11  5271.9  422.66  5292.4  421.56  5364.1  422.53  5466.5  425.45
#Mann= 9 ,-1 , 0
    4244    .045       0  4293.6    .035       0  4399.5     .12       0
  4611.2     .05       0  4628.2    .045       0  4717.1      .1       0
  4995.8     .05       0    5000     .05       0  5005.6     .05       0
Bank Sta=5000,5005.6
XS Rating Curve= 0 ,0
Exp/Cntr=0.3,0.1

Type RM Length L Ch R = 1 ,44725   ,925,925,925
BEGIN DESCRIPTION:
BEE BRANCH 59.0
END DESCRIPTION:
XS GIS Cut Line= 3
      2490725.01     13820575.01        2490175.       13820175.
      2489375.04     13820424.99
#Sta/Elev= 30
  4328.8  423.46    4357  423.83  4407.3  421.33  4438.3  422.18  4490.1  420.52
    4677  417.64  4796.4  416.63  4865.5  418.13  4872.9  417.23  4953.5  416.93
  4986.9  415.63  4995.4  409.23  4998.7  408.29  4999.2  407.79  5004.4  408.29
  5005.8  409.49  5011.5  409.49  5019.4  416.55  5050.8   414.7  5134.6  417.47
    5187  417.45  5312.7  420.19  5386.1  419.84  5417.5   421.3  5430.6  420.37
  5553.7  423.07  5574.6  424.73  5663.2  425.78  5830.8   431.3    5847   432.8
#Mann= 8 ,-1 , 0
  4328.8    .045       0  4438.3     .12       0  4490.1    .045       0
    4677     .12       0  4796.4      .1       0  4953.5     .05       0
  4998.7     .05       0  5004.4     .05       0
Bank Sta=4998.7,5004.4
XS Rating Curve= 0 ,0
Exp/Cntr=0.3,0.1

Type RM Length L Ch R = 1 ,43800   ,475,475,475
BEGIN DESCRIPTION:
BEE BRANCH 58.0
END DESCRIPTION:
XS GIS Cut Line= 3
      2491125.02     13820025.01        2489925.       13819525.
      2489575.01       13819675.
#Sta/Elev= 30
  3693.4  432.81  3779.9  427.39  3891.4  422.69  3938.8  420.38  4121.9  416.02
  4625.1  415.83  4859.4  414.11  4931.1  413.23  4949.5   413.6  4960.9  414.99
  4984.2  408.82  4987.9  404.56  4988.3  404.06  4993.6  404.56  5002.5  405.61
  5007.9  404.67  5026.1  411.03  5047.8  412.82  5084.1  412.83    5124  410.47
  5131.2  412.32  5147.6  412.24  5167.5  412.05  5189.3  414.33  5221.9  414.78
  5236.4   415.9  5254.5  415.83  5330.7  419.28  5359.5  419.76  5374.2  419.82
#Mann= 8 ,-1 , 0
  3693.4    .045       0  3779.9    .035       0  3891.4    .045       0
  4859.4      .1       0  4987.9     .05       0  4993.6      .1       0
  5147.6     .07       0  5359.5     .05       0
Bank Sta=4987.9,4993.6
XS Rating Curve= 0 ,0
Exp/Cntr=0.3,0.1

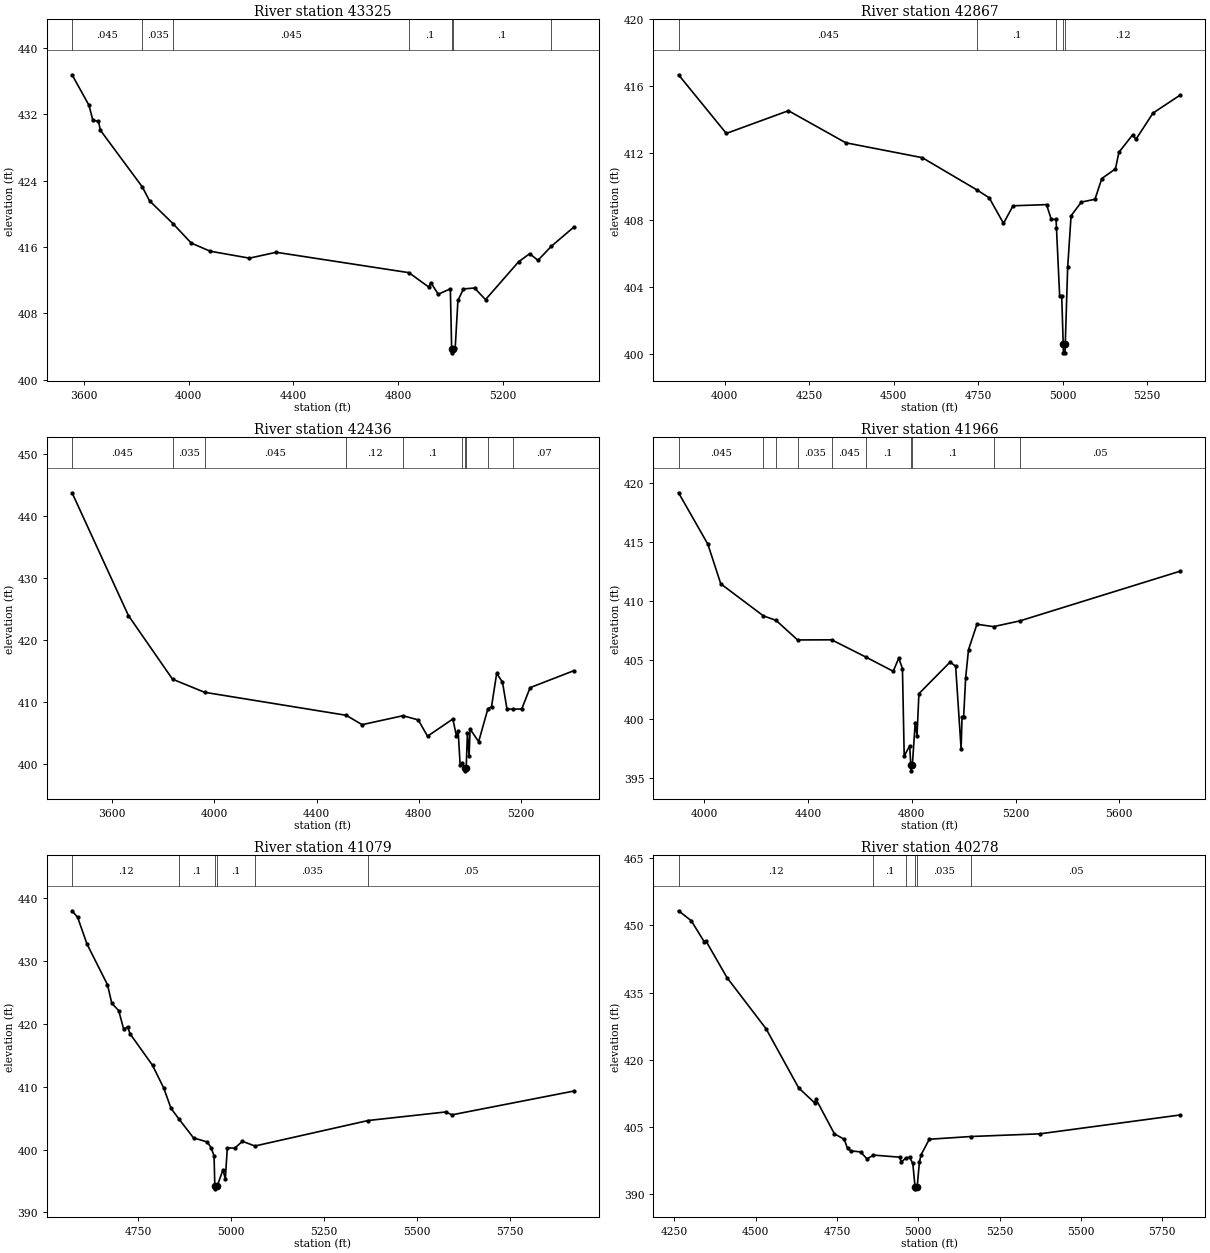
Type RM Length L Ch R = 1 ,43325   ,458,458,458
BEGIN DESCRIPTION:
BEE BRANCH 57.0
END DESCRIPTION:
XS GIS Cut Line= 3
        2491175.       13819975.        2489975.       13819175.
      2489524.96     13819024.99
#Sta/Elev= 30
  3554.4  436.78    3619   433.1    3634  431.27  3655.1  431.18  3662.6  430.09
  3823.2  423.23  3850.4  421.57  3939.4  418.84  4009.6  416.48  4081.7   415.5
  4231.9  414.66  4334.1  415.37    4841  412.91    4917  411.17  4924.5  411.72
    4953  410.31  4999.3  410.96  5004.2  403.74  5004.7  403.24  5010.1  403.74
  5017.7  403.78  5028.2  409.56  5049.3  410.95  5091.5  411.06  5133.6  409.66
  5260.1  414.23  5302.3   415.2  5333.9   414.4  5385.1   416.1    5471  418.41
#Mann= 7 ,-1 , 0
  3554.4    .045       0  3823.2    .035       0  3939.4    .045       0
    4841      .1       0  5004.2     .05       0  5010.1      .1       0
  5385.1     .12       0
Bank Sta=5004.2,5010.1
XS Rating Curve= 0 ,0
Exp/Cntr=0.3,0.1

Type RM Length L Ch R = 1 ,42867   ,431,431,431
BEGIN DESCRIPTION:
BEE BRANCH 56.0
END DESCRIPTION:
XS GIS Cut Line= 3
      2490774.97     13819574.97        2489975.       13818775.
      2489624.98       13818825.
#Sta/Elev= 30
  3863.7  416.68  4005.1  413.17  4188.9  414.53  4358.6  412.61  4584.9  411.72
  4745.9   409.8  4782.9  409.32  4825.3  407.79  4853.6  408.84  4952.6  408.91
  4966.7  408.03  4980.9  408.02  4982.1   407.5  4991.5  403.45  4997.6  403.45
  5002.1  400.54  5002.6  400.04  5007.6  400.04  5008.1  400.54  5015.2  405.15
  5025.3  408.24  5055.6  409.06    5096  409.23  5116.2  410.47  5156.7  411.05
  5166.8  412.04  5207.2  413.08  5217.3  412.82  5267.8  414.39  5348.6  415.47
#Mann= 5 ,-1 , 0
  3863.7    .045       0  4745.9      .1       0  4982.1     .12       0
  5002.1     .05       0  5008.1     .12       0
Bank Sta=5002.1,5008.1
XS Rating Curve= 0 ,0
Exp/Cntr=0.3,0.1

Type RM Length L Ch R = 1 ,42436   ,470,470,470
BEGIN DESCRIPTION:
BEE BRANCH 55.0
END DESCRIPTION:
XS GIS Cut Line= 3
      2491174.96     13819374.97        2489975.       13818375.
      2489575.01       13818325.
#Sta/Elev= 30
  3442.4  443.73    3663  423.95  3835.8  413.69  3961.1  411.58  4516.1  407.87
  4578.1  406.36  4738.2   407.8  4798.1  407.13  4834.5   404.5  4933.5  407.27
  4947.8  404.53  4954.3   405.4  4962.1  399.88  4970.2  400.16  4979.9  399.42
  4980.4  398.92  4985.9  399.42  4990.7  405.01  4997.2  401.27  5001.1  405.66
  5034.6  403.62  5070.8  408.91    5085  409.25  5105.2  414.62  5127.9  413.23
  5145.5  408.89  5169.7  408.86  5203.4  408.89  5236.2  412.33  5407.5  415.06
#Mann= 10 ,-1 , 0
  3442.4    .045       0  3835.8    .035       0  3961.1    .045       0
  4516.1     .12       0  4738.2      .1       0  4970.2     .12       0
  4979.9     .05       0  4985.9     .12       0  5070.8      .1       0
  5169.7     .07       0
Bank Sta=4979.9,4985.9
XS Rating Curve= 0 ,0
Exp/Cntr=0.3,0.1

Type RM Length L Ch R = 1 ,41966   ,887,887,887
BEGIN DESCRIPTION:
BEE BRANCH 54.0
END DESCRIPTION:
XS GIS Cut Line= 3
      2491124.97     13818874.97        2490325.       13818125.
        2489525.       13817875.
#Sta/Elev= 30
  3900.5  419.19  4013.5  414.83  4063.4  411.46  4227.9  408.74  4276.6  408.36
  4359.4   406.7  4490.9  406.71  4622.5  405.25  4728.2  404.04  4749.6  405.16
  4763.8  404.27  4770.6  396.85  4791.7  397.71    4796  396.09  4796.5  395.59
    4802  396.09  4813.1  399.69    4820  398.56  4827.3  402.14  4947.5  404.82
  4968.9  404.47    4990  397.44  4993.6  400.14  4999.7  400.14  5007.5  403.48
  5018.5  405.87    5051  408.03  5114.9  407.83  5217.2  408.32  5835.2  412.54
#Mann= 10 ,-1 , 0
  3900.5    .045       0  4227.9    .035       0  4276.6    .045       0
  4359.4    .035       0  4490.9    .045       0  4622.5      .1       0
    4796     .05       0    4802      .1       0  5114.9     .07       0
  5217.2     .05       0
Bank Sta=4796,4802
XS Rating Curve= 0 ,0
Exp/Cntr=0.3,0.1

Type RM Length L Ch R = 1 ,41079   ,801,801,801
BEGIN DESCRIPTION:
BEE BRANCH 53.0
END DESCRIPTION:
XS GIS Cut Line= 3
        2491275.       13817625.        2490875.       13817775.
      2489974.95     13817975.01
#Sta/Elev= 30
  4572.8  438.03  4587.9  436.97  4612.8  432.75    4668  426.26  4679.6  423.31
  4698.3  422.12  4711.6  419.17  4722.3  419.57  4728.5  418.46  4789.1  413.43
  4819.3   409.8  4838.9  406.57  4860.5  404.85  4899.4  401.87  4935.9  401.23
  4946.6  400.32  4954.6  399.01  4956.6  394.26  4957.1  393.76  4963.3  394.26
  4978.6  396.78  4984.9  395.32  4990.2  400.29  5010.2  400.23  5030.7  401.33
  5064.5  400.58  5369.1  404.64  5577.5     406  5594.1  405.54    5922  409.33
#Mann= 6 ,-1 , 0
  4572.8     .12       0  4860.5      .1       0  4956.6     .05       0
  4963.3      .1       0  5064.5    .035       0  5369.1     .05       0
Bank Sta=4956.6,4963.3
XS Rating Curve= 0 ,0
Exp/Cntr=0.3,0.1

Type RM Length L Ch R = 1 ,40278   ,435,435,435
BEGIN DESCRIPTION:
BEE BRANCH 52.0
END DESCRIPTION:
XS GIS Cut Line= 3
      2491424.04     13817307.51      2490755.61     13817327.32
      2489894.01     13817470.92
#Sta/Elev= 30
  4263.3  453.27  4302.4  451.05  4342.3  446.34  4347.3  446.56  4412.4  438.34
  4532.5  426.92  4632.5  413.74  4681.2  410.43  4686.2  411.16  4742.5  403.47
  4772.6  402.28  4782.6  400.22  4792.6  399.68  4822.6  399.45  4842.6   397.9
  4862.4  398.74  4942.8  398.28  4948.1  397.17  4961.5  398.07  4973.2   398.3
  4983.3  396.87  4990.1  391.71  4990.6  391.21  4996.8  391.71  5003.6  397.21
  5008.9  398.84    5034  402.28  5162.2  402.89  5373.9  403.49  5805.5   407.7
#Mann= 6 ,-1 , 0
  4263.3     .12       0  4862.4      .1       0  4961.5    .035       0
  4990.1    .035       0  4996.8    .035       0  5162.2     .05       0
Bank Sta=4990.1,4996.8
XS Rating Curve= 0 ,0
Exp/Cntr=0.3,0.1

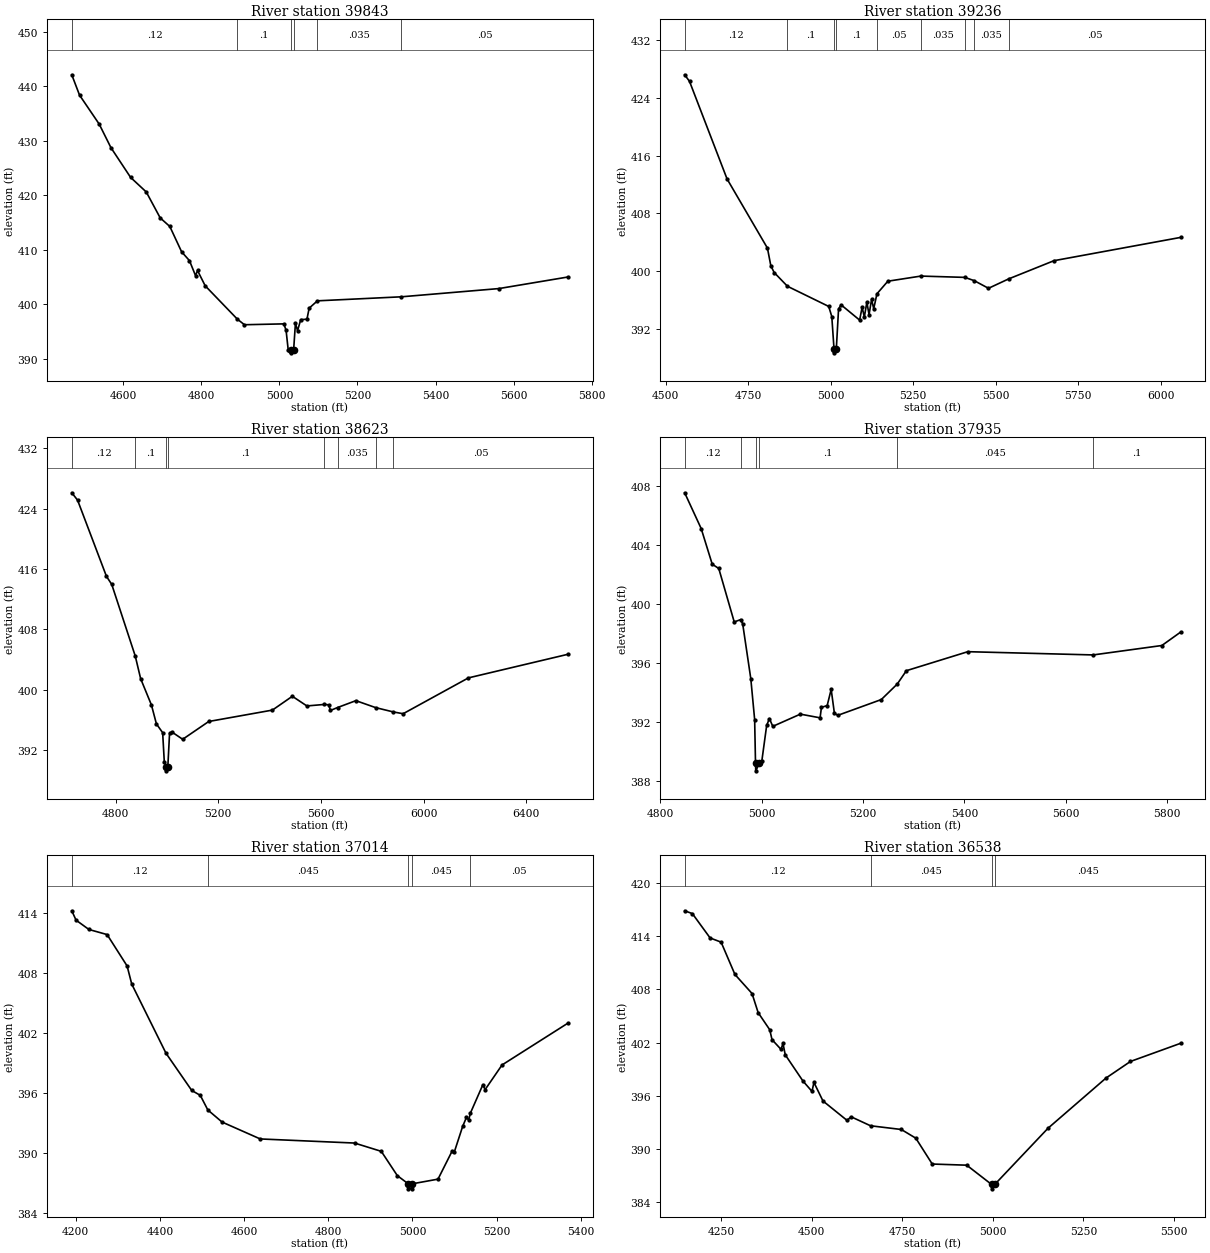
Type RM Length L Ch R = 1 ,39843   ,607,607,607
BEGIN DESCRIPTION:
X18184
END DESCRIPTION:
XS GIS Cut Line= 3
      2491354.78     13817045.08      2490819.98     13816985.65
      2490141.56     13817262.96
#Sta/Elev= 30
  4467.8  442.15  4487.7  438.41    4538   433.1  4568.2  428.76  4618.5  423.31
  4658.7  420.63  4694.4  415.87  4719.1  414.29  4749.3  409.64  4769.4  408.02
    4785  405.26    4790  406.21  4809.7   403.4  4892.2  397.27  4910.3  396.25
  5011.3  396.41    5017  395.23  5022.4  391.66  5029.4  391.59  5029.9  391.09
  5036.3  391.59    5041  396.53  5046.4  395.16  5054.5  397.18  5070.5  397.27
  5076.1  399.29  5097.3  400.64  5312.6  401.38  5562.2  402.89  5738.8  405.01
#Mann= 6 ,-1 , 0
  4467.8     .12       0  4892.2      .1       0  5029.4     .05       0
  5036.3      .1       0  5097.3    .035       0  5312.6     .05       0
Bank Sta=5029.4,5036.3
XS Rating Curve= 0 ,0
Exp/Cntr=0.3,0.1

Type RM Length L Ch R = 1 ,39236   ,613,613,613
BEGIN DESCRIPTION:
X18185
END DESCRIPTION:
XS GIS Cut Line= 3
      2491399.34     13816728.17       2490889.3     13816609.33
      2490146.24     13817247.81
#Sta/Elev= 30
  4557.1  427.18  4571.8  426.27  4685.6  412.77    4808   403.2  4818.4  400.74
  4828.5  399.82  4868.7  397.92  4993.8  395.13  5003.1  393.73  5009.9  389.21
  5010.4  388.71  5016.8  389.21  5023.6  394.77  5031.3  395.35  5087.5  393.24
  5095.1  395.03  5101.7  393.66  5109.4  395.72    5116     394  5123.7   396.1
  5130.2  394.82    5140  396.88    5173  398.62  5273.1  399.33  5406.2  399.15
  5434.7   398.7  5478.1  397.64  5539.3  398.94  5676.7  401.46  6060.5  404.68
#Mann= 9 ,-1 , 0
  4557.1     .12       0  4868.7      .1       0  5009.9     .05       0
  5016.8      .1       0    5140     .05       0  5273.1    .035       0
  5406.2     .05       0  5434.7    .035       0  5539.3     .05       0
Bank Sta=5009.9,5016.8
XS Rating Curve= 0 ,0
Exp/Cntr=0.3,0.1

Type RM Length L Ch R = 1 ,38623   ,688,688,688
BEGIN DESCRIPTION:
X18186
END DESCRIPTION:
XS GIS Cut Line= 3
      2491637.02     13816416.22       2491032.9     13816282.52
      2490133.86     13817240.63
#Sta/Elev= 30
  4629.4  426.11  4651.9  425.14  4764.6  415.03  4785.1  413.97  4876.7  404.48
  4897.8  401.47  4939.8  397.99  4959.2  395.48  4983.5  394.32  4989.9  390.46
  4996.7  389.76  4997.2  389.26  5003.6  389.76  5010.4  394.21  5020.7  394.38
  5061.6  393.44  5163.1   395.8  5411.2  397.31  5488.9  399.14  5545.5  397.86
    5614  398.06  5630.5  398.01  5637.3  397.26    5665  397.65  5736.5  398.56
  5813.4  397.64    5883  397.06  5920.6  396.83  6175.1  401.58    6562   404.7
#Mann= 8 ,-1 , 0
  4629.4     .12       0  4876.7      .1       0  4996.7     .05       0
  5003.6      .1       0    5614     .05       0    5665    .035       0
  5813.4     .07       0    5883     .05       0
Bank Sta=4996.7,5003.6
XS Rating Curve= 0 ,0
Exp/Cntr=0.3,0.1

Type RM Length L Ch R = 1 ,37935   ,921,921,921
BEGIN DESCRIPTION:
BEE BRANCH 51.0
END DESCRIPTION:
XS GIS Cut Line= 3
      2491575.02     13815774.99      2491325.05     13815881.43
      2490874.45     13816426.12
#Sta/Elev= 30
  4848.1  407.56  4880.7  405.13  4902.5  402.71  4915.4  402.42  4945.9  398.79
  4958.7  398.95  4962.6  398.66  4978.6  394.94  4986.2  392.16  4987.9  389.18
  4988.4  388.68  4995.4  389.18  5000.3  389.33  5009.9  391.76  5015.3  392.23
    5022   391.7  5076.4  392.53  5115.3  392.28    5118  392.99  5129.3  393.11
  5137.2  394.21  5143.6  392.58  5150.4  392.45  5236.1  393.52  5267.5  394.57
  5285.6  395.48  5406.8  396.77  5654.1  396.55  5789.7  397.19  5826.7   398.1
#Mann= 6 ,-1 , 0
  4848.1     .12       0  4958.7      .1       0  4987.9     .05       0
  4995.4      .1       0  5267.5    .045       0  5654.1      .1       0
Bank Sta=4987.9,4995.4
XS Rating Curve= 0 ,0
Exp/Cntr=0.3,0.1

Type RM Length L Ch R = 1 ,37014   ,476,476,476
BEGIN DESCRIPTION:
BEE BRANCH 50.0
END DESCRIPTION:
XS GIS Cut Line= 3
      2491574.98       13815475.        2490775.       13815325.
      2490425.02     13815424.99
#Sta/Elev= 30
  4190.8  414.26    4201  413.32  4231.5  412.39  4274.7  411.88  4322.2  408.74
  4333.2  406.93  4414.6  400.01  4475.7  396.29    4496   395.8  4513.9  394.34
  4547.7  393.13  4638.4  391.44  4862.3  391.03  4925.9   390.2    4964  387.77
    4990  386.95  4990.5  386.45  4998.5  386.45    4999  386.95  5060.6  387.42
  5094.4  390.25  5099.6  390.17  5119.1  392.69  5128.2   393.6  5133.4  393.33
  5137.6  394.03  5167.2  396.87  5172.4  396.37  5212.7  398.84  5368.7  403.01
#Mann= 5 ,-1 , 0
  4190.8     .12       0  4513.9    .045       0    4990    .045       0
    4999    .045       0  5137.6     .05       0
Bank Sta=4990,4999
XS Rating Curve= 0 ,0
Exp/Cntr=0.3,0.1

Type RM Length L Ch R = 1 ,36538   ,706,706,706
BEGIN DESCRIPTION:
BEE BRANCH 49.0
END DESCRIPTION:
XS GIS Cut Line= 3
      2491674.98     13815224.99        2490875.       13814925.
      2490424.97     13815175.02
#Sta/Elev= 30
  4149.4  416.87  4170.7  416.55  4219.7   413.8    4250  413.33  4288.2  409.68
  4335.4  407.53  4352.3  405.37  4384.3  403.44  4390.6  402.32  4415.5  401.22
  4420.8   401.9  4427.1  400.61    4476  397.65  4500.9  396.48  4506.3  397.49
  4531.2   395.4  4597.9   393.2  4608.6  393.62  4662.5   392.6  4747.5  392.18
  4787.5   391.2  4832.9  388.28  4928.1  388.15  4996.6  385.98  4997.1  385.48
  5005.6  385.98  5152.5  392.32  5312.7  397.99  5380.1  399.86  5518.6  401.91
#Mann= 4 ,-1 , 0
  4149.4     .12       0  4662.5    .045       0  4996.6    .045       0
  5005.6    .045       0
Bank Sta=4996.6,5005.6
XS Rating Curve= 0 ,0
Exp/Cntr=0.3,0.1

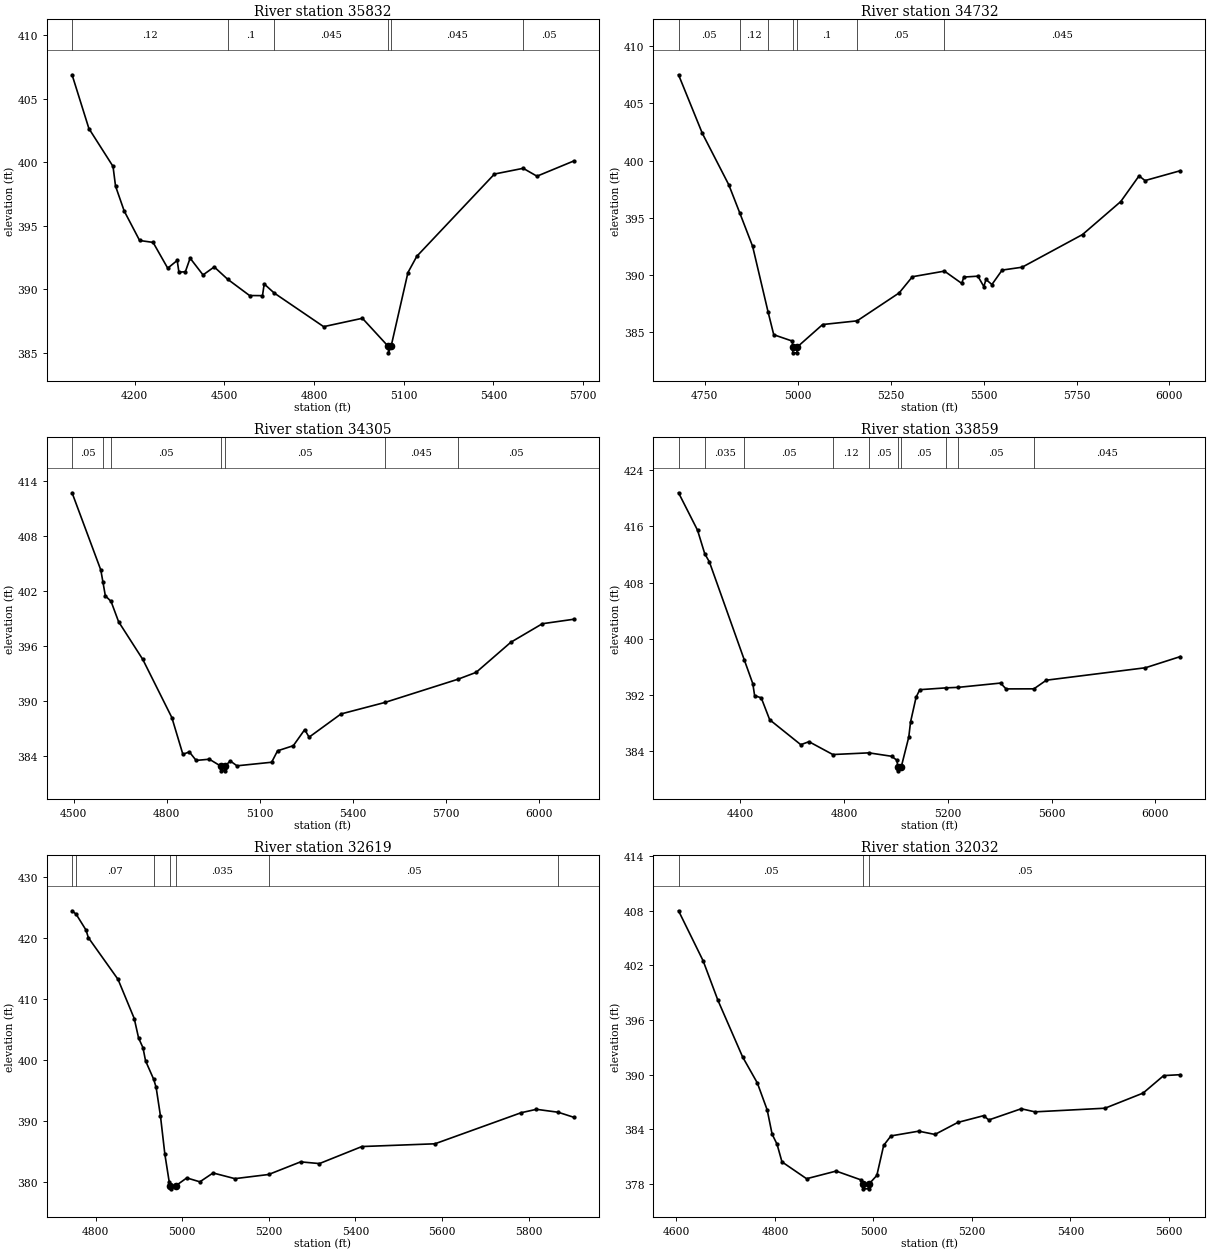
Type RM Length L Ch R = 1 ,35832   ,1100,1100,1100
BEGIN DESCRIPTION:
X18187
END DESCRIPTION:
XS GIS Cut Line= 4
      2491701.37     13814856.44      2490953.68      13814430.6
      2490661.53     13814485.07      2490354.52     13814905.96
#Sta/Elev= 30
  3990.7  406.89    4047  402.66  4127.7  399.68  4136.1  398.13  4165.1  396.17
  4216.7  393.85  4261.7   393.7  4310.7  391.67  4342.4  392.28  4348.1  391.36
  4369.7  391.39  4385.6  392.46  4428.8  391.14  4466.3  391.77  4510.7  390.81
  4584.4  389.52  4627.7  389.51  4633.4  390.43  4666.7  389.72  4832.3  387.07
  4961.9  387.73  5048.7  385.51  5049.2  385.01  5057.8  385.51  5114.3  391.33
    5144  392.61  5403.7  399.08  5499.8  399.53  5545.9  398.91  5669.3  400.11
#Mann= 6 ,-1 , 0
  3990.7     .12       0  4510.7      .1       0  4666.7    .045       0
  5048.7    .045       0  5057.8    .045       0  5499.8     .05       0
Bank Sta=5048.7,5057.8
XS Rating Curve= 0 ,0
Exp/Cntr=0.3,0.1

Type RM Length L Ch R = 1 ,34732   ,427,427,427
BEGIN DESCRIPTION:
BEE BRANCH 48.0
END DESCRIPTION:
XS GIS Cut Line= 3
      2491174.98     13813575.03        2490975.       13813825.
      2490474.99     13814725.02
#Sta/Elev= 30
  4679.5  407.48  4743.5  402.37  4814.7  397.88  4844.4  395.41  4878.8  392.51
  4920.1  386.82  4935.6   384.8    4986  384.24  4986.3  383.72  4986.8  383.22
    4998  383.22  4998.5  383.72  5067.1  385.69  5159.8  386.01    5273  388.45
  5308.5  389.86  5394.7  390.35  5441.2  389.28  5446.9  389.83  5484.7  389.91
  5500.7     389  5506.4  389.62  5522.4  389.18  5549.9  390.44  5603.6  390.69
  5766.1  393.54    5869  396.42  5918.2  398.66  5934.2  398.25  6029.2  399.11
#Mann= 7 ,-1 , 0
  4679.5     .05       0  4844.4     .12       0  4920.1      .1       0
  4986.3     .05       0  4998.5      .1       0  5159.8     .05       0
  5394.7    .045       0
Bank Sta=4986.3,4998.5
XS Rating Curve= 0 ,0
Exp/Cntr=0.3,0.1

Type RM Length L Ch R = 1 ,34305   ,446,446,446
BEGIN DESCRIPTION:
BEE BRANCH 47.0
END DESCRIPTION:
XS GIS Cut Line= 3
      2491024.97     13813325.02        2490625.       13813625.
        2490425.       13814725.
#Sta/Elev= 30
  4495.3  412.76    4588  404.31  4594.7  403.02  4602.6  401.49    4621  400.88
  4645.3  398.66  4723.4  394.53  4817.1  388.17  4852.6  384.16  4873.4  384.42
  4895.3  383.49    4938  383.62  4975.6  382.85  4976.1  382.35  4987.4  382.35
  4987.9  382.85  5005.4  383.43    5027   382.9  5138.8  383.29  5157.9  384.54
  5208.7   385.1  5245.5  386.86  5259.5  386.03  5362.4  388.57  5504.1  389.83
  5739.7  392.37  5798.2  393.12    5910  396.41  6011.7  398.44  6113.3  398.93
#Mann= 7 ,-1 , 0
  4495.3     .05       0  4594.7    .035       0    4621     .05       0
  4975.6     .05       0  4987.9     .05       0  5504.1    .045       0
  5739.7     .05       0
Bank Sta=4975.6,4987.9
XS Rating Curve= 0 ,0
Exp/Cntr=0.3,0.1

Type RM Length L Ch R = 1 ,33859   ,1240,1240,1240
BEGIN DESCRIPTION:
BEE BRANCH 46.0
END DESCRIPTION:
XS GIS Cut Line= 3
      2491074.98     13813125.01        2490275.       13813375.
      2489475.01     13814124.99
#Sta/Elev= 30
  4161.6  420.78  4234.9  415.45  4262.7   412.1  4280.5  410.95    4415  397.01
  4448.1   393.6  4454.9  391.92  4480.6  391.59  4513.1  388.48    4633  384.93
  4664.5  385.36  4756.5  383.53  4895.7  383.77  4983.5  383.28  5003.2  382.72
  5007.5  381.71    5008  381.21  5019.9  381.71  5049.3  386.02  5056.2  388.17
  5077.6   391.7  5091.8  392.76  5193.9  393.02    5240  393.09    5403   393.7
  5424.4  392.87  5531.8  392.88  5579.8  394.11  5961.8  395.88  6096.3  397.47
#Mann= 10 ,-1 , 0
  4161.6     .05       0  4262.7    .035       0    4415     .05       0
  4756.5     .12       0  4895.7     .05       0  5007.5     .05       0
  5019.9     .05       0  5193.9    .035       0    5240     .05       0
  5531.8    .045       0
Bank Sta=5007.5,5019.9
XS Rating Curve= 0 ,0
Exp/Cntr=0.3,0.1

Type RM Length L Ch R = 1 ,32619   ,587,587,587
BEGIN DESCRIPTION:
X18188
END DESCRIPTION:
XS GIS Cut Line= 3
      2491126.96     13812885.68      2490443.65      13812781.7
      2490012.87      13812964.9
#Sta/Elev= 30
  4745.4  424.48  4754.9  423.91  4777.7  421.31    4783  420.08  4851.6  413.24
    4889  406.83  4899.1  403.63  4909.2  402.04  4915.2  399.89  4933.9  396.88
  4939.6  395.55  4949.7  390.81  4959.8  384.58  4969.9  380.02  4972.6  379.42
  4973.1  378.92    4985  379.42  5010.4  380.71  5040.7  380.07  5071.1  381.52
  5121.6  380.59  5199.5  381.27  5273.4  383.34  5316.9  383.06    5415  385.85
  5583.7   386.3  5782.8  391.39  5818.2  391.95  5868.5  391.47  5904.7  390.64
#Mann= 7 ,-1 , 0
  4745.4     .05       0  4754.9     .07       0  4933.9    .035       0
  4972.6    .035       0    4985    .035       0  5199.5     .05       0
  5868.5    .035       0
Bank Sta=4972.6,4985
XS Rating Curve= 0 ,0
Exp/Cntr=0.3,0.1

Type RM Length L Ch R = 1 ,32032   ,495,495,495
BEGIN DESCRIPTION:
BEE BRANCH 45.0
END DESCRIPTION:
XS GIS Cut Line= 3
      2491024.99       13812375.        2490625.       13812375.
      2490032.62     13812553.93
#Sta/Elev= 30
  4604.2  407.99  4654.2  402.49  4684.2  398.16  4734.2  391.96  4764.2  389.09
  4784.2  386.13  4794.2  383.47  4804.2  382.37  4814.2  380.43  4864.2  378.58
  4924.2  379.42  4974.2  378.46  4977.9  377.97  4978.4  377.47  4989.9  377.47
  4990.4  377.97  5006.8  378.94  5020.7  382.24  5035.5  383.28  5091.8   383.8
  5124.8  383.44  5171.3  384.76  5223.6   385.5  5234.1  385.03    5300  386.26
  5327.8  385.92  5470.1  386.32  5547.4  387.98  5589.2   389.9    5623     390
#Mann= 3 ,-1 , 0
  4604.2     .05       0  4977.9     .05       0  4990.4     .05       0
Bank Sta=4977.9,4990.4
XS Rating Curve= 0 ,0
Exp/Cntr=0.3,0.1