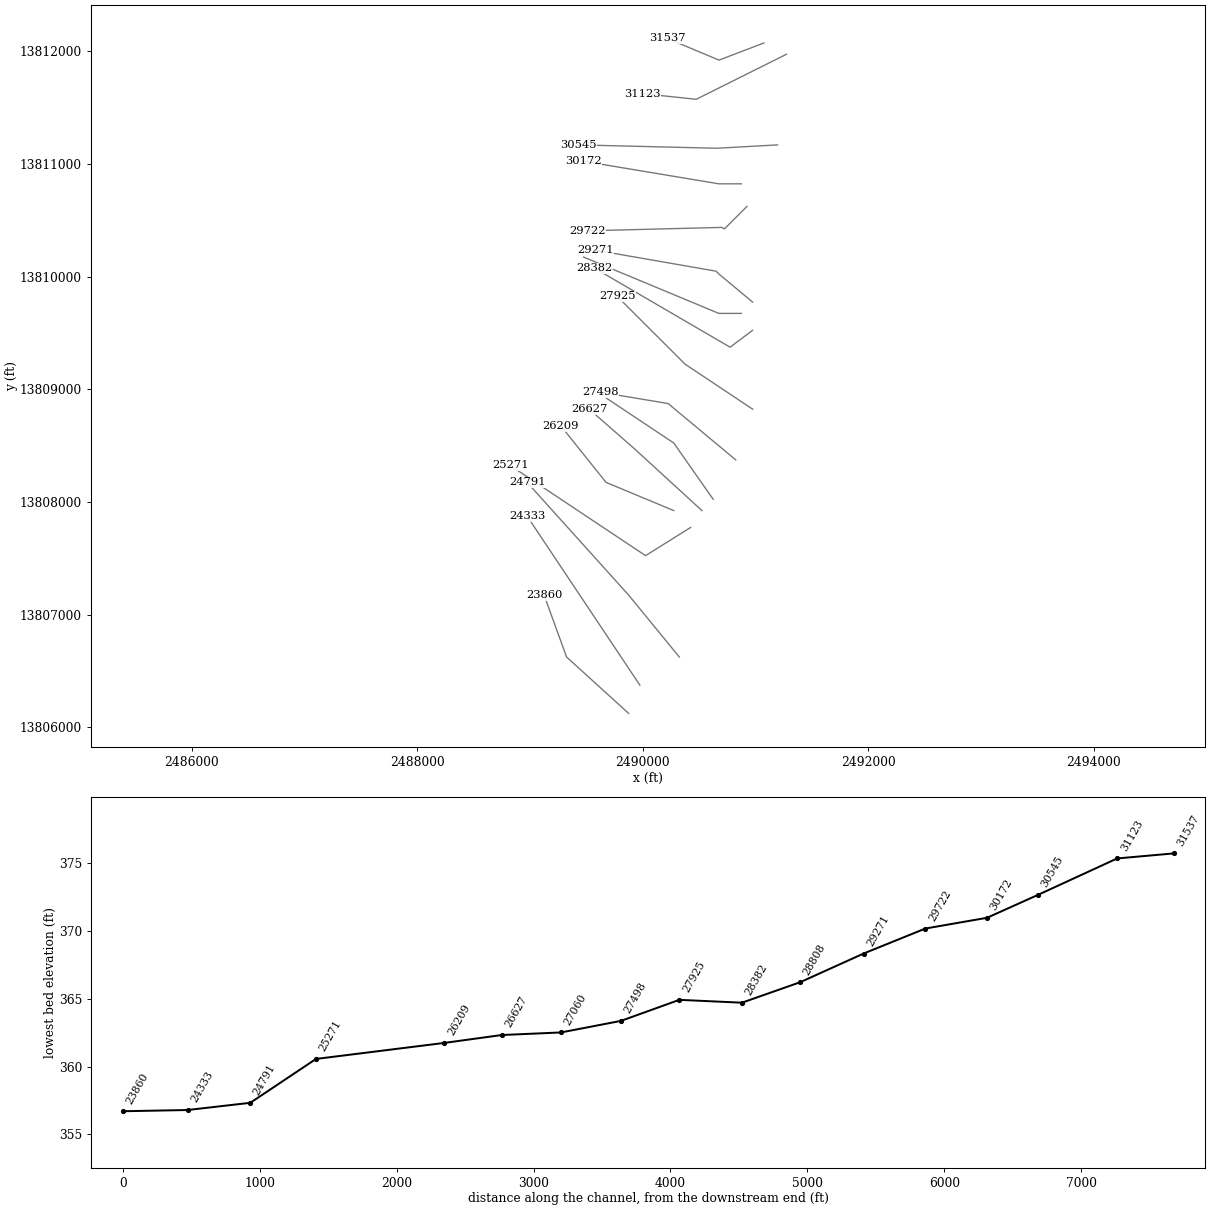
HEC-RAS study BEE BRANCH.prj: BEE BRANCH Base Level Engineering

--- BEE BRANCH.g01 (geometry) --- (continued)

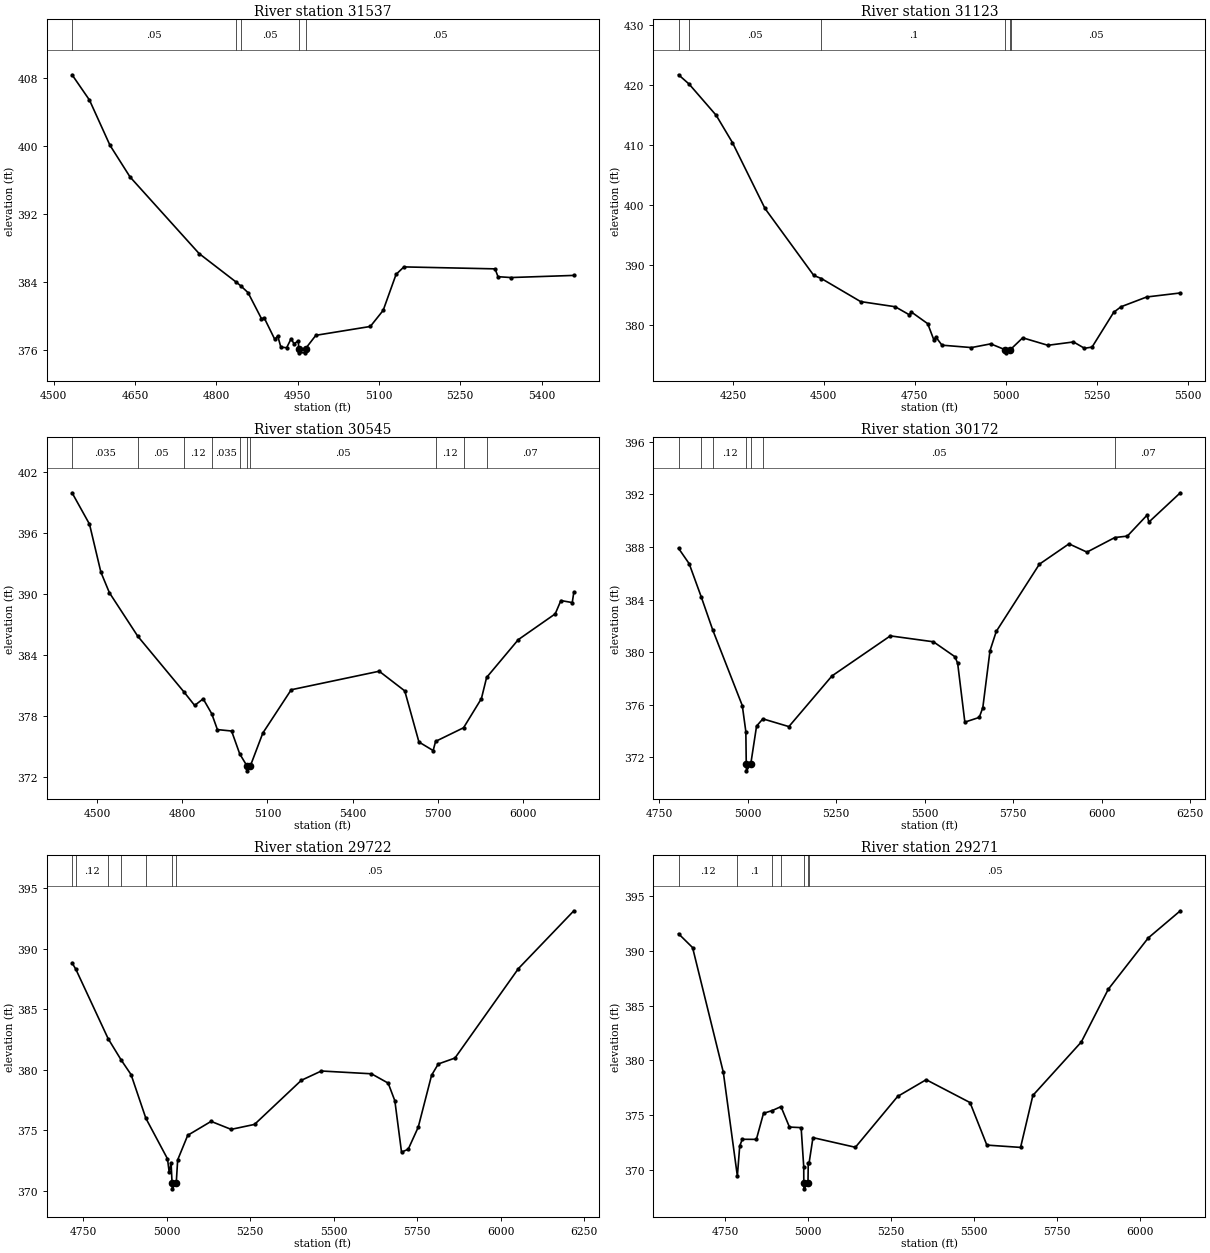
Type RM Length L Ch R = 1 ,31537   ,414,414,414
BEGIN DESCRIPTION:
BEE BRANCH 44.0
END DESCRIPTION:
XS GIS Cut Line= 3
      2491075.01       13812075.      2490676.38     13811923.08
      2490215.84     13812116.21
#Sta/Elev= 30
  4533.6  408.37  4565.7   405.4  4603.5  400.09  4640.6  396.36    4768  387.36
  4835.7  384.04  4844.6  383.58  4858.3  382.77    4883  379.72  4888.4  379.77
  4907.7  377.27  4913.1  377.67  4918.9  376.36  4929.6  376.29  4937.8  377.35
  4943.2  376.75    4951  377.09    4952  376.19  4952.5  375.69    4964  375.69
  4964.5  376.19  4983.5  377.75    5084  378.79  5107.7  380.68  5131.5  384.91
    5146  385.79  5314.2  385.56  5319.6  384.64  5343.4  384.54  5459.6  384.79
#Mann= 5 ,-1 , 0
  4533.6     .05       0  4835.7      .1       0  4844.6     .05       0
    4952     .05       0  4964.5     .05       0
Bank Sta=4952,4964.5
XS Rating Curve= 0 ,0
Exp/Cntr=0.3,0.1

Type RM Length L Ch R = 1 ,31123   ,578,578,578
BEGIN DESCRIPTION:
BEE BRANCH 43.0
END DESCRIPTION:
XS GIS Cut Line= 3
      2491275.04     13811975.02        2490475.       13811575.
      2489993.06     13811625.98
#Sta/Elev= 30
  4100.7  421.76  4129.7  420.21  4204.2  414.99  4248.9  410.43  4338.3  399.43
  4472.5  388.24  4493.6  387.72  4601.1  383.88  4696.1  383.02  4735.2  381.67
  4740.8  382.13  4785.5  380.19  4802.3   377.5  4807.9  377.96  4824.7   376.6
  4905.7   376.2  4958.8  376.82    4999  375.82  4999.5  375.32  5011.5  375.82
  5013.1  375.88  5046.6  377.83  5115.8  376.58  5186.2  377.14  5216.4  376.08
  5237.2  376.28  5296.8   382.1    5317  383.02  5387.4  384.65  5479.8  385.32
#Mann= 6 ,-1 , 0
  4100.7    .035       0  4129.7     .05       0  4493.6      .1       0
    4999     .05       0  5011.5      .1       0  5013.1     .05       0
Bank Sta=4999,5011.5
XS Rating Curve= 0 ,0
Exp/Cntr=0.3,0.1

Type RM Length L Ch R = 1 ,30545   ,373,373,373
BEGIN DESCRIPTION:
BEE BRANCH 42.0
END DESCRIPTION:
XS GIS Cut Line= 3
      2491196.32     13811170.43      2490656.58     13811140.72
       2489429.3     13811170.41
#Sta/Elev= 30
  4411.6  399.94    4473  396.86  4513.1  392.15  4543.1  390.13    4643  385.86
  4805.2  380.41  4843.6  379.06  4873.6  379.71  4903.7  378.25  4923.7  376.69
  4973.7  376.55  5002.3  374.31  5027.5  373.14    5028  372.64  5040.1  373.14
  5083.8  376.35  5183.8   380.6  5493.9  382.42  5583.9  380.49  5633.9  375.47
    5684  374.63  5692.5  375.53  5791.1  376.87    5854  379.73  5872.4  381.81
    5984  385.52  6114.1  388.05  6134.1  389.36  6174.1  389.16  6179.8   390.2
#Mann= 10 ,-1 , 0
  4411.6    .035       0    4643     .05       0  4805.2     .12       0
  4903.7    .035       0  5002.3     .05       0  5027.5    .035       0
  5040.1     .05       0  5692.5     .12       0  5791.1     .05       0
  5872.4     .07       0
#XS Ineff= 2 , 0
       0                  5416.5       0  381.06
Permanent Ineff=
       F       F
Bank Sta=5027.5,5040.1
XS Rating Curve= 0 ,0
Exp/Cntr=0.3,0.1

Type RM Length L Ch R = 1 ,30172   ,450,450,450
BEGIN DESCRIPTION:
BEE BRANCH 41.0
END DESCRIPTION:
XS GIS Cut Line= 3
      2490875.02       13810825.        2490675.       13810825.
      2489474.98       13811025.
#Sta/Elev= 30
    4805   387.9    4835  386.73  4869.1   384.2  4901.7  381.67    4985  375.92
    4995  373.94  4996.2  371.45  4996.7  370.95  5008.8  371.45  5025.3  374.36
  5043.1  374.91  5116.5  374.32  5238.2  378.18  5402.9  381.23  5524.6  380.78
  5585.4  379.64    5593  379.14  5613.3  374.66  5653.9  375.02    5664  375.76
  5684.3   380.1    5702  381.57  5823.7  386.69  5907.3  388.24    5958  387.61
  6036.6  388.72    6072  388.83  6127.8  390.43  6132.9   389.9  6221.6  392.13
#Mann= 7 ,-1 , 0
    4805     .12       0  4869.1     .05       0  4901.7     .12       0
  4996.2     .05       0  5008.8     .12       0  5043.1     .05       0
  6036.6     .07       0
#XS Ineff= 2 , 0
       0                    5402       0  380.24
Permanent Ineff=
       F       F
Bank Sta=4996.2,5008.8
XS Rating Curve= 0 ,0
Exp/Cntr=0.3,0.1

Type RM Length L Ch R = 1 ,29722   ,451,451,451
BEGIN DESCRIPTION:
BEE BRANCH 40.0
END DESCRIPTION:
XS GIS Cut Line= 4
      2490924.98     13810624.98        2490725.       13810425.
      2490701.16     13810438.24      2489509.13     13810407.83
#Sta/Elev= 30
  4717.1  388.82  4728.6  388.28  4825.3  382.55  4864.1   380.8  4893.8  379.59
    4938  375.99  5002.8  372.64  5007.9  371.54  5013.6  372.27  5016.5  370.66
    5017  370.16  5029.1  370.66  5033.3  372.55  5063.4  374.58  5133.4  375.73
  5193.4  375.07  5263.4  375.48  5403.5  379.12  5463.5  379.89  5613.5  379.66
  5663.6  378.89  5683.6  377.43  5703.6  373.19  5723.6  373.43  5753.6  375.25
  5793.6  379.54  5813.6  380.47  5863.6  380.96  6053.7  388.35  6219.6  393.12
#Mann= 7 ,-1 , 0
  4717.1    .035       0  4728.6     .12       0  4825.3    .035       0
  4864.1     .12       0    4938     .05       0  5016.5     .05       0
  5029.1     .05       0
#XS Ineff= 2 , 0
       0                  5460.7       0   379.3
Permanent Ineff=
       F       F
Bank Sta=5016.5,5029.1
XS Rating Curve= 0 ,0
Exp/Cntr=0.3,0.1

Type RM Length L Ch R = 1 ,29271   ,463,463,463
BEGIN DESCRIPTION:
BEE BRANCH 39.0
END DESCRIPTION:
XS GIS Cut Line= 4
      2490975.02     13809774.98        2490675.       13810025.
      2490650.26     13810049.74      2489581.28     13810235.93
#Sta/Elev= 30
  4609.7  391.53    4652  390.27  4744.5  378.93  4786.8  369.48  4793.9  372.22
  4801.7  372.83    4844  372.82  4865.5  375.19  4891.6  375.44  4918.1   375.8
  4943.6  373.94  4978.8  373.89  4986.6  370.32  4986.8  368.82  4987.3  368.32
  4999.4  368.82  5000.2  370.67  5002.7  370.67  5014.4  372.98  5142.1   372.1
  5269.4  376.73  5355.2  378.25  5487.2  376.17  5537.9   372.3  5639.4  372.09
  5676.4  376.82  5822.2  381.68  5903.4  386.48  6023.8  391.15  6120.3  393.62
#Mann= 7 ,-1 , 0
  4609.7     .12       0  4786.8      .1       0  4891.6     .05       0
  4918.1    .035       0  4986.8    .035       0  4999.4    .035       0
  5002.7     .05       0
#XS Ineff= 2 , 0
       0                  5367.6       0  377.57
Permanent Ineff=
       F       F
Bank Sta=4986.8,4999.4
XS Rating Curve= 0 ,0
Exp/Cntr=0.3,0.1

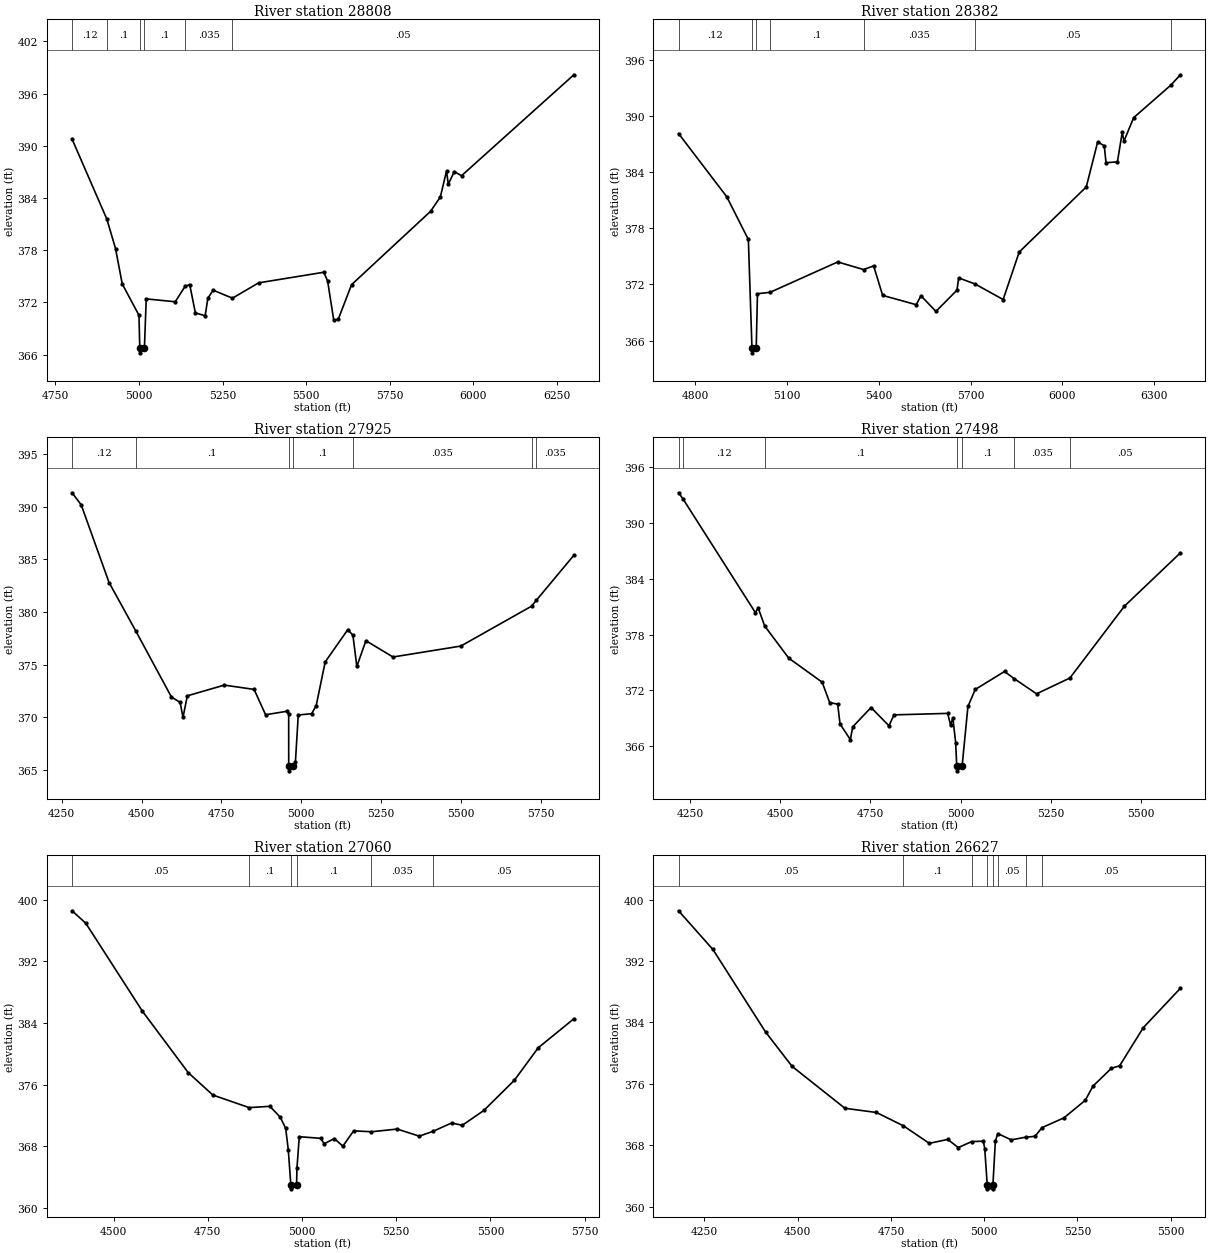
Type RM Length L Ch R = 1 ,28808   ,426,426,426
BEGIN DESCRIPTION:
BEE BRANCH 38.0
END DESCRIPTION:
XS GIS Cut Line= 3
      2490875.04       13809675.        2490675.       13809675.
      2489475.04     13810174.98
#Sta/Elev= 30
  4800.1  390.77  4904.1  381.57  4930.1  378.18  4950.1  374.12  5000.1  370.53
  5002.5  366.71    5003  366.21  5016.3  366.71  5021.8  372.41  5108.5  372.08
  5137.7  373.84  5151.8  374.06  5168.6   370.8  5197.9  370.47    5206  372.47
  5221.7  373.41  5279.6  372.49  5357.6  374.25  5552.6  375.47    5564  374.47
  5582.4  369.94    5596  370.08  5635.5  374.04  5871.7  382.47  5900.9  384.11
  5919.4   387.1  5924.8  385.58  5942.6  387.04  5964.3  386.56  6300.1  398.16
#Mann= 6 ,-1 , 0
  4800.1     .12       0  4904.1      .1       0  5002.5     .05       0
  5016.3      .1       0  5137.7    .035       0  5279.6     .05       0
Bank Sta=5002.5,5016.3
XS Rating Curve= 0 ,0
Exp/Cntr=0.3,0.1

Type RM Length L Ch R = 1 ,28382   ,457,457,457
BEGIN DESCRIPTION:
BEE BRANCH 37.0
END DESCRIPTION:
XS GIS Cut Line= 3
      2490974.98     13809524.99        2490775.       13809375.
      2489575.02     13810074.99
#Sta/Elev= 30
  4746.2  388.11  4903.5  381.37  4974.3   376.8  4986.1   365.2  4986.6   364.7
    5000   365.2    5004  371.01  5045.2  371.16  5266.2   374.4  5350.7  373.59
  5383.6  373.98    5413  370.83  5522.5  369.84  5538.2  370.79    5587  369.12
  5655.7  371.39  5661.4   372.7  5715.4  372.04  5806.6  370.39  5859.1  375.46
  6078.2  382.41  6115.4  387.21  6136.9   386.8  6142.7  384.99  6179.9  385.09
  6195.6  388.22  6201.4  387.31  6232.9   389.8    6355  393.29  6385.4  394.38
#Mann= 7 ,-1 , 0
  4746.2     .12       0  4986.1     .05       0    5000     .12       0
  5045.2      .1       0  5350.7    .035       0  5715.4     .05       0
    6355    .035       0
Bank Sta=4986.1,5000
XS Rating Curve= 0 ,0
Exp/Cntr=0.3,0.1

Type RM Length L Ch R = 1 ,27925   ,427,427,427
BEGIN DESCRIPTION:
BEE BRANCH 36.0
END DESCRIPTION:
XS GIS Cut Line= 3
      2490975.01     13808824.99        2490375.       13809225.
      2489774.97     13809825.03
#Sta/Elev= 30
  4282.8  391.34  4311.4  390.19  4398.5  382.81  4481.6  378.23  4593.8  371.92
  4620.8  371.42  4629.8  369.99  4643.4  372.04    4759  373.06  4852.2  372.65
  4888.2  370.24  4954.3  370.57  4960.4  370.31  4960.5  365.41    4961  364.91
  4975.2  365.41  4981.4  365.71  4990.4  370.22  5032.2  370.34  5046.4   371.1
  5074.6  375.26  5145.3  378.33  5161.4   377.8  5173.6  374.83  5201.9  377.28
  5286.8  375.73  5498.9  376.77  5720.1  380.56  5734.8  381.11  5852.5   385.4
#Mann= 7 ,-1 , 0
  4282.8     .12       0  4481.6      .1       0  4960.5     .05       0
  4975.2      .1       0  5161.4    .035       0  5720.1     .05       0
  5734.8    .035       0
Bank Sta=4960.5,4975.2
XS Rating Curve= 0 ,0
Exp/Cntr=0.3,0.1

Type RM Length L Ch R = 1 ,27498   ,438,438,438
BEGIN DESCRIPTION:
BEE BRANCH 35.0
END DESCRIPTION:
XS GIS Cut Line= 3
      2490824.97     13808375.03        2490225.       13808875.
      2489624.96     13808975.01
#Sta/Elev= 30
  4218.6  393.22  4230.3   392.6  4431.4  380.35  4439.2  380.85    4457  378.92
  4523.8  375.46  4616.2  372.88  4637.1  370.69  4659.2  370.52  4665.7   368.4
  4694.3  366.71  4700.8  368.08  4751.6  370.16  4801.1   368.2  4815.4  369.37
  4963.8  369.53  4971.6  368.29  4978.1  369.03  4985.9  366.38  4988.9  363.86
  4989.4  363.36  5003.7  363.86  5019.9  370.28  5040.1   372.1  5121.2  374.03
  5147.5  373.27  5209.9  371.63  5302.2  373.33  5453.3  381.05  5607.9  386.76
#Mann= 7 ,-1 , 0
  4218.6     .05       0  4230.3     .12       0    4457      .1       0
  4988.9     .05       0  5003.7      .1       0  5147.5    .035       0
  5302.2     .05       0
Bank Sta=4988.9,5003.7
XS Rating Curve= 0 ,0
Exp/Cntr=0.3,0.1

Type RM Length L Ch R = 1 ,27060   ,433,433,433
BEGIN DESCRIPTION:
BEE BRANCH 34.0
END DESCRIPTION:
XS GIS Cut Line= 3
      2490625.01     13808024.98        2490275.       13808525.
      2489674.97     13808925.02
#Sta/Elev= 30
  4389.7  398.56  4426.3  396.93  4575.9  385.57  4697.9  377.58  4763.3  374.67
  4859.7  373.04  4914.6  373.21  4942.1   371.8  4956.5  370.35  4963.4  367.59
  4970.2  363.01  4970.7  362.51  4985.4  363.01  4986.5  365.24  4992.6  369.27
  5049.6  369.06  5058.6  368.35  5085.7  369.03  5108.2  368.04  5136.8  370.03
  5184.2  369.91  5252.4  370.26    5311  369.34  5347.8  369.97  5396.7  371.05
  5425.2  370.75  5482.3  372.67  5563.4  376.59  5626.5  380.79  5721.2  384.56
#Mann= 6 ,-1 , 0
  4389.7     .05       0  4859.7      .1       0  4970.2     .05       0
  4985.4      .1       0  5184.2    .035       0  5347.8     .05       0
Bank Sta=4970.2,4985.4
XS Rating Curve= 0 ,0
Exp/Cntr=0.3,0.1

Type RM Length L Ch R = 1 ,26627   ,418,418,418
BEGIN DESCRIPTION:
BEE BRANCH 33.0
END DESCRIPTION:
XS GIS Cut Line= 3
      2490524.97     13807925.03        2489925.       13808475.
      2489525.01       13808825.
#Sta/Elev= 30
  4180.6  398.56  4272.7  393.52    4414  382.76  4484.9  378.29  4626.7  372.82
  4711.2  372.27  4783.6  370.53    4853  368.25  4902.3  368.76  4930.7   367.7
  4966.8  368.48  4997.8  368.53  5001.6  367.55  5008.3  362.82  5008.8  362.32
    5023  362.32  5023.5  362.82  5030.1  368.54  5036.6  369.52  5072.8   368.7
  5110.9  369.05  5136.4  369.16  5154.9  370.29  5214.2  371.58  5271.2  373.86
    5292  375.72  5341.4  378.04  5363.2  378.35  5426.8  383.33    5526  388.45
#Mann= 8 ,-1 , 0
  4180.6     .05       0  4783.6      .1       0  4966.8    .035       0
  5008.3    .035       0  5023.5    .035       0  5036.6     .05       0
  5110.9    .035       0  5154.9     .05       0
Bank Sta=5008.3,5023.5
XS Rating Curve= 0 ,0
Exp/Cntr=0.3,0.1

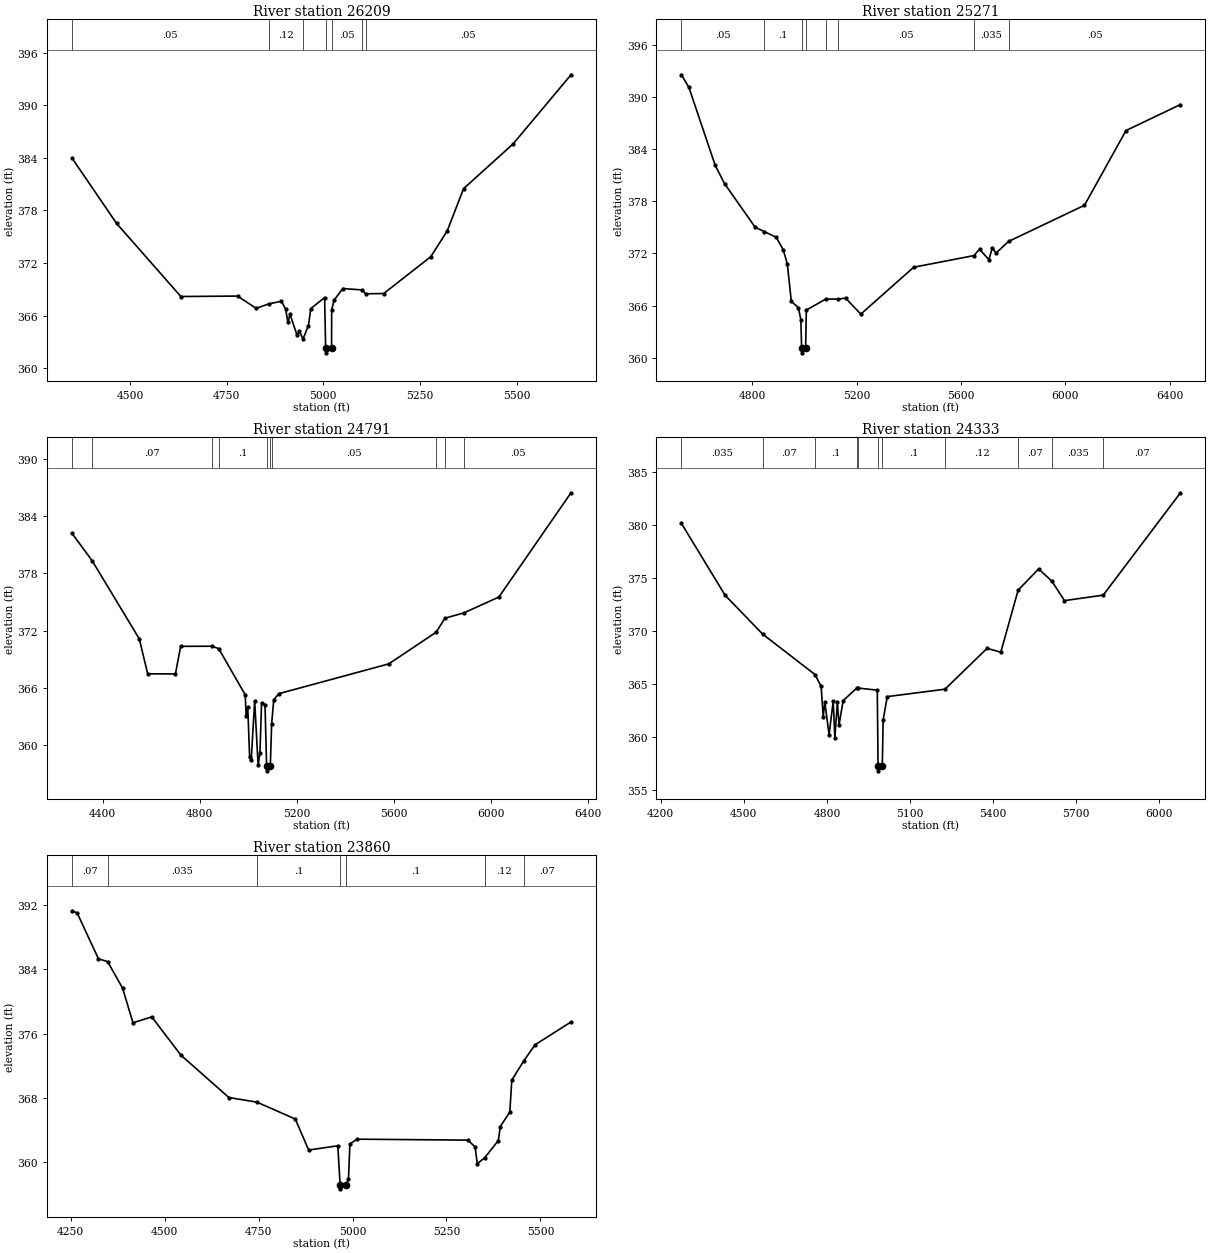
Type RM Length L Ch R = 1 ,26209   ,938,938,938
BEGIN DESCRIPTION:
BEE BRANCH 32.0
END DESCRIPTION:
XS GIS Cut Line= 3
      2490274.96     13807925.02        2489675.       13808175.
      2489274.98     13808675.03
#Sta/Elev= 30
    4350  383.98  4465.3  376.52  4631.6  368.17  4778.4  368.22  4826.1  366.82
  4858.4  367.32  4891.6  367.63  4902.5  366.73  4908.4  365.22  4913.8  366.15
  4932.2  363.72  4937.7  364.26  4947.4  363.32  4961.5  364.86  4967.5  366.79
  5003.2  368.05    5006  362.24  5006.5  361.74  5021.2  362.24  5021.6  366.67
    5028  367.77  5050.4  369.08  5100.7  368.92  5109.2  368.48    5156  368.51
  5277.7  372.71  5320.1  375.64  5362.5  380.48  5490.6  385.59  5640.3  393.48
#Mann= 7 ,-1 , 0
    4350     .05       0  4858.4     .12       0  4947.4     .05       0
    5006     .05       0  5021.2     .05       0  5100.7    .035       0
  5109.2     .05       0
Bank Sta=5006,5021.2
XS Rating Curve= 0 ,0
Exp/Cntr=0.3,0.1

Type RM Length L Ch R = 1 ,25271   ,480,480,480
BEGIN DESCRIPTION:
BEE BRANCH 31.0
END DESCRIPTION:
XS GIS Cut Line= 3
      2490425.03     13807775.02        2490025.       13807525.
      2488824.96     13808325.02
#Sta/Elev= 30
  4527.8  392.52  4556.7  391.06  4657.6   382.1  4693.5     380  4810.9  374.99
  4845.6   374.5  4891.6  373.84  4918.8  372.38  4934.1  370.76  4949.4  366.47
  4976.5  365.76    4986  364.37  4988.9  361.06  4989.4  360.56  5004.2  361.06
    5007  365.48  5082.3  366.75  5126.9  366.73  5157.3  366.85  5215.9  365.01
  5418.7   370.4  5650.1  371.74  5671.1  372.48  5707.1  371.26  5720.6  372.66
  5734.2  372.02  5782.8  373.37  6073.7  377.52  6232.9  386.11  6441.8   389.1
#Mann= 8 ,-1 , 0
  4527.8     .05       0  4845.6      .1       0  4988.9     .05       0
  5004.2      .1       0  5082.3     .12       0  5126.9     .05       0
  5650.1    .035       0  5782.8     .05       0
Bank Sta=4988.9,5004.2
XS Rating Curve= 0 ,0
Exp/Cntr=0.3,0.1

Type RM Length L Ch R = 1 ,24791   ,458,458,458
BEGIN DESCRIPTION:
BEE BRANCH 30.0
END DESCRIPTION:
XS GIS Cut Line= 3
      2490324.98     13806625.02        2489875.       13807175.
      2488974.98     13808175.02
#Sta/Elev= 30
    4273  382.21  4356.1  379.34  4550.1  371.17  4585.2  367.49  4699.4  367.48
  4720.9  370.37    4850  370.38  4877.5  370.13    4987  365.29  4990.7  363.05
  4997.4     364  5004.9   358.8  5011.6  358.49  5025.8  364.66    5040  357.92
  5047.5  359.18  5054.2  364.44  5068.4  364.25    5075  357.83  5075.5  357.33
  5090.3  357.83  5095.7  362.23  5104.3  364.77  5125.2  365.41  5578.2  368.53
  5773.6  371.85  5809.4  373.31  5887.3  373.87  6031.9  375.53    6329  386.45
#Mann= 10 ,-1 , 0
    4273    .035       0  4356.1     .07       0    4850     .05       0
  4877.5      .1       0    5075     .05       0  5090.3      .1       0
  5095.7     .05       0  5773.6    .035       0  5809.4     .07       0
  5887.3     .05       0
Bank Sta=5075,5090.3
XS Rating Curve= 0 ,0
Exp/Cntr=0.3,0.1

Type RM Length L Ch R = 1 ,24333   ,473,473,473
BEGIN DESCRIPTION:
BEE BRANCH 29.0
END DESCRIPTION:
XS GIS Cut Line= 3
      2489975.02     13806374.96        2489575.       13806975.
      2488975.01     13807874.98
#Sta/Elev= 30
  4274.4  380.14  4432.2  373.36  4568.1  369.69  4757.1  365.88  4779.2  364.76
  4786.7  361.92  4792.7  363.26  4807.8   360.2  4822.8  363.37  4828.8  359.92
  4837.8  363.29  4843.8  361.13  4858.8  363.42  4907.6   364.6  4911.1  364.61
    4982  364.41  4984.8   357.3  4985.3   356.8  5000.2   357.3  5003.1  361.58
  5018.1   363.8  5226.6   364.5  5378.6  368.35  5428.2  367.99  5490.9  373.84
  5564.9  375.84  5612.9  374.68  5658.1  372.85  5798.3  373.37  6077.2  383.02
#Mann= 11 ,-1 , 0
  4274.4    .035       0  4568.1     .07       0  4757.1      .1       0
  4907.6     .05       0  4911.1      .1       0  4984.8     .05       0
  5000.2      .1       0  5226.6     .12       0  5490.9     .07       0
  5612.9    .035       0  5798.3     .07       0
Bank Sta=4984.8,5000.2
XS Rating Curve= 0 ,0
Exp/Cntr=0.3,0.1

Type RM Length L Ch R = 1 ,23860   ,470,470,470
BEGIN DESCRIPTION:
BEE BRANCH 28.0
END DESCRIPTION:
XS GIS Cut Line= 3
      2489874.98     13806125.02        2489325.       13806625.
        2489125.     13807174.99
#Sta/Elev= 30
    4253  391.25  4266.8  390.99  4323.6  385.28    4348  384.94  4387.8  381.64
  4415.5  377.34  4465.5  378.07  4543.2  373.31  4670.9  368.05  4745.4  367.48
  4847.6  365.38  4883.1  361.53  4960.8  362.06  4966.9  357.21  4967.4  356.71
    4983  357.21  4989.2  357.93  4992.9  362.27  5011.6  362.88  5306.8  362.76
  5326.1  361.93  5332.1  359.85  5351.8  360.57    5388  362.71  5393.3  364.44
  5418.6  366.26  5423.9  370.21  5455.5  372.59  5485.7   374.6  5581.5  377.44
#Mann= 7 ,-1 , 0
    4253     .07       0    4348    .035       0  4745.4      .1       0
  4966.9     .05       0    4983      .1       0  5351.8     .12       0
  5455.5     .07       0
Bank Sta=4966.9,4983
XS Rating Curve= 0 ,0
Exp/Cntr=0.3,0.1