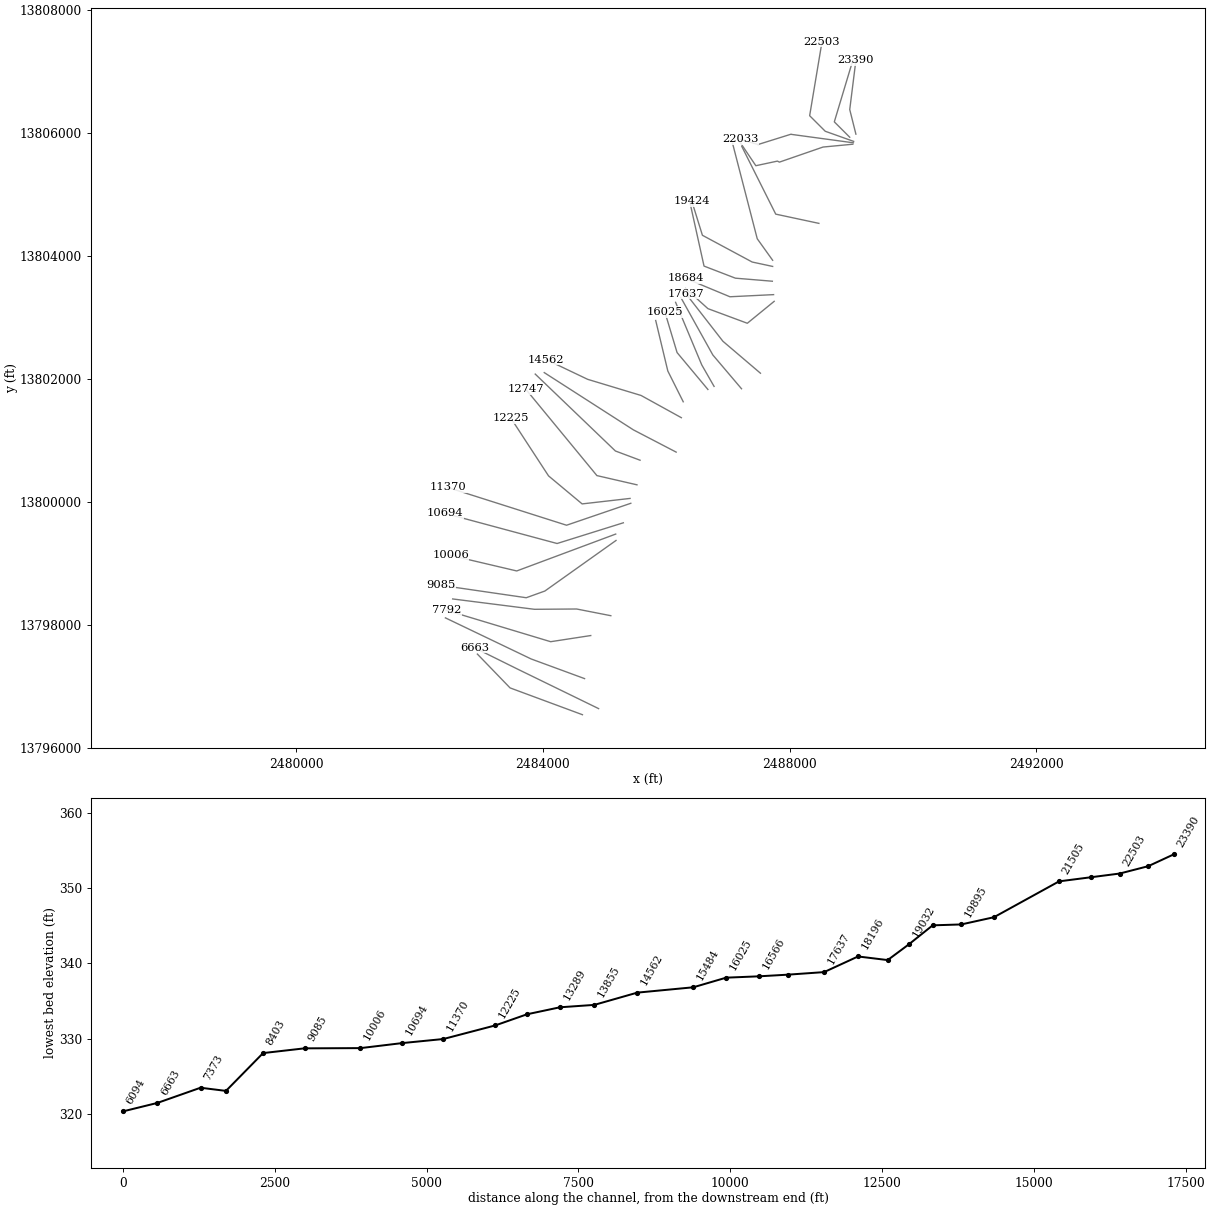
HEC-RAS study BEE BRANCH.prj: BEE BRANCH Base Level Engineering

--- BEE BRANCH.g01 (geometry) --- (continued)

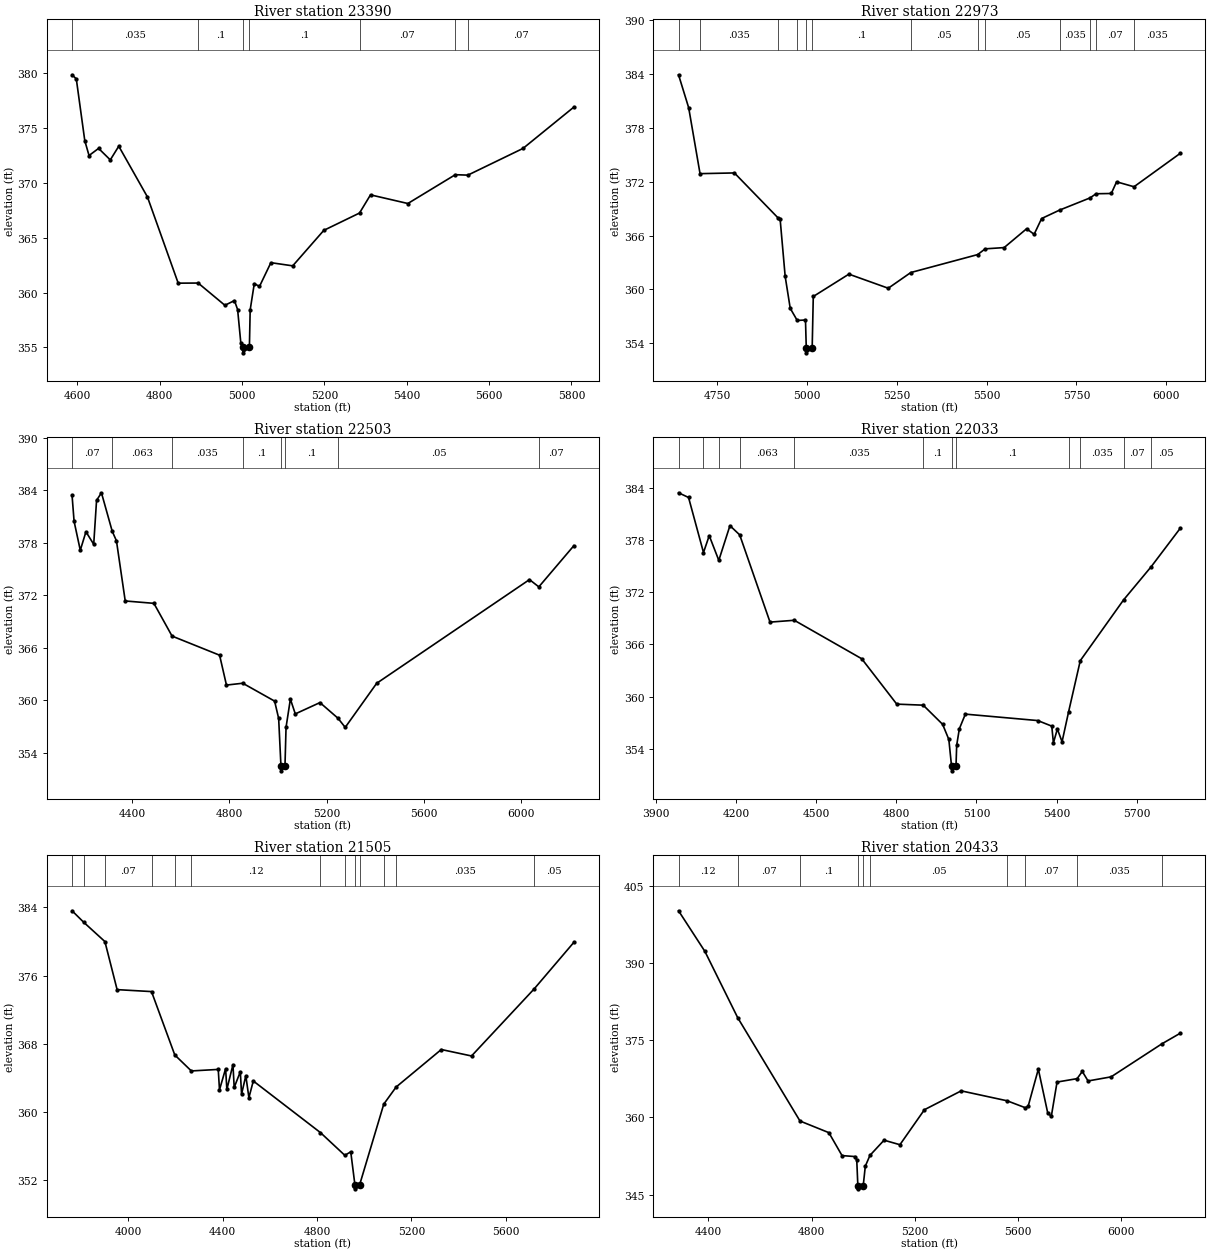
Type RM Length L Ch R = 1 ,23390   ,417,417,417
BEGIN DESCRIPTION:
BEE BRANCH 27.0
END DESCRIPTION:
XS GIS Cut Line= 3
        2489075.     13805975.01        2488975.       13806375.
        2489075.     13807174.97
#Sta/Elev= 30
  4587.3  379.88  4597.6   379.5  4618.2  373.86  4628.5  372.51  4651.7  373.16
  4680.1  372.11  4700.7  373.36  4770.3  368.73    4845  360.86  4893.5  360.87
  4958.4  358.84  4981.6  359.27  4989.3  358.45    4997  355.43  5001.5     355
    5002   354.5  5017.9     355  5019.8  358.42  5029.8  360.82  5042.4  360.56
  5070.1  362.73  5123.1  362.44  5198.6  365.68  5285.3  367.26    5312  368.92
  5402.7  368.13  5517.9  370.76  5548.4  370.72  5682.4  373.16  5805.8  376.93
#Mann= 7 ,-1 , 0
  4587.3    .035       0  4893.5      .1       0  5001.5     .05       0
  5017.9      .1       0  5285.3     .07       0  5517.9     .05       0
  5548.4     .07       0
Bank Sta=5001.5,5017.9
XS Rating Curve= 0 ,0
Exp/Cntr=0.3,0.1

Type RM Length L Ch R = 1 ,22973   ,470,470,470
BEGIN DESCRIPTION:
BEE BRANCH 26.0
END DESCRIPTION:
XS GIS Cut Line= 3
      2488975.01     13805924.99        2488725.       13806175.
        2489025.       13807175.
#Sta/Elev= 30
  4641.9  383.93  4670.2  380.25  4701.8  372.91  4797.5  372.99  4919.3  367.97
  4924.8  367.87  4938.9  361.46    4953   357.9  4972.5  356.55  4995.5   356.6
  4997.7  353.44  4998.2  352.94  5014.1  353.44  5017.2  359.22  5116.4  361.71
    5226  360.14  5288.8  361.89    5475  363.89    5496  364.53  5548.8  364.67
  5611.4  366.77  5632.3  366.15  5653.2  367.91  5703.3  368.85  5788.2  370.21
  5804.7  370.67  5847.2   370.7    5862     372  5910.5  371.45  6039.5  375.18
#Mann= 13 ,-1 , 0
  4641.9     .07       0  4701.8    .035       0  4919.3    .063       0
  4972.5      .1       0  4997.7     .05       0  5014.1      .1       0
  5288.8     .05       0    5475      .1       0    5496     .05       0
  5703.3    .035       0  5788.2     .05       0  5804.7     .07       0
  5910.5    .035       0
Bank Sta=4997.7,5014.1
XS Rating Curve= 0 ,0
Exp/Cntr=0.3,0.1

Type RM Length L Ch R = 1 ,22503   ,470,470,470
BEGIN DESCRIPTION:
BEE BRANCH 25.0
END DESCRIPTION:
XS GIS Cut Line= 4
      2489038.81     13805857.55      2488577.95     13806022.05
        2488325.       13806275.        2488525.     13807474.98
#Sta/Elev= 30
  4153.4  383.39  4161.7  380.44  4187.2  377.14  4210.5  379.25  4242.4  377.82
  4254.1  382.83  4274.2   383.7  4318.6   379.3  4335.9  378.22    4372  371.35
  4489.9  371.08  4564.7  367.34  4760.1  365.16  4788.3  361.75  4855.4  361.96
  4986.3  359.92    5003  357.94  5012.5  352.46    5013  351.96  5028.9  352.46
  5033.4  356.93  5051.2  360.15  5071.4  358.46  5172.8  359.75  5246.8  357.97
  5276.7  356.92    5406  361.95  6034.5  373.79  6072.9  372.96    6217  377.66
#Mann= 8 ,-1 , 0
  4153.4     .07       0  4318.6    .063       0  4564.7    .035       0
  4855.4      .1       0  5012.5     .05       0  5028.9      .1       0
  5246.8     .05       0  6072.9     .07       0
Bank Sta=5012.5,5028.9
XS Rating Curve= 0 ,0
Exp/Cntr=0.3,0.1

Type RM Length L Ch R = 1 ,22033   ,528,528,528
BEGIN DESCRIPTION:
BEE BRANCH 24.0
END DESCRIPTION:
XS GIS Cut Line= 5
      2489034.26     13805834.55      2488031.89     13805970.98
        2488025.       13805975.      2487489.17     13805806.96
      2487204.09     13805889.73
#Sta/Elev= 30
    3985  383.44  4022.5   382.9  4078.4  376.57  4099.9  378.51  4135.7  375.67
  4177.4  379.66  4213.9   378.6  4327.4  368.57  4418.3  368.78  4670.5  364.36
  4801.7  359.14  4900.7  359.02  4973.3  356.82  4996.6  355.08  5006.9  351.97
  5007.4  351.47  5023.4  351.97    5026  354.41    5036  356.31  5058.5  357.99
  5329.5  357.25  5381.9  356.61    5388  354.68  5402.8  356.28  5420.4  354.81
    5445  358.28  5488.6  364.14  5650.5  371.12  5753.9  374.94    5863  379.37
#Mann= 12 ,-1 , 0
    3985     .07       0  4078.4     .12       0  4135.7     .07       0
  4213.9    .063       0  4418.3    .035       0  4900.7      .1       0
  5006.9     .05       0  5023.4      .1       0    5445     .07       0
  5488.6    .035       0  5650.5     .07       0  5753.9     .05       0
Bank Sta=5006.9,5023.4
XS Rating Curve= 0 ,0
Exp/Cntr=0.3,0.1

Type RM Length L Ch R = 1 ,21505   ,1072,1072,1072
BEGIN DESCRIPTION:
BEE BRANCH 23.0
END DESCRIPTION:
XS GIS Cut Line= 6
      2489024.98     13805811.56      2488542.19     13805765.58
      2487834.33     13805520.33      2487802.61     13805537.06
      2487452.38     13805462.09      2487174.98     13805875.02
#Sta/Elev= 30
  3762.4  383.61  3811.3  382.27  3901.5  379.99  3953.2  374.34  4098.9  374.11
  4197.5  366.66  4267.6  364.78  4381.6  364.96  4386.9  362.56  4412.8  365.05
  4418.1  362.61  4443.9  365.52  4449.2  362.84  4475.1  364.69  4480.4  362.06
  4498.4  364.22  4511.5  361.64  4530.1   363.6  4814.6  357.53  4917.8  354.86
  4942.9  355.27  4960.4  351.42  4960.9  350.92  4980.8  351.42  5082.8  360.88
  5135.1  362.89  5326.5   367.3  5454.5  366.54    5720  374.43    5888   379.9
#Mann= 13 ,-1 , 0
  3762.4     .07       0  3811.3     .12       0  3901.5     .07       0
  4098.9     .12       0  4197.5    .063       0  4267.6     .12       0
  4814.6     .07       0  4917.8    .035       0  4960.4    .035       0
  4980.8    .035       0  5082.8     .07       0  5135.1    .035       0
    5720     .05       0
Bank Sta=4960.4,4980.8
XS Rating Curve= 0 ,0
Exp/Cntr=0.3,0.1

Type RM Length L Ch R = 1 ,20433   ,538,538,538
BEGIN DESCRIPTION:
BEE BRANCH 22.0
END DESCRIPTION:
XS GIS Cut Line= 3
      2488474.97     13804525.01        2487775.       13804675.
        2487225.       13805775.
#Sta/Elev= 30
  4284.4   400.1  4386.6  392.22  4513.9  379.35  4755.4  359.31  4867.3  357.05
  4918.4   352.6  4969.6  352.41  4975.5  351.65  4979.8  346.65  4980.3  346.15
  5000.3  346.65  5008.6  350.54  5026.6  352.64  5081.3  355.59  5142.8  354.71
  5237.8   361.5  5380.4  365.16  5558.7  363.23  5629.4  361.88  5640.3  362.22
  5679.5  369.37  5715.8  360.91  5729.8   360.2  5752.1  366.87  5829.9  367.53
    5850  368.93  5872.3  367.08  5961.8  367.88  6158.4  374.28  6230.1  376.35
#Mann= 10 ,-1 , 0
  4284.4     .12       0  4513.9     .07       0  4755.4      .1       0
  4979.8     .05       0  5000.3      .1       0  5026.6     .05       0
  5558.7    .035       0  5629.4     .07       0  5829.9    .035       0
  6158.4     .05       0
Bank Sta=4979.8,5000.3
XS Rating Curve= 0 ,0
Exp/Cntr=0.3,0.1

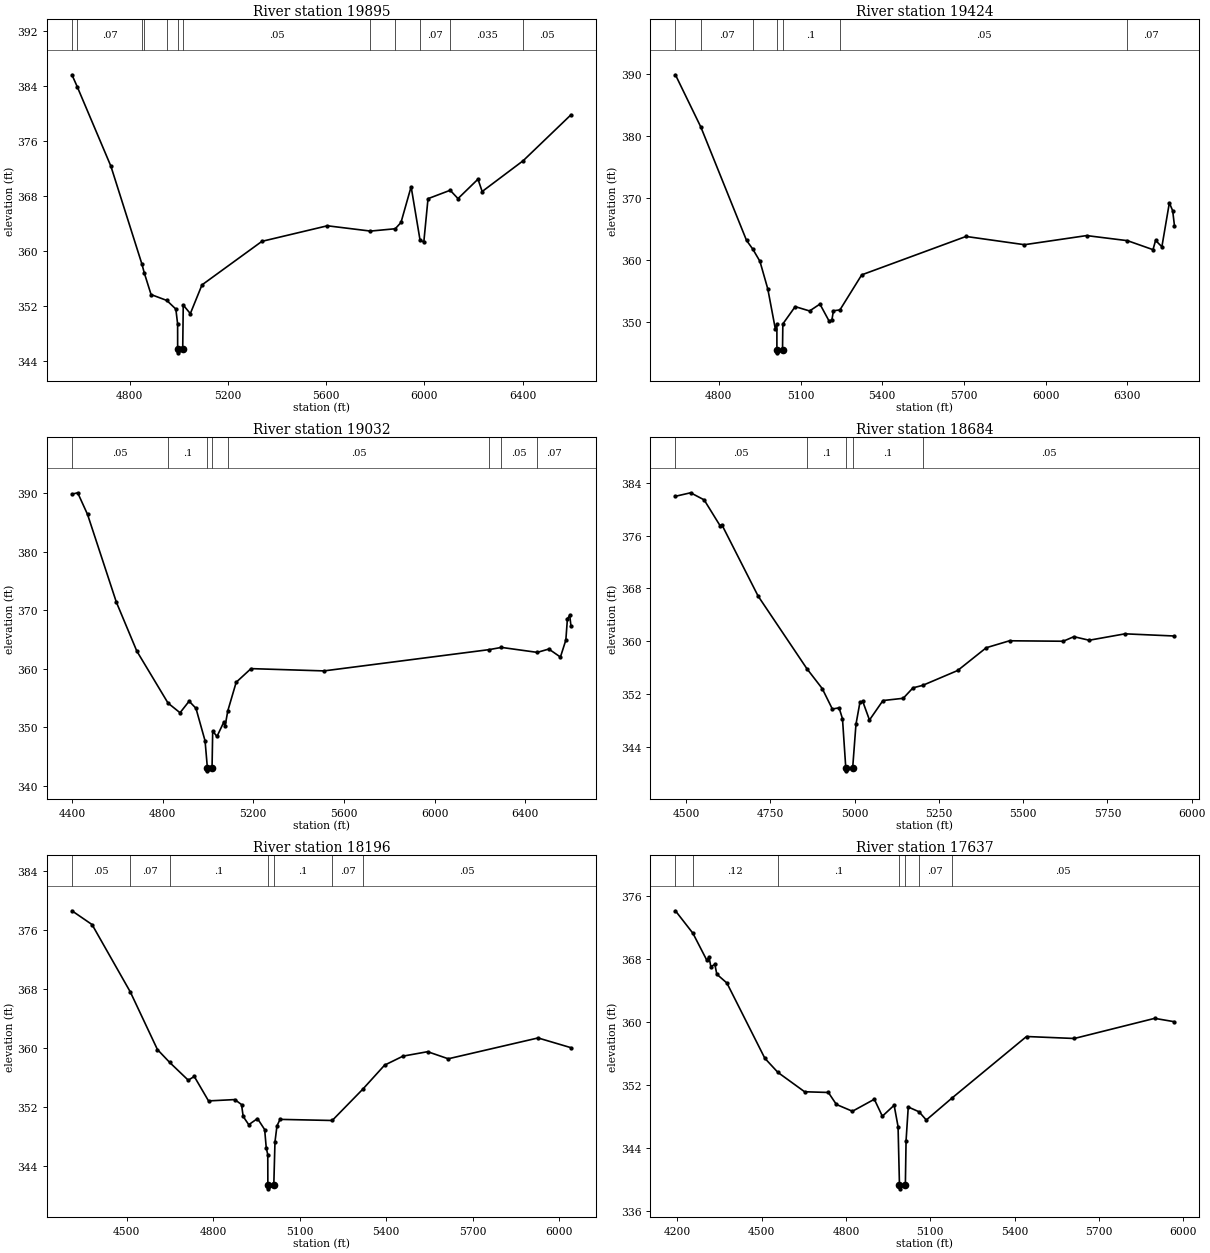
Type RM Length L Ch R = 1 ,19895   ,471,471,471
BEGIN DESCRIPTION:
BEE BRANCH 21.0
END DESCRIPTION:
XS GIS Cut Line= 3
      2487725.01     13803924.99        2487475.       13804275.
        2487075.     13805824.99
#Sta/Elev= 30
  4565.5  385.59    4587  383.86    4724  372.31  4850.7  358.04  4859.9   356.8
  4887.5  353.66  4951.6   352.8  4988.3  351.55  4995.6  349.38  4995.7  345.69
  4996.2  345.19  5016.3  345.69  5018.5  352.13  5047.3  350.89  5094.7  355.06
  5338.7  361.39    5605  363.65  5780.3  362.88  5881.2  363.22  5904.5  364.13
  5945.8  369.33  5982.1  361.56  5997.4  361.29  6014.5  367.59  6104.7  368.81
  6136.5   367.6  6217.8  370.42  6234.9  368.63  6401.9  373.11  6596.4  379.78
#Mann= 12 ,-1 , 0
  4565.5     .05       0    4587     .07       0  4850.7     .05       0
  4859.9      .1       0  4951.6     .05       0  4995.7     .05       0
  5016.3     .05       0  5780.3     .07       0  5881.2    .035       0
  5982.1     .07       0  6104.7    .035       0  6401.9     .05       0
Bank Sta=4995.7,5016.3
XS Rating Curve= 0 ,0
Exp/Cntr=0.3,0.1

Type RM Length L Ch R = 1 ,19424   ,392,392,392
BEGIN DESCRIPTION:
BEE BRANCH 20.0
END DESCRIPTION:
XS GIS Cut Line= 4
      2487725.04     13803824.99      2487393.43     13803896.44
        2486586.     13804331.21      2486415.42     13804881.41
#Sta/Elev= 30
  4640.5  389.89  4734.1  381.44  4901.5   363.2  4924.7  361.78  4950.8  359.82
  4979.7  355.36  5007.3  348.93    5013  349.73  5013.1  345.57  5013.6  345.07
  5033.7  345.57  5034.9  349.73  5080.2  352.52  5133.1  351.82    5171  352.93
  5205.1  350.16    5215  350.39  5220.7  351.85  5244.5  351.99  5324.5  357.64
  5707.4  363.83    5922   362.5  6150.1  363.97  6300.2  363.15  6393.9   361.7
  6403.3  363.19  6426.5  362.17  6453.9  369.24  6466.1  367.98  6472.8   365.5
#Mann= 7 ,-1 , 0
  4640.5     .05       0  4734.1     .07       0  4924.7      .1       0
  5013.1     .05       0  5033.7      .1       0  5244.5     .05       0
  6300.2     .07       0
Bank Sta=5013.1,5033.7
XS Rating Curve= 0 ,0
Exp/Cntr=0.3,0.1

Type RM Length L Ch R = 1 ,19032   ,348,348,348
BEGIN DESCRIPTION:
X18193
END DESCRIPTION:
XS GIS Cut Line= 4
      2487720.27     13803584.48      2487121.09       13803634.
      2486612.18     13803830.54      2486384.72     13804860.56
#Sta/Elev= 30
  4400.4  389.88  4425.8  390.12  4469.2  386.42  4596.3  371.41  4686.6  363.03
  4824.4  354.13  4877.3  352.48  4917.4  354.46  4947.5  353.24  4987.7  347.67
  4997.9  343.04  4998.4  342.54  5018.5  343.04  5021.3  349.33  5040.3  348.43
  5070.5  350.89  5075.8  350.14    5088  352.81    5125   357.7  5190.4  360.03
    5512  359.64  6240.6  363.28  6295.2  363.66  6453.1  362.81  6504.1  363.38
  6555.3  362.01  6579.2  364.92  6586.1  368.55  6596.3  369.14    6602  367.26
#Mann= 8 ,-1 , 0
  4400.4     .05       0  4824.4      .1       0  4997.9     .05       0
  5018.5      .1       0    5088     .05       0  6240.6     .07       0
  6295.2     .05       0  6453.1     .07       0
Bank Sta=4997.9,5018.5
XS Rating Curve= 0 ,0
Exp/Cntr=0.3,0.1

Type RM Length L Ch R = 1 ,18684   ,488,488,488
BEGIN DESCRIPTION:
X18192
END DESCRIPTION:
XS GIS Cut Line= 3
      2487740.06     13803366.61      2487031.96     13803331.95
      2486319.49     13803628.81
#Sta/Elev= 30
  4468.3  381.93  4513.4  382.46  4553.5  381.39    4601  377.47    4606  377.64
  4713.7  366.85  4858.4  355.88  4903.9  352.88  4933.9  349.79  4953.9  349.97
    4964  348.32  4973.7  340.95  4974.2  340.45  4994.3  340.95    5004  347.48
  5015.8  350.81    5024  350.95  5044.1  348.13  5084.1  351.07  5144.2  351.41
  5173.2  352.99  5201.8  353.36  5305.8  355.61  5390.6  359.05  5459.6   360.1
  5618.9  360.03  5650.6  360.72  5695.8  360.18  5802.3  361.15  5949.1  360.82
#Mann= 5 ,-1 , 0
  4468.3     .05       0  4858.4      .1       0  4973.7     .05       0
  4994.3      .1       0  5201.8     .05       0
Bank Sta=4973.7,4994.3
XS Rating Curve= 0 ,0
Exp/Cntr=0.3,0.1

Type RM Length L Ch R = 1 ,18196   ,559,559,559
BEGIN DESCRIPTION:
X18191
END DESCRIPTION:
XS GIS Cut Line= 4
      2487749.94     13803257.66      2487314.21     13802901.15
      2486675.44     13803138.83      2486313.93     13803465.68
#Sta/Elev= 30
  4309.7  378.56  4379.6  376.69  4512.5  367.56  4606.4  359.78  4649.1  358.03
  4713.4  355.63  4734.2  356.14  4783.7  352.83  4874.9  353.01  4898.3  352.33
  4903.9  350.73  4923.3  349.61  4953.6  350.44  4978.5  348.95    4984  346.48
  4989.3  345.55  4989.6  341.43  4990.1  340.93  5010.2  341.43  5014.3  347.28
  5021.2  349.45  5031.9  350.33  5212.9  350.18  5319.1  354.42  5394.7  357.67
  5458.7  358.89    5544  359.49  5615.6  358.53  5927.2  361.35  6041.6  360.03
#Mann= 7 ,-1 , 0
  4309.7     .05       0  4512.5     .07       0  4649.1      .1       0
  4989.6     .05       0  5010.2      .1       0  5212.9     .07       0
  5319.1     .05       0
Bank Sta=4989.6,5010.2
XS Rating Curve= 0 ,0
Exp/Cntr=0.3,0.1

Type RM Length L Ch R = 1 ,17637   ,595,595,595
BEGIN DESCRIPTION:
X18190
END DESCRIPTION:
XS GIS Cut Line= 3
      2487527.09     13802089.11      2486918.07     13802609.01
      2486320.05     13803380.01
#Sta/Elev= 30
  4192.8  374.08  4255.1  371.23  4304.6  367.81  4312.4  368.22  4318.9  367.01
  4333.2  367.28  4340.2  366.04    4376  364.93  4511.1  355.39  4557.7   353.6
  4652.7  351.15  4737.2  351.06  4765.8  349.54  4822.9  348.68  4900.8   350.2
  4929.4  348.05  4971.3  349.44  4985.3  346.74  4990.3  339.35  4990.8  338.85
  5011.3  339.35  5013.8  344.95  5021.6  349.22  5060.1  348.61  5085.8  347.57
  5176.5  350.33  5442.5  358.15  5612.7   357.9  5898.7  360.45  5969.3  360.02
#Mann= 7 ,-1 , 0
  4192.8     .07       0  4255.1     .12       0  4557.7      .1       0
  4990.3     .05       0  5011.3      .1       0  5060.1     .07       0
  5176.5     .05       0
Bank Sta=4990.3,5011.3
XS Rating Curve= 0 ,0
Exp/Cntr=0.3,0.1

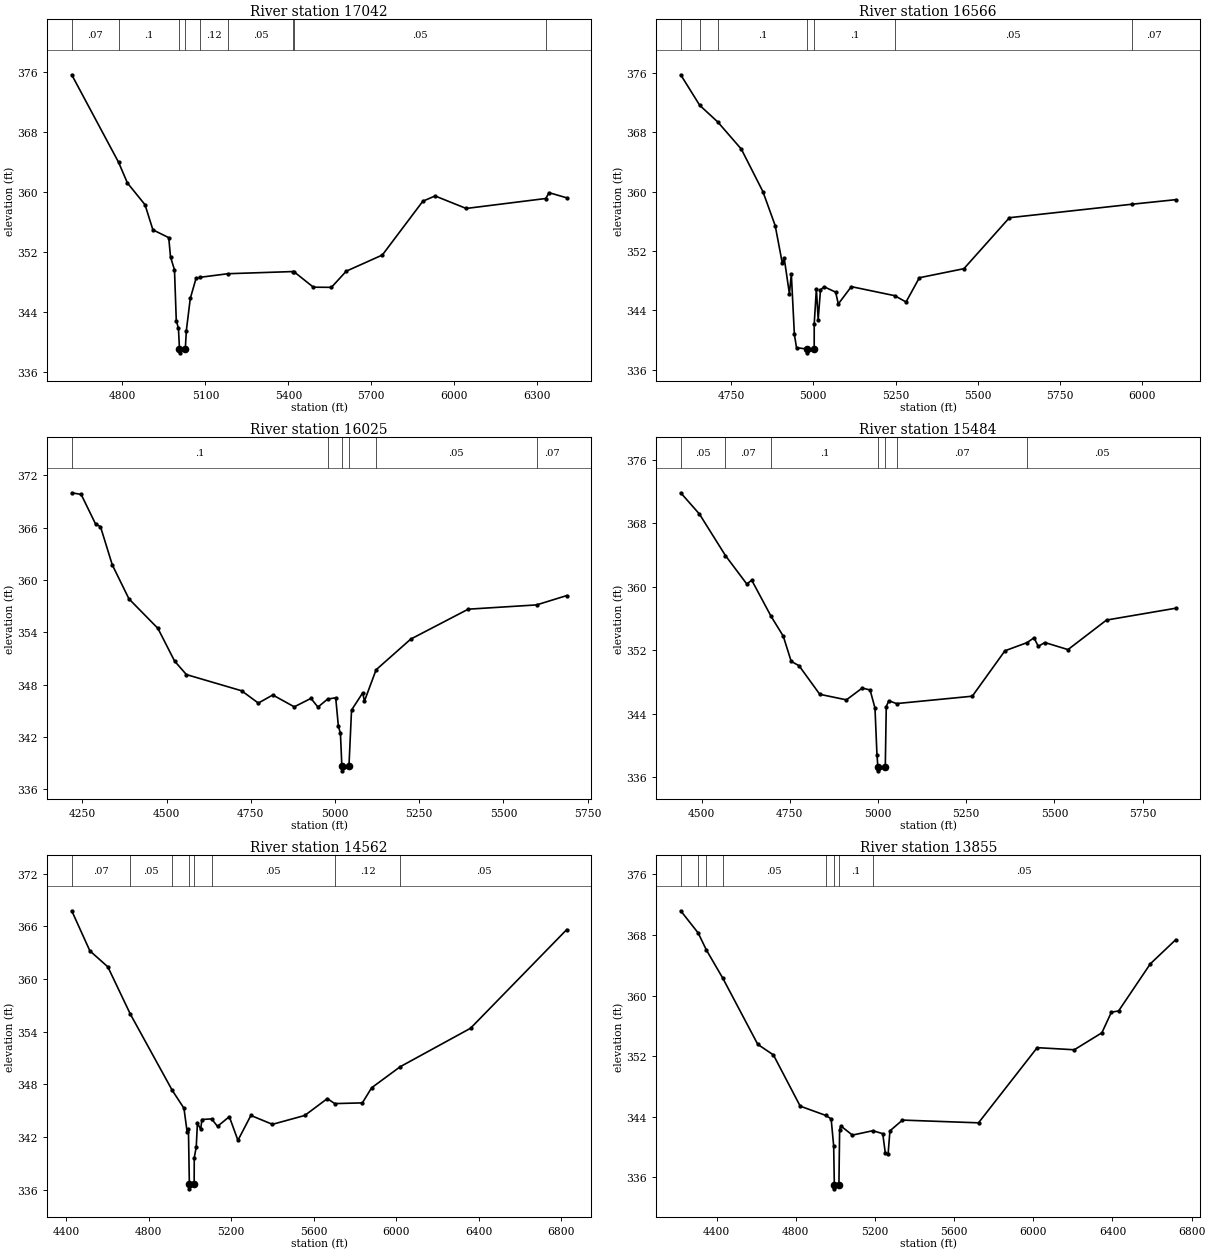
Type RM Length L Ch R = 1 ,17042   ,476,476,476
BEGIN DESCRIPTION:
X18189
END DESCRIPTION:
XS GIS Cut Line= 3
      2487220.12     13801836.55      2486754.67     13802386.18
      2486235.29     13803321.06
#Sta/Elev= 30
  4616.8  375.66  4786.4  363.95    4818  361.21  4881.7   358.3  4910.3  354.94
  4967.5   353.9    4974  351.31  4988.3   349.6  4994.8  342.81  5002.6  341.79
  5006.4  339.01  5006.9  338.51  5027.4  339.01  5031.2  341.49  5045.5  345.79
  5066.3  348.46  5080.5   348.6  5181.3  349.08  5416.8  349.37  5421.6  349.31
  5490.5  347.28  5555.7  347.26  5609.4  349.42  5739.8  351.58  5886.3  358.77
  5930.5  359.47    6043   357.8  6330.6  359.13  6342.4  359.91  6406.5  359.22
#Mann= 9 ,-1 , 0
  4616.8     .07       0  4786.4      .1       0  5006.4     .05       0
  5027.4      .1       0  5080.5     .12       0  5181.3     .05       0
  5416.8      .1       0  5421.6     .05       0  6330.6     .07       0
Bank Sta=5006.4,5027.4
XS Rating Curve= 0 ,0
Exp/Cntr=0.3,0.1

Type RM Length L Ch R = 1 ,16566   ,541,541,541
BEGIN DESCRIPTION:
BEE BRANCH 19.0
END DESCRIPTION:
XS GIS Cut Line= 3
      2486775.01     13801874.98        2486575.       13802225.
      2486151.14     13803241.43
#Sta/Elev= 30
  4596.9  375.76  4654.8  371.64  4709.6   369.4  4781.2  365.74  4846.7  360.02
  4884.1  355.43  4905.7  350.36  4911.5  351.03  4927.3  346.24  4933.1  348.92
  4942.4  340.77  4948.9  338.99  4981.6  338.79  4982.1  338.29  5002.6  338.79
  5002.7   342.2  5009.2   346.9  5014.7  342.78  5021.7  346.75  5032.5   347.2
  5067.7  346.47  5075.9  344.88  5115.4  347.21  5247.6  345.99  5281.7  345.14
  5322.2  348.41  5457.6  349.63  5595.9   356.5    5967  358.31  6101.3  358.93
#Mann= 7 ,-1 , 0
  4596.9      .1       0  4654.8     .12       0  4709.6      .1       0
  4981.6     .05       0  5002.6      .1       0  5247.6     .05       0
    5967     .07       0
Bank Sta=4981.6,5002.6
XS Rating Curve= 0 ,0
Exp/Cntr=0.3,0.1

Type RM Length L Ch R = 1 ,16025   ,541,541,541
BEGIN DESCRIPTION:
BEE BRANCH 18.0
END DESCRIPTION:
XS GIS Cut Line= 3
      2486675.01     13801824.99        2486175.       13802425.
      2485977.26     13803084.35
#Sta/Elev= 30
  4218.4     370  4246.4  369.81  4289.4   366.4  4303.7  366.12  4338.8  361.73
  4388.3  357.83  4474.2  354.45  4523.7   350.7  4558.8  349.15  4722.8  347.29
  4772.3  345.88  4815.2  346.81    4879  345.45  4928.5  346.42  4949.3  345.42
    4978  346.34    5002  346.49  5009.9  343.22    5016  342.44  5020.3  338.61
  5020.8  338.11  5041.3  338.61    5049  345.08  5082.1  347.05  5087.3  346.11
  5121.9   349.7  5224.8  353.22  5395.4  356.65  5598.2  357.14  5687.8  358.21
#Mann= 6 ,-1 , 0
  4218.4      .1       0    4978     .07       0  5020.3     .05       0
  5041.3     .07       0  5121.9     .05       0  5598.2     .07       0
Bank Sta=5020.3,5041.3
XS Rating Curve= 0 ,0
Exp/Cntr=0.3,0.1

Type RM Length L Ch R = 1 ,15484   ,922,922,922
BEGIN DESCRIPTION:
BEE BRANCH 17.0
END DESCRIPTION:
XS GIS Cut Line= 3
        2486275.     13801624.99        2486025.       13802125.
      2485828.71     13802945.73
#Sta/Elev= 30
  4440.9  371.85    4494  369.17  4567.6  363.95  4628.2  360.36  4642.2  360.84
  4696.9   356.3  4731.6  353.79    4754  350.62  4776.3  350.07    4835  346.47
  4910.5  345.77  4955.2  347.25  4977.6  347.02  4991.5  344.74  4997.1  338.88
  4999.7  337.33  5000.2  336.83  5020.7  337.33  5023.5  344.93  5030.8  345.66
  5052.6   345.3  5267.3  346.23  5359.8  351.95  5422.7  352.98  5442.1  353.59
  5454.4  352.51  5472.9  352.99  5538.5   352.1  5647.7  355.82  5843.8  357.31
#Mann= 7 ,-1 , 0
  4440.9     .05       0  4567.6     .07       0  4696.9      .1       0
  4999.7     .05       0  5020.7      .1       0  5052.6     .07       0
  5422.7     .05       0
Bank Sta=4999.7,5020.7
XS Rating Curve= 0 ,0
Exp/Cntr=0.3,0.1

Type RM Length L Ch R = 1 ,14562   ,707,707,707
BEGIN DESCRIPTION:
X18194
END DESCRIPTION:
XS GIS Cut Line= 4
      2486244.61     13801366.16      2485591.03     13801727.61
      2484724.49     13801990.05      2484051.03     13802311.92
#Sta/Elev= 30
  4427.8  367.76  4515.7   363.2  4602.8  361.38  4711.6  356.01  4914.8  347.33
  4971.6  345.29  4987.3  342.54  4993.3  342.97  4997.8  336.62  4998.3  336.12
    5021  336.62  5021.6  339.68  5031.1  340.86  5036.8  343.57  5052.9  342.92
  5058.6  344.01  5105.6  344.08  5134.2  343.23  5191.4  344.33  5233.2  341.64
  5295.9  344.47  5400.4  343.46  5557.1  344.47  5666.4  346.39  5702.2  345.82
  5836.2   345.9    5881  347.62  6019.9  350.02  6360.2  354.39  6826.5  365.62
#Mann= 8 ,-1 , 0
  4427.8     .07       0  4711.6     .05       0  4914.8      .1       0
  4997.8     .05       0    5021      .1       0  5105.6     .05       0
  5702.2     .12       0  6019.9     .05       0
Bank Sta=4997.8,5021
XS Rating Curve= 0 ,0
Exp/Cntr=0.3,0.1

Type RM Length L Ch R = 1 ,13855   ,566,566,566
BEGIN DESCRIPTION:
BEE BRANCH 16.0
END DESCRIPTION:
XS GIS Cut Line= 3
      2486160.46     13800806.61      2485467.24     13801168.07
      2484021.39     13802098.96
#Sta/Elev= 30
  4218.1  371.18  4306.2  368.26  4347.8  366.01  4430.7  362.29  4607.7  353.55
  4686.6  352.16    4822   345.4  4949.8  344.19  4978.3  343.73  4991.1  340.15
  4994.4  334.99  4994.9  334.49  5017.6  334.99  5021.2  342.31  5027.1  342.79
  5085.8  341.58    5189  342.16    5239  341.77  5252.3  339.16  5266.1  339.06
  5275.4  342.14  5338.7  343.56    5723   343.2  6019.5  353.12    6207  352.84
  6346.3  355.08  6394.5   357.8  6430.8  357.96  6591.2  364.18  6719.5  367.36
#Mann= 8 ,-1 , 0
  4218.1     .12       0  4306.2     .05       0  4347.8     .07       0
  4430.7     .05       0  4949.8      .1       0  4994.4     .05       0
  5017.6      .1       0    5189     .05       0
Bank Sta=4994.4,5017.6
XS Rating Curve= 0 ,0
Exp/Cntr=0.3,0.1

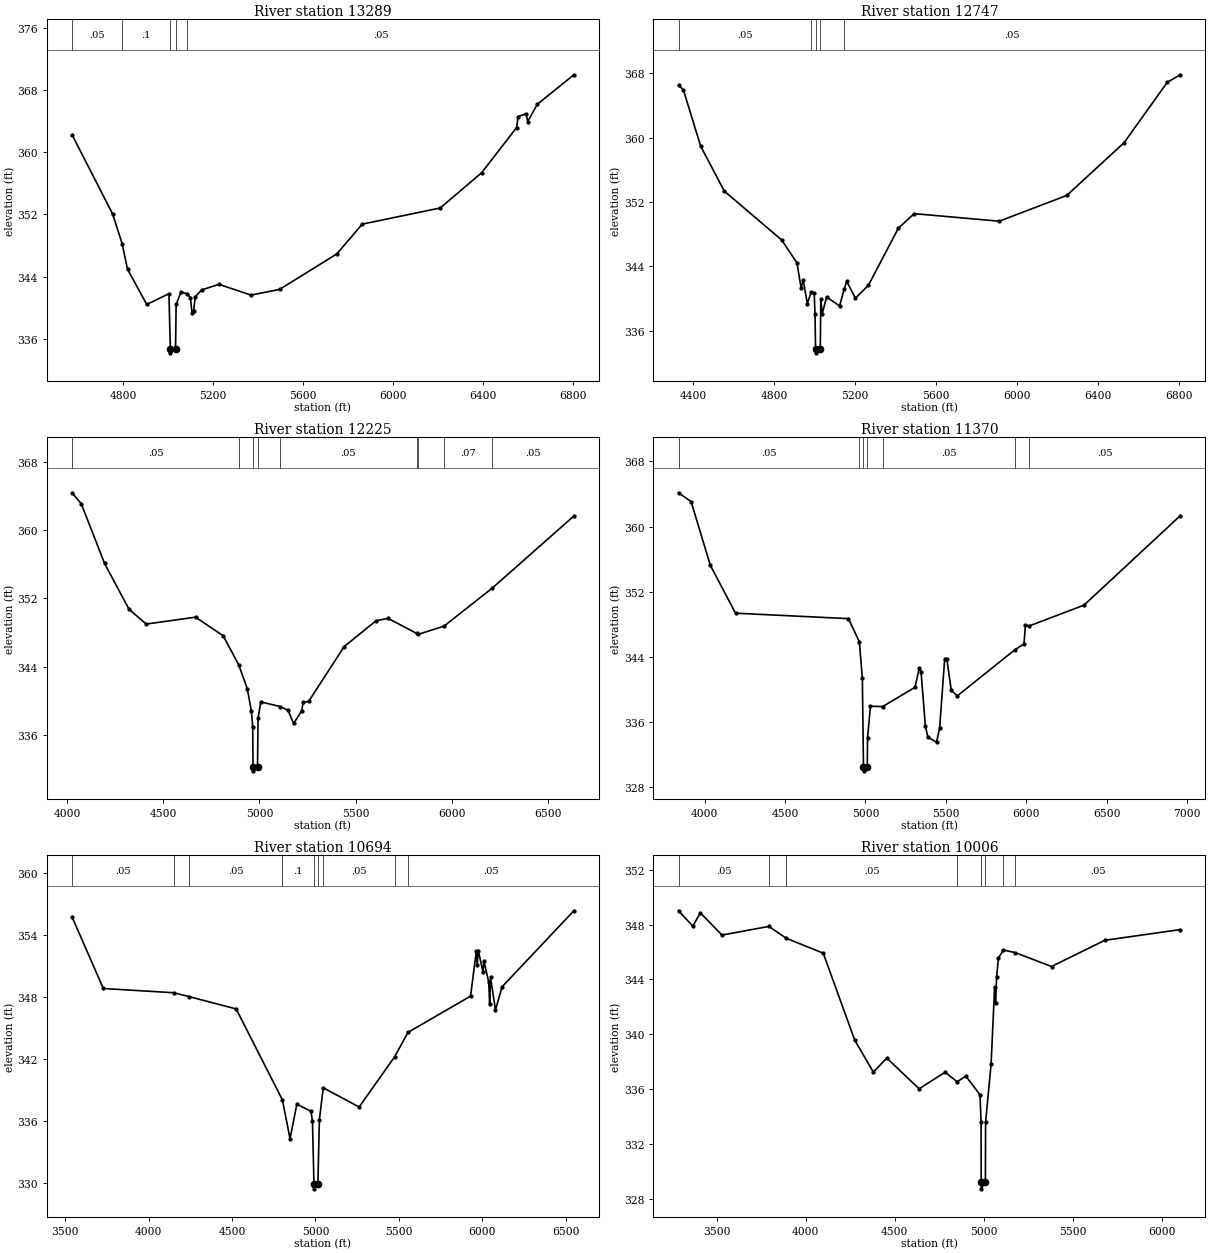
Type RM Length L Ch R = 1 ,13289   ,542,542,542
BEGIN DESCRIPTION:
BEE BRANCH 15.0
END DESCRIPTION:
XS GIS Cut Line= 3
      2485575.01       13800675.        2485175.       13800825.
      2483874.98     13802075.02
#Sta/Elev= 30
  4572.7  362.26  4753.4  352.03  4795.4  348.22  4819.2  344.94  4904.7   340.4
  5003.4  341.79  5009.5  334.67    5010  334.17  5032.7  334.67  5035.3   340.4
  5056.4  341.95  5084.9  341.79  5098.8  341.28    5106  339.34    5113  339.54
  5120.2  341.38  5148.5  342.28  5226.2  342.99  5367.7  341.61    5495  342.34
  5749.5  346.91  5862.7  350.75  6209.2  352.83  6393.2  357.36  6548.8  363.19
  6555.7  364.61  6591.3  364.98  6598.2  363.96  6640.6  366.18  6803.4  369.99
#Mann= 5 ,-1 , 0
  4572.7     .05       0  4795.4      .1       0  5009.5     .05       0
  5032.7      .1       0  5084.9     .05       0
Bank Sta=5009.5,5032.7
XS Rating Curve= 0 ,0
Exp/Cntr=0.3,0.1

Type RM Length L Ch R = 1 ,12747   ,522,522,522
BEGIN DESCRIPTION:
BEE BRANCH 14.0
END DESCRIPTION:
XS GIS Cut Line= 3
      2485524.98     13800275.01        2484875.       13800425.
      2483725.02     13801824.98
#Sta/Elev= 30
  4328.1  366.49    4352  365.93  4437.5  358.92  4553.9  353.35  4837.8  347.26
  4913.1  344.42  4933.6   341.3  4943.8   342.3  4964.4  339.36    4984  340.83
  4998.4  340.62  5002.3  338.05  5005.1  333.74  5005.6  333.24  5028.3  333.74
    5031  339.92  5037.5  338.09  5059.7  340.18  5123.6  339.07  5146.7  341.17
  5158.8  342.12  5201.8  340.04  5265.7  341.62  5414.2  348.74  5492.4  350.54
  5912.2   349.6  6245.8   352.8    6530  359.38  6742.4  366.87  6806.9   367.8
#Mann= 5 ,-1 , 0
  4328.1     .05       0    4984      .1       0  5005.1     .05       0
  5028.3      .1       0  5146.7     .05       0
Bank Sta=5005.1,5028.3
XS Rating Curve= 0 ,0
Exp/Cntr=0.3,0.1

Type RM Length L Ch R = 1 ,12225   ,855,855,855
BEGIN DESCRIPTION:
X18195
END DESCRIPTION:
XS GIS Cut Line= 4
      2485412.79     13800053.95      2484635.36     13799964.82
      2484090.68     13800420.37      2483481.62     13801356.24
#Sta/Elev= 30
  4025.6   364.4  4073.7   363.1  4194.5   356.1    4322  350.72  4411.2  348.99
  4667.6   349.8  4811.6  347.61  4892.5  344.19  4936.7  341.39  4957.5  338.84
    4965   336.9  4966.7  332.26  4967.2  331.76    4990  332.26  4992.6  337.93
    5007  339.85    5108  339.31  5148.8  338.85  5177.4  337.32  5220.4  338.83
  5226.9  339.82  5255.5   339.9  5440.3  346.34  5606.2  349.38  5669.5  349.65
  5816.6   347.9  5823.8  347.77  5959.1  348.74    6209  353.18  6634.8  361.67
#Mann= 9 ,-1 , 0
  4025.6     .05       0  4892.5      .1       0  4966.7     .05       0
    4990      .1       0    5108     .05       0  5816.6     .07       0
  5823.8     .05       0  5959.1     .07       0    6209     .05       0
Bank Sta=4966.7,4990
XS Rating Curve= 0 ,0
Exp/Cntr=0.3,0.1

Type RM Length L Ch R = 1 ,11370   ,676,676,676
BEGIN DESCRIPTION:
BEE BRANCH 13.0
END DESCRIPTION:
XS GIS Cut Line= 3
      2485425.04     13799975.01      2484382.82      13799618.2
      2482458.33     13800231.67
#Sta/Elev= 30
  3837.3  364.15  3915.6  363.06  4035.4  355.21  4191.9  349.34  4894.3  348.67
    4962  345.82  4980.8  341.33  4987.8  330.45  4988.3  329.95  5011.4  330.45
    5013  334.02  5031.1  337.89  5107.6  337.86  5308.1  340.22  5335.1  342.61
  5345.9  342.16  5372.5  335.51  5387.9  334.11  5442.2  333.46  5461.4   335.2
  5492.9  343.69  5506.6  343.68  5533.6  339.88    5571  339.16  5929.4  344.84
  5986.2  345.56  5994.9  347.85  6019.9  347.78  6359.7  350.33  6958.8  361.34
#Mann= 7 ,-1 , 0
  3837.3     .05       0    4962      .1       0  4987.8     .05       0
  5011.4      .1       0  5107.6     .05       0  5929.4    .035       0
  6019.9     .05       0
Bank Sta=4987.8,5011.4
XS Rating Curve= 0 ,0
Exp/Cntr=0.3,0.1

Type RM Length L Ch R = 1 ,10694   ,688,688,688
BEGIN DESCRIPTION:
X18196
END DESCRIPTION:
XS GIS Cut Line= 3
      2485303.83     13799657.82      2484229.32      13799321.1
      2482412.11     13799811.31
#Sta/Elev= 30
    3541  355.75  3728.4  348.82  4149.9  348.41    4243  348.03  4524.8  346.84
  4801.8  338.03  4847.6  334.27  4888.5  337.61  4973.5  336.92  4982.2  335.94
  4991.1  329.91  4991.6  329.41  5014.7  329.91  5023.7  336.12  5046.7   339.2
  5261.9  337.34  5474.1  342.19    5555  344.57  5929.9  348.08  5964.6  352.46
  5969.8  351.13  5976.5  352.49  6004.5  350.41  6009.7  351.49  6038.7  349.44
  6044.4  347.34  6049.6   349.9  6079.2  346.74  6119.1  348.99  6549.2  356.35
#Mann= 9 ,-1 , 0
    3541     .05       0  4149.9     .07       0    4243     .05       0
  4801.8      .1       0  4991.1     .05       0  5014.7      .1       0
  5046.7     .05       0  5474.1    .035       0    5555     .05       0
Bank Sta=4991.1,5014.7
XS Rating Curve= 0 ,0
Exp/Cntr=0.3,0.1

Type RM Length L Ch R = 1 ,10006   ,921,921,921
BEGIN DESCRIPTION:
BEE BRANCH 12.0
END DESCRIPTION:
XS GIS Cut Line= 3
      2485180.03      13799474.6        2483575.       13798875.
      2482501.17       13799128.
#Sta/Elev= 30
  3286.2     349  3366.3  347.88  3408.7  348.85  3529.9  347.23  3792.9  347.86
  3890.6     347  4098.5  345.91    4275  339.58  4380.1  337.24  4455.1  338.27
  4636.6  336.03    4783  337.24  4849.8  336.54  4898.9  336.95  4978.2   335.6
  4984.4  333.63    4985  329.24  4985.5  328.74  5008.7  329.24  5009.8   333.6
  5040.7  337.84  5060.5  343.45  5065.7  342.28  5071.5  344.18  5081.8  345.55
  5109.4  346.14  5176.4  345.95  5379.7  344.94  5679.1  346.85  6102.8  347.63
#Mann= 8 ,-1 , 0
  3286.2     .05       0  3792.9     .07       0  3890.6     .05       0
  4849.8      .1       0    4985     .05       0  5008.7      .1       0
  5109.4    .035       0  5176.4     .05       0
Bank Sta=4985,5008.7
XS Rating Curve= 0 ,0
Exp/Cntr=0.3,0.1

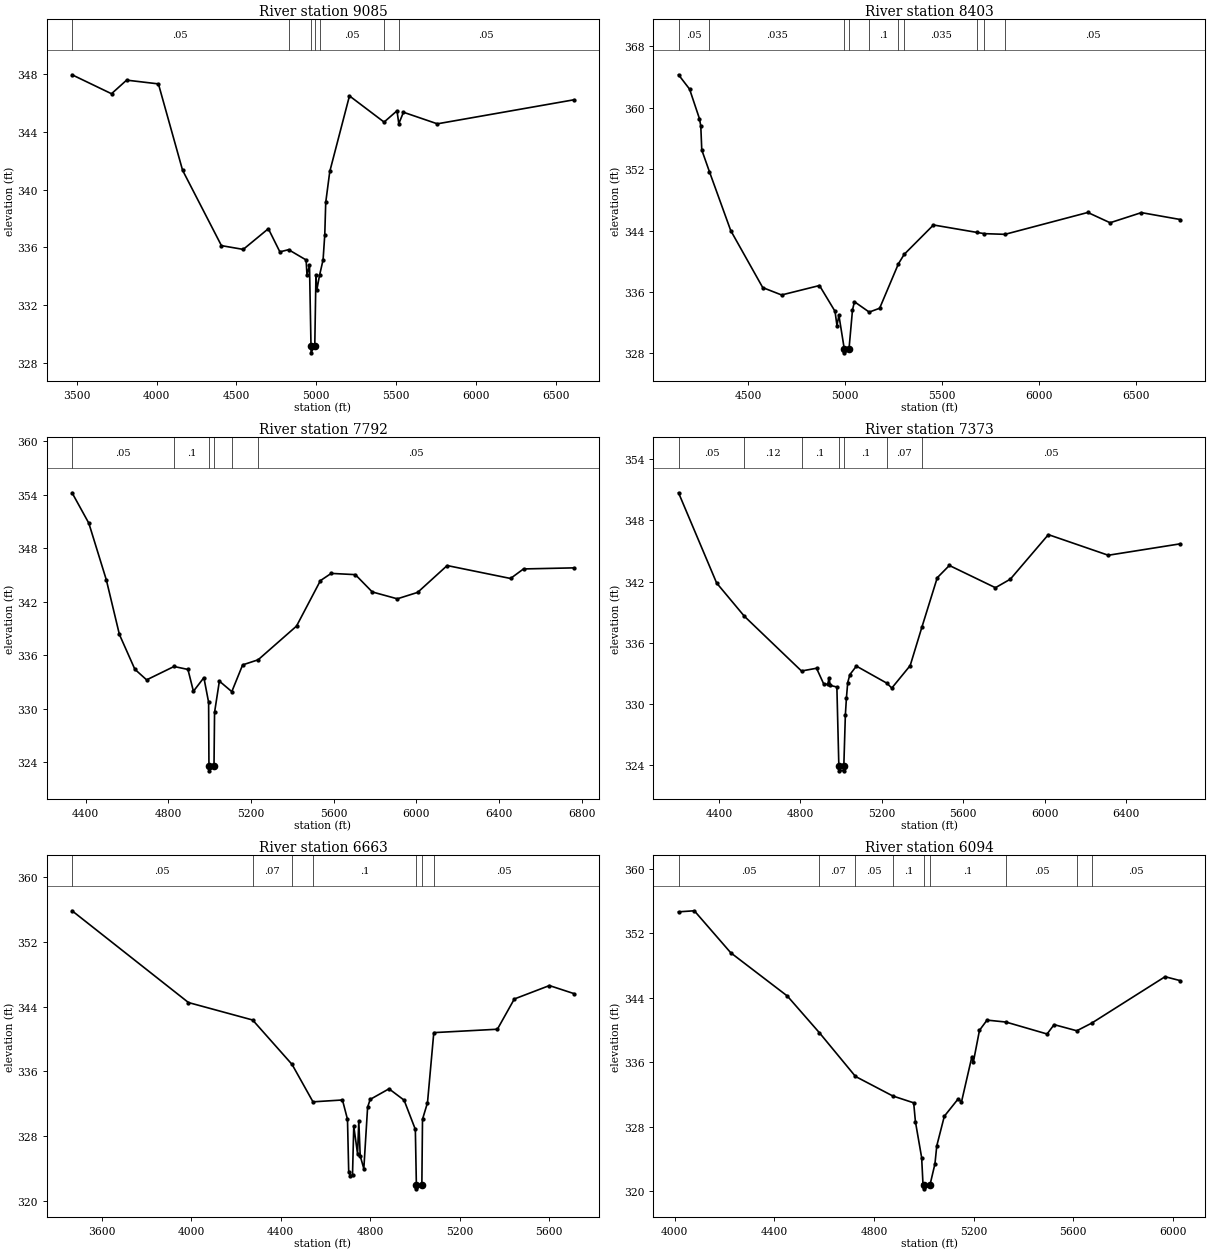
Type RM Length L Ch R = 1 ,9085    ,682,682,682
BEGIN DESCRIPTION:
X18197
END DESCRIPTION:
XS GIS Cut Line= 4
      2485184.98     13799370.61      2484031.26     13798548.65
       2483729.2     13798439.71      2482338.91     13798642.56
#Sta/Elev= 30
  3471.1  347.93  3718.1  346.62  3812.8  347.56  4011.9   347.3  4163.2  341.33
  4406.6  336.12  4543.1  335.86  4700.4  337.29  4772.6  335.69  4827.2  335.84
  4936.9  335.13  4942.4  334.09  4958.1  334.75  4967.5  329.21    4968  328.71
  4991.2  329.21  4998.5  334.08  5003.8  333.05  5020.9  334.06  5043.2  335.14
  5053.8  336.88  5059.8  339.11  5085.2  341.25  5208.4  346.47  5425.3  344.66
  5506.1  345.44  5517.5  344.55  5546.5  345.34  5758.7  344.54  6613.8   346.2
#Mann= 7 ,-1 , 0
  3471.1     .05       0  4827.2      .1       0  4967.5     .05       0
  4991.2      .1       0  5020.9     .05       0  5425.3    .035       0
  5517.5     .05       0
Bank Sta=4967.5,4991.2
XS Rating Curve= 0 ,0
Exp/Cntr=0.3,0.1

Type RM Length L Ch R = 1 ,8403    ,611,611,611
BEGIN DESCRIPTION:
X18198
END DESCRIPTION:
XS GIS Cut Line= 4
      2485100.85     13798147.56      2484546.23      13798256.5
       2483862.9     13798251.55       2482535.9      13798419.9
#Sta/Elev= 30
  4142.6  364.31  4199.5  362.44  4250.5  358.58  4257.3  357.63  4262.4  354.51
  4301.6   351.7  4411.6  344.01  4576.6  336.58  4673.8  335.62    4869  336.85
  4949.1  333.49  4959.1  331.64  4969.1  332.97  4996.9  328.58  4997.4  328.08
  5021.2  328.58  5039.1  333.65  5049.1  334.74  5125.3  333.39  5179.1  333.89
    5276  339.69  5305.6  340.91  5456.4  344.74    5683  343.76  5719.2  343.61
  5825.1  343.52  6251.9  346.37  6366.8  345.03  6528.1  346.35  6728.8  345.45
#Mann= 10 ,-1 , 0
  4142.6     .05       0  4301.6    .035       0  4996.9    .035       0
  5021.2    .035       0  5125.3      .1       0    5276     .05       0
  5305.6    .035       0    5683     .05       0  5719.2    .035       0
  5825.1     .05       0
Bank Sta=4996.9,5021.2
XS Rating Curve= 0 ,0
Exp/Cntr=0.3,0.1

Type RM Length L Ch R = 1 ,7792    ,419,419,419
BEGIN DESCRIPTION:
BEE BRANCH 11.0
END DESCRIPTION:
XS GIS Cut Line= 3
      2484775.02       13797825.        2484125.       13797725.
       2482431.9     13798236.68
#Sta/Elev= 30
  4334.8  354.23  4415.8  350.82  4500.5  344.46  4563.7  338.34  4638.4  334.44
  4695.3  333.25  4827.8  334.75  4895.1  334.42  4921.6  331.97  4972.2   333.5
  4995.1  330.73  4996.7  323.55  4997.2  323.05  5021.1  323.55  5023.8   329.6
  5047.1  333.11  5107.2  331.93  5159.6  334.93  5234.4   335.5  5420.1  339.28
  5535.7  344.38  5587.9  345.19  5704.6  345.05  5786.4  343.11  5907.5  342.34
  6005.8  343.06  6148.6  346.07    6455  344.62  6517.7  345.69  6761.2  345.81
#Mann= 6 ,-1 , 0
  4334.8     .05       0  4827.8      .1       0  4996.7     .05       0
  5021.1      .1       0  5107.2     .07       0  5234.4     .05       0
Bank Sta=4996.7,5021.1
XS Rating Curve= 0 ,0
Exp/Cntr=0.3,0.1

Type RM Length L Ch R = 1 ,7373    ,710,710,710
BEGIN DESCRIPTION:
BEE BRANCH 10.0
END DESCRIPTION:
XS GIS Cut Line= 3
      2484675.01       13797125.      2483808.43     13797444.43
       2482418.5     13798112.19
#Sta/Elev= 30
  4200.9  350.71  4388.1  341.87  4524.1  338.62  4805.1  333.25    4879  333.52
    4915  331.95  4934.6  331.95  4939.9  332.58    4947  331.84  4978.9  331.68
  4988.6  323.97  4989.1  323.47  5012.6  323.47  5013.1  323.97  5020.6  328.93
  5025.9  330.63  5032.2  332.12  5042.9   332.9  5074.8  333.73  5224.3  332.06
  5248.8  331.58  5339.1  333.78  5396.9  337.56  5472.2  342.39  5531.6  343.59
    5758  341.41  5831.4  342.25  6018.1  346.61  6312.4  344.59  6666.5  345.71
#Mann= 7 ,-1 , 0
  4200.9     .05       0  4524.1     .12       0  4805.1      .1       0
  4988.6     .05       0  5013.1      .1       0  5224.3     .07       0
  5396.9     .05       0
Bank Sta=4988.6,5013.1
XS Rating Curve= 0 ,0
Exp/Cntr=0.3,0.1

Type RM Length L Ch R = 1 ,6663    ,569,569,569
BEGIN DESCRIPTION:
BEE BRANCH 9.0
END DESCRIPTION:
XS GIS Cut Line= 3
      2484902.75      13796637.3      2483585.61     13797281.02
      2482888.69     13797627.01
#Sta/Elev= 30
  3466.7  355.84  3987.3  344.49  4274.3  342.33  4450.7  336.83  4544.1  332.21
  4675.9  332.44  4698.4  330.05  4703.9  323.54  4710.8  323.08  4720.9  323.18
  4726.5   329.2  4743.4  325.79    4749  329.83  4755.3  325.53  4771.5  323.94
  4788.4  331.54  4799.8  332.51  4884.1  333.82  4951.5  332.42  5001.9   328.8
  5006.5  321.95    5007  321.45    5031  321.95  5033.9  330.05  5056.2   332.1
  5084.4  340.77  5368.8  341.19  5444.5  344.93  5601.4  346.59  5710.8   345.6
#Mann= 7 ,-1 , 0
  3466.7     .05       0  4274.3     .07       0  4450.7     .12       0
  4544.1      .1       0  5006.5     .05       0    5031      .1       0
  5084.4     .05       0
Bank Sta=5006.5,5031
XS Rating Curve= 0 ,0
Exp/Cntr=0.3,0.1

Type RM Length L Ch R = 1 ,6094    ,463,463,463
BEGIN DESCRIPTION:
X18199
END DESCRIPTION:
XS GIS Cut Line= 3
      2484640.36     13796538.26      2483466.77     13796974.02
      2482936.94     13797523.65
#Sta/Elev= 30
  4015.3  354.65  4078.7  354.78  4225.2  349.57  4452.1  344.22  4581.2  339.66
  4725.9  334.25  4875.7  331.83  4959.7  330.98  4966.7  328.64  4991.7  324.19
  4997.1   320.9  5000.8  320.82  5001.3  320.32  5025.3  320.82  5045.1  323.42
  5052.5  325.66  5082.8  329.32  5138.2  331.46  5151.7  331.09  5193.6  336.71
    5199  335.98    5224  339.97  5254.3  341.23  5330.3  340.99  5495.4  339.51
  5523.7  340.67  5614.8  339.91  5674.8  340.86  5969.3  346.61  6030.6  346.12
#Mann= 9 ,-1 , 0
  4015.3     .05       0  4581.2     .07       0  4725.9     .05       0
  4875.7      .1       0  5000.8     .05       0  5025.3      .1       0
  5330.3     .05       0  5614.8     .12       0  5674.8     .05       0
Bank Sta=5000.8,5025.3
XS Rating Curve= 0 ,0
Exp/Cntr=0.3,0.1