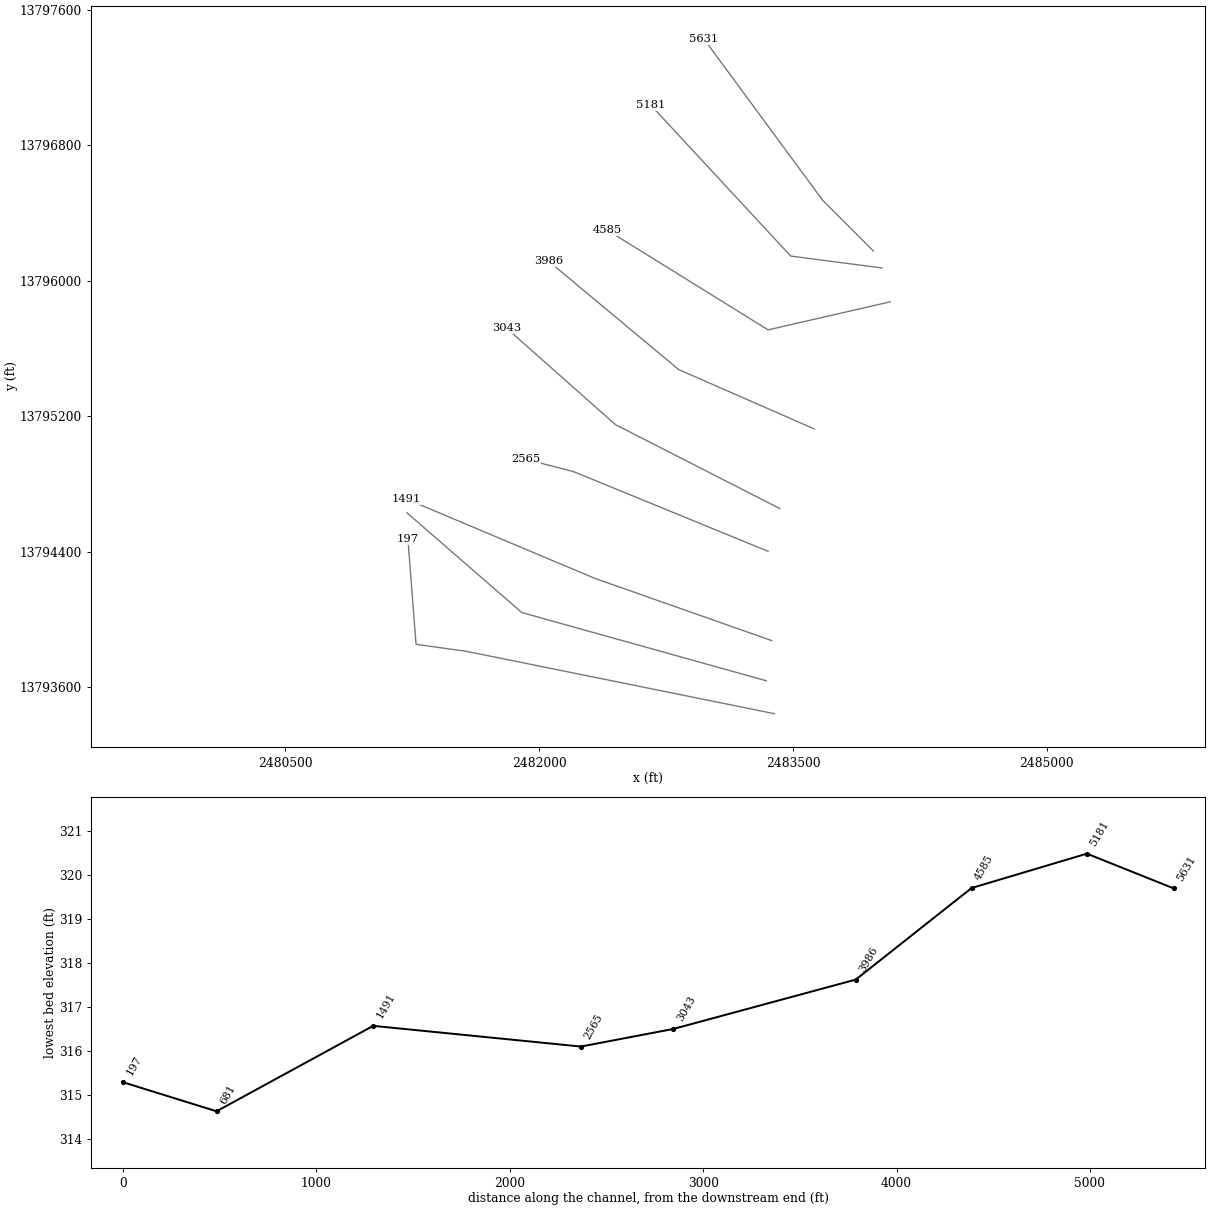
HEC-RAS study BEE BRANCH.prj: BEE BRANCH Base Level Engineering

--- BEE BRANCH.g01 (geometry) --- (continued)

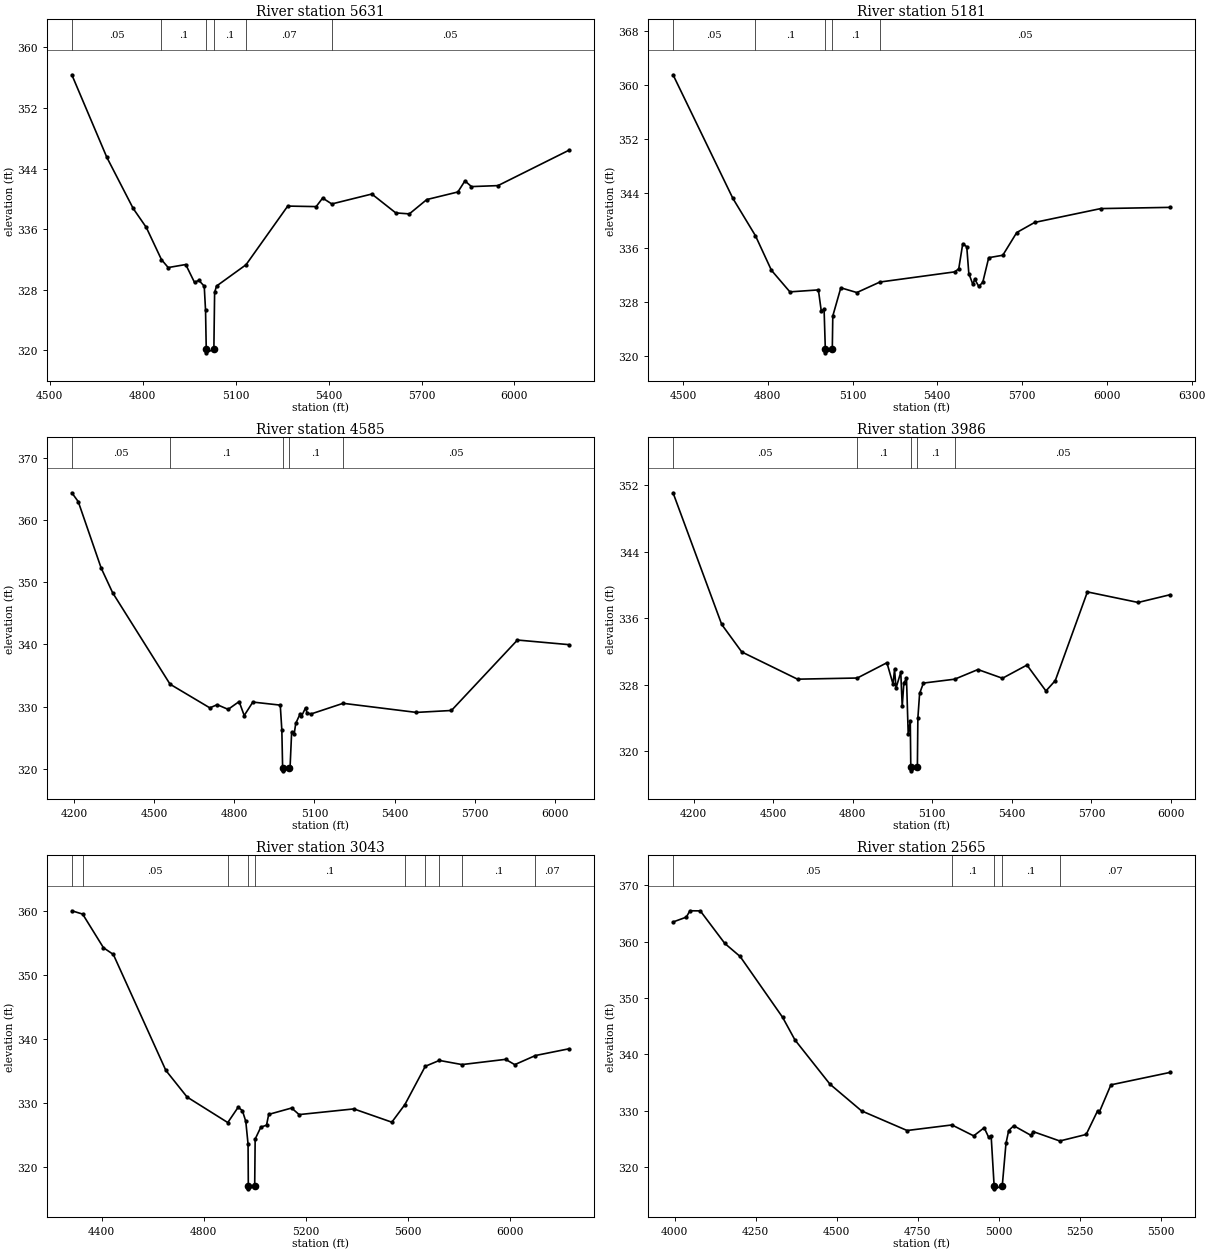
Type RM Length L Ch R = 1 ,5631    ,450,450,450
BEGIN DESCRIPTION:
BEE BRANCH 8.0
END DESCRIPTION:
XS GIS Cut Line= 3
        2483975.       13796175.        2483675.       13796475.
      2482975.01     13797424.99
#Sta/Elev= 30
  4571.2  356.37  4684.3  345.47  4769.2  338.74  4811.6  336.23  4860.6  331.98
  4882.3  330.94  4938.9  331.34  4967.2  328.98  4981.3  329.26  4998.6  328.48
  5002.8  325.32  5005.1  320.19  5005.6  319.69  5029.7  320.19  5032.1  327.66
  5038.3   328.5  5133.5  331.31  5268.1  339.05  5359.9  338.98  5380.8  340.11
  5410.3  339.33  5539.6  340.64  5616.8  338.15  5660.7  338.02    5717  339.91
  5817.3  340.91  5840.1  342.37  5861.2  341.62  5946.8  341.75  6175.5  346.41
#Mann= 6 ,-1 , 0
  4571.2     .05       0  4860.6      .1       0  5005.1     .05       0
  5029.7      .1       0  5133.5     .07       0  5410.3     .05       0
Bank Sta=5005.1,5029.7
XS Rating Curve= 0 ,0
Exp/Cntr=0.3,0.1

Type RM Length L Ch R = 1 ,5181    ,596,596,596
BEGIN DESCRIPTION:
BEE BRANCH 7.0
END DESCRIPTION:
XS GIS Cut Line= 3
      2484025.02       13796075.      2483486.57     13796145.11
      2482659.79     13797036.25
#Sta/Elev= 30
  4464.9  361.48  4676.7  343.25  4756.5  337.75  4813.1  332.65  4878.4  329.47
  4979.2  329.76  4989.3  326.67  4999.4  326.88  5003.8  320.98  5004.3  320.48
  5028.4  320.98  5030.2  325.92  5058.6  330.07  5115.3  329.37  5196.9  330.92
  5461.7  332.42  5475.9  332.88    5490  336.57  5504.2  336.12  5511.5  332.17
  5525.7  330.59  5532.5  331.34  5546.7  330.27  5560.9  330.89  5581.9  334.51
  5631.7  334.87  5681.1  338.22  5744.6  339.71  5978.2  341.75  6223.5  341.93
#Mann= 5 ,-1 , 0
  4464.9     .05       0  4756.5      .1       0  5003.8     .05       0
  5028.4      .1       0  5196.9     .05       0
Bank Sta=5003.8,5028.4
XS Rating Curve= 0 ,0
Exp/Cntr=0.3,0.1

Type RM Length L Ch R = 1 ,4585    ,599,599,599
BEGIN DESCRIPTION:
BEE BRANCH 6.0
END DESCRIPTION:
XS GIS Cut Line= 3
      2484075.02     13795875.01      2483352.88     13795709.36
      2482402.17     13796298.61
#Sta/Elev= 30
  4192.3  364.34  4216.3  362.92  4302.1  352.25    4345  348.29  4559.8  333.61
  4708.6  329.81  4736.1  330.32  4777.1  329.57  4818.2  330.82  4837.2  328.58
  4869.5  330.74  4972.1  330.25    4978  326.25  4980.9   320.2  4981.4   319.7
  5005.8   320.2  5008.8  320.28  5014.6  325.86  5024.1   325.6    5030  327.31
  5045.4  328.76  5051.3  328.43  5066.6  329.82  5072.5  328.95  5087.9  328.84
  5207.2  330.54  5481.3  329.08  5612.5  329.39  5859.4   340.7  6051.7  339.96
#Mann= 5 ,-1 , 0
  4192.3     .05       0  4559.8      .1       0  4980.9     .05       0
  5005.8      .1       0  5207.2     .05       0
Bank Sta=4980.9,5005.8
XS Rating Curve= 0 ,0
Exp/Cntr=0.3,0.1

Type RM Length L Ch R = 1 ,3986    ,943,943,943
BEGIN DESCRIPTION:
BEE BRANCH 5.0
END DESCRIPTION:
XS GIS Cut Line= 3
      2483625.01       13795125.        2482825.       13795475.
      2482055.55     13796115.39
#Sta/Elev= 30
  4122.3  351.11  4305.9  335.25  4381.5  331.94  4591.7  328.66  4817.2   328.8
  4928.9  330.64  4951.9  328.07  4957.7  329.86  4963.2  327.58  4981.1   329.5
  4986.6  325.37  4992.8  328.21  5002.7  328.75  5009.2  322.03    5017  323.62
  5018.9  318.12  5019.4  317.62  5043.8  318.12  5045.6  323.97  5052.2  326.94
  5066.5  328.19  5184.6  328.66  5272.2  329.82  5364.6  328.77    5457  330.36
  5528.6  327.24  5563.8  328.49  5684.9  339.17  5876.2   337.9  5996.6  338.83
#Mann= 5 ,-1 , 0
  4122.3     .05       0  4817.2      .1       0  5018.9     .05       0
  5043.8      .1       0  5184.6     .05       0
Bank Sta=5018.9,5043.8
XS Rating Curve= 0 ,0
Exp/Cntr=0.3,0.1

Type RM Length L Ch R = 1 ,3043    ,478,478,478
BEGIN DESCRIPTION:
BEE BRANCH 4.0
END DESCRIPTION:
XS GIS Cut Line= 3
       2483422.2     13794654.66      2482451.68     13795149.83
        2481809.     13795718.35
#Sta/Elev= 30
  4283.1  360.09  4325.5  359.57    4407   354.3  4445.8  353.24  4651.5  335.07
  4734.8  330.89  4894.2  326.89  4934.8  329.29  4951.4  328.77  4964.8  327.07
  4973.7  323.51  4974.7     317  4975.2   316.5  4999.7     317  5001.5   324.3
  5023.7  326.17    5046  326.48  5054.6  328.17  5144.4  329.17  5173.7  328.14
  5388.1  329.03    5537  326.95  5588.4  329.72  5668.1  335.71  5723.3  336.63
    5812  335.98  5982.8   336.8  6018.8  335.97  6099.9   337.4  6230.7  338.45
#Mann= 10 ,-1 , 0
  4283.1    .035       0  4325.5     .05       0  4894.2      .1       0
  4974.7     .05       0  4999.7      .1       0  5588.4     .07       0
  5668.1      .1       0  5723.3     .07       0    5812      .1       0
  6099.9     .07       0
Bank Sta=4974.7,4999.7
XS Rating Curve= 0 ,0
Exp/Cntr=0.3,0.1

Type RM Length L Ch R = 1 ,2565    ,1074,1074,1074
BEGIN DESCRIPTION:
BEE BRANCH 3.0
END DESCRIPTION:
XS GIS Cut Line= 3
      2483352.84     13794402.14      2482204.09     13794872.53
      2481922.14     13794945.24
#Sta/Elev= 30
  3995.2   363.5  4036.1  364.36  4047.3  365.49  4079.3  365.47    4155  359.68
  4202.1  357.37  4332.9  346.58  4371.1  342.55  4479.1  334.69  4576.4  329.95
  4716.9  326.46  4855.2  327.45  4922.2  325.51  4954.6  326.95  4968.4  325.26
  4976.2   325.4  4985.3   316.6  4985.8   316.1  5010.3   316.6  5021.8  324.16
  5030.2  326.46  5045.8  327.31  5099.2  325.59  5105.9  326.26  5187.7   324.6
  5269.1  325.76  5304.6  329.99  5309.8  329.75  5345.3  334.57  5527.7  336.78
#Mann= 5 ,-1 , 0
  3995.2     .05       0  4855.2      .1       0  4985.3     .05       0
  5010.3      .1       0  5187.7     .07       0
Bank Sta=4985.3,5010.3
XS Rating Curve= 0 ,0
Exp/Cntr=0.3,0.1

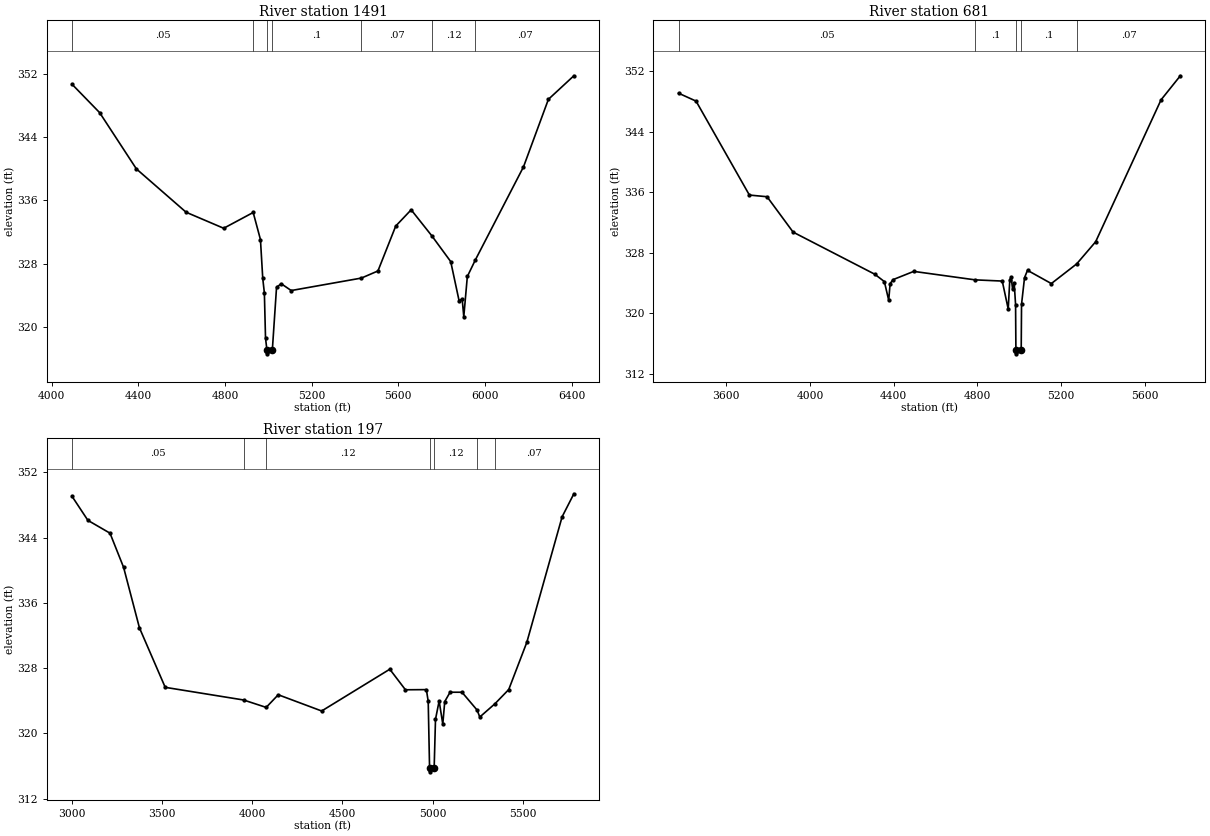
Type RM Length L Ch R = 1 ,1491    ,810,810,810
BEGIN DESCRIPTION:
BEE BRANCH 2.0
END DESCRIPTION:
XS GIS Cut Line= 3
      2483374.99       13793875.      2482330.28     13794242.22
      2481216.81      13794710.5
#Sta/Elev= 30
  4094.9  350.72  4222.1  347.13  4391.7     340  4621.1  334.51  4794.5  332.48
  4930.6  334.48  4964.1  331.05  4974.7  326.13  4982.2  324.29  4987.5  318.56
  4993.9  317.07  4994.4  316.57    5019  317.07  5038.3  324.98  5059.5  325.46
  5106.1  324.59  5429.9  326.17  5506.2  327.07  5588.3  332.76  5659.5  334.82
  5755.2  331.51    5842  328.26  5880.6   323.3  5894.9  323.52  5902.3  321.28
  5918.7  326.37  5955.9  328.48  6177.8  340.26  6292.8  348.82  6410.2   351.8
#Mann= 7 ,-1 , 0
  4094.9     .05       0  4930.6      .1       0  4993.9     .05       0
    5019      .1       0  5429.9     .07       0  5755.2     .12       0
  5955.9     .07       0
Bank Sta=4993.9,5019
XS Rating Curve= 0 ,0
Exp/Cntr=0.3,0.1

Type RM Length L Ch R = 1 ,681     ,484,484,484
BEGIN DESCRIPTION:
X18200
END DESCRIPTION:
XS GIS Cut Line= 3
      2483342.48     13793638.04      2481897.99     13794040.83
      2481219.38     13794629.42
#Sta/Elev= 30
  3371.7  349.09  3455.4  348.04  3710.3  335.62  3794.7   335.4  3919.3  330.72
  4309.2  325.16  4355.3  324.18  4376.1  321.71  4382.7  323.91  4396.8  324.44
  4495.7  325.53    4789  324.41  4918.7  324.25  4947.2  320.55  4954.7  324.44
  4961.4  324.74  4968.1  323.16  4975.7  324.01  4982.3  321.14  4983.9  315.13
  4984.4  314.63  5009.2  315.13  5010.8  321.18  5025.1   324.7  5039.3  325.67
  5153.2  323.92  5274.3  326.52    5365  329.45  5677.5  348.21  5769.6  351.39
#Mann= 5 ,-1 , 0
  3371.7     .05       0    4789      .1       0  4983.9     .05       0
  5009.2      .1       0  5274.3     .07       0
Bank Sta=4983.9,5009.2
XS Rating Curve= 0 ,0
Exp/Cntr=0.3,0.1

Type RM Length L Ch R = 1 ,197     ,0,0,0
BEGIN DESCRIPTION:
BEE BRANCH 1.0
END DESCRIPTION:
XS GIS Cut Line= 4
      2483391.05     13793443.61       2481571.6     13793811.66
      2481272.99     13793853.33        2481225.     13794474.97
#Sta/Elev= 30
  3001.7  349.06  3089.5  346.12  3211.9  344.55  3287.3  340.36  3375.2  332.94
    3518  325.65    3952   324.1  4077.6  323.19  4144.5  324.74  4385.2  322.75
  4762.7  327.87  4849.5  325.35  4965.6  325.37  4975.7  323.93  4983.2  315.79
  4983.7  315.29  5008.7  315.79  5016.1  321.73  5036.3  323.98  5056.5  321.14
  5067.4  323.91  5096.9  325.05  5162.9  325.05  5246.8  322.86  5261.5  322.01
  5345.3  323.63    5422  325.38  5522.3  331.17  5717.9  346.56    5783  349.38
#Mann= 7 ,-1 , 0
  3001.7     .05       0    3952     .07       0  4077.6     .12       0
  4983.2     .05       0  5008.7     .12       0  5246.8     .12       0
  5345.3     .07       0
Bank Sta=4983.2,5008.7
XS Rating Curve= 0 ,0
Exp/Cntr=0.3,0.1

Chan Stop Cuts=-1
Use User Specified Reach Order=0
Composite Channel Slope=5