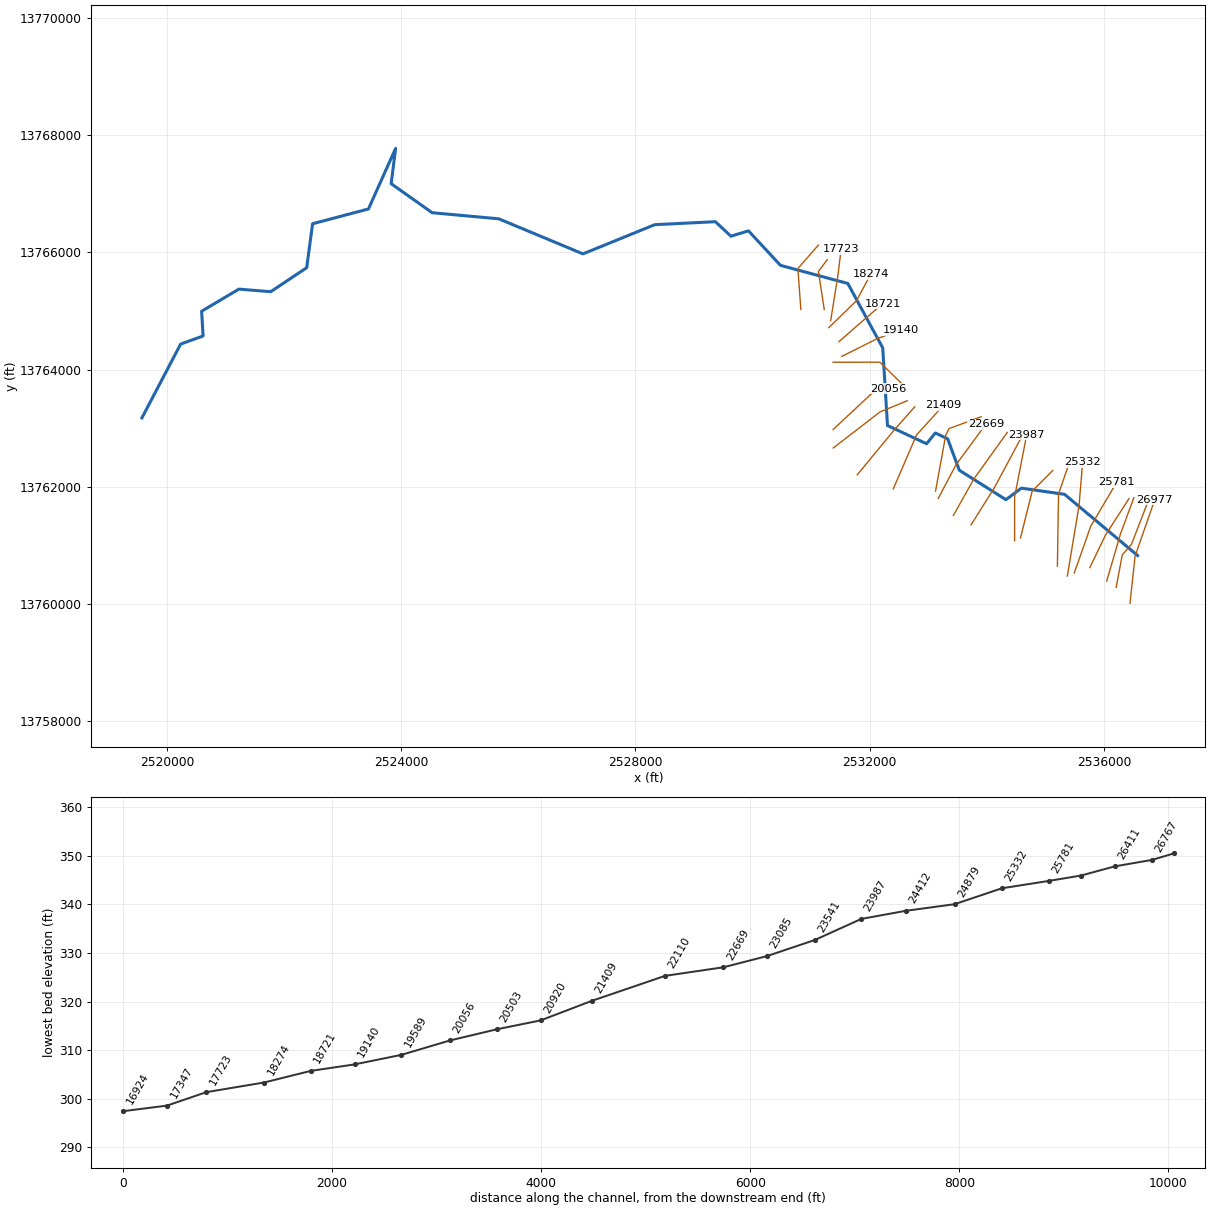
--- BEN BRANCH.prj (project) ---

Proj Title=BEN BRANCH Base Level Engineering
Current Plan=p01
Default Exp/Contr=0.3,0.1
English Units
Geom File=g01
Flow File=f01
Plan File=p01
Y Axis Title=Elevation
X Axis Title(PF)=Main Channel Distance
X Axis Title(XS)=Station
BEGIN DESCRIPTION:
BEN BRANCH
END DESCRIPTION:
DSS Export Rating Curves= 0
DSS Export Rating Curve Sorted= 0
DSS Export Volume Flow Curves= 0
DXF OffsetX= 0
DXF OffsetY= 0
DXF ScaleX= 1
DXF ScaleY= 10

--- BEN BRANCH.p01 (plan) ---

Plan Title=Multiple Run
Program Version=4.10
Short Identifier=Multiple
Geom File=g01
Flow File=f01
Subcritical Flow
K Sum by GR= 0
Std Step Tol= 0.01
Critical Tol= 0.01
Num of Std Step Trials= 20
Max Error Tol= 0.3
Flow Tol Ratio= 0.001
Split Flow NTrial= 30
Split Flow Tol= 0.02
Split Flow Ratio= 0.02
Log Output Level= 0
Friction Slope Method= 1
Unsteady Friction Slope Method= 2
Unsteady Bridges Friction Slope Method= 1
Parabolic Critical Depth
Global Vel Dist= 1 , 1 , 1
Global Log Level= 0
CheckData=True
Encroach Param=-1 ,0,0, 0
BEGIN DESCRIPTION:
Multiple Run
END DESCRIPTION:
Computation Interval=1HOUR
Output Interval=1HOUR
Run HTab= 0
Run UNet= 0
Run PostProcess= 0
Run WQNet= 0
UNET Theta= 1
UNET Theta Warmup= 1
UNET ZTol= 0.02
UNET ZSATol= 0.05
UNET MxIter= 20
UNET MaxInSteps= 0
UNET DtIC= 0
UNET DtMin= 0
UNET MaxCRTS= 20
UNET WFStab= 2
UNET SFStab= 1
UNET WFX= 1
UNET SFX= 1
UNET DSS MLevel= 4
UNET DZMax Abort= 100
UNET Convert EG Bridges= 0
UNET Use Existing IB Tables=-1
UNET Froude Reduction=False
UNET Froude Limit= 1
UNET Froude Power= 10
UNET Time Slicing=0,0, 5
UNET Junction Losses=0
Instantaneous Interval=1HOUR
Write IC File= 0
Write IC File at Sim End=0
Echo Input=False
Echo Parameters=False
Echo Output=False
Write Detailed= 0
WQ AD Non Conservative
WQ ULTIMATE=-1
WQ Max Comp Step=1HOUR
WQ Output Interval=15MIN
WQ Output Selected Increments= 0
WQ Output face flow=0
WQ Output face velocity=0
WQ Output face area=0
WQ Output face dispersion=0
WQ Output cell volume=0
WQ Output cell surface area=0
WQ Output cell continuity=0
WQ Output cumulative cell continuity=0
WQ Output face conc=0
WQ Output face dconc_dx=0
WQ Output face courant=0
WQ Output face peclet=0
WQ Output face adv mass=0
WQ Output face disp mass=0
WQ Output cell mass=0
WQ Output cell source sink temp=0
WQ Output cell source sink nsm=0
WQ Output MaxMinRange=-1
WQ Daily Max Min Mean=-1
WQ Daily Range=0
WQ Daily Time=0
WQ Create Restart=0
WQ Fixed Restart=0
WQ System Summary=0
WQ Use Fixed Temperature=0
Sorting and Armoring Iterations= 10
XS Update Threshold= 0.02
Hydraulics Update Threshold= 0.02
Energy Slope Method= 1
Volume Change Method= 0
XS Weighting Method= 0
Number of US Weighted Cross Sections= 1
Number of DS Weighted Cross Sections= 1
Upstream XS Weight=0.25
Main XS Weight=0.5
Downstream XS Weight=0.25
Number of DS XS's Weighted with US Boundary= 1
Upstream Boundary Weight= 1
Weight of XSs Associated with US Boundary= 0
Number of US XS's Weighted with DS Boundary= 1
Downstream Boundary Weight= 0.5
Weight of XSs Associated with DS Boundary= 0.5
Sediment Output Level= 4
Mass or Volume Output= 0
Output Increment Type= 1
Profile and TS Output Increment= 10
XS Output Flag= 0
XS Output Increment= 10
Disregard all LS=0
Disregard all Conn=0
Disregard all Breaches=0
Disregard all Pumps=0

--- BEN BRANCH.f01 (steady flow) ---

Flow Title=Multiple
Number of Profiles=7
Profile Names=10-year,25-year,50-year,1pct_min,100-year,1pct_plu,500-year
River Rch & RM= BEN BRANCH,Reach-1,26977
    1081    1807    2490    1662    3317    6618    5823
River Rch & RM= BEN BRANCH,Reach-1,23987
    1435    2422    3357    2250    4489    8958    7953
River Rch & RM= BEN BRANCH,Reach-1,16924
    1713    2895    4013    2687    5362   10699    9482
Boundary for River Rch & Prof#=BEN BRANCH,Reach-1,1
Up Type=0
Dn Type=3
Dn Slope=0.005
Boundary for River Rch & Prof#=BEN BRANCH,Reach-1,2
Up Type=0
Dn Type=3
Dn Slope=0.005
Boundary for River Rch & Prof#=BEN BRANCH,Reach-1,3
Up Type=0
Dn Type=3
Dn Slope=0.005
Boundary for River Rch & Prof#=BEN BRANCH,Reach-1,4
Up Type=0
Dn Type=3
Dn Slope=0.005
Boundary for River Rch & Prof#=BEN BRANCH,Reach-1,5
Up Type=0
Dn Type=3
Dn Slope=0.005
Boundary for River Rch & Prof#=BEN BRANCH,Reach-1,6
Up Type=0
Dn Type=3
Dn Slope=0.005
Boundary for River Rch & Prof#=BEN BRANCH,Reach-1,7
Up Type=0
Dn Type=3
Dn Slope=0.005

--- BEN BRANCH.g01 (geometry) ---

Geom Title=Existing Conditions
Program Version=4.10

River Reach=BEN BRANCH      ,Reach-1
Reach XY= 30
        2536575.       13760825.       2535327.7     13761869.64
       2534590.2     13761975.11       2534326.5     13761778.46
      2533530.58     13762280.58       2533331.5     13762817.27
      2533121.42     13762917.51      2532971.78     13762732.83
      2532304.52     13763044.63       2532223.2     13764368.89
      2531627.31     13765469.18       2530476.5     13765778.61
      2529931.52     13766367.33      2529631.12     13766276.76
      2529365.32     13766523.76      2528330.26     13766472.91
      2527104.95     13765974.41      2525669.06     13766572.74
      2524530.44     13766677.17       2523830.4     13767172.57
      2523906.44     13767775.36      2523442.13     13766741.04
       2522488.5     13766488.69      2522388.27     13765738.62
      2521773.54     13765328.54      2521230.45     13765372.84
      2520594.19     13764995.05      2520619.17     13764572.69
      2520235.75     13764434.71        2519575.       13763175.

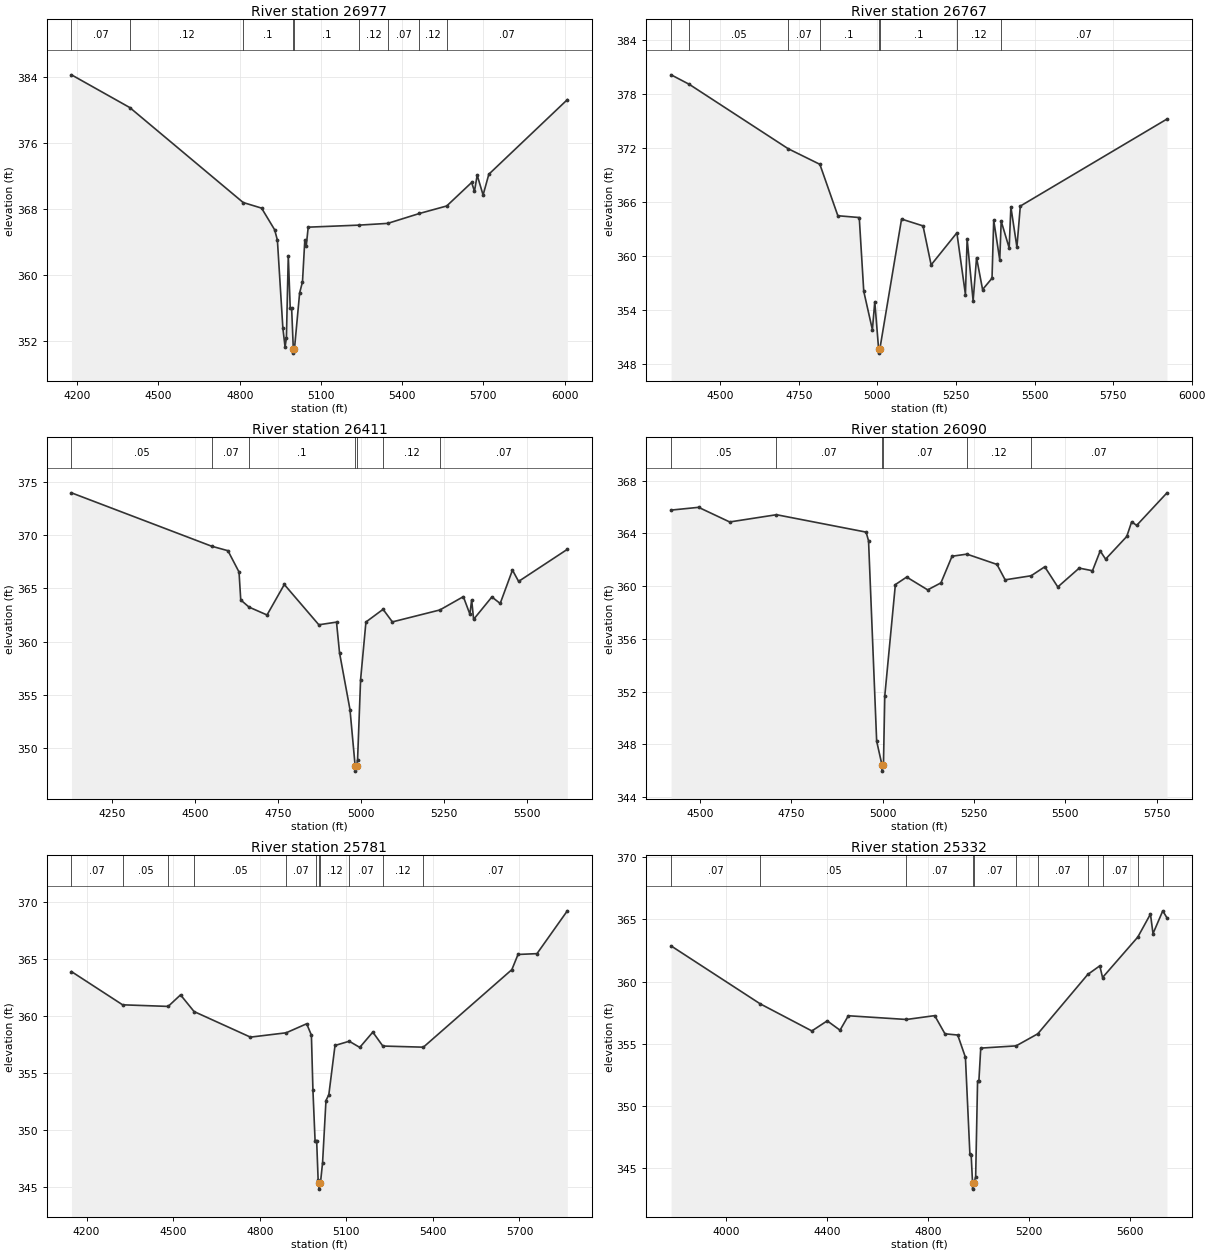
Type RM Length L Ch R = 1 ,26977   ,210,210,210
BEGIN DESCRIPTION:
BEN BRANCH 44.0
END DESCRIPTION:
XS GIS Cut Line= 3
      2536444.68     13760008.74      2536531.97     13760814.35
      2536868.02     13761778.86
#Sta/Elev= 30
  4178.5  384.27  4393.9   380.3  4812.8  368.78  4880.8   368.1  4929.1  365.47
  4939.2  364.21  4959.3  353.59  4967.5  351.24  4972.5  352.36  4979.4  362.33
  4986.6  355.95  4991.8  355.95    4998  351.01  4998.3  350.51  5002.2  351.01
  5021.3   357.8  5031.9  359.17  5040.4  364.18  5045.7  363.49    5053  365.79
  5242.2  366.04  5346.8  366.25  5463.8  367.45  5564.6  368.36  5656.7  371.21
  5667.2  370.15  5677.2   372.1    5699  369.69  5720.2  372.21  6010.2  381.26
#Mann= 9 ,-1 , 0
  4178.5     .07       0  4393.9     .12       0  4812.8      .1       0
    4998     .05       0  5002.2      .1       0  5242.2     .12       0
  5346.8     .07       0  5463.8     .12       0  5564.6     .07       0
Bank Sta=4998,5002.2
XS Rating Curve= 0 ,0
Exp/Cntr=0.3,0.1

Type RM Length L Ch R = 1 ,26767   ,356,356,356
BEGIN DESCRIPTION:
X18202
END DESCRIPTION:
XS GIS Cut Line= 4
      2536209.01     13760283.69      2536313.75     13760837.92
      2536470.86     13761016.85      2536749.85     13761740.47
#Sta/Elev= 30
  4343.8  380.08  4401.8  379.02  4716.4  371.87  4817.1  370.14  4874.3  364.43
  4942.4  364.23  4956.7  356.04  4984.2  351.77  4991.8  354.88  5003.9  349.67
  5004.2  349.17  5008.1  349.67    5077  364.06  5145.3   363.3  5171.1  358.97
    5253  362.53  5280.2  355.68  5285.6  361.84  5304.7  354.98  5315.6  359.77
  5334.8  356.23  5364.8  357.49  5370.2  363.93  5389.4  359.53    5394  363.82
  5419.4  360.85  5424.8  365.41    5444  360.94  5454.8   365.5  5921.5  375.17
#Mann= 8 ,-1 , 0
  4343.8     .07       0  4401.8     .05       0  4716.4     .07       0
  4817.1      .1       0  5003.9     .05       0  5008.1      .1       0
    5253     .12       0    5394     .07       0
Bank Sta=5003.9,5008.1
XS Rating Curve= 0 ,0
Exp/Cntr=0.3,0.1

Type RM Length L Ch R = 1 ,26411   ,321,321,321
BEGIN DESCRIPTION:
X18201
END DESCRIPTION:
XS GIS Cut Line= 3
      2536047.53     13760388.39      2536278.83      13761182.7
      2536509.88     13761810.43
#Sta/Elev= 30
  4126.7  373.95  4549.8  368.94  4598.8  368.52  4632.3  366.52  4637.5   363.9
  4662.4  363.23  4716.8  362.49  4768.9  365.35  4873.1  361.57  4926.4  361.82
  4935.6  358.93  4967.1  353.61  4982.6  348.34  4982.9  347.84  4986.9  348.34
    4990  348.92  4999.1  356.43  5015.2  361.83  5066.9  363.02    5095  361.84
  5238.2  362.96  5309.1  364.21  5328.9  362.56  5334.2  363.91  5340.1  362.08
  5395.2  364.18  5420.3  363.57  5457.3   366.7  5475.9  365.64  5622.9  368.65
#Mann= 7 ,-1 , 0
  4126.7     .05       0  4549.8     .07       0  4662.4      .1       0
  4982.6     .05       0  4986.9      .1       0  5066.9     .12       0
  5238.2     .07       0
Bank Sta=4982.6,4986.9
XS Rating Curve= 0 ,0
Exp/Cntr=0.3,0.1

Type RM Length L Ch R = 1 ,26090   ,309,309,309
BEGIN DESCRIPTION:
BEN BRANCH 43.0
END DESCRIPTION:
XS GIS Cut Line= 3
      2535759.47     13760617.92       2536025.7     13761172.22
      2536427.21      13761796.3
#Sta/Elev= 30
  4421.2  365.76  4496.4  365.97  4581.5  364.86  4709.5  365.41  4954.8  364.09
  4961.5  363.43  4983.7  348.23    4998  346.46  4998.3  345.96  5002.3  346.46
  5005.9  351.66  5034.9  360.11  5065.8  360.68  5123.3  359.71  5159.6  360.24
    5190  362.26  5230.6  362.42  5312.9  361.64  5335.3  360.47  5406.5  360.78
  5443.7  361.46  5479.4  359.93    5538  361.36  5574.3  361.16  5595.4  362.66
  5610.2  362.04  5668.1  363.76  5681.5  364.87  5695.2   364.6  5778.2  367.07
#Mann= 6 ,-1 , 0
  4421.2     .05       0  4709.5     .07       0    4998     .05       0
  5002.3     .07       0  5230.6     .12       0  5406.5     .07       0
Bank Sta=4998,5002.3
XS Rating Curve= 0 ,0
Exp/Cntr=0.3,0.1

Type RM Length L Ch R = 1 ,25781   ,449,449,449
BEGIN DESCRIPTION:
BEN BRANCH 42.0
END DESCRIPTION:
XS GIS Cut Line= 3
      2535493.25      13760526.3        2535775.       13761325.
      2536217.73     13762075.62
#Sta/Elev= 30
  4147.6   363.9  4324.8  360.99  4482.7  360.85  4525.6  361.86  4572.5   360.4
  4767.8  358.16  4891.7  358.54  4962.7  359.33  4979.1  358.33  4984.4  353.51
  4991.9  349.03  4994.2  349.03  4997.4  349.03  5002.4  345.66    5006  345.35
  5006.3  344.85  5010.3  345.35  5017.8  347.17  5029.6  352.61  5039.5  353.12
  5060.9  357.43  5110.2   357.8  5146.7  357.26  5191.9   358.6  5226.6  357.38
  5367.1  357.28  5673.7  364.07  5695.1   365.4  5760.8  365.47    5866  369.22
#Mann= 11 ,-1 , 0
  4147.6     .07       0  4324.8     .05       0  4482.7     .07       0
  4572.5     .05       0  4891.7     .07       0  4994.2     .12       0
    5006     .05       0  5010.3     .12       0  5110.2     .07       0
  5226.6     .12       0  5367.1     .07       0
Bank Sta=5006,5010.3
XS Rating Curve= 0 ,0
Exp/Cntr=0.3,0.1

Type RM Length L Ch R = 1 ,25332   ,453,453,453
BEGIN DESCRIPTION:
BEN BRANCH 41.0
END DESCRIPTION:
XS GIS Cut Line= 3
        2535375.       13760475.        2535575.       13761675.
      2535637.27     13762420.25
#Sta/Elev= 30
  3783.1  362.87  4135.8  358.22  4340.7  356.04  4401.5  356.85  4452.2   356.1
  4485.1  357.26  4715.5  356.96  4827.3  357.27  4867.9  355.81  4918.5  355.71
    4949  353.92  4966.7  346.15  4971.8  346.06  4977.2  343.83  4977.5  343.33
  4981.6  343.83  4989.5  344.28  4997.1  351.98  5002.2  351.98  5009.7  354.66
  5149.8  354.84  5235.7  355.81  5433.7  360.58  5481.3  361.27  5492.2  360.33
  5631.8  363.58    5682  365.43  5692.1  363.86  5730.8  365.69  5747.5  365.12
#Mann= 11 ,-1 , 0
  3783.1     .07       0  4135.8     .05       0  4715.5     .07       0
  4977.2     .05       0  4981.6     .07       0  5149.8     .05       0
  5235.7     .07       0  5433.7     .05       0  5492.2     .07       0
  5631.8     .05       0  5730.8     .12       0
Bank Sta=4977.2,4981.6
XS Rating Curve= 0 ,0
Exp/Cntr=0.3,0.1

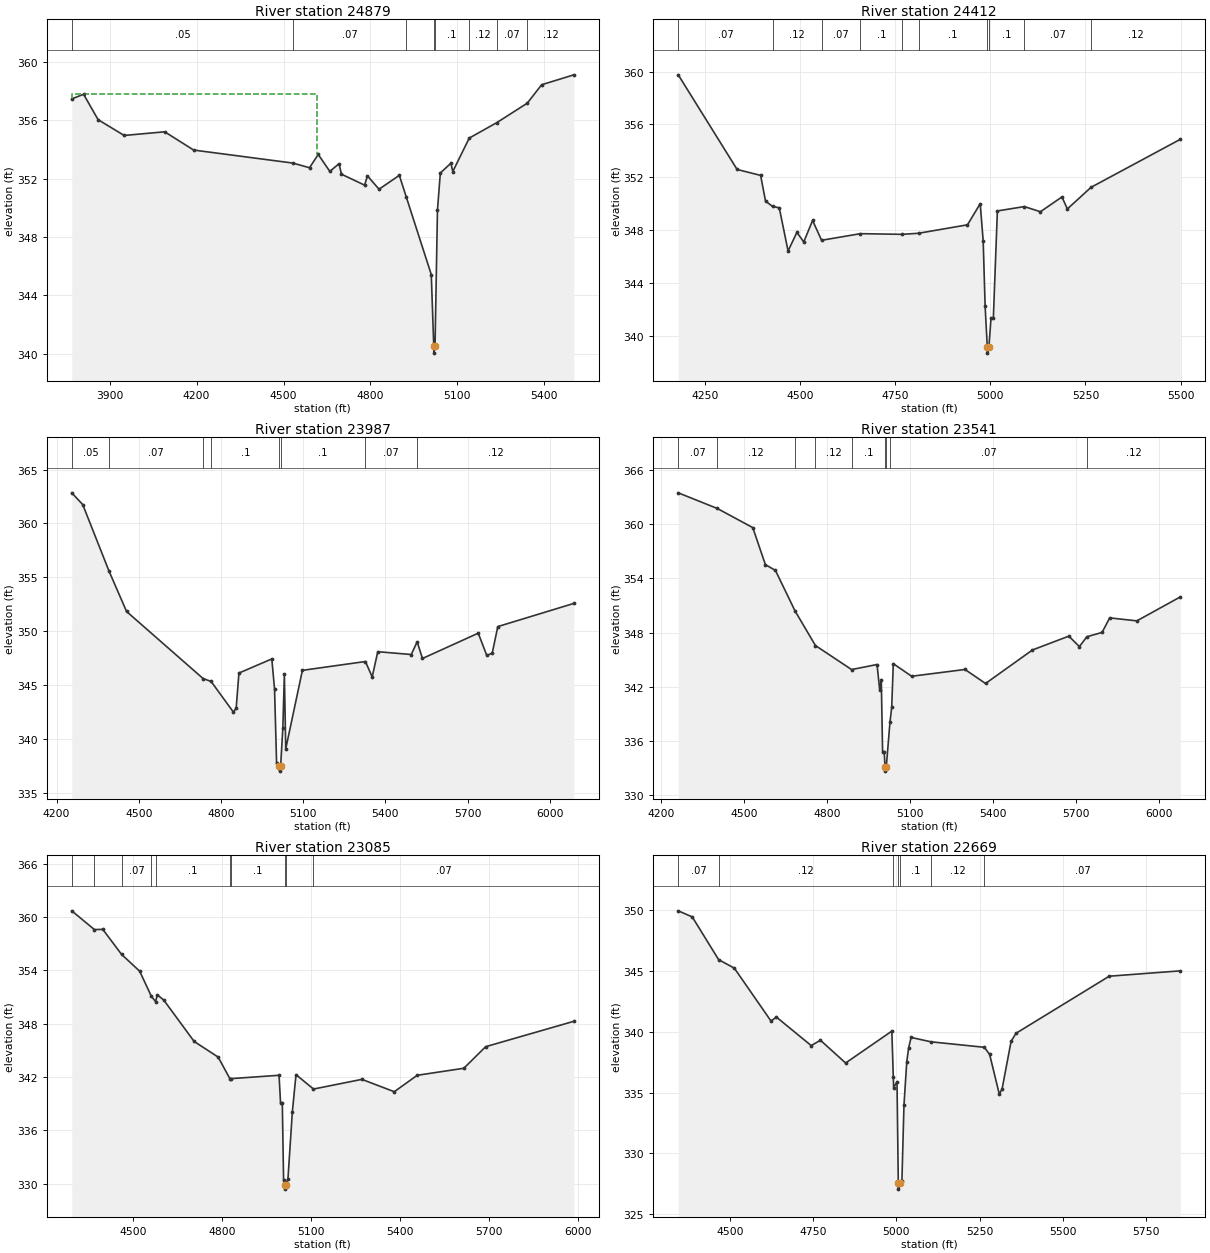
Type RM Length L Ch R = 1 ,24879   ,467,467,467
BEGIN DESCRIPTION:
BEN BRANCH 40.0
END DESCRIPTION:
XS GIS Cut Line= 3
      2535205.21     13760644.16        2535225.       13761875.
      2535388.41     13762350.29
#Sta/Elev= 30
  3768.9  357.45  3809.7  357.77  3859.8  356.03  3949.8  354.95  4089.8   355.2
  4189.8  353.95  4532.3  353.06  4589.8  352.74  4619.9  353.65  4659.9  352.49
  4691.9  353.02  4699.9   352.3  4779.9  351.55  4789.9  352.18  4829.9  351.27
  4899.9  352.22  4924.2  350.72  5010.2  345.43  5018.8  340.55  5019.1  340.05
  5023.2  340.55  5031.6  349.85  5041.5  352.38    5078  353.05  5084.5  352.48
  5141.3  354.77  5236.7  355.83  5341.8  357.16  5391.2  358.42  5502.5   359.1
#Mann= 8 ,-1 , 0
  3768.9     .05       0  4532.3     .07       0  4924.2      .1       0
  5018.8     .05       0  5023.2      .1       0  5141.3     .12       0
  5236.7     .07       0  5341.8     .12       0
#XS Ineff= 2 , 0
       0    4615  357.79    5385       0  357.79
Permanent Ineff=
       F       F
Bank Sta=5018.8,5023.2
XS Rating Curve= 0 ,0
Exp/Cntr=0.3,0.1

Type RM Length L Ch R = 1 ,24412   ,425,425,425
BEGIN DESCRIPTION:
BEN BRANCH 39.0
END DESCRIPTION:
XS GIS Cut Line= 3
      2534574.99     13761124.96        2534775.       13761925.
      2535124.97     13762274.97
#Sta/Elev= 30
  4179.6  359.75  4334.3  352.59  4396.1  352.14    4409   350.2  4427.4  349.79
  4445.1  349.69  4468.3  346.42  4491.5  347.83  4509.5   347.1  4532.7  348.73
  4556.4  347.23  4658.5  347.73  4768.1  347.68  4811.2  347.76  4939.8   348.4
  4973.3     350  4981.1  347.18  4986.2  342.24  4991.8  339.19  4992.1  338.69
  4996.2  339.19  5001.7  341.34  5007.8  341.34  5018.4  349.45  5089.3  349.78
  5131.5  349.39  5188.1  350.51  5202.3   349.6  5264.7  351.24  5499.2  354.87
#Mann= 10 ,-1 , 0
  4179.6     .07       0  4427.4     .12       0  4556.4     .07       0
  4658.5      .1       0  4768.1     .07       0  4811.2      .1       0
  4991.8     .05       0  4996.2      .1       0  5089.3     .07       0
  5264.7     .12       0
Bank Sta=4991.8,4996.2
XS Rating Curve= 0 ,0
Exp/Cntr=0.3,0.1

Type RM Length L Ch R = 1 ,23987   ,446,446,446
BEGIN DESCRIPTION:
BEN BRANCH 38.0
END DESCRIPTION:
XS GIS Cut Line= 3
        2534475.     13761075.05        2534475.       13761825.
      2534681.49     13762887.37
#Sta/Elev= 30
  4255.5  362.84  4295.5  361.75  4390.9  355.61  4455.5  351.83  4734.7  345.61
    4764  345.34  4845.5  342.49  4855.5  342.87  4865.5  346.12  4985.5  347.43
  4995.5  344.63    5003  337.74  5013.4  337.52  5013.7  337.02  5017.8  337.52
  5025.8  341.05  5031.3  346.02  5036.4  339.09  5097.1  346.37  5327.1  347.19
  5351.8  345.76  5372.2   348.1  5494.4  347.84    5516  349.02  5535.2  347.47
  5738.9  349.82    5770  347.75  5789.9  347.97  5810.2  350.43  6087.7  352.58
#Mann= 8 ,-1 , 0
  4255.5     .05       0  4390.9     .07       0  4734.7     .12       0
    4764      .1       0  5013.4     .05       0  5017.8      .1       0
  5327.1     .07       0    5516     .12       0
Bank Sta=5013.4,5017.8
XS Rating Curve= 0 ,0
Exp/Cntr=0.3,0.1

Type RM Length L Ch R = 1 ,23541   ,456,456,456
BEGIN DESCRIPTION:
BEN BRANCH 37.0
END DESCRIPTION:
XS GIS Cut Line= 3
      2533730.07     13761346.79        2534125.       13761975.
      2534632.87     13762921.18
#Sta/Elev= 30
  4261.9  363.47  4403.1  361.74  4531.5  359.62    4577  355.53  4613.5  354.88
  4684.5  350.39  4758.1  346.57  4888.9  343.91    4981  344.47  4990.4  341.68
  4996.3   342.8    5001  334.82  5006.8  334.82  5009.8  333.17  5010.1  332.67
  5014.4  333.17  5027.8  338.12    5034  339.72  5039.7  344.56  5106.1  343.17
    5299  343.92  5373.4  342.37  5543.1  346.08  5674.6  347.61  5712.8  346.45
  5739.7  347.54  5794.8  348.02  5822.4  349.63  5920.6   349.3  6077.8  351.95
#Mann= 9 ,-1 , 0
  4261.9     .07       0  4403.1     .12       0  4684.5      .1       0
  4758.1     .12       0  4888.9      .1       0  5009.8     .05       0
  5014.4      .1       0  5027.8     .07       0  5739.7     .12       0
Bank Sta=5009.8,5014.4
XS Rating Curve= 0 ,0
Exp/Cntr=0.3,0.1

Type RM Length L Ch R = 1 ,23085   ,416,416,416
BEGIN DESCRIPTION:
BEN BRANCH 36.0
END DESCRIPTION:
XS GIS Cut Line= 3
      2533428.95     13761508.31        2533775.       13762125.
       2534349.8     13762926.68
#Sta/Elev= 30
  4292.6  360.71  4368.9   358.6  4397.3  358.62  4460.7   355.8  4521.7  353.91
  4560.6  351.12  4575.4  350.48    4581  351.25  4602.7  350.67  4705.4     346
  4786.4  344.24  4826.4  341.78  4828.2  341.81  4991.8  342.19  4996.9  339.05
  5002.8  339.05  5007.1  330.39    5011  329.87  5011.3  329.37  5015.6  329.87
  5021.9  330.56  5036.6  338.07    5049  342.26    5108  340.64  5271.2  341.73
  5380.5  340.34  5457.9  342.19  5615.1  342.98  5688.7  345.41  5986.2  348.27
#Mann= 10 ,-1 , 0
  4292.6     .07       0  4368.9     .12       0  4460.7     .07       0
  4560.6     .12       0  4575.4      .1       0  4826.4     .12       0
  4828.2      .1       0    5011     .05       0  5015.6      .1       0
    5108     .07       0
Bank Sta=5011,5015.6
XS Rating Curve= 0 ,0
Exp/Cntr=0.3,0.1

Type RM Length L Ch R = 1 ,22669   ,559,559,559
BEGIN DESCRIPTION:
BEN BRANCH 35.0
END DESCRIPTION:
XS GIS Cut Line= 3
      2533171.44      13761800.7        2533475.       13762375.
      2533983.19     13763066.32
#Sta/Elev= 30
  4344.9  349.93    4387  349.43  4466.2  345.92  4513.4  345.22  4623.4  340.88
  4639.8   341.2  4744.2  338.86  4771.9   339.3  4847.5  337.43  4986.3  340.05
  4990.7  336.27  4991.7  335.41  5001.8  335.88  5005.7  327.57    5006  327.07
  5010.4  327.57  5016.5   327.7  5022.7  333.96  5031.1  337.53  5036.7  338.66
  5044.1  339.53    5104  339.17  5264.1  338.72    5280  338.13  5308.9  334.88
  5317.2  335.28  5344.4  339.21  5359.1  339.87  5639.1  344.56  5852.5     345
#Mann= 7 ,-1 , 0
  4344.9     .07       0  4466.2     .12       0  4990.7      .1       0
  5005.7     .05       0  5010.4      .1       0    5104     .12       0
  5264.1     .07       0
Bank Sta=5005.7,5010.4
XS Rating Curve= 0 ,0
Exp/Cntr=0.3,0.1

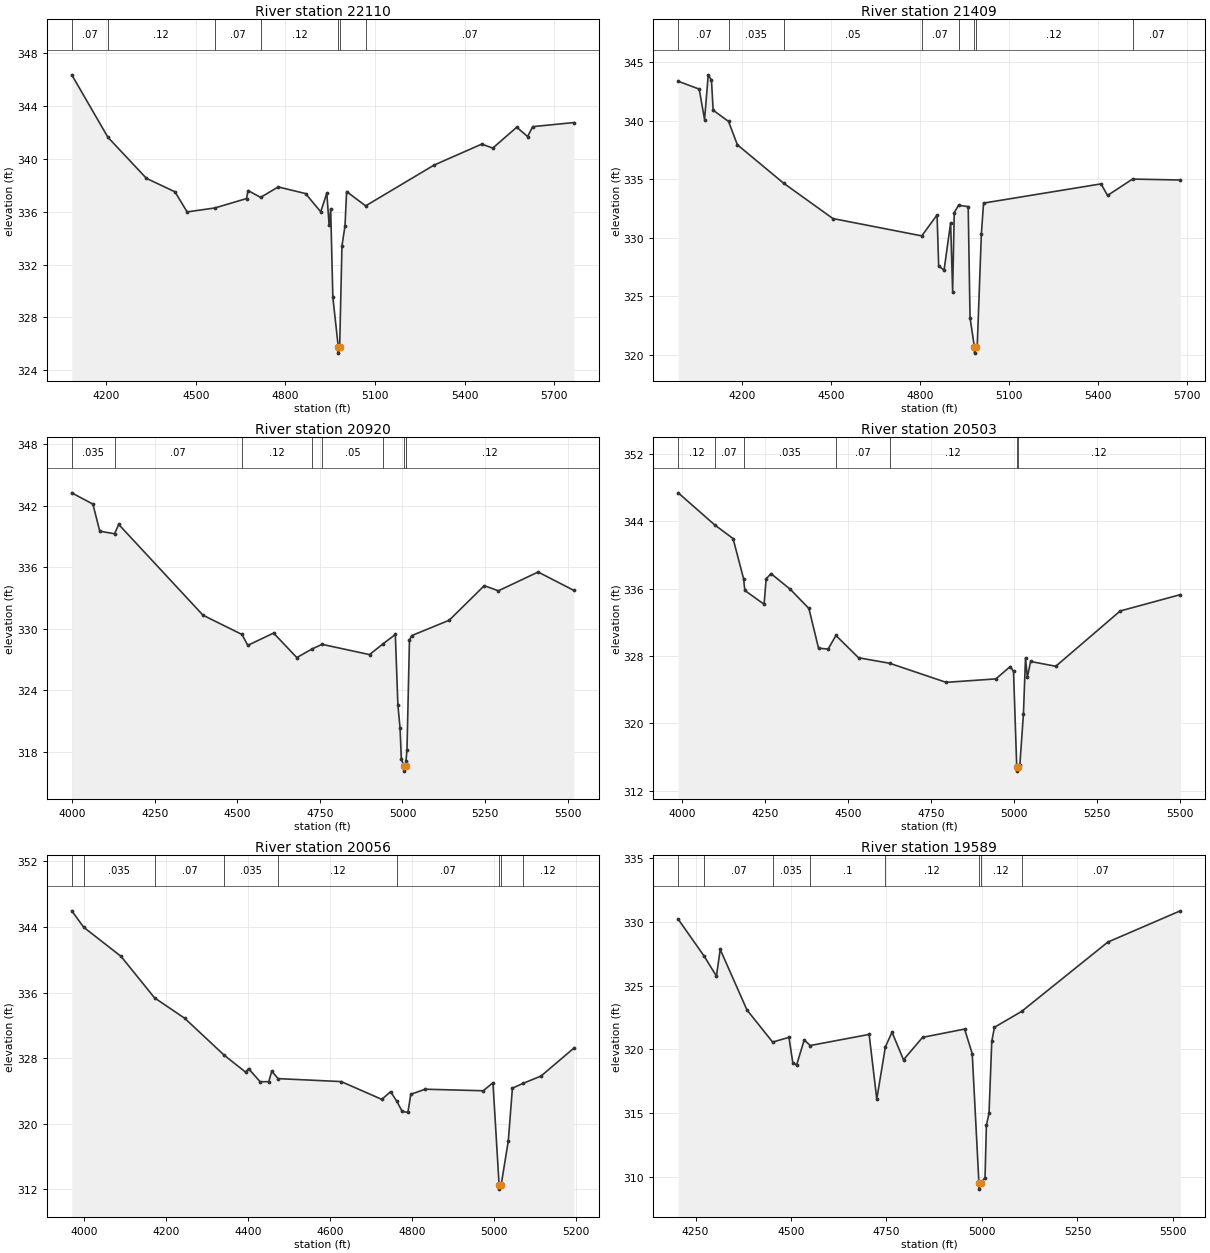
Type RM Length L Ch R = 1 ,22110   ,701,701,701
BEGIN DESCRIPTION:
BEN BRANCH 34.0
END DESCRIPTION:
XS GIS Cut Line= 4
      2533125.01     13761925.04        2533298.     13762874.31
      2533354.18     13762991.25      2533904.33     13763193.84
#Sta/Elev= 30
    4085  346.35  4205.9  341.63    4335  338.52  4430.6   337.5  4471.2  335.98
  4563.9  336.28    4670  336.99  4675.1   337.6  4717.2  337.08  4776.2  337.87
  4867.6  337.37  4918.5  335.99  4938.8   337.4  4946.7  334.96  4951.8  336.22
  4959.1  329.52  4977.1   325.8  4977.4   325.3  4981.9   325.8  4989.6  333.42
  4999.8  334.93  5005.1  337.52  5068.9  336.44  5297.7  339.52  5457.6  341.11
  5494.6  340.81  5574.8  342.39  5611.1  341.68  5628.1  342.43  5765.9  342.74
#Mann= 7 ,-1 , 0
    4085     .07       0  4205.9     .12       0  4563.9     .07       0
  4717.2     .12       0  4977.1     .05       0  4981.9     .12       0
  5068.9     .07       0
Bank Sta=4977.1,4981.9
XS Rating Curve= 0 ,0
Exp/Cntr=0.3,0.1

Type RM Length L Ch R = 1 ,21409   ,489,489,489
BEGIN DESCRIPTION:
BEN BRANCH 33.0
END DESCRIPTION:
XS GIS Cut Line= 3
       2532403.3     13761962.12      2532800.47     13762883.04
      2533263.07     13763393.64
#Sta/Elev= 30
  3984.8  343.36  4055.5  342.69  4073.5  340.09  4085.9  343.91  4096.8  343.45
  4102.5  340.89  4154.4  339.93    4184  337.94  4339.9  334.66    4506  331.64
  4805.5  330.16    4857  331.95  4862.4  327.62  4880.5  327.22  4902.7  331.27
  4909.5   325.4  4914.9  332.15  4929.5  332.77  4961.9  332.66  4968.1  323.17
    4983  320.65  4983.4  320.15  4987.9  320.65  4992.4  320.79  5006.3  330.32
  5013.7  332.96  5409.7   334.6  5431.4  333.61  5515.6  335.01  5676.7  334.93
#Mann= 8 ,-1 , 0
  3984.8     .07       0  4154.4    .035       0  4339.9     .05       0
  4805.5     .07       0  4929.5     .12       0    4983     .05       0
  4987.9     .12       0  5515.6     .07       0
Bank Sta=4983,4987.9
XS Rating Curve= 0 ,0
Exp/Cntr=0.3,0.1

Type RM Length L Ch R = 1 ,20920   ,417,417,417
BEGIN DESCRIPTION:
BEN BRANCH 32.0
END DESCRIPTION:
XS GIS Cut Line= 3
      2531787.98     13762202.24        2532425.       13762975.
      2532769.92     13763363.11
#Sta/Elev= 30
  3998.3  343.26  4062.3  342.16  4083.1  339.52  4127.9  339.27  4140.5  340.18
  4395.8  331.33  4513.9  329.45  4531.4  328.39  4609.6  329.59  4679.9   327.2
  4726.7  328.05  4756.5  328.49  4900.1  327.49  4942.3  328.57  4978.3  329.45
  4986.1  322.57  4992.6  320.34  4996.5   317.3  5004.4  316.63  5004.8  316.13
  5009.3  316.63  5010.5  317.08  5013.6  318.23  5021.1  328.89  5027.8  329.34
  5141.5  330.84  5247.7  334.21  5290.4  333.71  5410.8  335.54    5519  333.75
#Mann= 9 ,-1 , 0
  3998.3    .035       0  4127.9     .07       0  4513.9     .12       0
  4726.7     .07       0  4756.5     .05       0  4942.3     .07       0
  5004.4     .05       0  5009.3     .07       0  5010.5     .12       0
Bank Sta=5004.4,5009.3
XS Rating Curve= 0 ,0
Exp/Cntr=0.3,0.1

Type RM Length L Ch R = 1 ,20503   ,447,447,447
BEGIN DESCRIPTION:
BEN BRANCH 31.0
END DESCRIPTION:
XS GIS Cut Line= 3
      2531377.71     13762660.46        2532175.       13763275.
      2532641.65     13763467.15
#Sta/Elev= 30
  3989.3  347.38    4099  343.57  4154.3  341.95  4186.1  337.16  4189.7  335.78
  4247.7  334.14    4254  337.16  4268.5  337.78  4326.5  335.92  4382.6  333.64
  4411.6  328.92  4440.4  328.81    4464  330.43  4532.1  327.78  4625.4  327.13
  4795.7  324.86  4945.4  325.27  4988.7  326.74  4998.6  326.15  5008.2  314.81
  5008.5  314.31  5013.1  314.81  5017.6  315.06  5028.4  321.11  5034.6  327.78
    5040  325.44    5050  327.34  5125.7  326.77  5319.6  333.34  5500.6  335.28
#Mann= 7 ,-1 , 0
  3989.3     .12       0    4099     .07       0  4186.1    .035       0
    4464     .07       0  4625.4     .12       0  5008.2     .05       0
  5013.1     .12       0
Bank Sta=5008.2,5013.1
XS Rating Curve= 0 ,0
Exp/Cntr=0.3,0.1

Type RM Length L Ch R = 1 ,20056   ,467,467,467
BEGIN DESCRIPTION:
BEN BRANCH 30.0
END DESCRIPTION:
XS GIS Cut Line= 3
        2531375.       13762975.        2532125.       13763675.
      2532324.98       13763675.
#Sta/Elev= 30
  3969.8  345.97  3999.1  343.96  4090.2  340.41  4171.8  335.36  4245.6  332.86
  4342.4  328.34  4394.1   326.3  4401.4  326.72  4429.8  325.12  4450.8  325.13
  4458.1  326.41  4473.7   325.5  4627.6  325.14  4726.8  322.97  4748.3  323.91
  4763.6  322.72  4776.6   321.5  4790.5  321.38  4797.6  323.59  4832.8  324.21
  4974.5  324.02  4998.2     325  5013.2  312.52  5013.6  312.02  5018.2  312.52
  5035.7  317.92  5045.7  324.34  5071.2  324.91  5115.7  325.82  5195.7  329.22
#Mann= 9 ,-1 , 0
  3969.8     .07       0  3999.1    .035       0  4171.8     .07       0
  4342.4    .035       0  4473.7     .12       0  4763.6     .07       0
  5013.2     .05       0  5018.2     .07       0  5071.2     .12       0
Bank Sta=5013.2,5018.2
XS Rating Curve= 0 ,0
Exp/Cntr=0.3,0.1

Type RM Length L Ch R = 1 ,19589   ,449,449,449
BEGIN DESCRIPTION:
BEN BRANCH 29.0
END DESCRIPTION:
XS GIS Cut Line= 3
      2531375.02       13764125.        2532175.       13764125.
      2532542.96     13763764.65
#Sta/Elev= 30
  4204.6   330.2  4272.9  327.29  4304.6  325.74  4314.6  327.83  4384.6  323.09
  4451.8  320.57  4494.6  320.94  4504.6  318.96  4514.6  318.77  4534.6  320.74
  4550.3   320.3  4704.6  321.17  4724.6   316.1  4747.2   320.2  4764.6  321.34
  4794.6  319.18  4844.6  320.94  4954.6  321.59  4974.6  319.66  4992.1  309.54
  4992.5  309.04  4997.1  309.54  5008.1  309.92  5011.7  314.04  5018.6  314.99
  5025.8  320.62  5032.8  321.73  5103.8  322.97  5329.8  328.41  5519.6  330.86
#Mann= 8 ,-1 , 0
  4204.6     .05       0  4272.9     .07       0  4451.8    .035       0
  4550.3      .1       0  4747.2     .12       0  4992.1     .05       0
  4997.1     .12       0  5103.8     .07       0
Bank Sta=4992.1,4997.1
XS Rating Curve= 0 ,0
Exp/Cntr=0.3,0.1

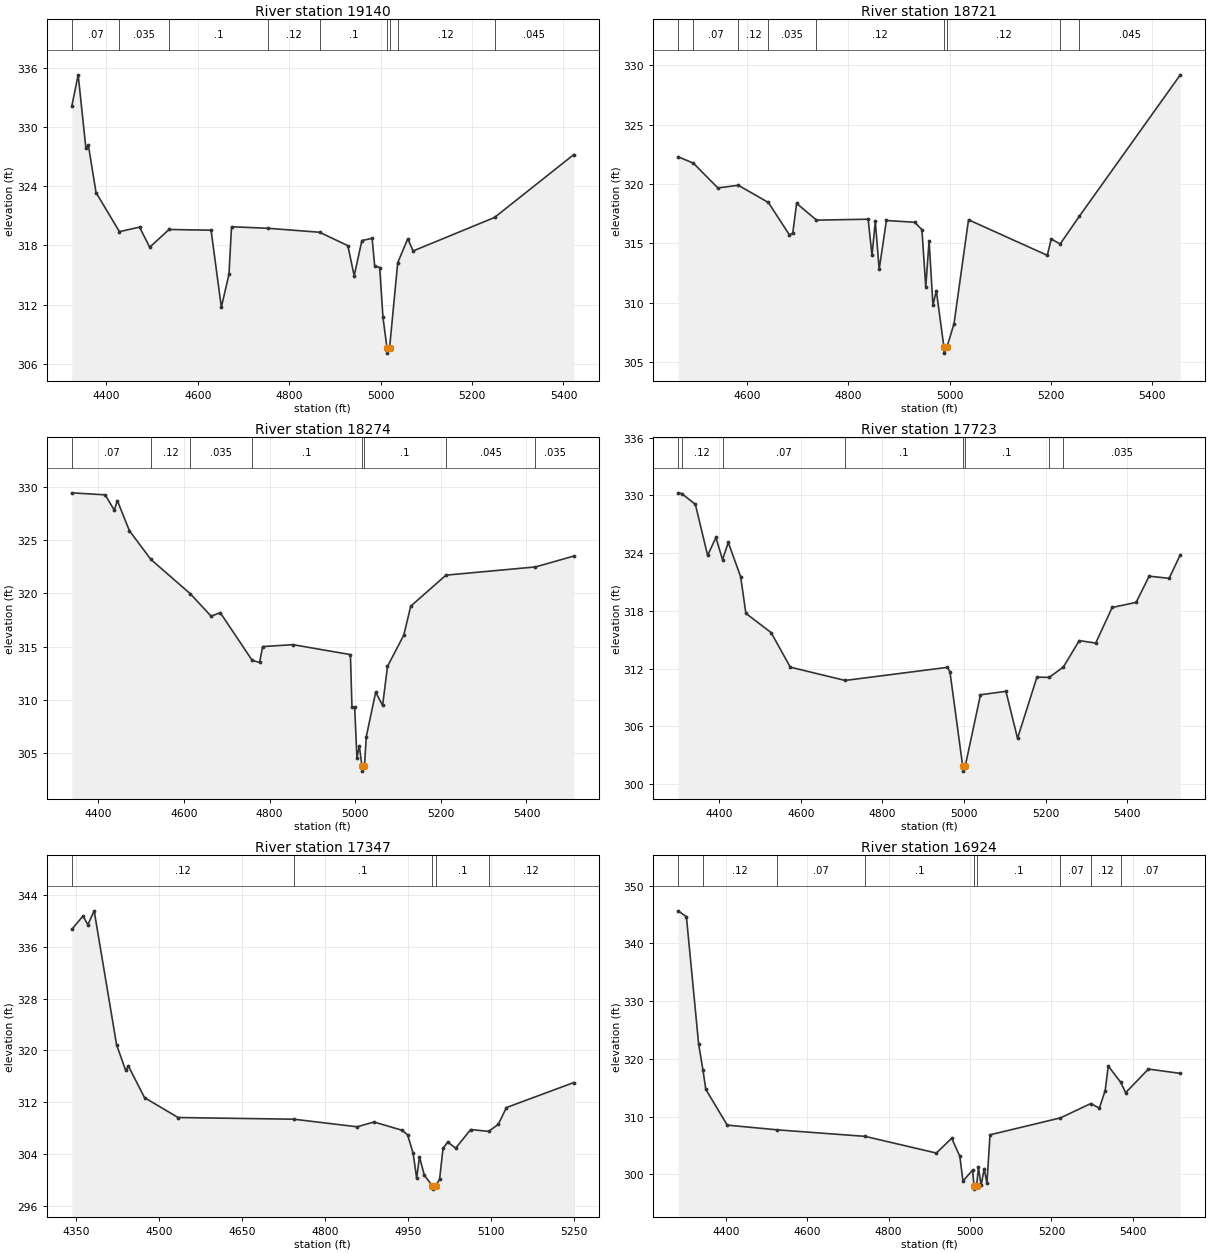
Type RM Length L Ch R = 1 ,19140   ,419,419,419
BEGIN DESCRIPTION:
BEN BRANCH 28.0
END DESCRIPTION:
XS GIS Cut Line= 3
      2531524.97     13764224.99        2532125.       13764525.
      2532525.04     13764675.02
#Sta/Elev= 30
  4324.6  332.12  4338.6  335.32  4355.4  327.91    4361  328.15  4377.7  323.37
  4428.8   319.4  4472.8  319.86  4495.1  317.82  4537.3  319.62  4629.3  319.55
  4651.7  311.73  4668.4  315.06    4674   319.9  4754.5  319.74  4866.6  319.34
  4928.4  317.98  4942.3  314.92  4959.1   318.5  4981.5  318.72  4987.1  315.93
  4998.1  315.76  5005.2   310.7  5014.1  307.57  5014.5  307.07  5019.6  307.57
  5037.5  316.25  5059.5  318.68  5071.1  317.44  5249.2  320.84  5422.7  327.23
#Mann= 9 ,-1 , 0
  4324.6     .07       0  4428.8    .035       0  4537.3      .1       0
  4754.5     .12       0  4866.6      .1       0  5014.1     .05       0
  5019.6      .1       0  5037.5     .12       0  5249.2    .045       0
Bank Sta=5014.1,5019.6
XS Rating Curve= 0 ,0
Exp/Cntr=0.3,0.1

Type RM Length L Ch R = 1 ,18721   ,447,447,447
BEGIN DESCRIPTION:
BEN BRANCH 27.0
END DESCRIPTION:
XS GIS Cut Line= 3
      2531474.99     13764474.99        2531875.       13764825.
      2532225.01       13765125.
#Sta/Elev= 30
  4463.6  322.29  4493.5  321.76  4541.9  319.67  4582.5  319.89  4641.8  318.44
  4683.3  315.71    4690  315.85  4697.6  318.37  4736.9  316.95    4839  317.03
  4846.6  313.98  4853.2  316.85  4860.8  312.79  4875.1  316.92  4931.1  316.77
  4945.3  316.15  4952.9  311.33  4959.5  315.21  4967.1  309.77  4973.8     311
  4988.8  306.23  4989.3  305.73  4994.7  306.23  5008.8  308.22  5037.4  316.98
  5193.2  313.98  5200.9  315.36  5218.6  314.94  5256.4  317.27  5456.1  329.21
#Mann= 9 ,-1 , 0
  4463.6     .12       0  4493.5     .07       0  4582.5     .12       0
  4641.8    .035       0  4736.9     .12       0  4988.8     .05       0
  4994.7     .12       0  5218.6      .1       0  5256.4    .045       0
Bank Sta=4988.8,4994.7
XS Rating Curve= 0 ,0
Exp/Cntr=0.3,0.1

Type RM Length L Ch R = 1 ,18274   ,551,551,551
BEGIN DESCRIPTION:
BEN BRANCH 26.0
END DESCRIPTION:
XS GIS Cut Line= 3
       2531303.5     13764716.04        2531775.       13765175.
      2532019.25     13765628.18
#Sta/Elev= 30
  4337.8  329.44  4415.9  329.25  4437.2  327.81  4444.2  328.72  4472.5  325.88
  4522.7  323.19  4614.5  319.98  4663.4  317.87  4684.7   318.2  4759.2  313.73
  4776.5  313.53  4783.7  315.02  4854.4   315.2  4988.7  314.27  4992.3  309.35
  4998.6  309.35  5003.9   304.6  5009.6   305.7  5015.5  303.84    5016  303.34
  5021.5  303.84  5025.8  306.58  5047.7  310.74  5063.9   309.5  5075.3  313.16
  5113.4   316.1  5129.6  318.81  5211.9  321.72  5420.9  322.49  5510.6  323.51
#Mann= 8 ,-1 , 0
  4337.8     .07       0  4522.7     .12       0  4614.5    .035       0
  4759.2      .1       0  5015.5     .05       0  5021.5      .1       0
  5211.9    .045       0  5420.9    .035       0
Bank Sta=5015.5,5021.5
XS Rating Curve= 0 ,0
Exp/Cntr=0.3,0.1

Type RM Length L Ch R = 1 ,17723   ,376,376,376
BEGIN DESCRIPTION:
BEN BRANCH 25.0
END DESCRIPTION:
XS GIS Cut Line= 3
      2531334.06     13764833.91      2531456.26     13765593.28
       2531512.9     13766050.75
#Sta/Elev= 30
  4299.9  330.27  4308.3   330.2  4341.9  329.07  4371.9  323.77  4392.2  325.63
  4408.4  323.33  4422.5  325.12  4452.9  321.54  4465.6  317.75  4527.5  315.75
  4574.5  312.16  4708.9  310.78  4959.4  312.14  4965.6  311.68  4996.9  301.86
  4997.4  301.36  5002.9  301.86  5040.4  309.29  5102.8  309.65  5131.2  304.77
  5178.7  311.12  5208.7   311.1  5243.4  312.17  5282.4  314.92  5322.7  314.66
    5363  318.36  5421.7  318.89  5453.7  321.61  5502.7  321.39    5530  323.84
#Mann= 8 ,-1 , 0
  4299.9     .07       0  4308.3     .12       0  4408.4     .07       0
  4708.9      .1       0  4996.9     .05       0  5002.9      .1       0
  5208.7     .07       0  5243.4    .035       0
Bank Sta=4996.9,5002.9
XS Rating Curve= 0 ,0
Exp/Cntr=0.3,0.1

Type RM Length L Ch R = 1 ,17347   ,423,423,423
BEGIN DESCRIPTION:
BEN BRANCH 24.0
END DESCRIPTION:
XS GIS Cut Line= 3
        2531225.     13765024.97        2531125.       13765675.
      2531275.01     13765875.02
#Sta/Elev= 30
  4342.3  338.68  4362.6  340.74  4371.4   339.4  4382.8  341.54  4423.3  320.88
  4439.7  316.92  4444.8  317.56  4473.9   312.7  4534.6  309.64  4743.7  309.38
  4858.3  308.21  4888.7  308.95  4939.3  307.68  4949.4  306.98  4959.5  304.13
  4965.8  300.27  4970.9  303.57  4979.7  300.73  4994.3  299.09  4994.8  298.59
  5000.5  299.09  5007.3  300.13  5013.5  304.87  5021.9  305.85  5036.4  304.92
  5063.5  307.79  5096.1   307.5  5113.5   308.6  5128.1  311.18    5250  315.04
#Mann= 5 ,-1 , 0
  4342.3     .12       0  4743.7      .1       0  4994.3     .05       0
  5000.5      .1       0  5096.1     .12       0
Bank Sta=4994.3,5000.5
XS Rating Curve= 0 ,0
Exp/Cntr=0.3,0.1

Type RM Length L Ch R = 1 ,16924   ,468,468,468
BEGIN DESCRIPTION:
BEN BRANCH 23.0
END DESCRIPTION:
XS GIS Cut Line= 3
        2530825.       13765025.        2530775.       13765725.
        2531125.     13766125.01
#Sta/Elev= 30
  4283.2  345.64  4303.3  344.61  4333.3  322.56    4344  318.01  4350.9  314.72
  4403.5  308.52  4526.6   307.7  4742.2  306.57  4917.3  303.68  4954.9  306.25
    4975   303.1  4982.5  298.82  5006.3  300.73  5009.8  297.93  5010.3  297.43
  5016.1  297.93  5020.6  301.21  5027.2  298.06  5034.8     301  5041.5  298.43
  5049.1  306.84    5222  309.77  5296.2  312.24  5317.7  311.48  5331.9  314.49
  5339.5  318.75    5370  315.95  5382.2  314.14  5438.2  318.23  5516.5  317.48
#Mann= 9 ,-1 , 0
  4283.2     .07       0    4344     .12       0  4526.6     .07       0
  4742.2      .1       0  5009.8     .05       0  5016.1      .1       0
    5222     .07       0  5296.2     .12       0    5370     .07       0
Bank Sta=5009.8,5016.1
XS Rating Curve= 0 ,0
Exp/Cntr=0.3,0.1