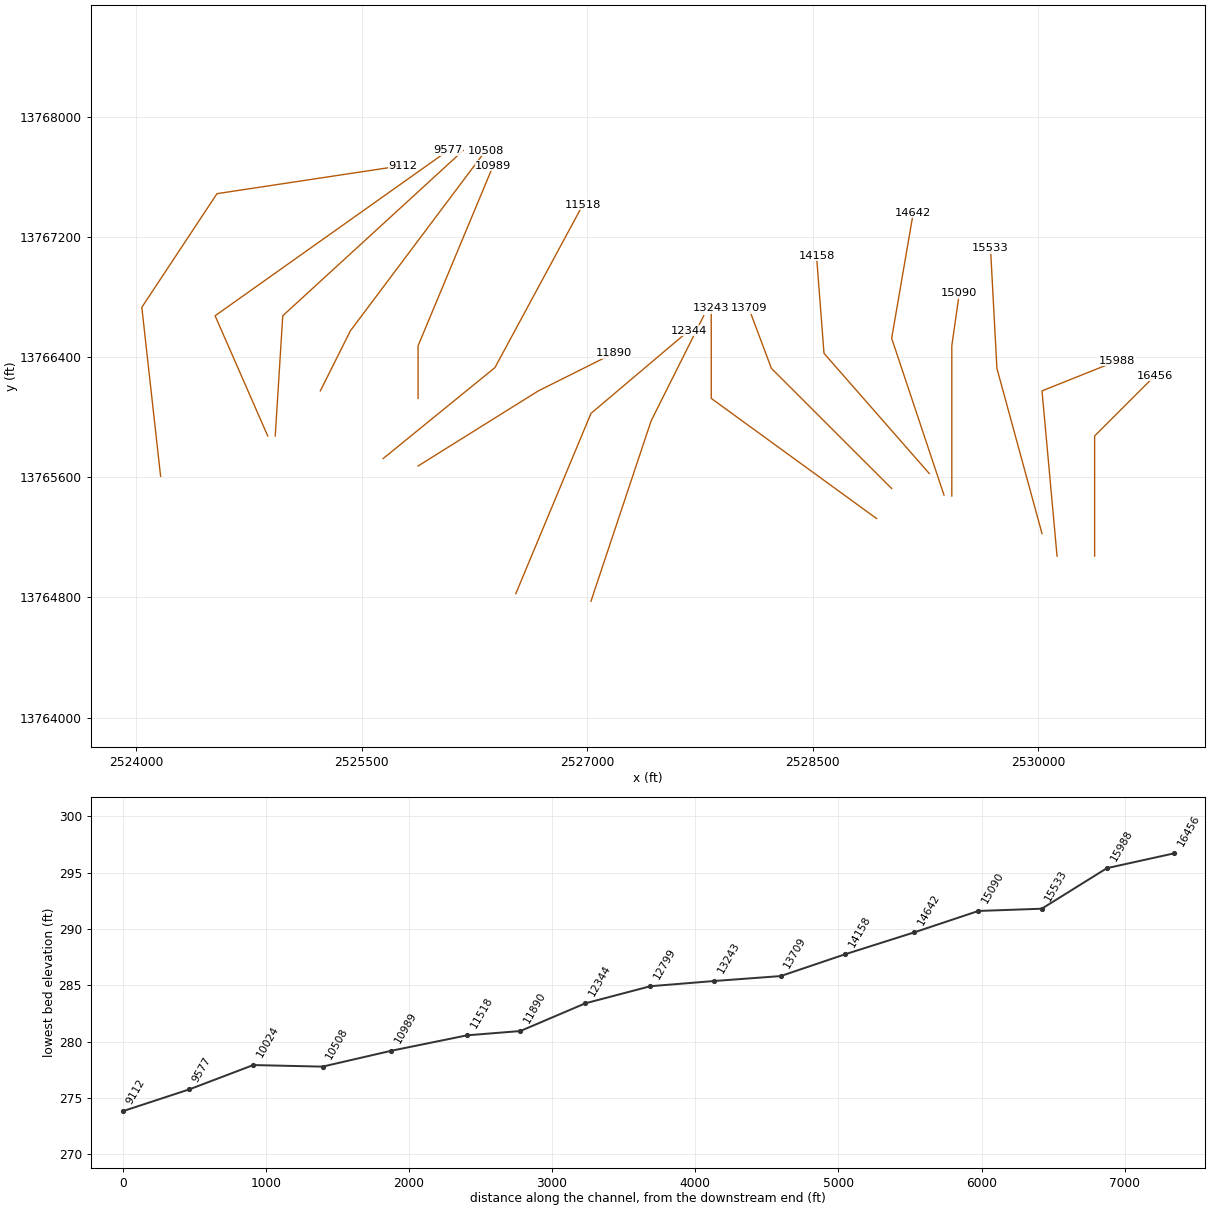
HEC-RAS study BEN BRANCH.prj: BEN BRANCH Base Level Engineering

--- BEN BRANCH.g01 (geometry) --- (continued)

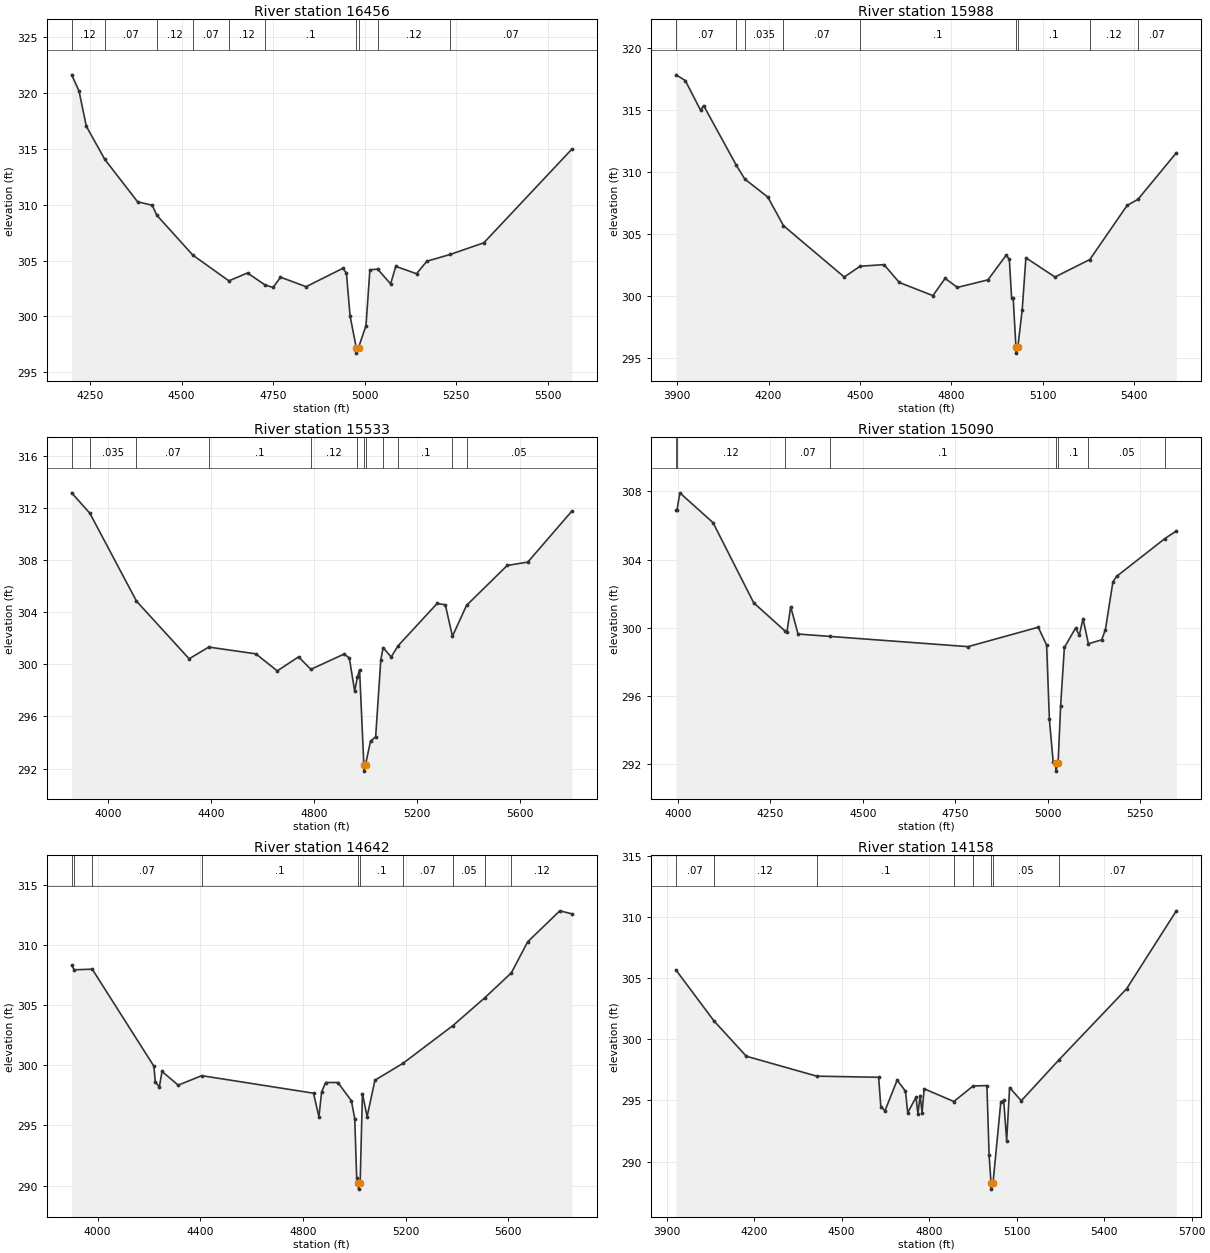
Type RM Length L Ch R = 1 ,16456   ,468,468,468
BEGIN DESCRIPTION:
BEN BRANCH 22.0
END DESCRIPTION:
XS GIS Cut Line= 3
        2530375.     13765075.05        2530375.       13765875.
      2530774.97     13766274.97
#Sta/Elev= 30
  4200.1  321.63  4220.1  320.19  4240.1  317.02  4290.7  314.05  4380.1  310.26
  4420.1  309.95  4432.4  309.06  4530.8  305.49  4629.3  303.18  4680.1  303.89
  4727.7  302.82  4750.1  302.59  4770.1  303.51  4840.1  302.66  4940.1   304.3
  4950.1  303.89  4960.1  300.05  4976.9  297.21  4977.4  296.71  4983.2  297.21
  5003.6  299.18  5014.2  304.17  5035.5  304.23  5070.8  302.91  5084.9  304.48
  5141.5  303.82  5169.8  304.94  5233.8  305.55  5325.3  306.59  5565.7  314.98
#Mann= 10 ,-1 , 0
  4200.1     .12       0  4290.7     .07       0  4432.4     .12       0
  4530.8     .07       0  4629.3     .12       0  4727.7      .1       0
  4976.9     .05       0  4983.2      .1       0  5035.5     .12       0
  5233.8     .07       0
Bank Sta=4976.9,4983.2
XS Rating Curve= 0 ,0
Exp/Cntr=0.3,0.1

Type RM Length L Ch R = 1 ,15988   ,455,455,455
BEGIN DESCRIPTION:
BEN BRANCH 21.0
END DESCRIPTION:
XS GIS Cut Line= 3
        2530125.     13765075.02        2530025.       13766175.
      2530524.97     13766374.99
#Sta/Elev= 30
  3896.2  317.85  3926.3  317.39  3976.5     315  3986.5  315.37  4094.3  310.54
  4121.9  309.44  4197.4  307.99  4248.9  305.68  4448.4  301.54  4500.7  302.41
    4579  302.54  4629.2   301.1  4739.6  300.04  4779.8  301.43    4820   300.7
  4920.4  301.31  4980.6  303.31  4990.7  302.96  4998.2  299.85  5003.4  299.85
  5012.3   295.9  5012.8   295.4  5018.7   295.9    5033  298.91  5045.1  303.09
  5140.7  301.54    5255  302.95  5377.7  307.32    5413   307.8  5539.2  311.56
#Mann= 9 ,-1 , 0
  3896.2     .07       0  4094.3     .12       0  4121.9    .035       0
  4248.9     .07       0  4500.7      .1       0  5012.3     .05       0
  5018.7      .1       0    5255     .12       0    5413     .07       0
Bank Sta=5012.3,5018.7
XS Rating Curve= 0 ,0
Exp/Cntr=0.3,0.1

Type RM Length L Ch R = 1 ,15533   ,443,443,443
BEGIN DESCRIPTION:
BEN BRANCH 20.0
END DESCRIPTION:
XS GIS Cut Line= 3
      2530024.99     13765225.04        2529725.       13766325.
      2529682.36     13767125.83
#Sta/Elev= 30
  3859.9  313.18  3930.5  311.61  4111.5  304.86  4315.9  300.43  4392.2  301.33
  4575.1  300.81    4658   299.5  4740.9  300.58  4788.5  299.62  4917.1  300.79
  4937.8   300.5  4958.6  297.95  4969.2  299.02  4977.6  299.59  4994.2   292.3
  4994.7   291.8  5000.7   292.3  5020.1   294.1  5040.1  294.44  5060.1  300.36
    5069  301.29  5100.2  300.57  5127.6  301.44  5278.8  304.68  5310.5  304.58
  5338.2  302.16  5392.8  304.53  5550.8   307.6  5630.9  307.86    5802  311.78
#Mann= 12 ,-1 , 0
  3859.9     .07       0  3930.5    .035       0  4111.5     .07       0
  4392.2      .1       0  4788.5     .12       0  4969.2      .1       0
  4994.2     .05       0  5000.7      .1       0    5069     .07       0
  5127.6      .1       0  5338.2     .07       0  5392.8     .05       0
Bank Sta=4994.2,5000.7
XS Rating Curve= 0 ,0
Exp/Cntr=0.3,0.1

Type RM Length L Ch R = 1 ,15090   ,448,448,448
BEGIN DESCRIPTION:
BEN BRANCH 19.0
END DESCRIPTION:
XS GIS Cut Line= 3
        2529425.     13765474.95        2529425.       13766475.
        2529475.       13766825.
#Sta/Elev= 30
  3994.8  306.91  3997.4  306.92  4004.8  307.92  4094.8  306.17  4204.8  301.47
  4289.4  299.82  4294.8  299.78  4304.8  301.24  4324.8  299.64  4411.2   299.5
  4784.8   298.9  4974.8  300.04  4997.4  298.99  5004.9  294.63  5015.1  292.15
  5021.9   292.1  5022.4   291.6  5028.5   292.1  5035.3  295.42  5045.4  298.85
  5075.7  299.99  5085.8  299.57  5095.9  300.54  5110.5  299.07  5146.4   299.3
  5156.5   299.9  5176.7  302.69  5186.8  303.02  5317.5  305.24  5348.4  305.68
#Mann= 8 ,-1 , 0
  3994.8    .035       0  3997.4     .12       0  4289.4     .07       0
  4411.2      .1       0  5021.9     .05       0  5028.5      .1       0
  5110.5     .05       0  5317.5     .07       0
Bank Sta=5021.9,5028.5
XS Rating Curve= 0 ,0
Exp/Cntr=0.3,0.1

Type RM Length L Ch R = 1 ,14642   ,484,484,484
BEGIN DESCRIPTION:
BEN BRANCH 18.0
END DESCRIPTION:
XS GIS Cut Line= 3
      2529373.14     13765481.12        2529025.       13766525.
      2529168.97      13767361.4
#Sta/Elev= 30
  3898.8  308.33  3908.9  307.97  3978.9  308.02  4219.1  299.94  4224.6  298.66
  4240.2  298.19  4250.8   299.5    4314  298.36  4405.5  299.15  4841.1  297.69
  4862.2  295.72  4872.7   297.8  4888.5  298.58    4936  298.58  4988.7  297.06
  5001.7  295.57  5009.4   290.6  5016.1   290.2  5016.6   289.7  5022.8   290.2
  5031.7  297.66  5049.9  295.74  5080.4  298.77  5189.8  300.18  5384.2  303.32
  5507.5  305.62  5611.8  307.71  5675.6   310.3  5800.8  312.88  5847.9  312.63
#Mann= 10 ,-1 , 0
  3898.8     .07       0  3908.9     .12       0  3978.9     .07       0
  4405.5      .1       0  5016.1     .05       0  5022.8      .1       0
  5189.8     .07       0  5384.2     .05       0  5507.5     .07       0
  5611.8     .12       0
Bank Sta=5016.1,5022.8
XS Rating Curve= 0 ,0
Exp/Cntr=0.3,0.1

Type RM Length L Ch R = 1 ,14158   ,449,449,449
BEGIN DESCRIPTION:
BEN BRANCH 17.0
END DESCRIPTION:
XS GIS Cut Line= 3
      2529275.02     13765624.97        2528575.       13766425.
        2528525.     13767075.03
#Sta/Elev= 30
  3932.5  305.64  4061.5  301.52  4173.1  298.61  4414.9  296.98  4626.8  296.89
  4634.4  294.48  4648.6  294.15  4690.4  296.66  4718.9  295.75  4726.5     294
  4754.9  295.25  4761.6  293.91  4769.2   295.4  4775.8  294.01  4782.9  295.95
  4884.7  294.91  4950.8  296.18  4998.1  296.21  5005.6  290.52  5012.2  288.25
  5012.7  287.75    5019  288.25  5045.7  294.87  5055.7     295  5065.8  291.69
  5075.8  296.05  5115.9  294.97  5245.7  298.33    5477  304.12  5647.5  310.49
#Mann= 8 ,-1 , 0
  3932.5     .07       0  4061.5     .12       0  4414.9      .1       0
  4884.7     .12       0  4950.8     .05       0  5012.2     .05       0
    5019     .05       0  5245.7     .07       0
Bank Sta=5012.2,5019
XS Rating Curve= 0 ,0
Exp/Cntr=0.3,0.1

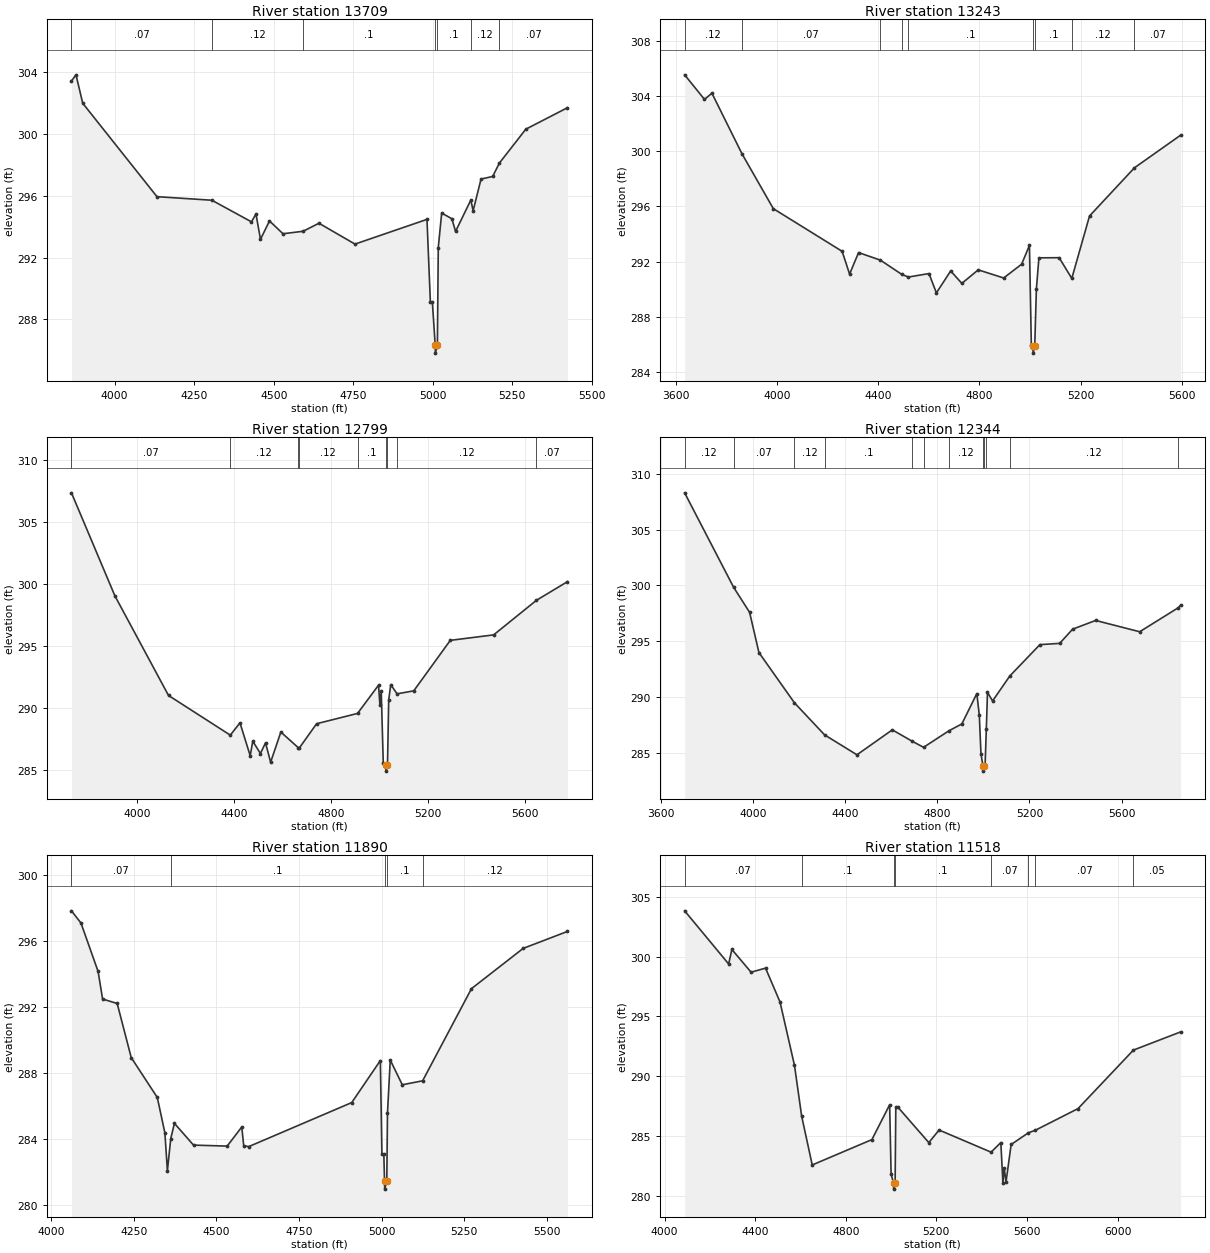
Type RM Length L Ch R = 1 ,13709   ,466,466,466
BEGIN DESCRIPTION:
BEN BRANCH 16.0
END DESCRIPTION:
XS GIS Cut Line= 3
      2529025.01     13765524.99        2528225.       13766325.
        2528075.     13766725.01
#Sta/Elev= 30
  3864.5  303.44  3878.7  303.84  3899.9     302  4133.2  295.95  4305.8  295.72
  4430.2  294.32  4444.3  294.83  4458.5  293.19  4486.8  294.38  4529.2  293.55
  4592.4  293.71  4642.3  294.23  4755.5  292.88  4981.7  294.48  4992.4  289.12
  4998.6  289.12  5007.6  286.32  5008.1  285.82  5014.4  286.32  5017.2  292.65
  5027.9  294.89    5060  294.52  5071.5   293.7  5119.5  295.73  5126.7  295.04
  5151.6  297.09  5188.1  297.26  5209.4  298.13  5292.3  300.32  5423.1  301.71
#Mann= 7 ,-1 , 0
  3864.5     .07       0  4305.8     .12       0  4592.4      .1       0
  5007.6     .05       0  5014.4      .1       0  5119.5     .12       0
  5209.4     .07       0
Bank Sta=5007.6,5014.4
XS Rating Curve= 0 ,0
Exp/Cntr=0.3,0.1

Type RM Length L Ch R = 1 ,13243   ,444,444,444
BEGIN DESCRIPTION:
BEN BRANCH 15.0
END DESCRIPTION:
XS GIS Cut Line= 3
      2528925.01     13765324.99        2527825.       13766125.
        2527825.     13766725.04
#Sta/Elev= 30
  3635.1  305.53  3713.5  303.75  3742.9   304.2  3861.8  299.81  3985.6  295.84
  4257.6  292.75    4287   291.1  4322.5  292.66    4409  292.11  4493.4  291.08
  4519.5  290.89  4600.7  291.14  4630.1  289.74  4686.5  291.33  4730.6  290.43
  4795.5  291.41    4896  290.82    4967  291.82  4997.8  293.18  5005.3  285.96
  5011.9  285.88  5012.4  285.38  5018.7  285.88  5025.3  290.04  5035.3  292.28
  5115.3  292.29  5165.2  290.79  5235.3  295.31  5412.9   298.8  5595.3  301.16
#Mann= 9 ,-1 , 0
  3635.1     .12       0  3861.8     .07       0    4409     .12       0
  4493.4     .07       0  4519.5      .1       0  5011.9     .05       0
  5018.7      .1       0  5165.2     .12       0  5412.9     .07       0
Bank Sta=5011.9,5018.7
XS Rating Curve= 0 ,0
Exp/Cntr=0.3,0.1

Type RM Length L Ch R = 1 ,12799   ,455,455,455
BEGIN DESCRIPTION:
BEN BRANCH 14.0
END DESCRIPTION:
XS GIS Cut Line= 3
      2527024.99     13764774.96        2527425.       13765975.
      2527775.01     13766675.02
#Sta/Elev= 30
  3728.2  307.35  3907.4  299.05  4128.8  291.02  4383.9  287.82  4423.9  288.81
  4466.1  286.16  4476.7  287.33  4508.3  286.34  4529.4   287.2  4550.4  285.64
  4592.6  288.07    4664  286.82    4668  286.76  4740.2  288.74  4909.3  289.57
    4996  291.85  5001.5  290.27  5007.1  291.36  5015.5  285.56    5026  285.42
  5026.5  284.92  5032.9  285.42  5037.9  290.65  5046.3  291.89  5072.4  291.15
  5141.3  291.39  5292.2  295.46  5471.1   295.9    5648  298.69  5775.8  300.19
#Mann= 9 ,-1 , 0
  3728.2     .07       0  4383.9     .12       0    4664      .1       0
    4668     .12       0  4909.3      .1       0    5026     .05       0
  5032.9      .1       0  5072.4     .12       0    5648     .07       0
Bank Sta=5026,5032.9
XS Rating Curve= 0 ,0
Exp/Cntr=0.3,0.1

Type RM Length L Ch R = 1 ,12344   ,454,454,454
BEGIN DESCRIPTION:
BEN BRANCH 13.0
END DESCRIPTION:
XS GIS Cut Line= 3
        2526525.       13764825.        2527025.       13766025.
      2527675.03     13766575.02
#Sta/Elev= 30
  3704.1  308.28  3916.7  299.83  3985.8   297.6  4026.4     294  4180.3  289.51
  4311.2  286.64  4451.6  284.86  4604.9  287.09  4692.2  286.06  4740.6  285.53
  4850.9  287.01  4906.6  287.62  4971.6  290.33  4982.4  288.39  4989.5  284.96
  4997.9   283.9  4998.4   283.4  5004.8   283.9  5007.4   283.9  5012.8  287.18
  5017.8  290.45  5039.8  289.67  5114.8  291.91  5245.2  294.71    5331  294.82
    5387  296.09    5487  296.87  5678.1  295.86  5846.4  298.02  5855.6  298.24
#Mann= 12 ,-1 , 0
  3704.1     .12       0  3916.7     .07       0  4180.3     .12       0
  4311.2      .1       0  4692.2     .12       0  4740.6      .1       0
  4850.9     .12       0  4997.9     .05       0  5004.8     .12       0
  5012.8      .1       0  5114.8     .12       0  5846.4     .07       0
Bank Sta=4997.9,5004.8
XS Rating Curve= 0 ,0
Exp/Cntr=0.3,0.1

Type RM Length L Ch R = 1 ,11890   ,372,372,372
BEGIN DESCRIPTION:
BEN BRANCH 12.0
END DESCRIPTION:
XS GIS Cut Line= 3
      2525875.04     13765675.02        2526675.       13766175.
      2527175.02     13766425.01
#Sta/Elev= 30
  4060.7  297.82  4089.5  297.08  4141.4  294.14    4155  292.47  4199.2   292.2
  4241.7  288.92  4320.7   286.5  4343.7  284.35  4351.3  282.06  4361.5  284.01
  4372.6  284.93  4430.4  283.61  4532.4  283.55  4576.6  284.71  4582.5  283.57
  4597.8  283.52  4909.7  286.19  4996.4  288.74  5001.1  283.07  5006.9  283.07
    5009  281.44  5009.5  280.94  5015.9  281.44    5018  285.56  5026.4  288.77
  5062.8  287.27  5124.4  287.51  5272.4   293.1  5428.9  295.54  5563.1  296.57
#Mann= 5 ,-1 , 0
  4060.7     .07       0  4361.5      .1       0    5009     .05       0
  5015.9      .1       0  5124.4     .12       0
Bank Sta=5009,5015.9
XS Rating Curve= 0 ,0
Exp/Cntr=0.3,0.1

Type RM Length L Ch R = 1 ,11518   ,529,529,529
BEGIN DESCRIPTION:
BEN BRANCH 11.0
END DESCRIPTION:
XS GIS Cut Line= 3
      2525642.81     13765724.53      2526386.25     13766329.81
       2526970.9      13767413.7
#Sta/Elev= 30
  4088.4  303.82  4282.7  299.38    4297  300.59  4381.8  298.69  4445.7  299.03
  4509.6   296.2  4573.5   290.9  4605.1  286.66  4651.8  282.58  4915.4   284.7
  4993.7  287.61  5000.1  281.82    5011  281.06  5011.5  280.56  5017.9  281.06
  5020.9  287.39  5028.8  287.44  5166.6  284.45  5212.1   285.5  5441.6  283.65
  5484.7  284.45  5493.9  281.08  5499.6  282.32  5507.5  281.15  5530.2  284.29
  5606.5  285.27    5637  285.48  5825.6  287.29  6070.1  292.18  6278.6   293.7
#Mann= 8 ,-1 , 0
  4088.4     .07       0  4605.1      .1       0    5011     .05       0
  5017.9      .1       0  5441.6     .07       0  5606.5     .12       0
    5637     .07       0  6070.1     .05       0
Bank Sta=5011,5017.9
XS Rating Curve= 0 ,0
Exp/Cntr=0.3,0.1

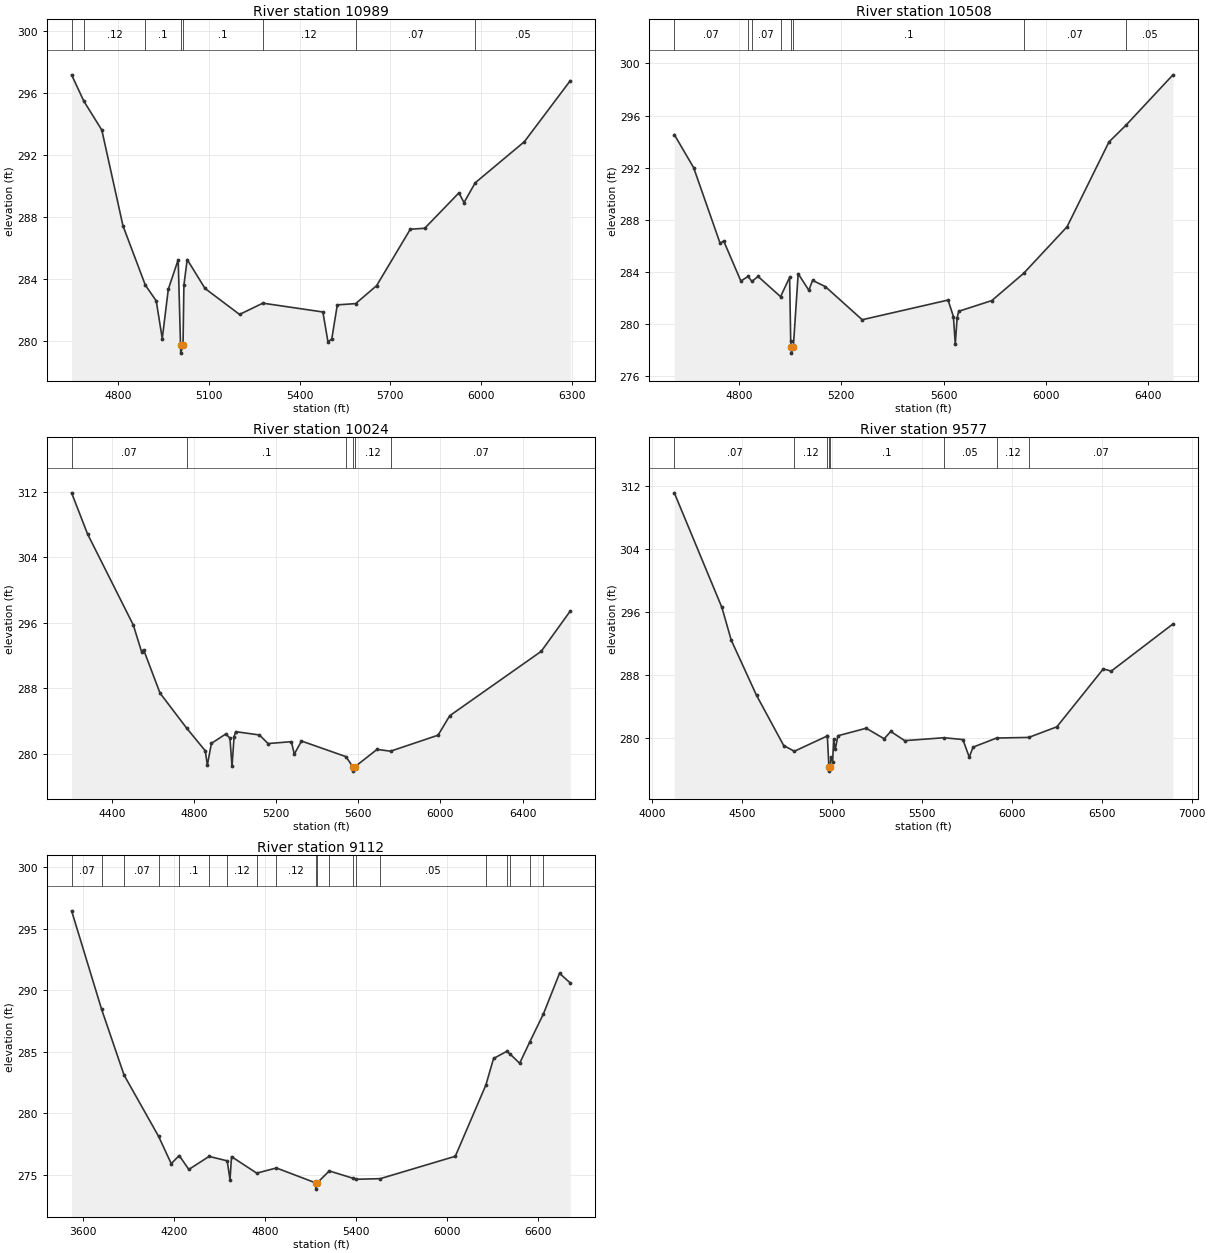
Type RM Length L Ch R = 1 ,10989   ,481,481,481
BEGIN DESCRIPTION:
BEN BRANCH 10.0
END DESCRIPTION:
XS GIS Cut Line= 3
        2525875.     13766125.03        2525875.       13766475.
      2526375.01     13767675.03
#Sta/Elev= 30
  4645.5  297.18  4685.7  295.49  4745.5  293.61  4815.5  287.42  4889.4  283.59
  4925.5  282.57  4945.5  280.13  4965.5  283.32  4998.2  285.23    5006  279.69
  5006.5  279.19  5014.2  279.69  5017.1  283.58    5028  285.24    5087  283.37
  5201.3  281.69  5278.2  282.42    5477  281.85  5493.8  279.92  5506.3   280.1
  5524.7  282.31  5585.3  282.39  5654.7  283.55  5766.3   287.2  5813.9  287.26
  5927.1  289.55  5943.9  288.92    5981   290.2  6143.8  292.86  6295.5   296.8
#Mann= 8 ,-1 , 0
  4645.5     .07       0  4685.7     .12       0  4889.4      .1       0
    5006     .05       0  5014.2      .1       0  5278.2     .12       0
  5585.3     .07       0    5981     .05       0
Bank Sta=5006,5014.2
XS Rating Curve= 0 ,0
Exp/Cntr=0.3,0.1

Type RM Length L Ch R = 1 ,10508   ,484,484,484
BEGIN DESCRIPTION:
BEN BRANCH 9.0
END DESCRIPTION:
XS GIS Cut Line= 3
        2525225.       13766175.        2525425.       13766575.
      2526324.99     13767774.99
#Sta/Elev= 30
  4548.5  294.54    4624     292  4727.4   286.2  4741.4  286.38  4808.4  283.31
  4836.5  283.66  4851.6  283.28  4875.5  283.66  4963.4  282.11  4998.8  283.59
    5003  278.72  5005.2  278.28  5005.7  277.78  5013.4  278.28  5032.2  283.87
  5073.8   282.6  5088.4  283.36  5138.4  282.88  5282.2  280.34  5617.6  281.85
  5638.4  280.58  5645.7  278.47    5653  280.51  5659.3  280.99  5788.4  281.81
  5912.7   283.9  6082.2  287.47  6245.7  293.97  6313.3  295.28  6495.7  299.12
#Mann= 8 ,-1 , 0
  4548.5     .07       0  4836.5      .1       0  4851.6     .07       0
  4963.4      .1       0  5005.2     .05       0  5013.4      .1       0
  5912.7     .07       0  6313.3     .05       0
Bank Sta=5005.2,5013.4
XS Rating Curve= 0 ,0
Exp/Cntr=0.3,0.1

Type RM Length L Ch R = 1 ,10024   ,447,447,447
BEGIN DESCRIPTION:
BEN BRANCH 8.0
END DESCRIPTION:
XS GIS Cut Line= 3
        2524925.     13765875.02        2524975.       13766675.
      2526174.98     13767774.99
#Sta/Elev= 30
  4202.9  311.84  4280.5  306.83  4503.5  295.73  4543.5   292.5  4553.6  292.73
  4633.7  287.43  4763.8  283.15  4854.1   280.4  4864.2  278.65  4884.2  281.31
  4954.3  282.45  4974.4  281.94  4984.4   278.5  4994.4  282.08  5001.9  282.73
  5117.6  282.33  5160.1  281.28  5273.6  281.51  5287.8  279.99  5322.9  281.59
    5540  279.68  5573.5  278.42    5574  277.92  5581.7  278.42    5691  280.57
  5756.8  280.35  5988.3   282.3    6045  284.67  6490.8  292.52  6632.3  297.43
#Mann= 6 ,-1 , 0
  4202.9     .07       0  4763.8      .1       0    5540     .12       0
  5573.5     .05       0  5581.7     .12       0  5756.8     .07       0
Bank Sta=5573.5,5581.7
XS Rating Curve= 0 ,0
Exp/Cntr=0.3,0.1

Type RM Length L Ch R = 1 ,9577    ,465,465,465
BEGIN DESCRIPTION:
BEN BRANCH 7.0
END DESCRIPTION:
XS GIS Cut Line= 3
      2524874.99     13765875.01        2524525.       13766675.
      2526075.04     13767775.03
#Sta/Elev= 30
  4122.1  311.18  4386.8  296.59    4439  292.42  4579.4  285.41  4730.6  279.02
    4790  278.29  4968.8  280.19  4973.5   280.2  4982.2  276.26  4982.7  275.76
  4990.4  276.26  4992.6  277.56  5002.7  276.98  5008.8  279.82  5017.5  278.54
  5032.1  280.26  5189.7  281.22  5289.6  279.88  5326.2  280.81  5403.7  279.64
  5622.1  280.01  5727.3  279.78  5762.9  277.54  5783.8  278.81  5914.6  279.97
  6093.8  280.05  6250.1   281.4  6508.4  288.77  6552.6  288.49    6896  294.49
#Mann= 8 ,-1 , 0
  4122.1     .07       0    4790     .12       0  4968.8      .1       0
  4982.2     .05       0  4990.4      .1       0  5622.1     .05       0
  5914.6     .12       0  6093.8     .07       0
Bank Sta=4982.2,4990.4
XS Rating Curve= 0 ,0
Exp/Cntr=0.3,0.1

Type RM Length L Ch R = 1 ,9112    ,0,0,0
BEGIN DESCRIPTION:
BEN BRANCH 6.0
END DESCRIPTION:
XS GIS Cut Line= 4
      2524162.54     13765606.12      2524037.53     13766731.13
      2524537.54     13767487.72      2525775.03       13767675.
#Sta/Elev= 30
  3523.1  296.44  3721.3  288.43  3869.3  283.09  4097.5   278.1  4180.5  275.89
  4233.1  276.55  4296.7  275.42  4430.5  276.48  4549.7  276.12  4568.4  274.59
  4578.4  276.46  4744.6  275.12  4874.6  275.54    5135  274.32  5135.5  273.82
  5143.3  274.32  5223.2   275.3  5383.2  274.69  5396.5  274.62  5559.8  274.67
  6054.9  276.49  6256.7  282.28  6307.5  284.44  6394.9  285.02    6419  284.77
  6479.7  284.05  6546.2  285.78  6636.7  288.07  6742.7  291.36  6813.5  290.58
#Mann= 20 ,-1 , 0
  3523.1     .07       0  3721.3     .12       0  3869.3     .07       0
  4097.5     .12       0  4233.1      .1       0  4430.5     .07       0
  4549.7     .12       0  4744.6     .07       0  4874.6     .12       0
    5135     .05       0  5143.3     .12       0  5223.2     .07       0
  5383.2     .12       0  5396.5     .07       0  5559.8     .05       0
  6256.7     .07       0  6394.9     .12       0    6419     .07       0
  6546.2     .05       0  6636.7     .07       0
Bank Sta=5135,5143.3
XS Rating Curve= 0 ,0
Exp/Cntr=0.3,0.1

Chan Stop Cuts=-1
Use User Specified Reach Order=0
Composite Channel Slope=5