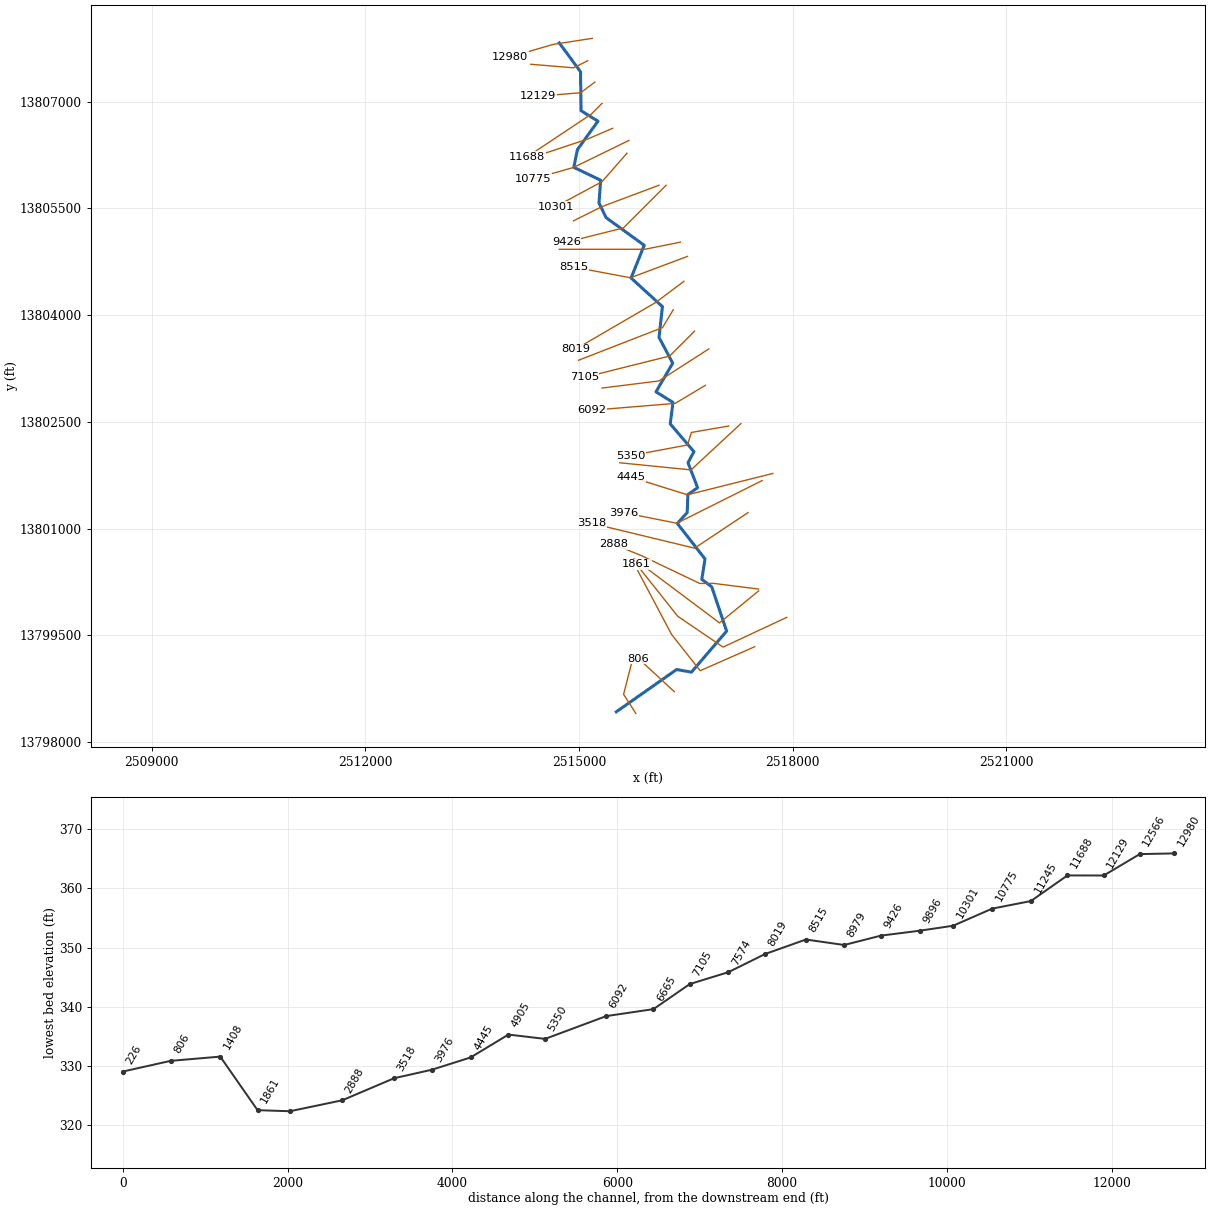
--- BOGGY CREEK 2.prj (project) ---

Proj Title=BOGGY CREEK 2 Base Level Engineering
Current Plan=p01
Default Exp/Contr=0.3,0.1
English Units
Geom File=g01
Flow File=f01
Plan File=p01
Y Axis Title=Elevation
X Axis Title(PF)=Main Channel Distance
X Axis Title(XS)=Station
BEGIN DESCRIPTION:
BOGGY CREEK 2
END DESCRIPTION:
DSS Export Rating Curves= 0
DSS Export Rating Curve Sorted= 0
DSS Export Volume Flow Curves= 0
DXF OffsetX= 0
DXF OffsetY= 0
DXF ScaleX= 1
DXF ScaleY= 10

--- BOGGY CREEK 2.p01 (plan) ---

Plan Title=Multiple Run
Short Identifier=Multiple
Geom File=g01
Flow File=f01
Subcritical Flow
K Sum by GR= 0
Std Step Tol= 0.01
Critical Tol= 0.01
Num of Std Step Trials= 20
Max Error Tol= 0.3
Flow Tol Ratio= 0.001
Split Flow NTrial= 30
Split Flow Tol= 0.02
Split Flow Ratio= 0.02
Log Output Level= 0
Friction Slope Method= 1
Unsteady Friction Slope Method= 2
Unsteady Bridges Friction Slope Method= 1
Parabolic Critical Depth
Global Vel Dist=  1 , 1 , 1
Global Log Level= 0
CheckData=True
Encroach Param= -1, 0, 0, 0
BEGIN DESCRIPTION:
Multiple Run
END DESCRIPTION:

--- BOGGY CREEK 2.f01 (steady flow) ---

Flow Title=Multiple
Number of Profiles=7
Profile Names=10-year,25-year,50-year,1pct_min,100-year,1pct_plu,500-year
River Rch & RM= BOGGY CREEK 2,Reach-1,12980
     648    1034    1378     890    1776    3543    2916
River Rch & RM= BOGGY CREEK 2,Reach-1,10301
     993    1614    2179    1422    2837    5661    4763
River Rch & RM= BOGGY CREEK 2,Reach-1,806
    1573    2617    3588    2374    4736    9450    8179
Boundary for River Rch & Prof#=BOGGY CREEK 2,Reach-1,1
Up Type=0
Dn Type=3
Dn Slope=0.005
Boundary for River Rch & Prof#=BOGGY CREEK 2,Reach-1,2
Up Type=0
Dn Type=3
Dn Slope=0.005
Boundary for River Rch & Prof#=BOGGY CREEK 2,Reach-1,3
Up Type=0
Dn Type=3
Dn Slope=0.005
Boundary for River Rch & Prof#=BOGGY CREEK 2,Reach-1,4
Up Type=0
Dn Type=3
Dn Slope=0.005
Boundary for River Rch & Prof#=BOGGY CREEK 2,Reach-1,5
Up Type=0
Dn Type=3
Dn Slope=0.005
Boundary for River Rch & Prof#=BOGGY CREEK 2,Reach-1,6
Up Type=0
Dn Type=3
Dn Slope=0.005
Boundary for River Rch & Prof#=BOGGY CREEK 2,Reach-1,7
Up Type=0
Dn Type=3
Dn Slope=0.005

--- BOGGY CREEK 2.g01 (geometry) ---

Geom Title=Existing Conditions
Program Version=4.10

River Reach=BOGGY CREEK 2   ,Reach-1
Reach XY= 30
        2514725.       13807825.       2515023.4     13807419.12
       2515030.4     13806872.29      2515267.92     13806725.02
      2514980.52     13806327.43      2514928.45     13806076.48
      2515305.91     13805895.53      2515282.56       13805575.
      2515383.13     13805368.93      2515917.55     13804981.07
      2515732.79     13804521.58      2516173.45     13804119.15
      2516125.75     13803685.68      2516317.69      13803324.9
      2516082.61     13802921.64      2516321.64      13802773.3
      2516283.08      13802471.7      2516615.63     13802081.66
      2516532.53     13801925.01      2516667.77     13801574.69
      2516530.36      13801477.7      2516521.52     13801226.26
      2516383.01     13801071.72      2516771.47     13800573.53
      2516726.51     13800286.87       2516865.7     13800181.68
      2517075.11     13799559.63      2516581.18     13798982.76
      2516372.49     13799019.67        2515525.       13798425.

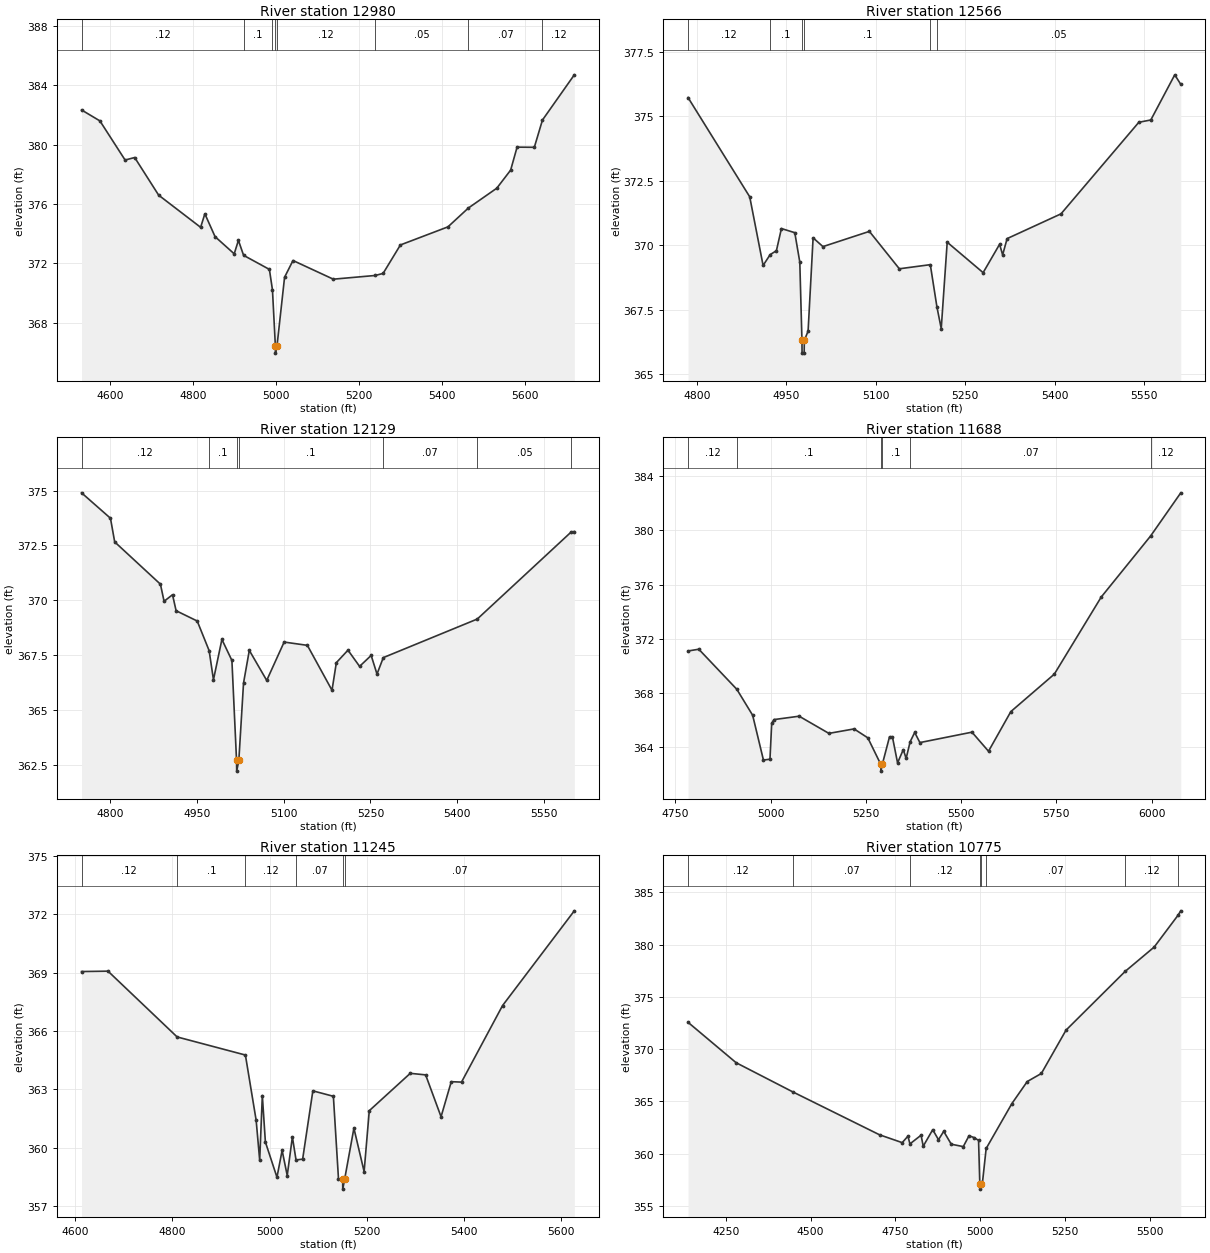
Type RM Length L Ch R = 1 ,12980   ,414,414,414
BEGIN DESCRIPTION:
X18323
END DESCRIPTION:
XS GIS Cut Line= 3
      2515188.73     13807889.32      2514637.39     13807803.68
      2514032.51     13807627.03
#Sta/Elev= 30
  4530.5  382.35  4574.8  381.61  4635.5  378.97  4658.6  379.14  4716.4   376.6
  4817.6  374.43  4827.8  375.34  4852.4   373.8  4898.6  372.64  4908.7  373.55
  4921.2  372.54  4983.4  371.59  4990.8  370.21  4997.8  366.44    4998  365.94
  5001.8  366.44    5020  371.06  5040.3  372.19  5137.5  370.93  5238.6  371.18
  5257.6  371.32  5299.3  373.24  5413.9  374.46  5463.1  375.73  5531.7  377.07
  5565.1  378.29  5580.6  379.84  5622.2  379.83  5641.8  381.67  5718.6  384.72
#Mann= 8 ,-1 , 0
  4530.5     .12       0  4921.2      .1       0  4990.8     .12       0
  4997.8     .05       0  5001.8     .12       0  5238.6     .05       0
  5463.1     .07       0  5641.8     .12       0
Bank Sta=4997.8,5001.8
XS Rating Curve= 0 ,0
Exp/Cntr=0.3,0.1

Type RM Length L Ch R = 1 ,12566   ,437,437,437
BEGIN DESCRIPTION:
BOGGY CREEK 2 22.0
END DESCRIPTION:
XS GIS Cut Line= 3
        2515125.       13807575.        2514925.       13807475.
      2514324.98       13807525.
#Sta/Elev= 30
  4785.3  375.73  4888.7  371.88  4911.1  369.22    4923  369.64  4933.4  369.79
  4941.8  370.65  4964.2  370.49  4972.6  369.35  4976.2  366.32  4976.4  365.82
  4979.9  365.82  4980.2  366.32  4986.5  366.67  4994.9  370.29  5011.4  369.95
  5089.2  370.54  5139.4  369.09  5191.3  369.25  5202.4  367.61  5209.6  366.77
  5219.6  370.12  5279.8  368.94  5307.4  370.04  5312.5  369.63    5320  370.26
  5410.3  371.22  5540.7  374.77  5560.8  374.86  5600.9  376.61    5611  376.24
#Mann= 6 ,-1 , 0
  4785.3     .12       0    4923      .1       0  4976.2     .05       0
  4980.2      .1       0  5191.3     .12       0  5202.4     .05       0
Bank Sta=4976.2,4980.2
XS Rating Curve= 0 ,0
Exp/Cntr=0.3,0.1

Type RM Length L Ch R = 1 ,12129   ,441,441,441
BEGIN DESCRIPTION:
BOGGY CREEK 2 21.0
END DESCRIPTION:
XS GIS Cut Line= 3
      2515224.98     13807274.99        2515025.       13807125.
      2514424.96       13807075.
#Sta/Elev= 30
  4750.5   374.9  4800.5  373.74  4807.8  372.66  4886.9  370.73  4893.2  369.95
  4907.8  370.25    4914  369.52  4950.5  369.05  4971.1   367.7  4978.6  366.37
  4993.2  368.21  5010.5  367.25  5018.5   362.7  5018.8   362.2  5022.5   362.7
  5030.6  366.22  5040.6  367.71  5070.7  366.34  5100.8  368.09    5141  367.94
  5183.6  365.89  5191.1  367.15  5211.2  367.72  5231.3  366.98  5251.3  367.48
  5261.4  366.63  5272.3  367.38  5434.8  369.14  5597.5  373.12  5602.6  373.13
#Mann= 7 ,-1 , 0
  4750.5     .12       0  4971.1      .1       0  5018.5     .05       0
  5022.5      .1       0  5272.3     .07       0  5434.8     .05       0
  5597.5     .07       0
Bank Sta=5018.5,5022.5
XS Rating Curve= 0 ,0
Exp/Cntr=0.3,0.1

Type RM Length L Ch R = 1 ,11688   ,443,443,443
BEGIN DESCRIPTION:
BOGGY CREEK 2 20.0
END DESCRIPTION:
XS GIS Cut Line= 3
      2515325.02     13806975.02        2515175.       13806825.
      2514275.02     13806225.01
#Sta/Elev= 30
  4782.9  371.09  4811.2  371.22    4911  368.26  4952.6  366.34  4980.9  363.03
  4998.1  363.09  5002.6  365.74  5008.6  366.02  5074.7  366.27  5152.8     365
  5218.9  365.33    5255  364.67    5289  362.71  5289.3  362.21    5293  362.71
    5312  364.75  5319.6  364.74  5333.1  362.82  5348.1   363.8  5355.6  363.15
  5366.1  364.38  5378.1  365.07  5391.7  364.32  5528.4  365.09  5571.9  363.68
  5630.5  366.61  5744.7  369.38  5867.9  375.08  5997.5  379.59  6076.7  382.78
#Mann= 6 ,-1 , 0
  4782.9     .12       0    4911      .1       0    5289     .05       0
    5293      .1       0  5366.1     .07       0  5997.5     .12       0
Bank Sta=5289,5293
XS Rating Curve= 0 ,0
Exp/Cntr=0.3,0.1

Type RM Length L Ch R = 1 ,11245   ,470,470,470
BEGIN DESCRIPTION:
BOGGY CREEK 2 19.0
END DESCRIPTION:
XS GIS Cut Line= 3
      2515474.98     13806624.99        2515125.       13806475.
      2514525.02     13806275.01
#Sta/Elev= 30
  4613.3  369.05  4667.7  369.07  4809.8  365.69  4950.2  364.76  4972.3  361.41
  4979.6  359.35    4985  362.68  4991.3  360.29  5015.1  358.48  5025.7  359.86
  5036.2  358.57  5046.8  360.55  5054.3  359.37  5067.9  359.41  5088.9  362.92
  5131.1  362.64  5141.6   358.4  5150.2  358.37  5150.4  357.87  5154.2  358.37
  5173.3     361  5194.3  358.77  5204.9   361.9  5289.2  363.82  5320.8  363.74
  5352.5  361.59  5373.5  363.39  5394.6  363.37  5478.9   367.3  5626.5  372.17
#Mann= 6 ,-1 , 0
  4613.3     .12       0  4809.8      .1       0  4950.2     .12       0
  5054.3     .07       0  5150.2     .05       0  5154.2     .07       0
Bank Sta=5150.2,5154.2
XS Rating Curve= 0 ,0
Exp/Cntr=0.3,0.1

Type RM Length L Ch R = 1 ,10775   ,474,474,474
BEGIN DESCRIPTION:
BOGGY CREEK 2 18.0
END DESCRIPTION:
XS GIS Cut Line= 3
      2515702.65     13806454.65        2514925.       13806075.
      2514359.52     13805914.13
#Sta/Elev= 30
  4138.4  372.56  4280.3  368.69  4447.3   365.9  4703.3  361.79  4770.1  361.04
    4787  361.66  4792.9  360.92  4825.7  361.75  4832.1   360.7  4860.1  362.28
  4877.1  361.32  4892.5  362.12  4914.8  360.89  4950.2  360.66  4967.2   361.7
  4981.5  361.53  4995.3  361.26    4999  357.09  4999.2  356.59    5003  357.09
  5006.4  357.09  5017.7  360.48  5093.6  364.78  5138.9  366.89  5180.5  367.66
  5253.3  371.81  5427.6  377.43  5513.2  379.76  5583.2  382.79  5591.7  383.23
#Mann= 8 ,-1 , 0
  4138.4     .12       0  4447.3     .07       0  4792.9     .12       0
    4999     .05       0    5003     .12       0  5017.7     .07       0
  5427.6     .12       0  5583.2     .07       0
Bank Sta=4999,5003
XS Rating Curve= 0 ,0
Exp/Cntr=0.3,0.1

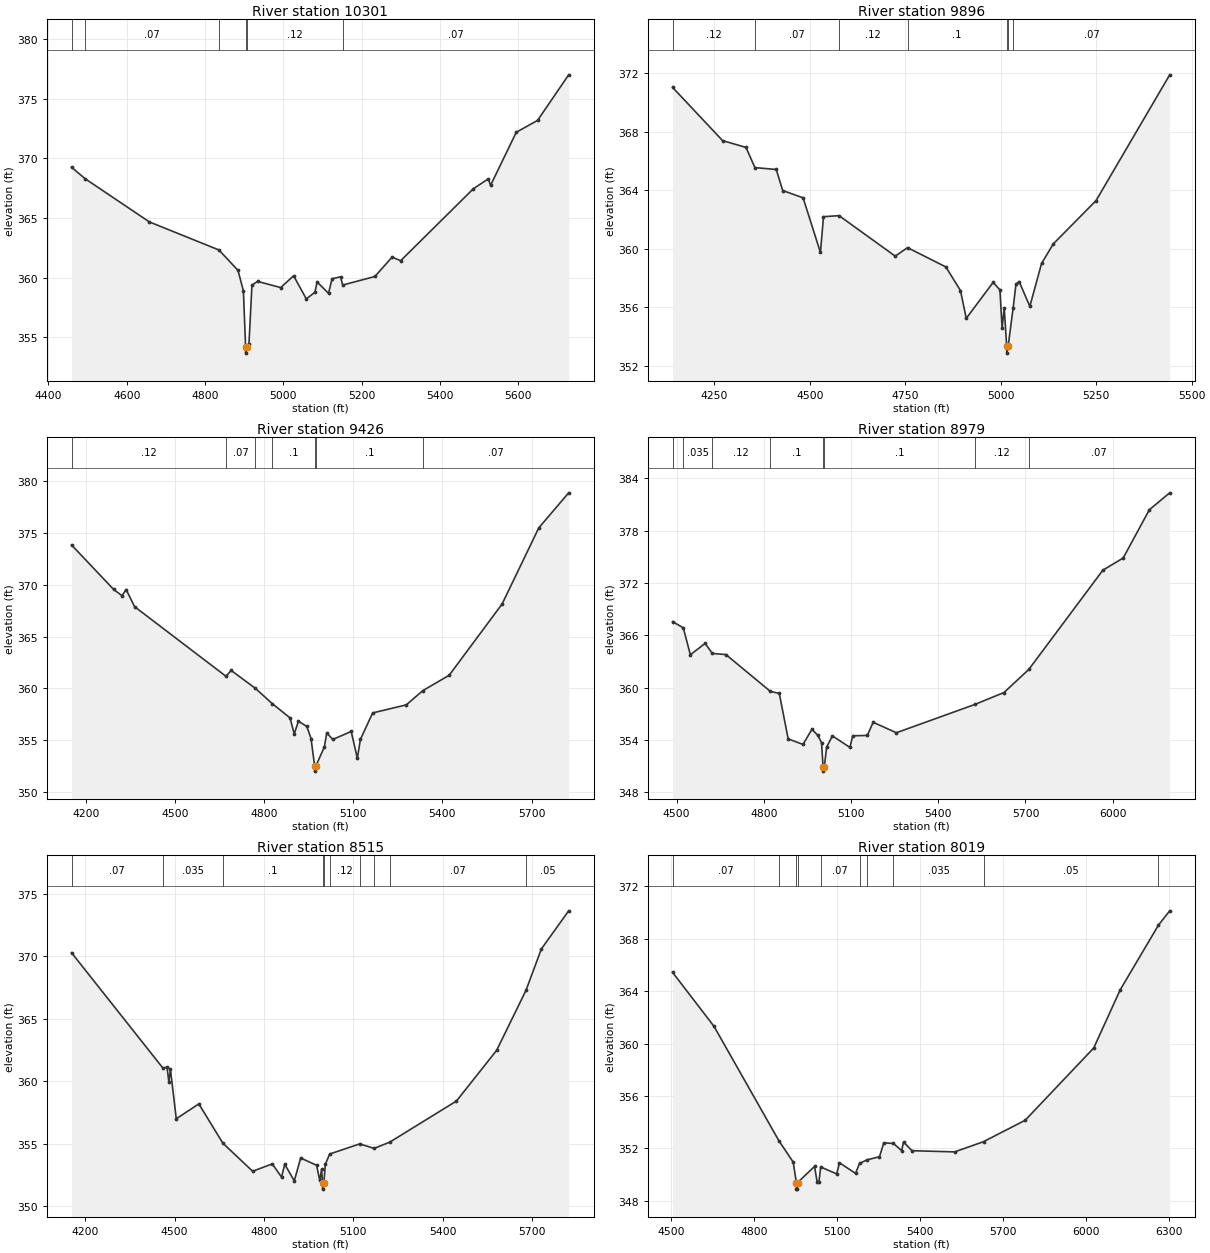
Type RM Length L Ch R = 1 ,10301   ,405,405,405
BEGIN DESCRIPTION:
BOGGY CREEK 2 17.0
END DESCRIPTION:
XS GIS Cut Line= 3
        2515675.       13806275.        2515325.       13805875.
      2514675.04     13805525.02
#Sta/Elev= 30
  4458.9  369.26  4493.6   368.3  4657.7  364.68  4835.4  362.33  4884.1  360.62
  4897.9   358.9  4903.5  354.19  4903.7  353.69  4907.5  354.19  4912.1  354.48
  4919.7  359.38  4933.9   359.7  4993.2  359.18  5026.1  360.17  5058.6  358.23
  5080.5  358.79  5086.1  359.65  5115.3   358.7  5124.3  359.92  5146.2  360.08
  5151.4  359.39  5233.8  360.11  5277.6  361.73  5299.5  361.43  5485.3  367.46
  5523.4  368.29  5529.1  367.74  5594.8  372.19  5649.1  373.18  5728.6     377
#Mann= 6 ,-1 , 0
  4458.9     .12       0  4493.6     .07       0  4835.4     .12       0
  4903.5     .05       0  4907.5     .12       0  5151.4     .07       0
Bank Sta=4903.5,4907.5
XS Rating Curve= 0 ,0
Exp/Cntr=0.3,0.1

Type RM Length L Ch R = 1 ,9896    ,470,470,470
BEGIN DESCRIPTION:
BOGGY CREEK 2 16.0
END DESCRIPTION:
XS GIS Cut Line= 3
      2516125.04     13805825.01        2515325.       13805525.
      2514924.96     13805324.98
#Sta/Elev= 30
  4140.8  371.04  4271.7   367.4  4333.1  366.93  4356.4  365.55  4412.3  365.42
  4429.2  363.98  4482.6  363.48    4528  359.74    4536  362.19  4576.8  362.26
  4723.8  359.49  4756.1  360.07  4856.4  358.75  4894.7  357.13  4909.8  355.23
  4980.1  357.69    4998  357.18  5003.6  354.57  5009.2  355.95  5015.6  353.35
  5015.9  352.85  5019.6  353.35  5032.7  355.97    5040  357.57  5048.3  357.75
  5076.3  356.05    5107  358.99  5137.8  360.33  5249.6  363.29  5442.5   371.9
#Mann= 7 ,-1 , 0
  4140.8     .12       0  4356.4     .07       0  4576.8     .12       0
  4756.1      .1       0  5015.6     .05       0  5019.6      .1       0
  5032.7     .07       0
Bank Sta=5015.6,5019.6
XS Rating Curve= 0 ,0
Exp/Cntr=0.3,0.1

Type RM Length L Ch R = 1 ,9426    ,447,447,447
BEGIN DESCRIPTION:
BOGGY CREEK 2 15.0
END DESCRIPTION:
XS GIS Cut Line= 3
      2516225.02     13805825.02        2515625.       13805225.
      2514824.98       13805025.
#Sta/Elev= 30
  4151.7  373.86  4293.2  369.57  4321.4  368.96  4335.6  369.55  4363.9   367.9
  4671.4  361.18  4689.1  361.74  4770.6  360.01  4827.6  358.53  4887.1  357.16
  4901.3  355.61  4915.4  356.84  4943.7  356.33  4957.8  355.17  4969.9  352.52
  4970.1  352.02  4974.1  352.52  5002.8  354.36  5010.6  355.71  5031.2  355.08
    5093  355.85  5113.6  353.27    5124  355.08  5165.2  357.64  5278.6  358.42
  5333.4  359.78  5422.9  361.28  5600.7  368.15  5724.4  375.51  5824.9  378.89
#Mann= 7 ,-1 , 0
  4151.7     .12       0  4671.4     .07       0  4770.6     .12       0
  4827.6      .1       0  4969.9     .05       0  4974.1      .1       0
  5333.4     .07       0
Bank Sta=4969.9,4974.1
XS Rating Curve= 0 ,0
Exp/Cntr=0.3,0.1

Type RM Length L Ch R = 1 ,8979    ,464,464,464
BEGIN DESCRIPTION:
BOGGY CREEK 2 14.0
END DESCRIPTION:
XS GIS Cut Line= 3
      2516424.96     13805024.99        2515925.       13804925.
      2514724.96       13804925.
#Sta/Elev= 30
  4486.2  367.56  4523.1  366.86  4547.4  363.77  4598.3  365.07    4623  363.92
  4669.7  363.79  4822.7  359.57  4853.3  359.33  4883.9  354.12  4934.9  353.49
  4965.5  355.23  4985.9  354.52  4998.6  353.69  5003.9  350.93  5004.2  350.43
  5008.2  350.93  5016.1  353.19  5036.1  354.47  5096.1  353.15  5106.1  354.48
  5156.1  354.52  5176.1  356.03  5256.1  354.83  5525.7  358.07  5626.1  359.44
  5711.6  362.09  5966.1  373.46  6036.1  374.86  6126.1  380.39  6196.1  382.33
#Mann= 8 ,-1 , 0
  4486.2     .07       0  4523.1    .035       0    4623     .12       0
  4822.7      .1       0  5003.9     .05       0  5008.2      .1       0
  5525.7     .12       0  5711.6     .07       0
Bank Sta=5003.9,5008.2
XS Rating Curve= 0 ,0
Exp/Cntr=0.3,0.1

Type RM Length L Ch R = 1 ,8515    ,496,496,496
BEGIN DESCRIPTION:
BOGGY CREEK 2 13.0
END DESCRIPTION:
XS GIS Cut Line= 3
      2516524.96     13804824.98        2515725.       13804525.
        2514925.       13804675.
#Sta/Elev= 30
    4154  370.28  4461.2  361.03  4474.4  361.13  4480.6  359.94  4485.9  360.97
  4505.5  356.99  4581.2  358.18  4661.8  355.04  4761.8  352.79  4827.7  353.38
  4858.8  352.32  4869.5  353.35  4901.6  352.02  4922.9  353.85  4976.3  353.27
    4987  352.06  4993.2  352.94  4996.4  351.86  4996.7  351.36  5000.8  351.86
  5005.7  353.35  5020.4  354.17  5121.1  354.98  5169.5  354.62  5221.9  355.12
  5445.8  358.41  5580.7  362.47  5679.3  367.28  5730.7  370.58  5822.3  373.63
#Mann= 10 ,-1 , 0
    4154     .07       0  4461.2    .035       0  4661.8      .1       0
  4996.4     .05       0  5000.8      .1       0  5020.4     .12       0
  5121.1     .05       0  5169.5     .12       0  5221.9     .07       0
  5679.3     .05       0
Bank Sta=4996.4,5000.8
XS Rating Curve= 0 ,0
Exp/Cntr=0.3,0.1

Type RM Length L Ch R = 1 ,8019    ,445,445,445
BEGIN DESCRIPTION:
BOGGY CREEK 2 12.0
END DESCRIPTION:
XS GIS Cut Line= 3
      2516474.98     13804474.98        2516075.       13804175.
      2514953.24     13803521.11
#Sta/Elev= 30
  4505.3  365.43  4655.3  361.31  4890.2  352.58  4941.7  350.96  4953.1   349.4
  4953.4   348.9  4957.2   348.9  4957.5   349.4  5018.9  350.63  5028.4  349.44
  5034.6  349.42  5041.1  350.59  5099.1  350.06  5109.1  350.91  5167.3   350.1
  5181.7  350.86  5209.8  351.14  5253.8  351.37  5269.5  352.43  5304.3  352.38
    5334  351.84  5340.9  352.49  5371.3  351.83  5525.9  351.74  5630.3  352.52
  5780.8  354.15  6028.8  359.66  6124.7   364.1    6263  369.03  6303.7  370.12
#Mann= 10 ,-1 , 0
  4505.3     .07       0  4890.2     .12       0  4953.1     .05       0
  4957.5     .12       0  5041.1     .07       0  5181.7    .035       0
  5209.8     .05       0  5304.3    .035       0  5630.3     .05       0
    6263     .07       0
Bank Sta=4953.1,4957.5
XS Rating Curve= 0 ,0
Exp/Cntr=0.3,0.1

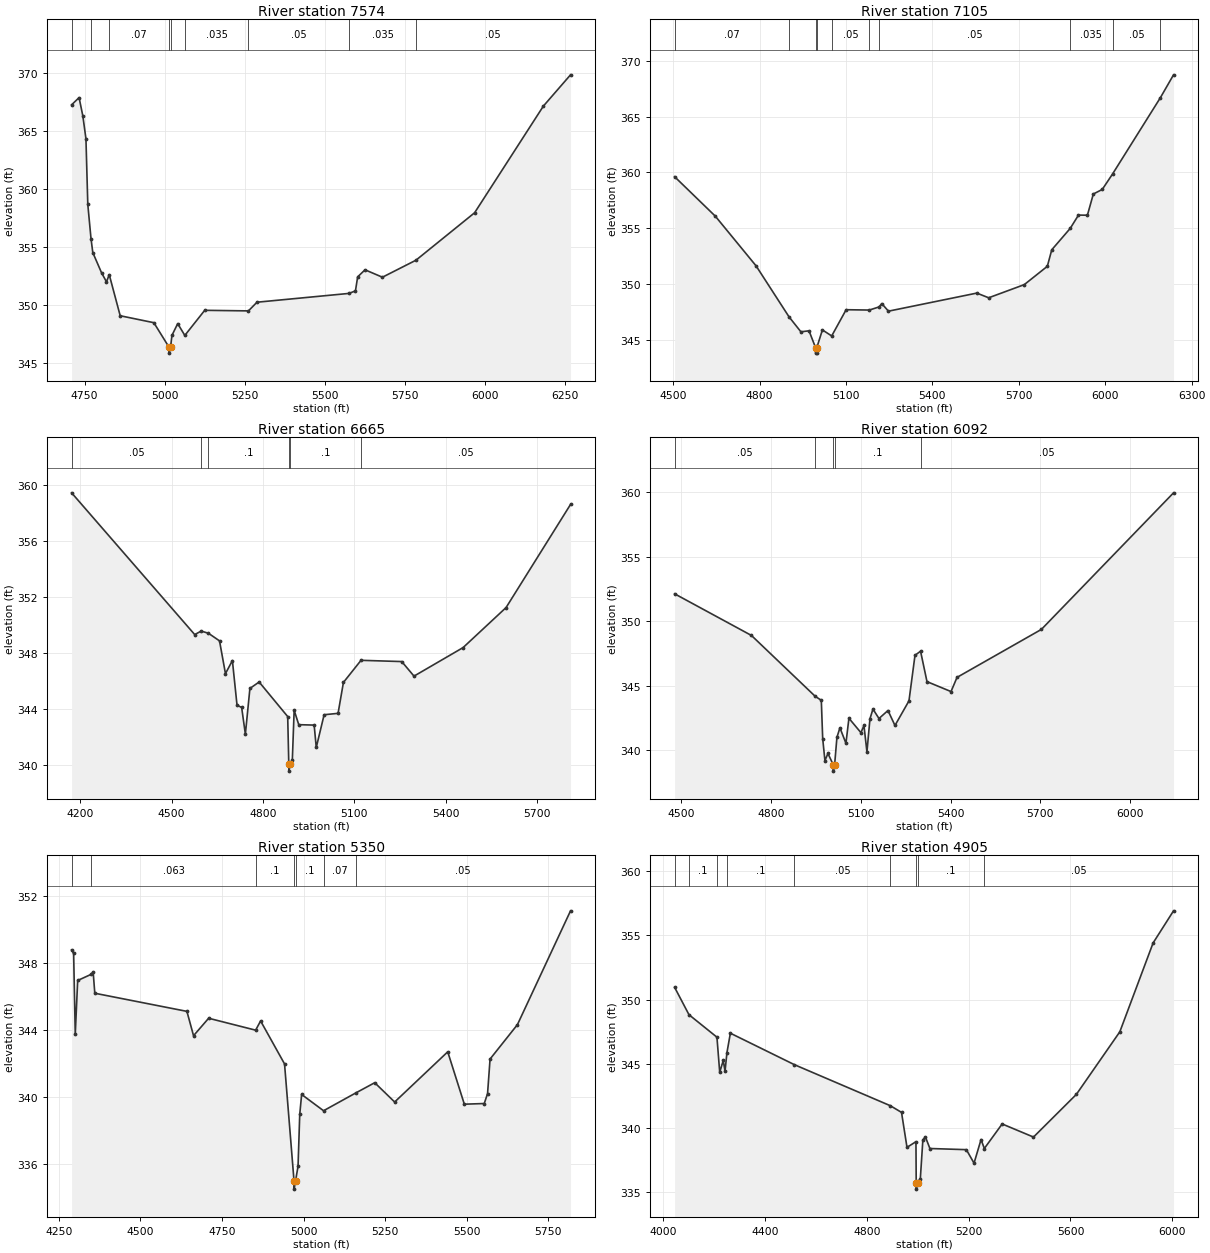
Type RM Length L Ch R = 1 ,7574    ,469,469,469
BEGIN DESCRIPTION:
BOGGY CREEK 2 11.0
END DESCRIPTION:
XS GIS Cut Line= 3
        2516325.       13804075.        2516175.       13803825.
       2514996.1     13803365.88
#Sta/Elev= 30
  4709.3  367.29  4732.6  367.91  4744.3  366.33    4754  364.36  4759.8  358.68
  4769.8  355.73  4775.4  354.52  4802.6  352.78  4818.1  351.99  4826.7  352.61
  4860.9  349.06  4965.9  348.46  5013.5  346.33  5013.8  345.83    5018  346.33
  5022.3  347.36  5040.3  348.38  5062.5  347.36  5124.6  349.53    5261  349.48
  5287.7  350.23  5574.6  350.99  5594.9  351.21  5601.8  352.42  5624.8  353.03
  5679.1  352.39  5783.7  353.86  5966.7  357.96  6181.3  367.18    6266  369.88
#Mann= 9 ,-1 , 0
  4709.3     .07       0  4769.8     .12       0  4826.7     .07       0
  5013.5     .05       0    5018     .07       0  5062.5    .035       0
    5261     .05       0  5574.6    .035       0  5783.7     .05       0
Bank Sta=5013.5,5018
XS Rating Curve= 0 ,0
Exp/Cntr=0.3,0.1

Type RM Length L Ch R = 1 ,7105    ,440,440,440
BEGIN DESCRIPTION:
BOGGY CREEK 2 10.0
END DESCRIPTION:
XS GIS Cut Line= 3
      2516624.97     13803774.97        2516275.       13803425.
      2515074.96     13803124.99
#Sta/Elev= 30
  4505.2  359.62  4646.6  356.08    4788  351.63  4902.4  347.06  4943.6  345.72
  4971.8  345.81  4994.3  344.31  4994.6  343.81  4998.6  343.81  4998.9  344.31
  5018.2  345.89  5050.5  345.35  5100.6   347.7  5181.1  347.67  5214.9  347.95
  5224.3  348.25  5247.5  347.57  5554.2  349.19  5595.4  348.77  5719.1  349.95
    5799  351.59  5814.4  353.07  5878.5  354.99  5907.2  356.18  5938.1  356.17
  5958.7  358.07  5989.7  358.48  6025.6  359.87  6191.2  366.69  6237.1  368.75
#Mann= 10 ,-1 , 0
  4505.2     .07       0  4902.4     .12       0  4994.3     .05       0
  4998.9     .12       0  5050.5     .05       0  5181.1     .12       0
  5214.9     .05       0  5878.5    .035       0  6025.6     .05       0
  6191.2    .035       0
Bank Sta=4994.3,4998.9
XS Rating Curve= 0 ,0
Exp/Cntr=0.3,0.1

Type RM Length L Ch R = 1 ,6665    ,573,573,573
BEGIN DESCRIPTION:
BOGGY CREEK 2 9.0
END DESCRIPTION:
XS GIS Cut Line= 3
      2516824.97     13803524.98        2516125.       13803075.
      2515324.96     13802974.99
#Sta/Elev= 30
  4171.9  359.46  4576.1  349.33  4597.6  349.58  4621.4  349.42  4657.6  348.88
  4677.1  346.54  4699.9  347.47  4715.1  344.28  4730.3  344.12  4742.5  342.21
  4757.4  345.48  4787.7  345.94  4881.5  343.47  4885.1  340.07  4885.5  339.57
  4889.8  340.07  4896.7  340.35  4902.7  343.92  4917.8  342.89  4968.4  342.86
  4975.3  341.26  5001.1   343.6  5046.9   343.7  5064.5  345.91  5122.3  347.49
    5256   347.4  5296.3  346.36  5457.5   348.4  5598.6  351.26  5810.3  358.63
#Mann= 6 ,-1 , 0
  4171.9     .05       0  4597.6     .07       0  4621.4      .1       0
  4885.1     .05       0  4889.8      .1       0  5122.3     .05       0
Bank Sta=4885.1,4889.8
XS Rating Curve= 0 ,0
Exp/Cntr=0.3,0.1

Type RM Length L Ch R = 1 ,6092    ,742,742,742
BEGIN DESCRIPTION:
BOGGY CREEK 2 8.0
END DESCRIPTION:
XS GIS Cut Line= 3
      2516777.24     13803013.66      2516352.13     13802759.67
       2515183.8     13802663.42
#Sta/Elev= 30
  4477.6  352.14  4734.4  348.91  4947.1   344.2  4967.9  343.88  4972.5  340.92
    4980   339.2    4990  339.76  5007.7  338.89    5008  338.39  5012.4  338.89
  5020.1  341.01  5030.1  341.75  5050.2  340.55  5060.2  342.49  5100.4  341.37
  5110.4  341.93  5120.4  339.88  5130.5  342.45  5140.5   343.2  5160.6  342.47
  5190.7  343.09  5214.1  341.93  5260.9  343.84    5281  347.37  5299.6  347.69
  5321.1  345.33  5401.4  344.56  5421.5  345.66  5703.5  349.38  6145.1  359.97
#Mann= 5 ,-1 , 0
  4477.6     .05       0  4947.1      .1       0  5007.7     .05       0
  5012.4      .1       0  5299.6     .05       0
Bank Sta=5007.7,5012.4
XS Rating Curve= 0 ,0
Exp/Cntr=0.3,0.1

Type RM Length L Ch R = 1 ,5350    ,445,445,445
BEGIN DESCRIPTION:
BOGGY CREEK 2 7.0
END DESCRIPTION:
XS GIS Cut Line= 4
      2517103.35     13802441.51      2516580.08     13802351.24
        2516525.       13802175.      2515724.99       13802025.
#Sta/Elev= 30
    4289  348.78  4295.2  348.57  4300.2  343.76  4307.6  346.96  4349.3  347.33
    4355  347.48  4360.1   346.2  4642.5  345.12  4662.8  343.67  4709.1  344.71
  4853.2     344  4868.4  344.55  4941.8  341.99  4970.8  335.03  4971.2  334.53
  4975.6  335.03  4983.2  335.89  4988.4  338.98  4994.2  340.17  5061.4   339.2
  5161.1  340.27  5218.3  340.87  5279.4  339.72  5442.1  342.71    5493  339.59
  5554.1  339.63  5564.2  340.22  5571.9  342.28  5655.8  344.33  5818.6  351.11
#Mann= 7 ,-1 , 0
    4289    .035       0  4349.3    .063       0  4853.2      .1       0
  4970.8     .05       0  4975.6      .1       0  5061.4     .07       0
  5161.1     .05       0
Bank Sta=4970.8,4975.6
XS Rating Curve= 0 ,0
Exp/Cntr=0.3,0.1

Type RM Length L Ch R = 1 ,4905    ,460,460,460
BEGIN DESCRIPTION:
BOGGY CREEK 2 6.0
END DESCRIPTION:
XS GIS Cut Line= 3
      2517275.01     13802475.01        2516575.       13801825.
      2515575.05       13801925.
#Sta/Elev= 30
  4044.7  350.96  4101.1  348.83    4211  347.08  4221.9  344.35  4235.8  345.27
  4242.8  344.43  4250.3  345.88  4263.8  347.39  4515.5  344.94  4892.1  341.75
  4936.2  341.23  4957.7  338.51  4992.9  338.95  4993.9  335.76  4994.3  335.26
  4999.3  335.76    5010  336.04  5020.1   339.1  5030.1  339.32  5047.7  338.42
  5190.9  338.33  5221.1  337.28  5248.7  339.12  5261.5  338.42  5331.6  340.33
  5454.7  339.31  5623.1  342.63  5793.9   347.5  5924.6  354.41  6004.9  356.91
#Mann= 9 ,-1 , 0
  4044.7    .035       0  4101.1      .1       0    4211    .063       0
  4250.3      .1       0  4515.5     .05       0  4892.1      .1       0
  4993.9     .05       0  4999.3      .1       0  5261.5     .05       0
Bank Sta=4993.9,4999.3
XS Rating Curve= 0 ,0
Exp/Cntr=0.3,0.1

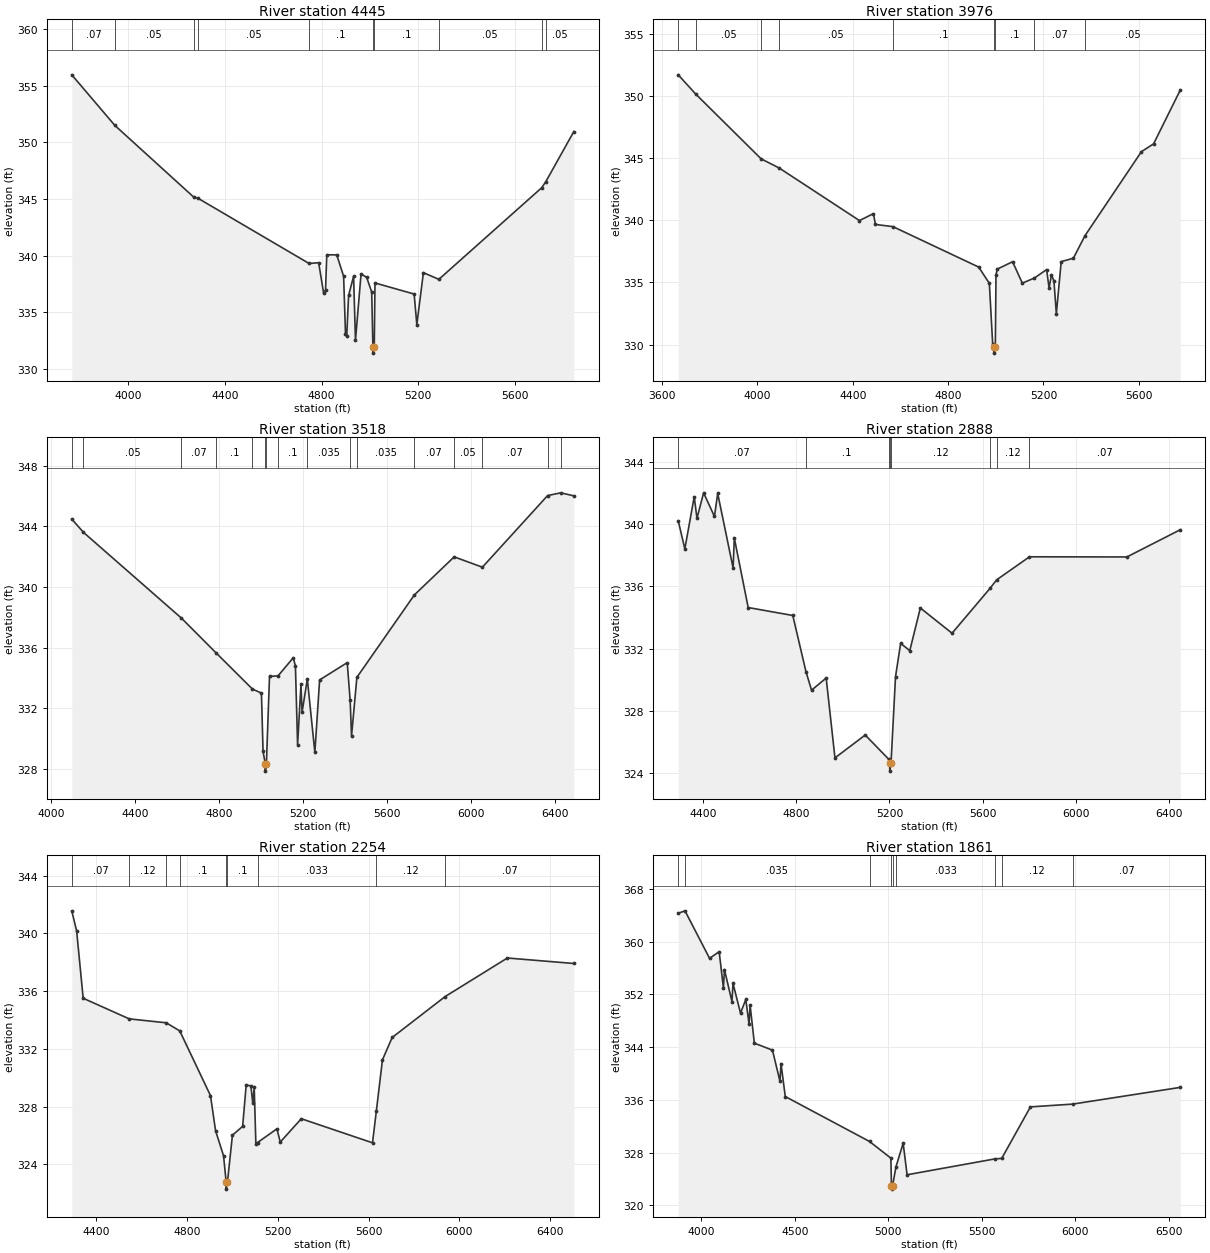
Type RM Length L Ch R = 1 ,4445    ,469,469,469
BEGIN DESCRIPTION:
BOGGY CREEK 2 5.0
END DESCRIPTION:
XS GIS Cut Line= 3
      2517725.02     13801775.01        2516525.       13801475.
      2515725.01       13801725.
#Sta/Elev= 30
  3767.8  355.97  3945.9   351.5  4271.6  345.17  4290.6  345.05  4748.7   339.3
  4788.3  339.37  4808.9  336.65  4816.6  336.95  4821.8  340.07    4863  340.06
  4891.4  338.17  4899.1  333.07  4904.3  332.93    4912  336.49  4932.6  338.17
  4940.3  332.51  4963.5  338.38  4986.7  338.07  5007.4  336.78  5012.5  331.88
  5012.9  331.38    5018  331.88    5021  337.58  5182.9   336.6  5193.9   333.9
  5221.1  338.49    5285   337.9  5709.8  345.99  5726.8  346.52  5842.9  350.96
#Mann= 10 ,-1 , 0
  3767.8     .07       0  3945.9     .05       0  4271.6     .07       0
  4290.6     .05       0  4748.7      .1       0  5012.5     .05       0
    5018      .1       0    5285     .05       0  5709.8    .035       0
  5726.8     .05       0
Bank Sta=5012.5,5018
XS Rating Curve= 0 ,0
Exp/Cntr=0.3,0.1

Type RM Length L Ch R = 1 ,3976    ,458,458,458
BEGIN DESCRIPTION:
BOGGY CREEK 2 4.0
END DESCRIPTION:
XS GIS Cut Line= 3
      2517574.99       13801675.        2516375.       13801075.
      2515624.98       13801225.
#Sta/Elev= 30
  3667.7  351.69  3740.2  350.16  4015.7  344.93  4091.1   344.2    4428  339.97
  4486.7  340.53    4495  339.66  4568.8  339.48  4928.3  336.23    4973  334.92
    4987  330.04  4992.6  329.81  4993.1  329.31  4998.1  329.81  5000.9   335.6
  5006.5  336.07  5070.5  336.66  5111.3  334.94  5162.1  335.35  5213.3  336.03
  5223.5  334.56  5233.7   335.6  5243.9  335.12  5254.1  332.49  5274.5  336.67
  5325.5  336.94  5374.4  338.76    5611  345.51    5662  346.14  5774.2  350.47
#Mann= 9 ,-1 , 0
  3667.7     .07       0  3740.2     .05       0  4015.7     .07       0
  4091.1     .05       0  4568.8      .1       0  4992.6     .05       0
  4998.1      .1       0  5162.1     .07       0  5374.4     .05       0
Bank Sta=4992.6,4998.1
XS Rating Curve= 0 ,0
Exp/Cntr=0.3,0.1

Type RM Length L Ch R = 1 ,3518    ,630,630,630
BEGIN DESCRIPTION:
BOGGY CREEK 2 3.0
END DESCRIPTION:
XS GIS Cut Line= 3
        2517375.       13801225.        2516625.       13800725.
      2515175.03     13801074.99
#Sta/Elev= 30
  4098.8  344.48  4154.2  343.61  4621.7  337.95  4787.5  335.65  4959.8  333.28
  5002.8  333.01  5010.5  329.17  5020.9  328.37  5021.3  327.87  5026.5  328.37
  5041.3  334.11  5082.1  334.15  5154.5  335.34  5164.8   334.8  5175.1   329.6
  5191.2  333.59  5196.4  331.74  5221.5  333.94  5257.4   329.1  5280.1  333.88
  5411.7  335.02  5425.6  332.55  5432.2  330.18  5457.7  334.05  5731.6  339.48
  5921.4  341.99  6055.9  341.31  6366.8  346.03  6429.2  346.21  6491.8  346.01
#Mann= 16 ,-1 , 0
  4098.8     .07       0  4154.2     .05       0  4621.7     .07       0
  4787.5      .1       0  4959.8    .035       0  5020.9    .035       0
  5026.5    .035       0  5082.1      .1       0  5221.5    .035       0
  5425.6      .1       0  5457.7    .035       0  5731.6     .07       0
  5921.4     .05       0  6055.9     .07       0  6366.8     .05       0
  6429.2     .07       0
Bank Sta=5020.9,5026.5
XS Rating Curve= 0 ,0
Exp/Cntr=0.3,0.1

Type RM Length L Ch R = 1 ,2888    ,634,634,634
BEGIN DESCRIPTION:
BOGGY CREEK 2 2.0
END DESCRIPTION:
XS GIS Cut Line= 5
      2517523.17     13800150.32      2516892.15     13800230.13
      2516698.38     13800228.88      2515881.69     13800618.38
      2515491.23     13800778.61
#Sta/Elev= 30
  4292.8  340.21  4321.2  338.41  4361.5  341.76  4373.3  340.37  4401.8  342.01
  4448.4  340.49  4462.3  341.97  4528.6  337.17  4533.6  339.11  4593.3  334.64
  4784.9  334.13  4841.3  330.53  4865.5  329.33  4928.3  330.11    4966  324.98
    5096  326.45    5196  324.91    5201  324.63  5201.5  324.13  5206.8  324.63
  5226.1  330.19  5248.2  332.34  5287.4  331.87  5332.8  334.61    5469  332.99
  5632.5  335.88  5660.5  336.42  5801.6   337.9    6220  337.89  6449.5  339.64
#Mann= 8 ,-1 , 0
  4292.8     .07       0  4841.3      .1       0    5196     .12       0
    5201     .05       0  5206.8     .12       0  5632.5     .07       0
  5660.5     .12       0  5801.6     .07       0
Bank Sta=5201,5206.8
XS Rating Curve= 0 ,0
Exp/Cntr=0.3,0.1

Type RM Length L Ch R = 1 ,2254    ,393,393,393
BEGIN DESCRIPTION:
BOGGY CREEK 2 1.0
END DESCRIPTION:
XS GIS Cut Line= 3
      2517524.98     13800124.98        2516975.       13799675.
        2515775.       13800575.
#Sta/Elev= 30
  4293.5  341.57    4315  340.17  4343.7  335.51  4546.7  334.08  4709.3  333.81
  4768.9  333.25  4904.3  328.76  4926.6  326.33  4961.8  324.59  4973.2  322.78
  4973.7  322.28    4979  322.78  5000.9  326.02  5045.8  326.63  5061.4  329.49
  5082.2  329.44  5090.6  328.22  5096.8  329.33  5104.1  325.41  5111.5  325.51
  5196.8  326.46  5211.4  325.54  5304.1  327.16  5617.6  325.49  5634.5  327.69
  5661.4  331.24  5704.1  332.79  5937.7  335.63  6211.4   338.3  6504.1  337.92
#Mann= 9 ,-1 , 0
  4293.5     .07       0  4546.7     .12       0  4709.3     .07       0
  4768.9      .1       0  4973.2     .05       0    4979      .1       0
  5111.5    .033       0  5634.5     .12       0  5937.7     .07       0
Bank Sta=4973.2,4979
XS Rating Curve= 0 ,0
Exp/Cntr=0.3,0.1

Type RM Length L Ch R = 1 ,1861    ,453,453,453
BEGIN DESCRIPTION:
X18322
END DESCRIPTION:
XS GIS Cut Line= 4
      2517918.89     13799752.43      2517024.93     13799334.89
      2516387.89      13799768.5       2515809.9     13800496.35
#Sta/Elev= 30
  3876.5  364.32  3912.6  364.69  4044.2  357.48  4095.5  358.49  4118.3     353
  4123.8  355.78    4164  350.91  4169.5  353.68  4209.7  349.17  4238.1  351.24
  4255.4  347.49    4261  350.39  4283.8  344.61  4380.7  343.55  4420.9  338.82
  4426.4  341.51  4449.3  336.51  4900.3  329.69  5014.4  327.16  5017.4  322.96
  5017.9  322.46  5023.4  322.96  5041.8  325.87  5080.1  329.42  5101.1  324.64
  5571.7  327.05  5607.4  327.12  5761.2  334.94  5986.5  335.36  6563.2   337.9
#Mann= 9 ,-1 , 0
  3876.5    .063       0  3912.6    .035       0  4900.3      .1       0
  5017.4     .05       0  5023.4      .1       0  5041.8    .033       0
  5571.7     .07       0  5607.4     .12       0  5986.5     .07       0
Bank Sta=5017.4,5023.4
XS Rating Curve= 0 ,0
Exp/Cntr=0.3,0.1

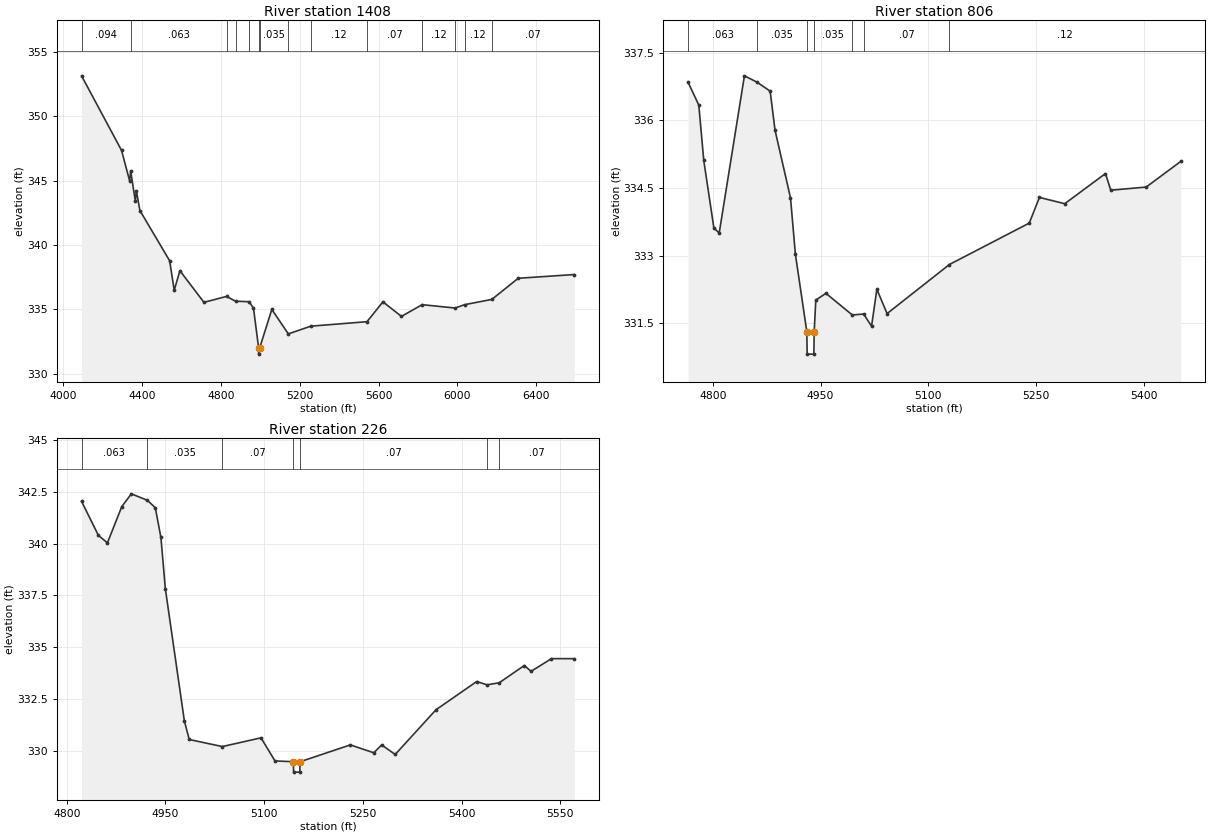
Type RM Length L Ch R = 1 ,1408    ,602,602,602
BEGIN DESCRIPTION:
X18321
END DESCRIPTION:
XS GIS Cut Line= 4
      2517469.27     13799340.26      2516703.73     13799002.99
      2516302.24     13799511.55      2515826.05     13800410.43
#Sta/Elev= 30
  4091.8  353.14  4294.8  347.35  4335.9  344.98  4341.1  345.77  4364.7  343.42
  4370.2  344.21  4388.1  342.68    4539  338.78  4562.3  336.49  4591.1  338.01
  4713.2  335.55  4827.7  336.01  4873.7  335.64  4942.5   335.6  4964.7   335.1
  4990.6  332.03  4991.1  331.53  4996.6  332.03  5057.7     335  5141.6   333.1
  5255.5   333.7  5541.1  334.05  5621.8  335.59    5716  334.46  5820.8  335.37
    5988  335.11  6036.7  335.37    6175  335.78  6308.7  337.42  6593.5  337.71
#Mann= 14 ,-1 , 0
  4091.8    .094       0  4341.1    .063       0  4827.7    .035       0
  4873.7    .063       0  4942.5    .035       0  4990.6    .035       0
  4996.6    .035       0  5141.6     .07       0  5255.5     .12       0
  5541.1     .07       0  5820.8     .12       0    5988     .07       0
  6036.7     .12       0    6175     .07       0
Bank Sta=4990.6,4996.6
XS Rating Curve= 0 ,0
Exp/Cntr=0.3,0.1

Type RM Length L Ch R = 1 ,806     ,580,580,580
BEGIN DESCRIPTION:
X18320
END DESCRIPTION:
XS GIS Cut Line= 2
      2516339.72     13798708.56      2515836.48     13799174.33
#Sta/Elev= 30
  4765.5  336.85  4780.5  336.34  4787.4  335.11  4801.5  333.61  4808.9   333.5
    4844  336.99  4861.4  336.85  4879.8  336.65  4886.6  335.78  4908.1  334.28
  4914.9  333.03  4930.8  331.31  4931.3  330.81  4940.6  330.81  4941.1  331.31
  4943.3  332.01  4957.4  332.16  4994.1  331.68  5009.9   331.7  5020.9  331.43
  5028.3  332.25  5042.5  331.71  5129.2   332.8  5240.4  333.72  5254.5  334.29
  5289.7  334.15  5346.4  334.82  5353.8  334.45  5403.1  334.52  5451.2  335.09
#Mann= 7 ,-1 , 0
  4765.5    .063       0  4861.4    .035       0  4930.8     .05       0
  4941.1    .035       0  4994.1     .12       0  5009.9     .07       0
  5129.2     .12       0
Bank Sta=4930.8,4941.1
XS Rating Curve= 0 ,0
Exp/Cntr=0.3,0.1

Type RM Length L Ch R = 1 ,226     ,0,0,0
BEGIN DESCRIPTION:
X18319
END DESCRIPTION:
XS GIS Cut Line= 3
      2515799.03     13798403.45      2515627.74      13798671.1
       2515734.8     13799088.62
#Sta/Elev= 30
  4822.5  342.03  4848.1  340.39  4861.8  340.03  4883.7  341.78  4898.2  342.39
  4922.4  342.08  4934.6  341.72  4943.1  340.29  4949.8  337.83  4978.7  331.47
  4986.1  330.57  5036.4  330.23  5095.2  330.65  5116.4  329.54  5144.3   329.5
  5144.8     329  5154.1     329  5154.6   329.5    5231  330.31  5266.6  329.93
  5278.5  330.31  5299.1  329.85  5361.1     332    5423  333.36  5438.7   333.2
  5457.2   333.3  5495.3  334.13  5505.6  333.85  5536.6  334.46  5571.3  334.46
#Mann= 7 ,-1 , 0
  4822.5    .063       0  4922.4    .035       0  5036.4     .07       0
  5144.3    .035       0  5154.6     .07       0  5438.7     .12       0
  5457.2     .07       0
Bank Sta=5144.3,5154.6
XS Rating Curve= 0 ,0
Exp/Cntr=0.3,0.1

Chan Stop Cuts=-1
Use User Specified Reach Order=0
Composite Channel Slope=5