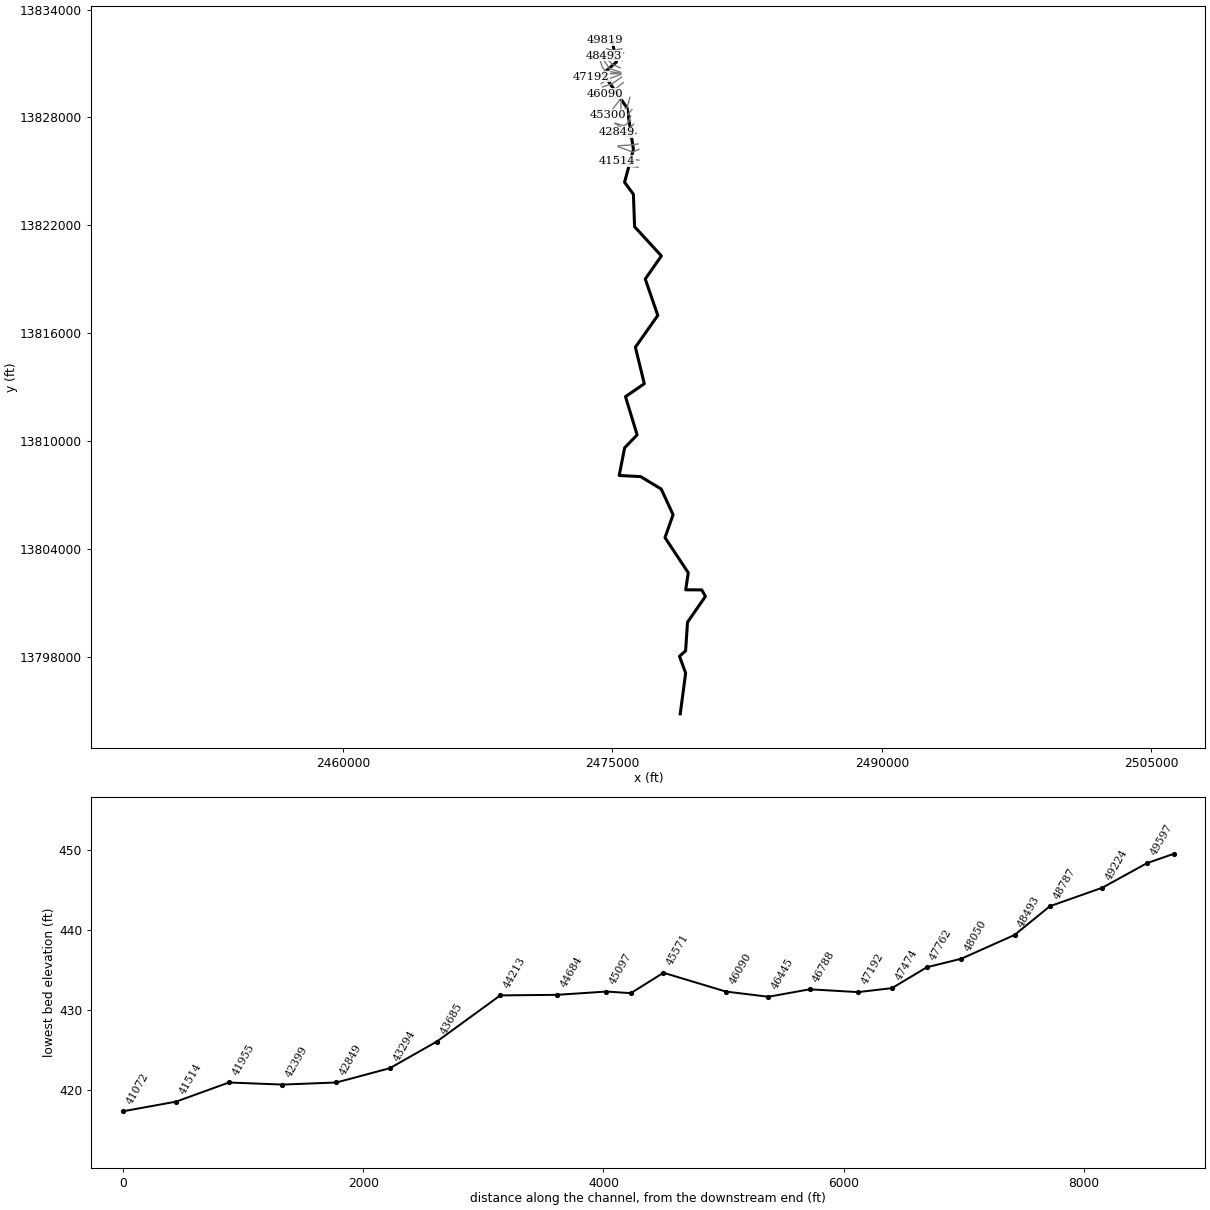
--- BUCK BRANCH.prj (project) ---

Proj Title=BUCK BRANCH Base Level Engineering
Current Plan=p01
Default Exp/Contr=0.3,0.1
English Units
Geom File=g01
Flow File=f01
Plan File=p01
Y Axis Title=Elevation
X Axis Title(PF)=Main Channel Distance
X Axis Title(XS)=Station
BEGIN DESCRIPTION:
BUCK BRANCH
END DESCRIPTION:
DSS Export Rating Curves= 0
DSS Export Rating Curve Sorted= 0
DSS Export Volume Flow Curves= 0
DXF OffsetX= 0
DXF OffsetY= 0
DXF ScaleX= 1
DXF ScaleY= 10

--- BUCK BRANCH.p01 (plan) ---

Plan Title=Multiple Run
Program Version=4.10
Short Identifier=Multiple
Geom File=g01
Flow File=f01
Subcritical Flow
K Sum by GR= 0
Std Step Tol= 0.01
Critical Tol= 0.01
Num of Std Step Trials= 20
Max Error Tol= 0.3
Flow Tol Ratio= 0.001
Split Flow NTrial= 30
Split Flow Tol= 0.02
Split Flow Ratio= 0.02
Log Output Level= 0
Friction Slope Method= 1
Unsteady Friction Slope Method= 2
Unsteady Bridges Friction Slope Method= 1
Parabolic Critical Depth
Global Vel Dist= 1 , 1 , 1
Global Log Level= 0
CheckData=True
Encroach Param=-1 ,0,0, 0
BEGIN DESCRIPTION:
Multiple Run
END DESCRIPTION:
Computation Interval=1HOUR
Output Interval=1HOUR
Run HTab= 0
Run UNet= 0
Run PostProcess= 0
Run WQNet= 0
UNET Theta= 1
UNET Theta Warmup= 1
UNET ZTol= 0.02
UNET ZSATol= 0.05
UNET MxIter= 20
UNET MaxInSteps= 0
UNET DtIC= 0
UNET DtMin= 0
UNET MaxCRTS= 20
UNET WFStab= 2
UNET SFStab= 1
UNET WFX= 1
UNET SFX= 1
UNET DSS MLevel= 4
UNET DZMax Abort= 100
UNET Convert EG Bridges= 0
UNET Use Existing IB Tables=-1
UNET Froude Reduction=False
UNET Froude Limit= 1
UNET Froude Power= 10
UNET Time Slicing=0,0, 5
UNET Junction Losses=0
Instantaneous Interval=1HOUR
Write IC File= 0
Write IC File at Sim End=0
Echo Input=False
Echo Parameters=False
Echo Output=False
Write Detailed= 0
WQ AD Non Conservative
WQ ULTIMATE=-1
WQ Max Comp Step=1HOUR
WQ Output Interval=15MIN
WQ Output Selected Increments= 0
WQ Output face flow=0
WQ Output face velocity=0
WQ Output face area=0
WQ Output face dispersion=0
WQ Output cell volume=0
WQ Output cell surface area=0
WQ Output cell continuity=0
WQ Output cumulative cell continuity=0
WQ Output face conc=0
WQ Output face dconc_dx=0
WQ Output face courant=0
WQ Output face peclet=0
WQ Output face adv mass=0
WQ Output face disp mass=0
WQ Output cell mass=0
WQ Output cell source sink temp=0
WQ Output cell source sink nsm=0
WQ Output MaxMinRange=-1
WQ Daily Max Min Mean=-1
WQ Daily Range=0
WQ Daily Time=0
WQ Create Restart=0
WQ Fixed Restart=0
WQ System Summary=0
WQ Use Fixed Temperature=0
Sorting and Armoring Iterations= 10
XS Update Threshold= 0.02
Hydraulics Update Threshold= 0.02
Energy Slope Method= 1
Volume Change Method= 0
XS Weighting Method= 0
Number of US Weighted Cross Sections= 1
Number of DS Weighted Cross Sections= 1
Upstream XS Weight=0.25
Main XS Weight=0.5
Downstream XS Weight=0.25
Number of DS XS's Weighted with US Boundary= 1
Upstream Boundary Weight= 1
Weight of XSs Associated with US Boundary= 0
Number of US XS's Weighted with DS Boundary= 1
Downstream Boundary Weight= 0.5
Weight of XSs Associated with DS Boundary= 0.5
Sediment Output Level= 4
Mass or Volume Output= 0
Output Increment Type= 1
Profile and TS Output Increment= 10
XS Output Flag= 0
XS Output Increment= 10
Disregard all LS=0
Disregard all Conn=0
Disregard all Breaches=0
Disregard all Pumps=0

--- BUCK BRANCH.f01 (steady flow) ---

Flow Title=Multiple
Number of Profiles=7
Profile Names=10-year,25-year,50-year,1pct_min,100-year,1pct_plu,500-year
River Rch & RM= BUCK BRANCH,Reach-1,49819
     770    1246    1678    1095    2184    4358    3660
River Rch & RM= BUCK BRANCH,Reach-1,47192
    1056    1739    2368    1559    3110    6206    5318
River Rch & RM= BUCK BRANCH,Reach-1,43294
    1427    2378    3264    2165    4320    8619    7494
River Rch & RM= BUCK BRANCH,Reach-1,41072
    1497    2501    3439    2283    4556    9090    7922
River Rch & RM= BUCK BRANCH,Reach-1,38350
    1735    2920    4033    2689    5365   10705    9410
River Rch & RM= BUCK BRANCH,Reach-1,37473
    2595    4406    6124    4102    8185   16332   14488
River Rch & RM= BUCK BRANCH,Reach-1,31618
    2702    4585    6368    4261    8502   16964   15018
River Rch & RM= BUCK BRANCH,Reach-1,28050
    2752    4678    6505    4356    8692   17342   15383
River Rch & RM= BUCK BRANCH,Reach-1,20414
    3728    6405    8971    6047   12064   24072   21628
River Rch & RM= BUCK BRANCH,Reach-1,16073
    4025    6912    9681    6524   13017   25973   23319
River Rch & RM= BUCK BRANCH,Reach-1,12195
    3887    6679    9356    6306   12581   25103   22551
River Rch & RM= BUCK BRANCH,Reach-1,9417
    3933    6743    9431    6345   12660   25260   22612
River Rch & RM= BUCK BRANCH,Reach-1,2257
    3992    6842    9568    6435   12840   25619   22920
Boundary for River Rch & Prof#=BUCK BRANCH,Reach-1,1
Up Type=0
Dn Type=3
Dn Slope=0.005
Boundary for River Rch & Prof#=BUCK BRANCH,Reach-1,2
Up Type=0
Dn Type=3
Dn Slope=0.005
Boundary for River Rch & Prof#=BUCK BRANCH,Reach-1,3
Up Type=0
Dn Type=3
Dn Slope=0.005
Boundary for River Rch & Prof#=BUCK BRANCH,Reach-1,4
Up Type=0
Dn Type=3
Dn Slope=0.005
Boundary for River Rch & Prof#=BUCK BRANCH,Reach-1,5
Up Type=0
Dn Type=3
Dn Slope=0.005
Boundary for River Rch & Prof#=BUCK BRANCH,Reach-1,6
Up Type=0
Dn Type=3
Dn Slope=0.005
Boundary for River Rch & Prof#=BUCK BRANCH,Reach-1,7
Up Type=0
Dn Type=3
Dn Slope=0.005

--- BUCK BRANCH.g01 (geometry) ---

Geom Title=Existing Conditions
Program Version=4.10

River Reach=BUCK BRANCH     ,Reach-1
Reach XY= 30
        2474975.       13832325.      2475222.77      13831080.9
      2474475.36     13830440.16      2475816.93     13828528.31
      2476167.44       13826225.      2475674.91     13824394.88
      2476167.52     13823728.62      2476233.05     13821921.71
      2477725.42       13820300.      2476826.22      13819014.5
      2477525.05     13816990.34      2476277.05     13815219.14
      2476774.62     13813190.16      2475726.96     13812469.11
      2476374.94     13810345.03      2475678.53     13809623.55
      2475376.19      13808085.5      2476568.97     13808023.38
       2477717.2     13807331.21      2478374.93     13805904.97
      2477926.96     13804630.89      2479221.39      13802673.5
      2479078.54     13801726.46      2479969.14     13801722.93
      2480174.91     13801359.61      2479178.45     13799923.75
      2479072.94     13798330.86      2478732.98     13798028.35
      2479075.43     13797095.18        2478775.       13794825.

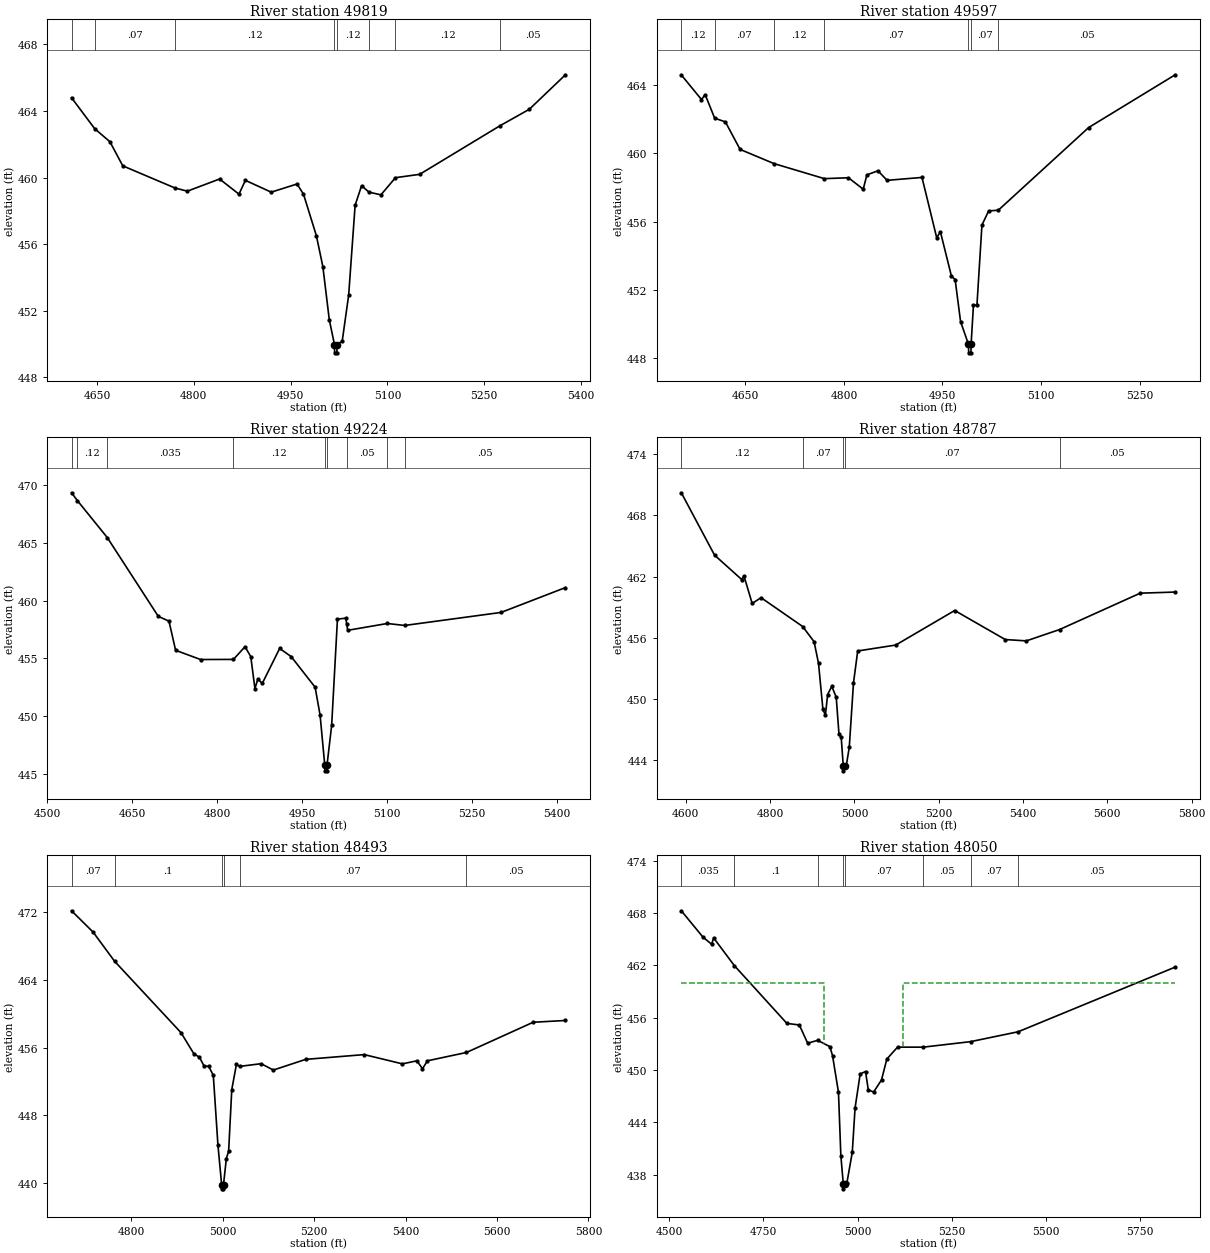
Type RM Length L Ch R = 1 ,49819   ,222,222,222
BEGIN DESCRIPTION:
X18351
END DESCRIPTION:
XS GIS Cut Line= 2
      2475364.39     13832294.91       2474599.1     13832298.98
#Sta/Elev= 30
  4610.6  464.79  4646.5  462.93    4670  462.15    4690   460.7  4770.9  459.37
    4790  459.18    4840  459.91    4870     459    4880  459.83    4920  459.12
    4960  459.61    4970     459    4990   456.5    5000  454.65    5010  451.45
    5018  449.97  5018.2  449.47  5021.7  449.47    5022  449.97    5030  450.17
    5040  452.94    5050  458.33    5060  459.51  5071.5  459.12    5090  458.96
  5112.5  459.99    5150  460.19  5274.1   463.1    5320   464.1  5375.9  466.17
#Mann= 8 ,-1 , 0
  4610.6     .12       0  4646.5     .07       0  4770.9     .12       0
    5018     .05       0    5022     .12       0  5071.5     .05       0
  5112.5     .12       0  5274.1     .05       0
Bank Sta=5018,5022
XS Rating Curve= 0 ,0
Exp/Cntr=0.3,0.1

Type RM Length L Ch R = 1 ,49597   ,373,373,373
BEGIN DESCRIPTION:
BUCK BRANCH 89.0
END DESCRIPTION:
XS GIS Cut Line= 3
      2475374.99       13832275.        2474975.       13832075.
      2474675.04     13832124.99
#Sta/Elev= 30
  4552.7  464.59  4583.4  463.15    4589  463.44  4603.4  462.06  4619.8  461.84
  4642.1  460.23  4693.7   459.4  4770.2  458.52    4807  458.57  4829.4   457.9
    4835  458.74  4851.8  458.98  4865.7  458.42  4918.8  458.59  4941.2  455.06
  4946.8  455.41  4963.6  452.81  4969.2  452.61  4977.5  450.15  4989.5  448.82
  4989.8  448.32  4993.3  448.32  4993.5  448.82  4997.1  451.11  5002.4  451.11
    5010   455.8  5020.2  456.63  5034.9  456.67  5172.3  461.51    5304   464.6
#Mann= 7 ,-1 , 0
  4552.7     .12       0  4603.4     .07       0  4693.7     .12       0
  4770.2     .07       0  4989.5     .05       0  4993.5     .07       0
  5034.9     .05       0
Bank Sta=4989.5,4993.5
XS Rating Curve= 0 ,0
Exp/Cntr=0.3,0.1

Type RM Length L Ch R = 1 ,49224   ,437,437,437
BEGIN DESCRIPTION:
BUCK BRANCH 88.0
END DESCRIPTION:
XS GIS Cut Line= 3
      2475525.01       13831825.      2475050.59     13831728.47
      2474675.04     13831824.99
#Sta/Elev= 30
  4542.6  469.33  4552.8  468.66  4605.7  465.45  4695.7  458.63  4714.6  458.21
  4726.3  455.69  4770.3  454.89  4828.4   454.9  4848.8     456    4859  455.14
  4866.3  452.38  4871.4  453.18  4879.4  452.83    4910  455.85  4930.4  455.14
  4972.6  452.49  4981.4  450.06  4989.6  445.75  4989.9  445.25  4993.4  445.25
  4993.6  445.75  5001.8  449.19    5012  458.39  5026.7  458.47  5028.4  457.95
  5030.1  457.42    5100  458.01  5130.8  457.84    5301  458.97  5414.5  461.12
#Mann= 9 ,-1 , 0
  4542.6    .035       0  4552.8     .12       0  4605.7    .035       0
  4828.4     .12       0  4989.6     .05       0  4993.6     .12       0
  5028.4     .05       0    5100     .07       0  5130.8     .05       0
Bank Sta=4989.6,4993.6
XS Rating Curve= 0 ,0
Exp/Cntr=0.3,0.1

Type RM Length L Ch R = 1 ,48787   ,294,294,294
BEGIN DESCRIPTION:
X18352
END DESCRIPTION:
XS GIS Cut Line= 3
      2475625.16     13831593.98      2475254.35     13831475.81
      2474471.91     13831492.11
#Sta/Elev= 30
  4589.2  470.22  4668.1   464.1  4732.5  461.71  4737.8  462.07  4757.3  459.36
  4778.3  459.93  4877.1   457.1  4904.2  455.61  4914.7  453.49  4925.2  448.96
  4931.1   448.4  4936.3  450.42  4946.2  451.23  4956.7  450.17  4963.3  446.52
  4968.5  446.26  4973.4  443.44  4973.6  442.94  4977.5  443.44  4980.6  443.44
  4987.7  445.26  4997.7  451.57  5007.7   454.7  5097.8  455.28  5237.8  458.67
  5357.8  455.82  5407.8  455.69  5486.5   456.8  5677.9  460.37    5761  460.48
#Mann= 5 ,-1 , 0
  4589.2     .12       0  4877.1     .07       0  4973.4     .05       0
  4977.5     .07       0  5486.5     .05       0
Bank Sta=4973.4,4977.5
XS Rating Curve= 0 ,0
Exp/Cntr=0.3,0.1

Type RM Length L Ch R = 1 ,48493   ,443,443,443
BEGIN DESCRIPTION:
X18353
END DESCRIPTION:
XS GIS Cut Line= 3
      2475551.86     13831162.02      2474948.71      13831247.6
      2474520.79     13831443.22
#Sta/Elev= 30
  4669.9  472.11  4717.2  469.59  4763.9  466.17  4909.1  457.76  4937.3  455.27
  4949.5  454.86  4959.6  453.82  4969.7  453.79  4979.8  452.73  4989.9  444.53
    4998  439.86  4998.2  439.36  5001.8  439.36  5002.1  439.86  5008.3  442.93
  5013.3   443.8  5020.2  451.06  5030.3  454.01  5037.2  453.78  5084.3   454.1
  5111.1  453.35  5181.8  454.61  5309.8  455.17  5393.1  454.08  5424.9  454.44
  5437.1   453.5  5447.9  454.44  5533.2  455.42    5679  458.98  5749.6  459.19
#Mann= 6 ,-1 , 0
  4669.9     .07       0  4763.9      .1       0    4998     .05       0
  5002.1      .1       0  5037.2     .07       0  5533.2     .05       0
Bank Sta=4998,5002.1
XS Rating Curve= 0 ,0
Exp/Cntr=0.3,0.1

Type RM Length L Ch R = 1 ,48050   ,288,288,288
BEGIN DESCRIPTION:
X18354
END DESCRIPTION:
XS GIS Cut Line= 3
      2475429.58      13830754.5      2475034.29     13830937.89
      2474386.33      13831528.8
#Sta/Elev= 30
  4531.6  468.25  4589.2  465.23  4612.1  464.42  4617.6  465.14  4672.3  461.98
  4812.2  455.35  4845.3  455.17  4867.4  453.08  4893.9  453.41  4926.4  452.69
  4933.5  451.66  4949.3  447.46  4955.6  440.21  4962.2   436.9  4962.4   436.4
  4966.3   436.9  4971.8  437.11    4986  440.59  4993.4  445.67    5007  449.56
  5021.2  449.84  5028.6  447.73  5042.8  447.49  5063.7  448.88  5077.9  451.27
  5106.3  452.63  5174.6  452.63  5300.5  453.26  5426.8  454.39  5844.3   461.8
#Mann= 8 ,-1 , 0
  4531.6    .035       0  4672.3      .1       0  4893.9     .07       0
  4962.2     .05       0  4966.3     .07       0  5174.6     .05       0
  5300.5     .07       0  5426.8     .05       0
#XS Ineff= 2 , 0
       0    4911     460    5120       0     460
Permanent Ineff=
       F       F
Bank Sta=4962.2,4966.3
XS Rating Curve= 0 ,0
Exp/Cntr=0.3,0.1

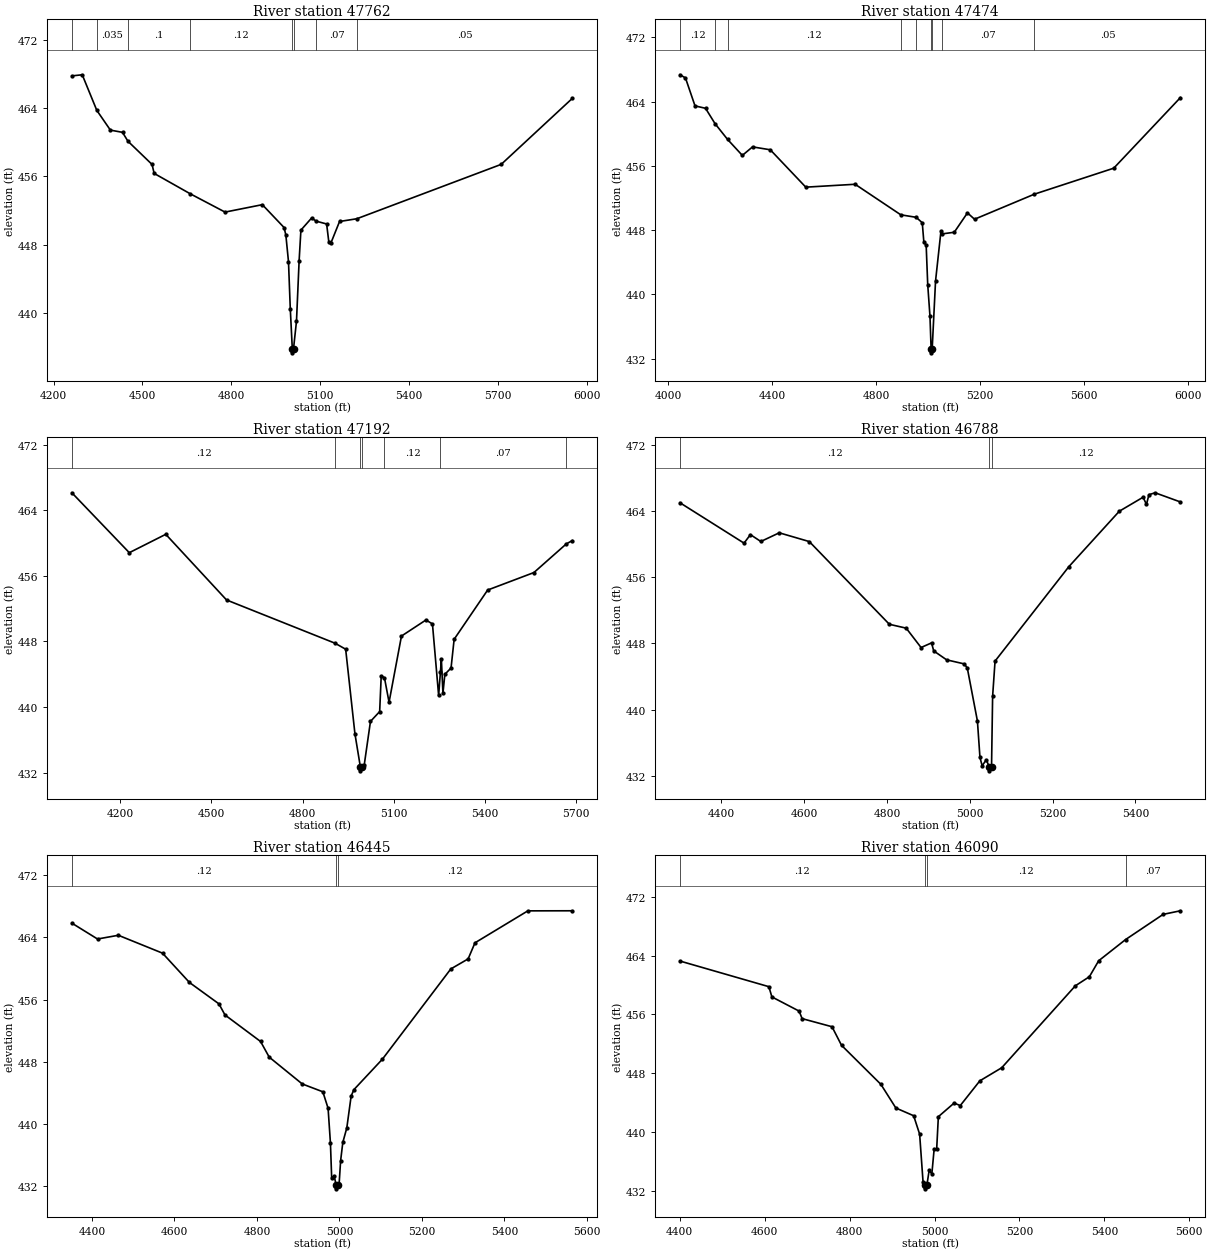
Type RM Length L Ch R = 1 ,47762   ,288,288,288
BEGIN DESCRIPTION:
X18355
END DESCRIPTION:
XS GIS Cut Line= 3
      2475458.15     13830514.05      2474830.53     13830725.98
      2474251.84     13831573.64
#Sta/Elev= 30
    4262  467.76    4297  467.89  4346.2  463.72    4392  461.41  4432.9  461.15
  4451.2  460.11  4532.6  457.39  4539.7  456.34  4661.2  453.96    4779  451.81
  4904.8  452.68  4978.2     450  4984.2  449.12  4993.1     446  4999.1  440.52
  5005.9  435.83  5006.2  435.33  5010.1  435.83  5020.1  439.04    5029  446.14
    5035   449.7  5070.9  451.11  5087.4  450.74  5121.8  450.42  5129.1  448.34
  5136.7  448.23  5165.4  450.71  5223.6  451.03    5711   457.4  5950.8  465.12
#Mann= 8 ,-1 , 0
    4262     .12       0  4346.2    .035       0  4451.2      .1       0
  4661.2     .12       0  5005.9     .05       0  5010.1     .12       0
  5087.4     .07       0  5223.6     .05       0
Bank Sta=5005.9,5010.1
XS Rating Curve= 0 ,0
Exp/Cntr=0.3,0.1

Type RM Length L Ch R = 1 ,47474   ,282,282,282
BEGIN DESCRIPTION:
X18356
END DESCRIPTION:
XS GIS Cut Line= 4
      2475462.18     13830457.02      2474586.02      13830591.5
      2474414.87     13830848.23      2474211.59     13831551.57
#Sta/Elev= 30
  4045.3  467.33  4066.3  466.94  4103.1  463.46  4143.6  463.16  4180.2  461.25
  4228.2   459.3  4285.3   457.3  4324.6  458.36    4393     458  4529.7  453.35
  4719.7  453.71  4895.6  449.91  4954.7   449.6  4978.3  448.92  4984.3  446.55
  4993.3  446.13  4999.3  441.22    5008  437.27  5012.3  433.24  5012.5  432.74
  5016.5  433.24  5029.4  441.67  5050.4  447.92  5055.6  447.54  5101.5  447.74
  5152.3  450.15  5179.6  449.36  5410.2  452.48  5715.7  455.71  5972.4  464.49
#Mann= 9 ,-1 , 0
  4045.3     .12       0  4180.2    .035       0  4228.2     .12       0
  4895.6     .07       0  4954.7     .12       0  5012.3     .05       0
  5016.5     .12       0  5055.6     .07       0  5410.2     .05       0
Bank Sta=5012.3,5016.5
XS Rating Curve= 0 ,0
Exp/Cntr=0.3,0.1

Type RM Length L Ch R = 1 ,47192   ,404,404,404
BEGIN DESCRIPTION:
X18357
END DESCRIPTION:
XS GIS Cut Line= 3
        2475454.     13830436.64      2474651.23     13830432.57
      2473824.02      13830265.5
#Sta/Elev= 30
  4040.7  466.12  4229.7  458.82  4349.7  461.06  4549.7  453.06  4906.7  447.79
  4941.7  447.06  4972.3  436.73    4990  432.74  4990.4  432.24  4995.4  432.74
  5002.9  432.98  5023.3  438.26  5053.6  439.46  5058.7  443.81  5069.4  443.58
  5084.5   440.6  5125.3  448.66  5205.9  450.62  5227.3  450.14  5247.7  441.42
  5253.5  444.27  5256.7  445.84  5261.8  441.68  5268.1     444  5288.5  444.77
  5298.7  448.27    5409  454.27  5561.2   456.4  5668.1   459.9  5687.4  460.29
#Mann= 7 ,-1 , 0
  4040.7     .12       0  4906.7     .07       0    4990     .05       0
  4995.4     .07       0  5069.4     .12       0  5253.5     .07       0
  5668.1     .05       0
Bank Sta=4990,4995.4
XS Rating Curve= 0 ,0
Exp/Cntr=0.3,0.1

Type RM Length L Ch R = 1 ,46788   ,343,343,343
BEGIN DESCRIPTION:
X18358
END DESCRIPTION:
XS GIS Cut Line= 3
      2475460.37     13830387.93      2474696.44     13830110.14
       2474370.9     13829884.43
#Sta/Elev= 30
  4299.8     465  4454.5  460.12  4469.9  461.15  4495.1  460.32  4539.6  461.37
  4612.2  460.31  4805.6  450.31  4846.3  449.84  4882.2   447.5  4907.5  448.06
  4912.8  447.09    4944  446.01  4986.5  445.52  4993.9  445.03  5018.4  438.61
  5024.5  434.22  5029.8   433.2  5039.7  433.92    5047  433.09  5047.5  432.59
  5052.5  433.09  5055.1   441.6    5061  445.86    5239  457.26  5361.2  463.98
  5418.6  465.67  5426.8  464.81  5432.9  465.98  5447.7  466.21  5508.8   465.1
#Mann= 3 ,-1 , 0
  4299.8     .12       0    5047     .05       0  5052.5     .12       0
Bank Sta=5047,5052.5
XS Rating Curve= 0 ,0
Exp/Cntr=0.3,0.1

Type RM Length L Ch R = 1 ,46445   ,355,355,355
BEGIN DESCRIPTION:
X18359
END DESCRIPTION:
XS GIS Cut Line= 3
      2475512.45     13830244.71       2474982.9     13829871.42
       2474444.7     13829697.81
#Sta/Elev= 30
  4351.3  465.83  4413.5  463.79    4464  464.27  4571.1  461.97  4636.4   458.2
  4707.9  455.45  4722.6  454.02  4808.9  450.61  4829.8   448.6  4909.9  445.15
  4959.9  444.14  4972.6  442.02  4978.3  437.54  4981.3  433.06  4987.4  433.31
  4992.1  432.16  4992.5  431.66  4997.6  432.16  4999.2  432.16    5003  435.28
  5008.3  437.63    5018   439.5  5028.5  443.59  5035.1  444.41  5104.4  448.34
  5270.2  459.94  5312.2  461.23  5328.8   463.3    5457  467.41  5564.7  467.42
#Mann= 3 ,-1 , 0
  4351.3     .12       0  4992.1     .05       0  4997.6     .12       0
Bank Sta=4992.1,4997.6
XS Rating Curve= 0 ,0
Exp/Cntr=0.3,0.1

Type RM Length L Ch R = 1 ,46090   ,519,519,519
BEGIN DESCRIPTION:
X18360
END DESCRIPTION:
XS GIS Cut Line= 3
      2475603.52     13829940.84      2475134.81     13829563.26
      2474609.78     13829324.61
#Sta/Elev= 30
  4400.5  463.25  4609.8  459.77  4616.9  458.38  4681.1  456.45  4688.1  455.43
  4758.5  454.33  4780.9  451.81  4873.7   446.5  4908.9  443.29  4950.8  442.24
  4964.9  439.74  4972.9  433.29  4976.5  432.81    4977  432.31    4982  432.81
  4987.3  434.81  4993.7  434.35    4999  437.66    5005  437.66    5009  442.11
  5046.1  443.96  5060.6  443.62  5106.7  446.98  5158.3  448.76  5331.7  459.89
  5364.7  461.12  5386.6  463.29    5450  466.17  5538.4  469.59  5579.1  470.08
#Mann= 4 ,-1 , 0
  4400.5     .12       0  4976.5     .05       0    4982     .12       0
    5450     .07       0
Bank Sta=4976.5,4982
XS Rating Curve= 0 ,0
Exp/Cntr=0.3,0.1

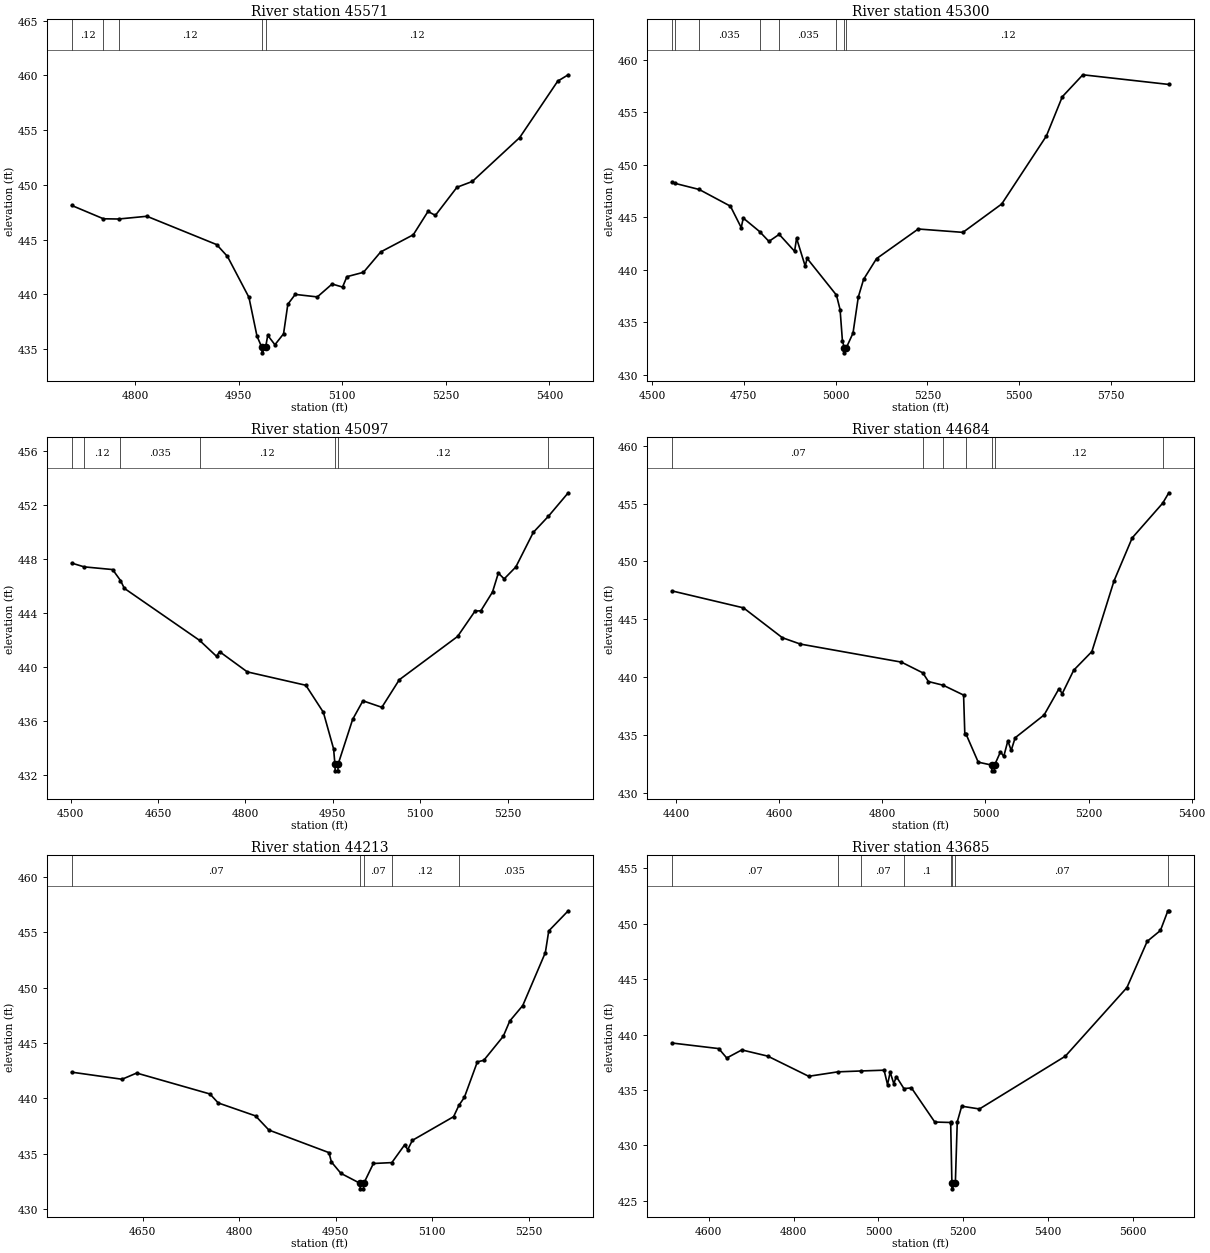
Type RM Length L Ch R = 1 ,45571   ,271,271,271
BEGIN DESCRIPTION:
BUCK BRANCH 80.0
END DESCRIPTION:
XS GIS Cut Line= 3
      2475475.02     13829225.01        2475225.       13829075.
      2474824.97     13829225.01
#Sta/Elev= 30
  4708.4  448.12  4754.4   446.9  4776.3  446.88  4817.3  447.13  4918.3  444.54
  4933.9  443.46    4965  439.72  4976.6  436.19  4983.6  435.15    4984  434.65
  4989.1  435.15  4992.2  436.25  5002.6  435.39  5015.1  436.39  5021.3  439.09
    5032  439.99    5064  439.76  5085.4  440.94  5100.5  440.66  5106.8  441.61
  5130.8  442.01  5155.7  443.87  5202.9  445.44  5224.2  447.57  5234.9  447.21
  5266.1  449.78  5288.3  450.31  5356.9  454.32    5412  459.48  5427.2  460.06
#Mann= 5 ,-1 , 0
  4708.4     .12       0  4754.4    .035       0  4776.3     .12       0
  4983.6     .05       0  4989.1     .12       0
Bank Sta=4983.6,4989.1
XS Rating Curve= 0 ,0
Exp/Cntr=0.3,0.1

Type RM Length L Ch R = 1 ,45300   ,203,203,203
BEGIN DESCRIPTION:
X18361
END DESCRIPTION:
XS GIS Cut Line= 3
      2475516.75     13829269.85      2475351.82      13828896.6
      2474762.03     13828159.35
#Sta/Elev= 30
  4555.4  448.35  4564.1  448.22  4628.7  447.65  4713.8  446.06  4743.2  444.02
  4748.7  444.93  4793.1  443.65  4818.6  442.71  4846.6  443.38  4888.5  441.77
  4893.9  443.01  4917.3  440.37  4922.7  441.09  5002.5   437.6  5012.4  436.22
  5018.8  433.23    5024  432.61  5024.4  432.11  5029.6  432.61  5047.6  433.99
    5062  437.42  5076.4   439.1  5111.6  441.07  5225.3  443.89  5346.9  443.57
  5452.6  446.27  5574.2  452.74  5617.5  456.47  5673.5  458.56  5907.6  457.64
#Mann= 8 ,-1 , 0
  4555.4    .035       0  4564.1     .12       0  4628.7    .035       0
  4793.1     .12       0  4846.6    .035       0  5002.5     .12       0
    5024    .035       0  5029.6     .12       0
Bank Sta=5024,5029.6
XS Rating Curve= 0 ,0
Exp/Cntr=0.3,0.1

Type RM Length L Ch R = 1 ,45097   ,413,413,413
BEGIN DESCRIPTION:
BUCK BRANCH 79.0
END DESCRIPTION:
XS GIS Cut Line= 3
        2475525.     13829224.99        2475475.       13828725.
        2475475.     13828374.98
#Sta/Elev= 30
  4501.6  447.68  4522.9   447.4  4571.9   447.2  4585.4  446.39    4592  445.81
  4721.2  441.96  4750.3  440.78  4755.4  441.13  4803.1  439.63  4903.6  438.64
  4933.7  436.64  4951.3  433.93  4953.5  432.81    4954  432.31  4958.7  432.31
  4959.1  432.81    4984  436.12  5001.6  437.49  5034.1  437.01  5064.1  439.05
  5164.1  442.25  5194.1  444.13  5204.1  444.15  5224.1  445.54  5234.1  446.94
  5244.1  446.51  5264.1  447.39  5294.1  449.95    5320  451.14  5354.1  452.88
#Mann= 7 ,-1 , 0
  4501.6    .035       0  4522.9     .12       0  4585.4    .035       0
  4721.2     .12       0  4953.5     .05       0  4959.1     .12       0
    5320    .035       0
Bank Sta=4953.5,4959.1
XS Rating Curve= 0 ,0
Exp/Cntr=0.3,0.1

Type RM Length L Ch R = 1 ,44684   ,471,471,471
BEGIN DESCRIPTION:
BUCK BRANCH 78.0
END DESCRIPTION:
XS GIS Cut Line= 3
      2475975.01     13829125.04      2475829.25     13828575.42
      2475524.98     13828324.99
#Sta/Elev= 30
  4392.9  447.45    4531  445.99  4606.3  443.41  4641.2  442.86  4837.1   441.3
  4878.7  440.37  4889.5  439.62  4918.2   439.3  4957.7  438.45  4960.1  435.05
  4962.7  435.05  4986.1  432.65  5011.9   432.4  5012.4   431.9  5017.3   431.9
  5017.8   432.4  5029.2  433.54  5035.6  433.15  5043.5  434.49    5050  433.67
  5057.7  434.76  5113.8  436.73  5142.5  438.99    5149  438.58  5171.2   440.6
  5206.4  442.21  5249.4  448.33  5284.6  452.04  5343.7  455.04  5355.6  455.94
#Mann= 7 ,-1 , 0
  4392.9     .07       0  4878.7     .05       0  4918.2     .07       0
  4962.7     .12       0  5011.9     .05       0  5017.8     .12       0
  5343.7    .035       0
Bank Sta=5011.9,5017.8
XS Rating Curve= 0 ,0
Exp/Cntr=0.3,0.1

Type RM Length L Ch R = 1 ,44213   ,528,528,528
BEGIN DESCRIPTION:
BUCK BRANCH 77.0
END DESCRIPTION:
XS GIS Cut Line= 3
      2476085.34     13828445.22      2475837.93     13828124.03
      2475475.03       13828175.
#Sta/Elev= 30
  4539.7  442.37    4618  441.73  4640.7  442.29  4754.6   440.4  4767.5  439.59
  4825.5  438.42  4846.3  437.14  4939.7   435.1  4943.4  434.26  4958.2  433.23
  4987.9  432.33  4988.4  431.83  4993.3  431.83  4993.8  432.33  5008.7  434.12
  5037.4   434.2  5057.1  435.79  5062.1  435.38  5069.3  436.21  5133.4  438.35
  5141.6  439.37  5150.1  440.09  5170.3   443.3  5180.3  443.44  5210.6  445.61
  5220.7  446.99  5240.9  448.39    5276  453.17  5281.3  455.13  5311.6  456.95
#Mann= 5 ,-1 , 0
  4539.7     .07       0  4987.9     .05       0  4993.8     .07       0
  5037.4     .12       0  5141.6    .035       0
Bank Sta=4987.9,4993.8
XS Rating Curve= 0 ,0
Exp/Cntr=0.3,0.1

Type RM Length L Ch R = 1 ,43685   ,391,391,391
BEGIN DESCRIPTION:
BUCK BRANCH 76.0
END DESCRIPTION:
XS GIS Cut Line= 6
      2476018.83     13828074.59      2475895.14     13827757.77
      2475847.39     13827683.98      2475715.02     13827577.65
      2475619.53     13827547.27      2475165.98     13827677.47
#Sta/Elev= 30
  4514.2  439.24  4623.7  438.74  4642.6  437.89  4678.1  438.62  4739.2  438.06
  4835.7  436.24  4904.3  436.64    4959  436.72  5013.4  436.79  5021.5  435.48
  5027.7  436.61  5036.2  435.58  5042.3  436.21  5060.1  435.13  5077.9  435.19
  5132.8  432.11  5169.9  432.07  5170.3  432.06  5173.2  426.58  5173.3  426.08
  5181.3  426.58  5185.8  432.12  5196.3  433.54  5238.1  433.29  5440.4  438.05
  5585.7  444.25  5633.4  448.42  5664.6   449.4  5681.6  451.12  5684.4  451.18
#Mann= 8 ,-1 , 0
  4514.2     .07       0  4904.3      .1       0    4959     .07       0
  5060.1      .1       0  5169.9     .07       0  5173.2     .05       0
  5181.3     .07       0  5681.6     .05       0
Bank Sta=5173.2,5181.3
XS Rating Curve= 0 ,0
Exp/Cntr=0.3,0.1

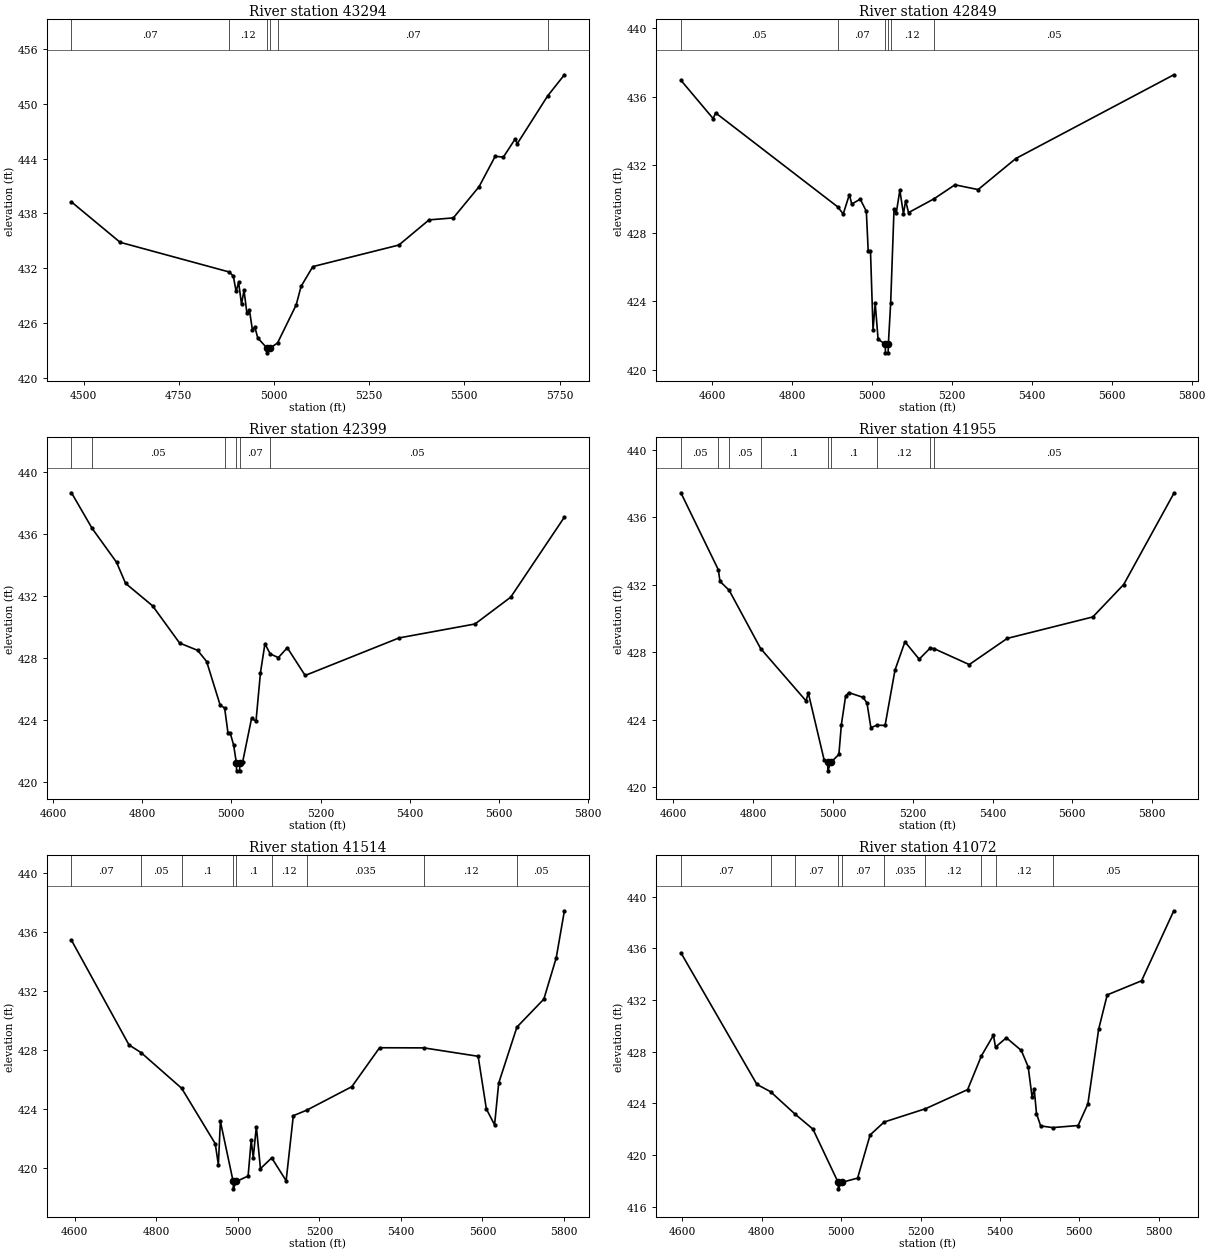
Type RM Length L Ch R = 1 ,43294   ,445,445,445
BEGIN DESCRIPTION:
BUCK BRANCH 75.0
END DESCRIPTION:
XS GIS Cut Line= 3
      2476175.03     13827625.03        2475775.       13827275.
      2475124.97     13827675.02
#Sta/Elev= 30
    4468  439.26  4595.7  434.85  4882.5   431.6  4893.2  431.14  4900.4  429.47
    4907  430.47  4914.6  428.08  4921.2  429.61  4928.8  427.08  4935.5  427.42
  4943.1   425.3  4949.7  425.58  4957.3  424.38    4982  423.26  4982.5  422.76
  4989.5  423.26  5009.4  423.85  5058.3  428.01  5071.1  430.03  5101.9  432.19
    5328  434.55  5407.2   437.3  5471.1  437.52  5538.6  440.93  5581.1  444.26
  5602.4  444.16  5633.2  446.13  5639.1  445.64  5718.5  450.84  5762.8  453.17
#Mann= 6 ,-1 , 0
    4468     .07       0  4882.5     .12       0    4982     .05       0
  4989.5     .12       0  5009.4     .07       0  5718.5     .05       0
Bank Sta=4982,4989.5
XS Rating Curve= 0 ,0
Exp/Cntr=0.3,0.1

Type RM Length L Ch R = 1 ,42849   ,450,450,450
BEGIN DESCRIPTION:
BUCK BRANCH 74.0
END DESCRIPTION:
XS GIS Cut Line= 3
      2476324.99     13827124.99        2475925.       13826875.
      2475224.96     13827175.02
#Sta/Elev= 30
    4522  436.96  4602.8  434.71  4608.7  435.05  4914.2  429.54  4928.2  429.12
  4943.6  430.26  4949.5   429.7  4970.7  429.99    4986  429.28  4990.7  426.94
  4996.4  426.94  5002.8  422.33  5008.2  423.89  5015.4  421.78  5033.4  421.48
  5033.9  420.98  5040.6  420.98  5041.1  421.48  5046.9   423.9  5055.3  429.41
  5060.8  429.16  5069.8  430.51  5078.9  429.13  5084.3  429.89  5091.6   429.2
  5155.4  430.01  5207.7  430.83  5265.7  430.55    5360  432.37  5755.3  437.28
#Mann= 6 ,-1 , 0
    4522     .05       0  4914.2     .07       0  5033.4     .05       0
  5041.1     .07       0  5046.9     .12       0  5155.4     .05       0
Bank Sta=5033.4,5041.1
XS Rating Curve= 0 ,0
Exp/Cntr=0.3,0.1

Type RM Length L Ch R = 1 ,42399   ,444,444,444
BEGIN DESCRIPTION:
BUCK BRANCH 73.0
END DESCRIPTION:
XS GIS Cut Line= 3
      2476424.99       13826525.        2476075.       13826475.
      2475325.01       13826425.
#Sta/Elev= 30
  4641.6  438.65  4687.7  436.36  4742.6  434.17  4762.8  432.81  4823.4  431.36
    4884  428.96  4924.4  428.49  4944.6  427.77  4974.9  424.96    4985  424.77
  4992.6  423.13  4997.7  423.13  5005.2  422.38  5011.3  421.22  5011.8  420.72
  5018.6  420.72  5019.1  421.22  5025.2  421.27  5045.3   424.1  5055.3  423.92
  5065.3  427.05  5075.3  428.91  5087.2  428.26  5105.4  428.02  5125.4  428.66
  5165.5  426.87    5376  429.29  5546.4  430.19  5626.5  431.92  5746.8  437.08
#Mann= 6 ,-1 , 0
  4641.6    .035       0  4687.7     .05       0    4985     .07       0
  5011.3     .05       0  5019.1     .07       0  5087.2     .05       0
Bank Sta=5011.3,5019.1
XS Rating Curve= 0 ,0
Exp/Cntr=0.3,0.1

Type RM Length L Ch R = 1 ,41955   ,441,441,441
BEGIN DESCRIPTION:
BUCK BRANCH 72.0
END DESCRIPTION:
XS GIS Cut Line= 3
      2476475.03     13826225.01        2476125.       13826075.
      2475325.02     13826374.99
#Sta/Elev= 30
  4619.1  437.44    4713  432.88    4717   432.2    4740  431.67  4818.9  428.22
  4932.8  425.12  4938.3   425.6  4978.2  421.61  4986.9  421.48  4987.4  420.98
  4994.8  421.48    5015  421.95  5021.3  423.72    5032  425.42    5040  425.61
  5075.6  425.33  5085.4     425  5095.2  423.54  5110.5  423.68  5130.8  423.67
  5155.7  426.95  5180.6  428.62  5216.2  427.59  5243.5  428.24    5253  428.22
  5341.7  427.27  5436.9  428.82  5651.4  430.09  5728.8  432.01  5854.3   437.4
#Mann= 9 ,-1 , 0
  4619.1     .05       0    4713     .07       0    4740     .05       0
  4818.9      .1       0  4986.9     .05       0  4994.8      .1       0
  5110.5     .12       0  5243.5     .07       0    5253     .05       0
Bank Sta=4986.9,4994.8
XS Rating Curve= 0 ,0
Exp/Cntr=0.3,0.1

Type RM Length L Ch R = 1 ,41514   ,442,442,442
BEGIN DESCRIPTION:
BUCK BRANCH 71.0
END DESCRIPTION:
XS GIS Cut Line= 3
      2476474.99       13825625.        2476075.       13825675.
      2475275.03       13825575.
#Sta/Elev= 30
  4591.9  435.45    4733  428.35  4762.6  427.83  4862.2  425.41  4944.6  421.65
  4952.2  420.23  4957.2  423.17  4988.5  419.09    4989  418.59  4996.5  419.09
  5025.2  419.46  5032.8  421.89  5037.8   420.7  5045.4  422.81  5055.5  419.96
  5083.1  420.69  5118.5  419.14  5136.1  423.55  5169.4  423.93  5279.7  425.52
  5347.7  428.16  5456.7  428.15  5589.6  427.58  5609.7  424.01  5629.9  422.93
    5640  425.76  5684.7  429.56  5750.8  431.46  5781.1  434.25  5801.2  437.45
#Mann= 9 ,-1 , 0
  4591.9     .07       0  4762.6     .05       0  4862.2      .1       0
  4988.5     .05       0  4996.5      .1       0  5083.1     .12       0
  5169.4    .035       0  5456.7     .12       0  5684.7     .05       0
Bank Sta=4988.5,4996.5
XS Rating Curve= 0 ,0
Exp/Cntr=0.3,0.1

Type RM Length L Ch R = 1 ,41072   ,468,468,468
BEGIN DESCRIPTION:
BUCK BRANCH 70.0
END DESCRIPTION:
XS GIS Cut Line= 3
        2476425.       13825225.        2476025.       13825275.
      2475224.97     13825525.01
#Sta/Elev= 30
  4596.5  435.66    4788  425.47  4822.2  424.91  4882.7  423.21  4929.1  422.01
  4992.5  417.89    4993  417.39  5001.6  417.89  5041.5  418.22    5073  421.56
  5108.3  422.56  5212.5  423.59  5318.6  425.07  5353.3  427.68  5383.6  429.28
  5388.8  428.36  5416.1  429.08  5453.8   428.1  5471.1  426.83    5481  424.48
  5486.3  425.12    5492  423.22  5502.5  422.26  5532.8  422.13  5596.8  422.29
  5621.4  423.96  5648.7  429.76  5670.1   432.4  5756.6  433.49  5837.8  438.91
#Mann= 10 ,-1 , 0
  4596.5     .07       0  4822.2     .12       0  4882.7     .07       0
  4992.5     .05       0  5001.6     .07       0  5108.3    .035       0
  5212.5     .12       0  5353.3    .035       0  5388.8     .12       0
  5532.8     .05       0
Bank Sta=4992.5,5001.6
XS Rating Curve= 0 ,0
Exp/Cntr=0.3,0.1