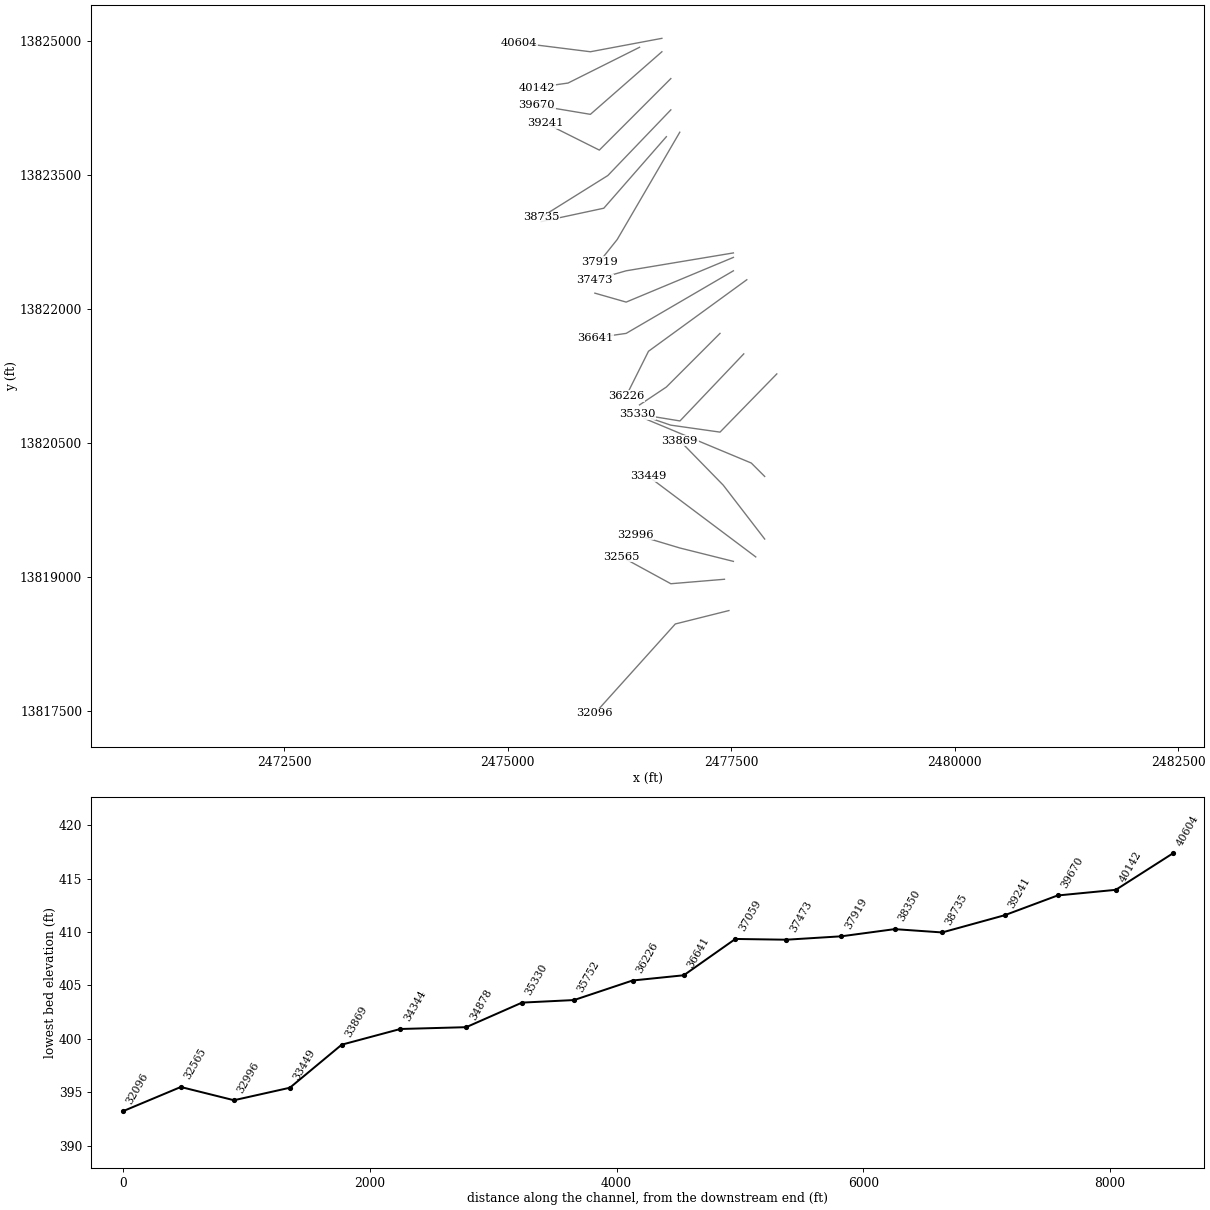
HEC-RAS study BUCK BRANCH.prj: BUCK BRANCH Base Level Engineering

--- BUCK BRANCH.g01 (geometry) --- (continued)

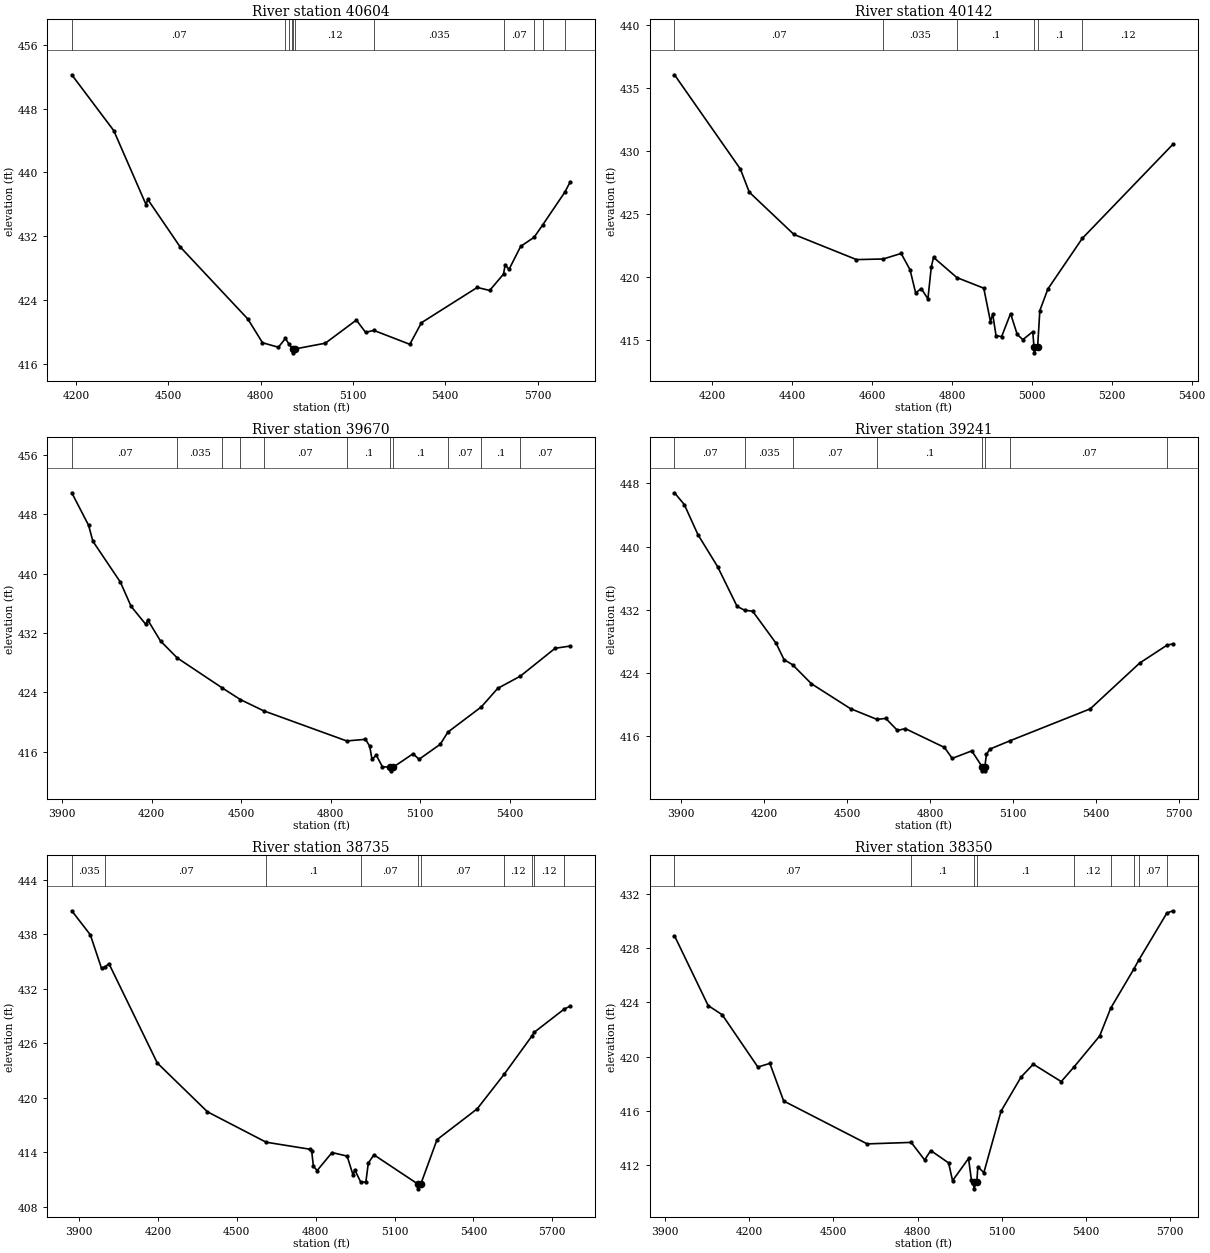
Type RM Length L Ch R = 1 ,40604   ,462,462,462
BEGIN DESCRIPTION:
BUCK BRANCH 69.0
END DESCRIPTION:
XS GIS Cut Line= 3
      2476724.98       13825025.        2475925.       13824875.
      2475125.05     13824974.99
#Sta/Elev= 30
  4186.1  452.26  4322.6  445.25  4427.7  435.94  4432.8  436.63  4537.9  430.68
  4758.4   421.6  4805.9  418.63  4857.6  418.06  4880.4  419.17  4891.7  418.47
  4901.3  417.99  4903.9  417.86  4904.4  417.36    4913  417.86  5010.1  418.57
  5110.9  421.47  5141.1  419.93  5167.5  420.18  5284.7  418.43  5322.5  421.14
  5503.9  425.57  5544.2  425.19  5589.2  427.24  5594.6  428.39  5607.2  427.84
    5645  430.72  5688.8  431.87  5716.8  433.43  5788.4  437.52  5806.2  438.83
#Mann= 11 ,-1 , 0
  4186.1     .07       0  4880.4     .12       0  4891.7    .035       0
  4901.3     .12       0  4903.9     .05       0    4913     .12       0
  5167.5    .035       0  5589.2     .07       0  5688.8     .12       0
  5716.8     .07       0  5788.4     .12       0
Bank Sta=4903.9,4913
XS Rating Curve= 0 ,0
Exp/Cntr=0.3,0.1

Type RM Length L Ch R = 1 ,40142   ,472,472,472
BEGIN DESCRIPTION:
BUCK BRANCH 68.0
END DESCRIPTION:
XS GIS Cut Line= 3
      2476474.96     13824924.98        2475675.       13824525.
      2475325.04     13824475.01
#Sta/Elev= 30
  4105.2  436.05  4270.1  428.56  4292.4  426.72  4404.2  423.36  4560.8  421.36
  4627.8  421.41  4672.6  421.85  4694.9  420.55  4708.9  418.71  4722.9  419.06
  4739.6  418.24    4748  420.76  4753.6  421.54  4812.2  419.93  4879.4  419.09
  4896.2  416.44  4901.8  417.03  4910.1  415.32  4924.1  415.24  4946.5  417.07
  4963.2  415.41  4977.2     415  5002.1  415.63    5005  414.45  5005.5  413.95
  5014.3  414.45  5019.8  417.31    5040  419.03  5125.9  423.04  5353.1  430.53
#Mann= 6 ,-1 , 0
  4105.2     .07       0  4627.8    .035       0  4812.2      .1       0
    5005     .05       0  5014.3      .1       0  5125.9     .12       0
Bank Sta=5005,5014.3
XS Rating Curve= 0 ,0
Exp/Cntr=0.3,0.1

Type RM Length L Ch R = 1 ,39670   ,429,429,429
BEGIN DESCRIPTION:
BUCK BRANCH 67.0
END DESCRIPTION:
XS GIS Cut Line= 3
      2476724.98     13824874.98        2475925.       13824175.
      2475324.97     13824275.01
#Sta/Elev= 30
  3931.8  450.92  3988.2  446.53  4002.5  444.39  4094.6  438.88  4130.6  435.61
    4180  433.17  4186.6  433.76  4229.3  430.93  4285.3  428.65  4437.1  424.58
  4497.1  423.03  4574.8  421.52  4853.6  417.45  4916.5  417.67  4930.7  416.74
  4938.3  414.98  4952.6  415.53  4973.4  413.96  5000.3  413.92  5000.8  413.42
  5009.6  413.92  5075.9  415.72  5096.2  414.98  5167.1     417    5193  418.65
  5304.8  422.04  5359.8  424.54  5435.7  426.19  5552.4  429.95  5603.1  430.25
#Mann= 11 ,-1 , 0
  3931.8     .07       0  4285.3    .035       0  4437.1     .07       0
  4497.1    .035       0  4574.8     .07       0  4853.6      .1       0
  5000.3     .05       0  5009.6      .1       0    5193     .07       0
  5304.8      .1       0  5435.7     .07       0
Bank Sta=5000.3,5009.6
XS Rating Curve= 0 ,0
Exp/Cntr=0.3,0.1

Type RM Length L Ch R = 1 ,39241   ,506,506,506
BEGIN DESCRIPTION:
BUCK BRANCH 66.0
END DESCRIPTION:
XS GIS Cut Line= 3
        2476825.       13824575.        2476025.       13823775.
      2475424.99     13824075.01
#Sta/Elev= 30
  3875.8  446.82  3911.2  445.33  3960.6  441.51  4031.4  437.47  4102.1  432.42
    4129  431.94  4158.6   431.8  4243.5  427.72  4271.8  425.67  4302.8  425.02
  4370.8  422.61  4512.2  419.45  4607.9  418.09  4639.5  418.22  4681.9  416.69
  4710.2  416.92  4851.6  414.54  4879.9  413.15  4950.6   414.1  4988.3  412.07
  4988.8  411.57  4997.2  411.57  4997.7  412.07  5003.6  413.65  5015.6  414.32
  5088.6  415.38  5378.9  419.43  5557.8  425.24  5656.8  427.51    5678  427.66
#Mann= 8 ,-1 , 0
  3875.8     .07       0    4129    .035       0  4302.8     .07       0
  4607.9      .1       0  4988.3     .05       0  4997.7      .1       0
  5088.6     .07       0  5656.8     .05       0
Bank Sta=4988.3,4997.7
XS Rating Curve= 0 ,0
Exp/Cntr=0.3,0.1

Type RM Length L Ch R = 1 ,38735   ,385,385,385
BEGIN DESCRIPTION:
BUCK BRANCH 65.0
END DESCRIPTION:
XS GIS Cut Line= 3
      2476825.02     13824225.03      2476120.05     13823490.52
      2475375.01       13823025.
#Sta/Elev= 30
  3871.9  440.61  3942.5  437.96    3985  434.27  3999.4  434.45  4013.3  434.78
  4197.3  423.83  4388.2  418.45  4611.4   415.1  4777.2  414.33  4784.4  414.18
  4791.3  412.43  4805.5  411.98  4862.1  413.96  4919.5  413.57  4942.4  411.45
  4948.3  412.07    4971  410.72  4990.7   410.7  5000.2  412.81  5021.4  413.71
  5190.1  410.46  5190.6  409.96  5199.5  410.46  5261.5  415.38  5414.1  418.77
    5517  422.59  5622.4   426.8  5631.1  427.21  5745.2  429.77  5768.5   430.1
#Mann= 10 ,-1 , 0
  3871.9    .035       0  3999.4     .07       0  4611.4      .1       0
    4971     .07       0  5190.1     .05       0  5199.5     .07       0
    5517     .12       0  5622.4     .07       0  5631.1     .12       0
  5745.2     .07       0
Bank Sta=5190.1,5199.5
XS Rating Curve= 0 ,0
Exp/Cntr=0.3,0.1

Type RM Length L Ch R = 1 ,38350   ,431,431,431
BEGIN DESCRIPTION:
BUCK BRANCH 64.0
END DESCRIPTION:
XS GIS Cut Line= 3
        2476775.       13823925.        2476075.       13823125.
      2475375.01       13822975.
#Sta/Elev= 30
  3932.8  428.91  4052.9  423.77  4103.2  423.09  4230.4  419.24  4273.1  419.51
  4322.4  416.74  4620.4  413.58  4777.5  413.69  4825.4   412.4  4847.3  413.09
  4910.9  412.18  4925.1  410.87  4982.1  412.51  4992.5   410.9  5000.5  410.77
    5001  410.27  5011.5  410.77  5015.4   411.9  5036.7  411.46  5098.1  415.99
  5169.7  418.51  5213.1  419.45  5312.9  418.17    5359  419.26  5450.1  421.53
  5489.6  423.58  5571.5  426.44  5589.7  427.12  5689.8  430.58  5711.7  430.75
#Mann= 9 ,-1 , 0
  3932.8     .07       0  4777.5      .1       0  5000.5     .05       0
  5011.5      .1       0    5359     .12       0  5489.6     .07       0
  5571.5     .12       0  5589.7     .07       0  5689.8     .12       0
Bank Sta=5000.5,5011.5
XS Rating Curve= 0 ,0
Exp/Cntr=0.3,0.1

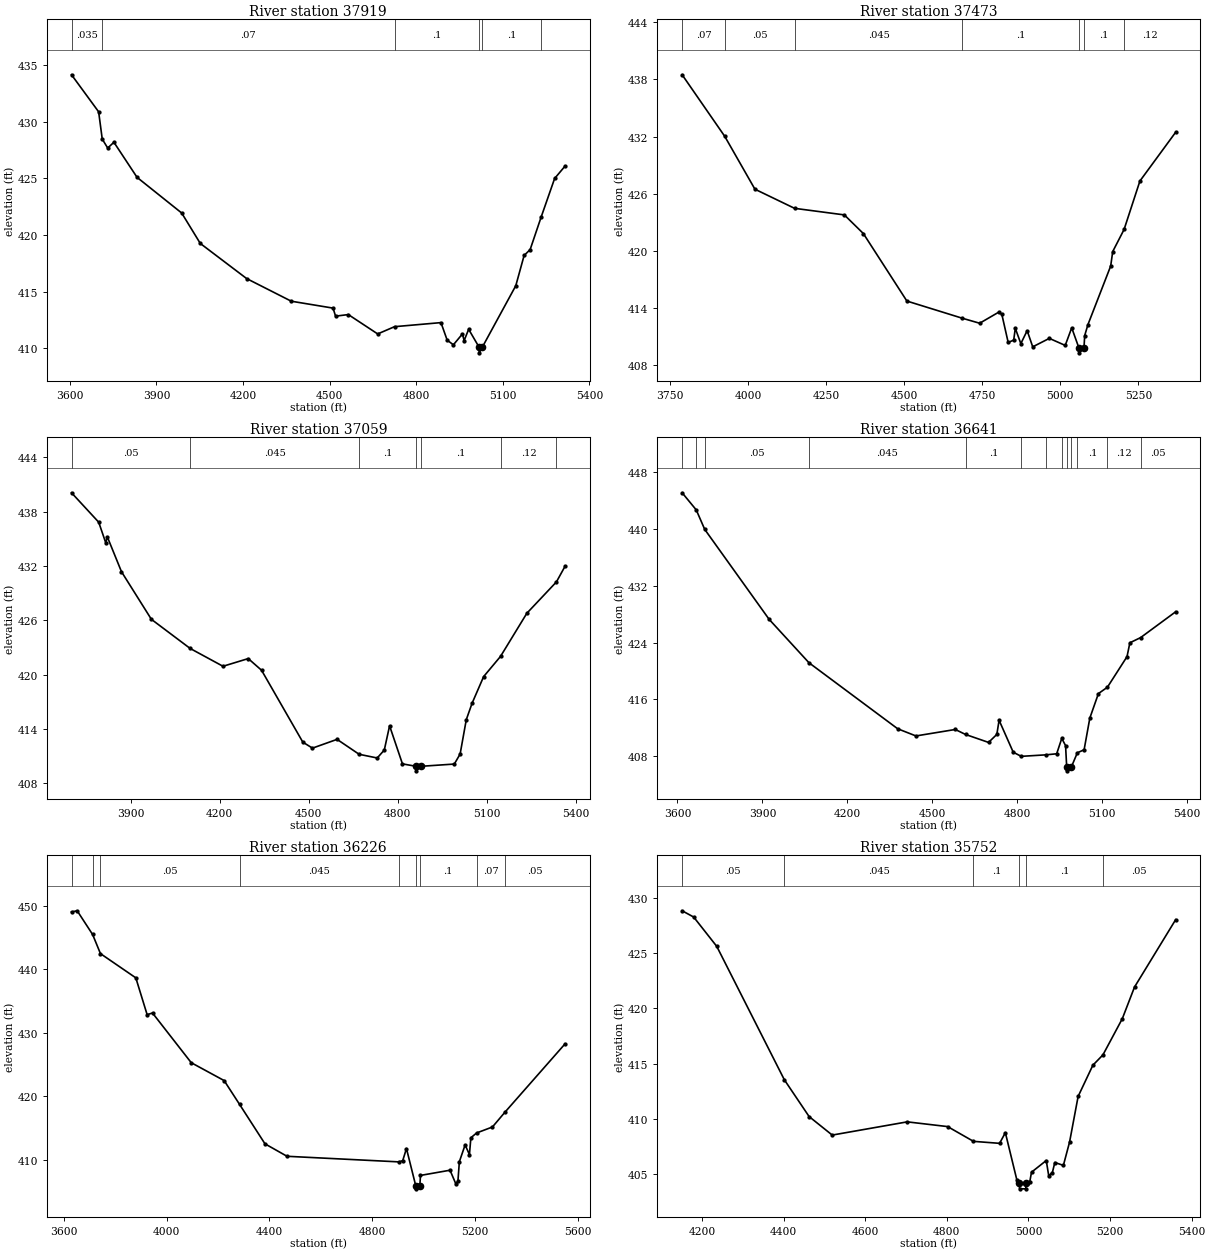
Type RM Length L Ch R = 1 ,37919   ,446,446,446
BEGIN DESCRIPTION:
BUCK BRANCH 63.0
END DESCRIPTION:
XS GIS Cut Line= 3
      2476925.01     13823975.01        2476225.       13822775.
      2476025.01     13822525.01
#Sta/Elev= 30
  3606.1  434.16    3700  430.89  3712.5  428.48  3731.4  427.69  3752.9   428.2
  3833.1   425.1  3987.7  421.95  4052.2  419.26  4212.7  416.16  4367.3  414.16
    4512  413.55  4520.7  412.84  4564.9  412.98  4666.6  411.27  4724.9  411.91
  4885.8  412.27  4907.3  410.72  4928.8  410.31  4960.2  411.27    4966  410.68
  4981.7  411.68  5017.8   410.1  5018.3   409.6    5029   410.1    5145  415.53
  5173.8   418.2  5194.7  418.72  5232.5  421.57  5279.5     425  5315.5  426.09
#Mann= 6 ,-1 , 0
  3606.1    .035       0  3712.5     .07       0  4724.9      .1       0
  5017.8     .05       0    5029      .1       0  5232.5     .12       0
Bank Sta=5017.8,5029
XS Rating Curve= 0 ,0
Exp/Cntr=0.3,0.1

Type RM Length L Ch R = 1 ,37473   ,414,414,414
BEGIN DESCRIPTION:
BUCK BRANCH 62.0
END DESCRIPTION:
XS GIS Cut Line= 3
      2477524.98       13822625.        2476325.       13822425.
      2475975.03     13822325.01
#Sta/Elev= 30
    3789  438.49  3925.5  432.02  4022.1  426.47  4149.1  424.46  4308.5  423.77
  4369.4  421.81  4508.8  414.72  4686.8  412.91  4741.9  412.39  4802.8  413.55
  4812.9  413.32  4833.2  410.37  4850.9  410.62    4856  411.86  4873.7  410.25
    4894  411.61  4911.8  409.91    4965   410.8  5015.9  410.06  5036.7  411.91
  5059.9  409.78  5060.4  409.28  5075.9  409.78  5078.3   411.1  5088.7  412.25
  5161.5   418.4    5168  419.92  5204.4  422.24  5255.1  427.33  5369.5  432.45
#Mann= 7 ,-1 , 0
    3789     .07       0  3925.5     .05       0  4149.1    .045       0
  4686.8      .1       0  5059.9     .05       0  5075.9      .1       0
  5204.4     .12       0
Bank Sta=5059.9,5075.9
XS Rating Curve= 0 ,0
Exp/Cntr=0.3,0.1

Type RM Length L Ch R = 1 ,37059   ,418,418,418
BEGIN DESCRIPTION:
BUCK BRANCH 61.0
END DESCRIPTION:
XS GIS Cut Line= 3
      2477525.04     13822575.02        2476325.       13822075.
      2475974.96     13822175.01
#Sta/Elev= 30
  3700.3  440.09  3791.9  436.84  3815.7  434.56  3821.1  435.21  3868.8  431.36
  3969.6   426.1  4100.3  422.88  4211.1  420.91  4296.2  421.76  4341.1  420.47
  4480.3  412.52  4512.8  411.86  4595.7  412.83  4670.1  411.18  4731.1  410.77
    4755  411.65  4772.8  414.33  4816.2  410.12  4862.3  409.85  4862.8  409.35
  4878.3  409.85  4991.1   410.1  5010.7  411.21  5031.5  415.01    5051  416.82
    5090  419.77  5146.9     422  5235.7  426.77  5335.5  430.24  5364.4  431.96
#Mann= 7 ,-1 , 0
  3700.3     .05       0  4100.3    .045       0  4670.1      .1       0
  4862.3     .05       0  4878.3      .1       0  5146.9     .12       0
  5335.5     .05       0
Bank Sta=4862.3,4878.3
XS Rating Curve= 0 ,0
Exp/Cntr=0.3,0.1

Type RM Length L Ch R = 1 ,36641   ,415,415,415
BEGIN DESCRIPTION:
BUCK BRANCH 60.0
END DESCRIPTION:
XS GIS Cut Line= 3
      2477525.03     13822425.01        2476325.       13821725.
      2475975.03       13821675.
#Sta/Elev= 30
  3616.5  445.08  3666.3  442.67  3696.2  439.93  3923.7  427.27  4064.4  421.16
  4377.7  411.87  4442.2  410.86  4581.1  411.77  4617.3  411.07  4698.6  409.95
  4727.9  411.08  4735.8  413.07  4785.8  408.57    4814  407.99  4900.9   408.2
  4939.2  408.35  4957.2  410.52  4970.6   409.5  4974.6  406.45  4975.1  405.95
  4990.6  406.45  5012.2  408.49  5036.1  408.92  5056.3  413.38  5086.6  416.82
  5118.4  417.72  5187.6  422.02  5197.7  423.97  5235.6   424.7  5359.3  428.33
#Mann= 13 ,-1 , 0
  3616.5     .05       0  3666.3     .07       0  3696.2     .05       0
  4064.4    .045       0  4617.3      .1       0    4814     .07       0
  4900.9      .1       0  4957.2     .07       0  4974.6     .05       0
  4990.6     .07       0  5012.2      .1       0  5118.4     .12       0
  5235.6     .05       0
Bank Sta=4974.6,4990.6
XS Rating Curve= 0 ,0
Exp/Cntr=0.3,0.1

Type RM Length L Ch R = 1 ,36226   ,474,474,474
BEGIN DESCRIPTION:
BUCK BRANCH 59.0
END DESCRIPTION:
XS GIS Cut Line= 3
      2477674.97     13822324.98        2476575.       13821525.
      2476325.01     13821025.02
#Sta/Elev= 30
  3630.3  449.02  3652.3   449.2  3712.3  445.47  3742.8  442.46  3880.3  438.65
  3924.3  432.86  3945.2  433.12  4095.9   425.3  4223.8  422.49    4284  418.73
  4382.6  412.54  4468.4  410.58  4903.7   409.7  4918.2  409.89  4932.8   411.8
  4968.8  405.96  4969.3  405.46  4984.9  405.96  4987.3  407.57  5102.2  408.39
  5124.6  406.26    5133  406.69  5138.5  409.73  5160.9  412.37  5177.7  410.85
  5183.3  413.49  5205.6  414.25  5267.1  415.19  5316.3  417.54  5549.4  428.26
#Mann= 9 ,-1 , 0
  3630.3     .05       0  3712.3     .07       0  3742.8     .05       0
    4284    .045       0  4903.7      .1       0  4968.8     .05       0
  4984.9      .1       0  5205.6     .07       0  5316.3     .05       0
Bank Sta=4968.8,4984.9
XS Rating Curve= 0 ,0
Exp/Cntr=0.3,0.1

Type RM Length L Ch R = 1 ,35752   ,422,422,422
BEGIN DESCRIPTION:
BUCK BRANCH 58.0
END DESCRIPTION:
XS GIS Cut Line= 3
      2477374.99     13821724.99        2476775.       13821125.
      2476474.97     13820924.98
#Sta/Elev= 30
  4151.5  428.87  4179.8   428.3  4236.3  425.64  4401.9  413.53  4462.6  410.19
  4519.2  408.51    4703  409.71    4802  409.28  4865.3  407.94  4929.3  407.76
  4943.4  408.73  4971.7  404.42  4977.8  404.13  4978.3  403.63  4993.4  403.63
  4993.9  404.13    5003  404.23  5007.5  405.14  5043.6   406.2  5049.6  404.83
  5058.6  405.11  5064.6  406.02  5085.6  405.76  5100.7  407.87  5121.7  412.02
  5157.8  414.85  5182.5  415.79  5229.9  419.07  5259.9  421.95  5360.6  428.06
#Mann= 6 ,-1 , 0
  4151.5     .05       0  4401.9    .045       0  4865.3      .1       0
  4977.8     .05       0  4993.9      .1       0  5182.5     .05       0
Bank Sta=4977.8,4993.9
XS Rating Curve= 0 ,0
Exp/Cntr=0.3,0.1

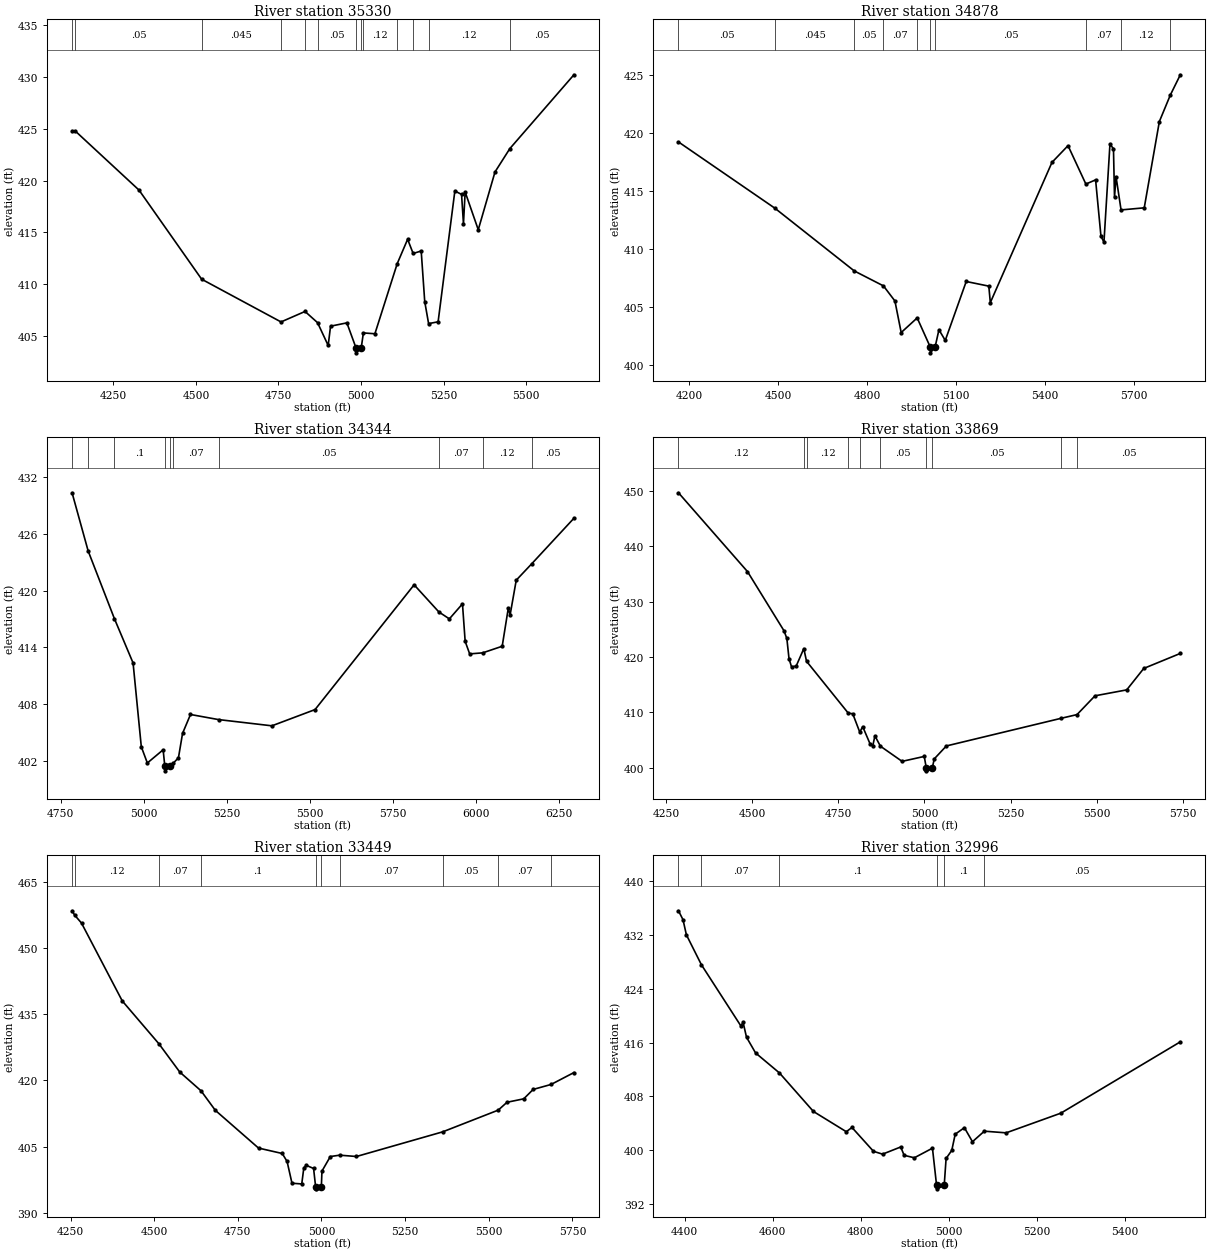
Type RM Length L Ch R = 1 ,35330   ,452,452,452
BEGIN DESCRIPTION:
X18362
END DESCRIPTION:
XS GIS Cut Line= 3
      2477640.91     13821495.75      2476927.34     13820745.73
      2476449.09      13820823.7
#Sta/Elev= 30
    4125  424.77  4134.9  424.77  4327.8  419.08  4517.4  410.49  4757.8  406.37
  4830.5  407.38  4868.4   406.3  4900.6   404.1  4907.8  405.96  4957.2  406.28
  4984.6  403.89  4985.1  403.39  5000.8  403.89  5007.2  405.31  5042.1  405.23
  5109.7  411.99  5141.2  414.34  5157.9  412.97  5182.3  413.21    5193  408.33
  5204.7  406.21  5233.5  406.38  5284.2  418.99  5304.5  418.67  5310.3  415.84
  5315.4   418.9  5355.1  415.26  5405.8  420.83  5450.7  423.08  5644.8   430.2
#Mann= 13 ,-1 , 0
    4125     .07       0  4134.9     .05       0  4517.4    .045       0
  4757.8     .05       0  4830.5    .035       0  4868.4     .05       0
  4984.6     .05       0  5000.8     .05       0  5007.2     .12       0
  5109.7     .05       0  5157.9     .07       0  5204.7     .12       0
  5450.7     .05       0
Bank Sta=4984.6,5000.8
XS Rating Curve= 0 ,0
Exp/Cntr=0.3,0.1

Type RM Length L Ch R = 1 ,34878   ,534,534,534
BEGIN DESCRIPTION:
X18363
END DESCRIPTION:
XS GIS Cut Line= 4
      2478010.67     13821271.77      2477375.26     13820620.73
      2476823.17     13820698.85      2476609.78     13820771.72
#Sta/Elev= 30
  4163.8  419.27  4488.9  413.56  4756.8  408.15  4855.3  406.86  4893.9  405.56
    4915  402.84    4969   404.1  5013.1  401.59  5013.6  401.09  5029.4  401.59
  5042.4  403.08  5063.7  402.16  5134.4  407.24  5210.6  406.84  5215.7  405.42
  5423.7  417.51  5477.8  418.95    5538  415.64  5570.8     416  5588.9  411.14
    5599  410.63  5619.2  419.07  5631.1  418.69  5634.6  414.51  5639.8  416.27
  5656.7  413.41  5734.9  413.59  5785.9  421.03    5823  423.32  5856.6  425.06
#Mann= 10 ,-1 , 0
  4163.8     .05       0  4488.9    .045       0  4756.8     .05       0
  4855.3     .07       0    4969     .05       0  5013.1     .05       0
  5029.4     .05       0    5538     .07       0  5656.7     .12       0
    5823     .05       0
Bank Sta=5013.1,5029.4
XS Rating Curve= 0 ,0
Exp/Cntr=0.3,0.1

Type RM Length L Ch R = 1 ,34344   ,475,475,475
BEGIN DESCRIPTION:
BUCK BRANCH 57.0
END DESCRIPTION:
XS GIS Cut Line= 3
        2477875.       13820125.        2477725.       13820275.
      2476525.03     13820774.99
#Sta/Elev= 30
  4784.1  430.38  4832.6  424.21  4911.8  417.03  4967.9  412.35  4992.7  403.47
  5010.9  401.75  5058.5  403.15  5063.5  401.42    5064  400.92  5080.6  401.42
    5089  401.73  5104.6   402.3    5117  404.89  5140.9  406.89  5225.4  406.35
  5386.2  405.69  5516.2  407.41  5814.7  420.63  5889.4  417.75  5920.9  417.02
  5960.4  418.61  5968.5  414.64  5982.1  413.31  6021.3  413.42  6080.1  414.12
  6098.5  418.16  6103.9  417.43  6122.4  421.12  6168.9  422.85  6296.2  427.68
#Mann= 10 ,-1 , 0
  4784.1     .05       0  4832.6     .12       0  4911.8      .1       0
  5063.5     .05       0  5080.6      .1       0    5089     .07       0
  5225.4     .05       0  5889.4     .07       0  6021.3     .12       0
  6168.9     .05       0
Bank Sta=5063.5,5080.6
XS Rating Curve= 0 ,0
Exp/Cntr=0.3,0.1

Type RM Length L Ch R = 1 ,33869   ,420,420,420
BEGIN DESCRIPTION:
BUCK BRANCH 56.0
END DESCRIPTION:
XS GIS Cut Line= 3
      2477874.97     13819425.03      2477411.72     13820026.98
      2476925.02     13820524.98
#Sta/Elev= 30
  4286.3  449.63  4486.5  435.41  4592.5  424.72  4600.7  423.34    4607  419.68
  4614.3  418.21  4627.8  418.36  4649.9  421.51  4657.8  419.22  4779.3  409.83
  4791.8  409.76  4812.2  406.44  4820.8  407.42  4841.7  404.38  4849.9  403.94
  4856.2  405.76  4872.1   403.9    4935  401.16  4999.3  402.05  5005.3  399.95
  5005.8  399.45  5022.5  399.95  5028.4  401.61  5063.4  403.94    5397  408.94
  5442.5   409.6  5494.7  412.99  5586.7  414.06  5636.1  417.93  5742.2  420.64
#Mann= 10 ,-1 , 0
  4286.3     .12       0  4649.9      .1       0  4657.8     .12       0
  4779.3     .05       0  4812.2      .1       0  4872.1     .05       0
  5005.3     .05       0  5022.5     .05       0    5397     .12       0
  5442.5     .05       0
Bank Sta=5005.3,5022.5
XS Rating Curve= 0 ,0
Exp/Cntr=0.3,0.1

Type RM Length L Ch R = 1 ,33449   ,453,453,453
BEGIN DESCRIPTION:
BUCK BRANCH 55.0
END DESCRIPTION:
XS GIS Cut Line= 3
      2477775.02     13819224.98        2477175.       13819675.
      2476575.02     13820124.98
#Sta/Elev= 30
  4254.5  458.44  4262.5  457.43  4282.7  455.65  4404.5  438.01  4514.1  428.29
  4576.4  421.89  4639.9  417.64  4682.7  413.21  4811.8  404.66  4882.7  403.43
  4897.2  401.62  4911.8  396.69    4941  396.53  4947.2  400.19  4954.5  400.75
  4976.4  400.03  4982.4  395.92  4982.9  395.42  4999.6  395.92  5001.4  399.44
  5026.4  402.74  5054.3  403.05  5104.5  402.75  5362.4  408.34  5528.3  413.26
  5554.5  415.04  5604.5  415.82  5632.7  417.95  5686.3  419.08  5754.5  421.77
#Mann= 10 ,-1 , 0
  4254.5     .07       0  4262.5     .12       0  4514.1     .07       0
  4639.9      .1       0  4982.4     .05       0  4999.6      .1       0
  5054.3     .07       0  5362.4     .05       0  5528.3     .07       0
  5686.3     .12       0
Bank Sta=4982.4,4999.6
XS Rating Curve= 0 ,0
Exp/Cntr=0.3,0.1

Type RM Length L Ch R = 1 ,32996   ,431,431,431
BEGIN DESCRIPTION:
BUCK BRANCH 54.0
END DESCRIPTION:
XS GIS Cut Line= 3
        2477525.       13819175.        2476925.       13819325.
      2476424.98     13819475.01
#Sta/Elev= 30
  4385.9  435.62  4396.2  434.29  4403.9  432.04  4438.1  427.58  4527.6   418.5
  4532.8  419.01  4540.5  416.81  4561.1  414.47  4615.4  411.49  4692.6  405.76
  4767.3  402.75  4780.2  403.38  4829.1  399.83  4849.7  399.41    4891  400.48
  4898.7  399.24  4921.9  398.87  4963.1   400.3  4972.5  394.75    4973  394.25
  4989.8  394.75  4994.1  398.77    5007  399.97  5014.8  402.38  5035.7  403.35
    5054  401.26    5081  402.83  5130.5  402.58  5254.9  405.51  5526.4  416.12
#Mann= 6 ,-1 , 0
  4385.9     .12       0  4438.1     .07       0  4615.4      .1       0
  4972.5     .05       0  4989.8      .1       0    5081     .05       0
Bank Sta=4972.5,4989.8
XS Rating Curve= 0 ,0
Exp/Cntr=0.3,0.1

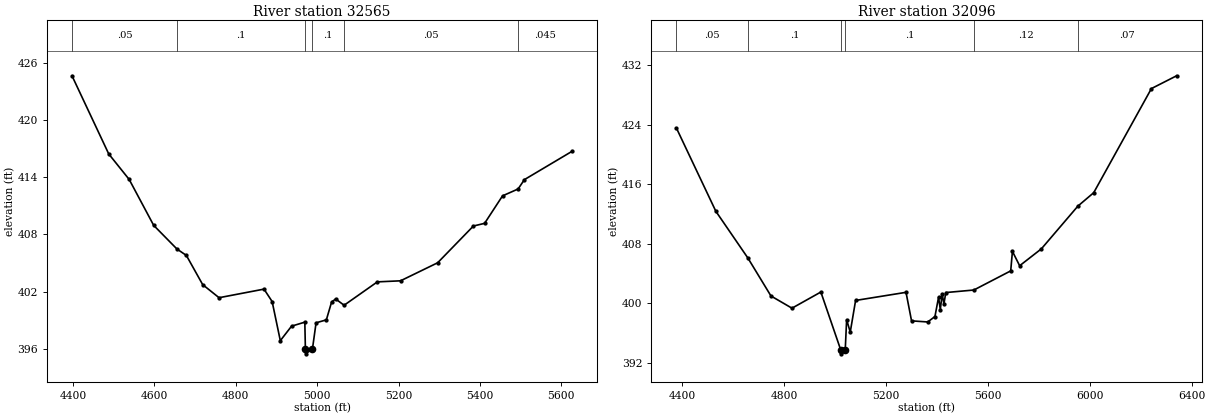
Type RM Length L Ch R = 1 ,32565   ,469,469,469
BEGIN DESCRIPTION:
BUCK BRANCH 53.0
END DESCRIPTION:
XS GIS Cut Line= 3
      2477425.02       13818975.        2476825.       13818925.
        2476275.       13819225.
#Sta/Elev= 30
  4397.8  424.62  4488.1  416.43  4538.3  413.76  4598.5  408.95  4655.7  406.47
  4678.8   405.8  4718.9  402.74  4759.1  401.37  4869.5  402.27  4889.5  400.97
  4909.6  396.87  4937.2  398.39  4969.8  398.81  4971.2  395.99  4971.7  395.49
  4988.5  395.99  4997.4  398.74  5022.7  399.05  5035.5  400.91  5045.5  401.24
  5066.3  400.58    5148  403.03  5204.9  403.14  5296.1  405.03  5383.9  408.88
  5411.4  409.16  5455.5  412.04  5493.7  412.76  5509.2  413.74  5626.4  416.71
#Mann= 6 ,-1 , 0
  4397.8     .05       0  4655.7      .1       0  4971.2     .05       0
  4988.5      .1       0  5066.3     .05       0  5493.7    .045       0
Bank Sta=4971.2,4988.5
XS Rating Curve= 0 ,0
Exp/Cntr=0.3,0.1

Type RM Length L Ch R = 1 ,32096   ,478,478,478
BEGIN DESCRIPTION:
BUCK BRANCH 52.0
END DESCRIPTION:
XS GIS Cut Line= 3
      2477474.97     13818624.99        2476875.       13818475.
        2475975.       13817475.
#Sta/Elev= 30
  4376.9  423.52  4531.5  412.36  4657.2  406.09  4747.9  400.99  4830.4  399.35
  4943.8  401.52  5022.1  393.72  5022.6  393.22  5039.5  393.72    5045  397.81
  5059.2  396.14  5080.2  400.39  5278.2  401.48  5299.9  397.65  5363.4   397.5
  5391.8  398.23    5406  400.83  5412.8  399.16  5420.2  401.27    5427  399.92
  5434.4  401.45  5544.5  401.79  5689.3  404.36    5696  406.98  5724.4  405.05
  5809.7  407.32  5953.1  413.06  6015.2  414.86  6241.7  428.84  6340.7  430.56
#Mann= 6 ,-1 , 0
  4376.9     .05       0  4657.2      .1       0  5022.1     .05       0
  5039.5      .1       0  5544.5     .12       0  5953.1     .07       0
Bank Sta=5022.1,5039.5
XS Rating Curve= 0 ,0
Exp/Cntr=0.3,0.1