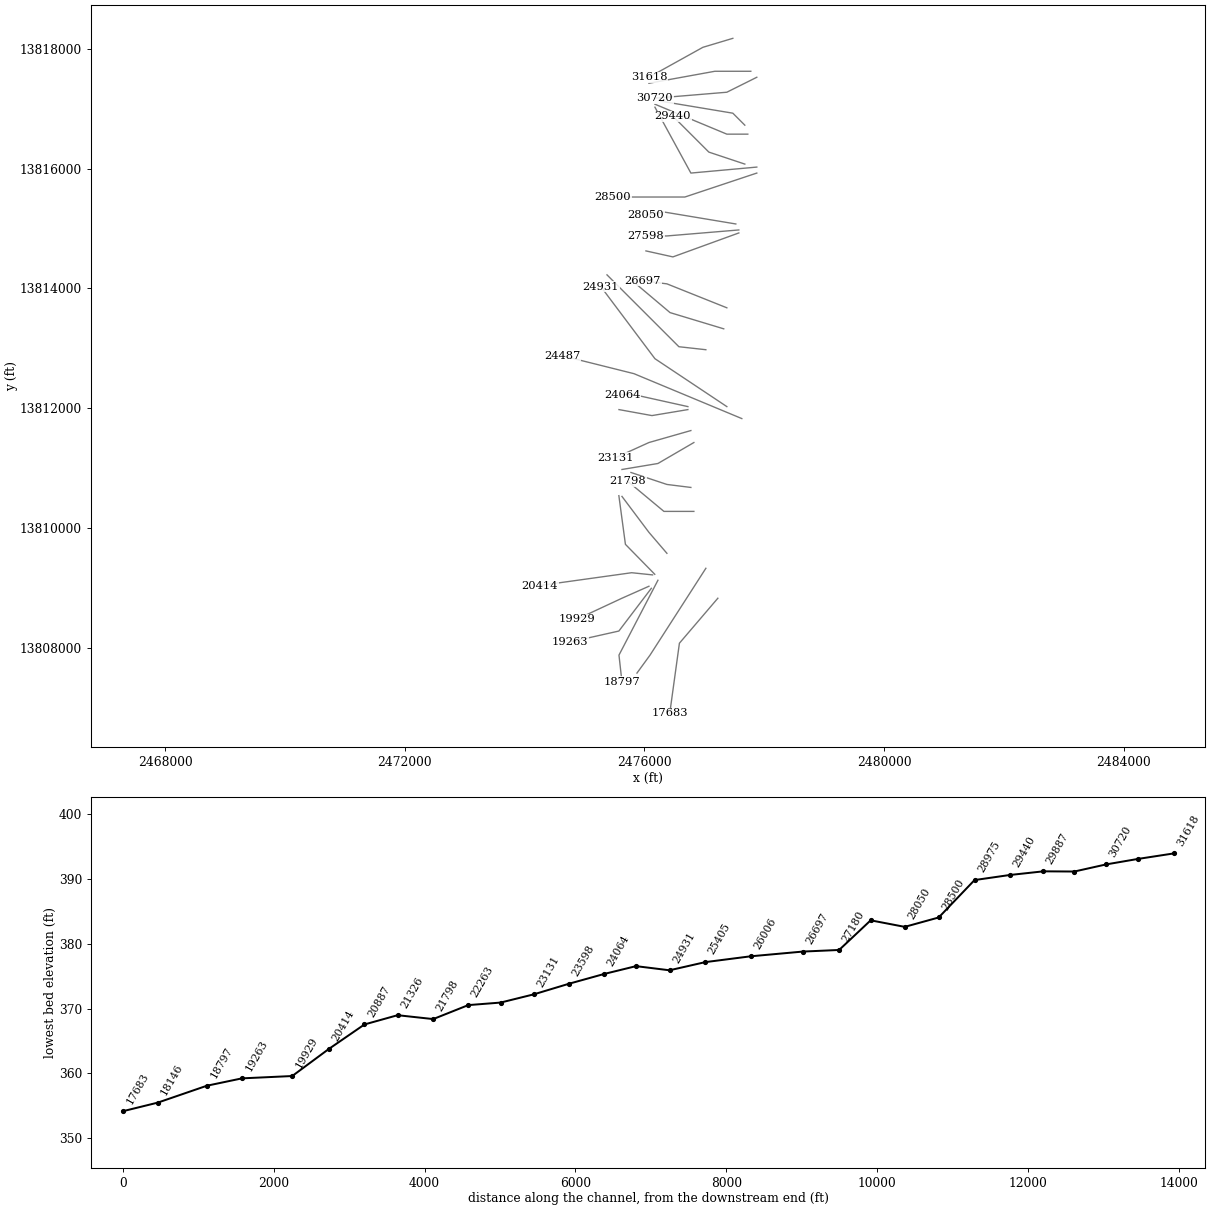
HEC-RAS study BUCK BRANCH.prj: BUCK BRANCH Base Level Engineering

--- BUCK BRANCH.g01 (geometry) --- (continued)

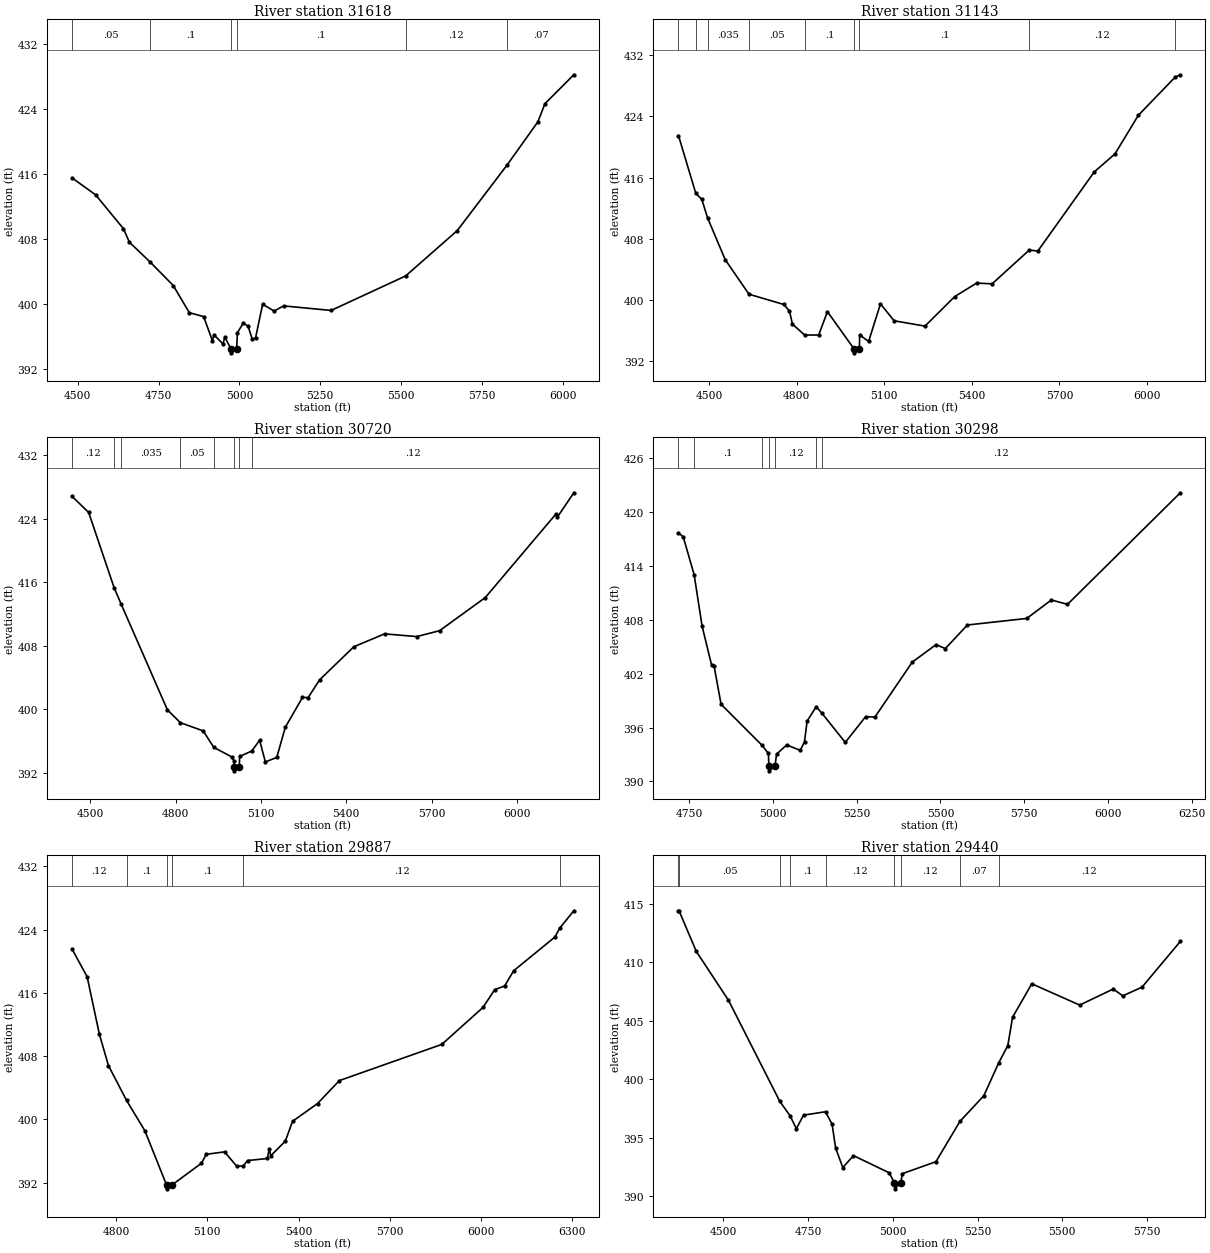
Type RM Length L Ch R = 1 ,31618   ,475,475,475
BEGIN DESCRIPTION:
BUCK BRANCH 51.0
END DESCRIPTION:
XS GIS Cut Line= 3
      2477475.01       13818175.        2476975.       13818025.
      2476074.99       13817525.
#Sta/Elev= 30
  4482.2  415.52  4555.3  413.43  4641.4  409.26  4659.7   407.6  4724.5  405.13
  4795.4  402.26    4845  398.92  4889.4  398.43  4916.4  395.47  4921.6  396.17
  4949.4  395.06  4954.6  395.93  4973.5  394.47    4974  393.97  4991.4  394.47
  4993.8  396.45  5012.2  397.65  5027.1  397.22  5039.7  395.63    5050  395.83
  5071.7  399.95  5107.2  399.12  5136.9  399.75  5283.4  399.19    5514  403.44
  5673.4  409.02  5827.6   417.1  5922.8  422.42  5944.6  424.65  6033.8  428.21
#Mann= 6 ,-1 , 0
  4482.2     .05       0  4724.5      .1       0  4973.5     .05       0
  4991.4      .1       0    5514     .12       0  5827.6     .07       0
Bank Sta=4973.5,4991.4
XS Rating Curve= 0 ,0
Exp/Cntr=0.3,0.1

Type RM Length L Ch R = 1 ,31143   ,423,423,423
BEGIN DESCRIPTION:
BUCK BRANCH 50.0
END DESCRIPTION:
XS GIS Cut Line= 3
      2477775.04       13817625.        2477175.       13817625.
      2476074.98       13817425.
#Sta/Elev= 30
  4395.9  421.48  4455.2  413.93  4475.9  413.15  4495.3  410.75  4555.9  405.28
  4637.3  400.77  4755.9  399.44  4775.9  398.59  4785.9  396.88  4827.6  395.44
  4875.9  395.45  4905.9  398.49  4997.2  393.62  4997.7  393.12  5015.1  393.62
  5016.3  395.47  5046.8   394.6  5087.4  399.51  5134.4   397.3  5239.9  396.61
  5341.5  400.46  5416.5  402.22  5469.8  402.13    5597  406.54  5626.1   406.4
  5819.2  416.73  5890.4  419.09  5970.4  424.13  6096.3   429.1    6114  429.41
#Mann= 9 ,-1 , 0
  4395.9     .12       0  4455.2     .05       0  4495.3    .035       0
  4637.3     .05       0  4827.6      .1       0  4997.2     .05       0
  5015.1      .1       0    5597     .12       0  6096.3     .07       0
Bank Sta=4997.2,5015.1
XS Rating Curve= 0 ,0
Exp/Cntr=0.3,0.1

Type RM Length L Ch R = 1 ,30720   ,422,422,422
BEGIN DESCRIPTION:
BUCK BRANCH 49.0
END DESCRIPTION:
XS GIS Cut Line= 3
      2477875.03     13817525.01        2477375.       13817275.
        2476175.       13817175.
#Sta/Elev= 30
  4436.1  426.85  4494.8  424.82  4584.1  415.35  4608.5  413.31  4771.5  399.95
  4817.4  398.33  4897.3   397.3  4934.3  395.23  4997.7  394.02  5005.2  393.51
  5006.2  392.77  5006.7  392.27  5024.2  392.77  5025.2  394.08    5068  394.77
  5095.5  396.13  5115.6  393.39  5155.7  393.96  5185.8  397.76    5246  401.51
  5266.1   401.5  5306.2  403.73  5426.6   407.9  5534.5  409.52  5647.4  409.18
  5727.7  409.92  5888.2  414.09  6136.6  424.62  6141.6  424.22  6199.3  427.29
#Mann= 8 ,-1 , 0
  4436.1     .12       0  4584.1     .05       0  4608.5    .035       0
  4817.4     .05       0  4934.3      .1       0  5006.2     .05       0
  5024.2      .1       0    5068     .12       0
Bank Sta=5006.2,5024.2
XS Rating Curve= 0 ,0
Exp/Cntr=0.3,0.1

Type RM Length L Ch R = 1 ,30298   ,411,411,411
BEGIN DESCRIPTION:
BUCK BRANCH 48.0
END DESCRIPTION:
XS GIS Cut Line= 3
      2477674.99     13816725.01        2477475.       13816925.
      2476274.99       13817125.
#Sta/Elev= 30
  4717.2  417.69  4731.3  417.27    4764  413.04  4787.9  407.28  4816.2  402.95
  4823.3   402.9  4844.5  398.59    4966  394.05  4985.9  393.11  4987.3  391.67
  4987.8  391.17  5005.6  391.67  5010.2  393.03  5040.6  394.06  5081.1  393.45
  5093.8  394.42  5101.4   396.7  5128.4  398.31  5145.1  397.63  5215.5  394.34
  5276.3  397.21  5304.2  397.17  5415.7  403.29  5486.7  405.24  5514.5   404.8
  5580.4  407.43  5757.8  408.16  5831.3  410.22  5879.5  409.73  6216.6  422.17
#Mann= 7 ,-1 , 0
  4717.2     .07       0    4764      .1       0    4966     .12       0
  4987.3     .05       0  5005.6     .12       0  5128.4      .1       0
  5145.1     .12       0
Bank Sta=4987.3,5005.6
XS Rating Curve= 0 ,0
Exp/Cntr=0.3,0.1

Type RM Length L Ch R = 1 ,29887   ,447,447,447
BEGIN DESCRIPTION:
BUCK BRANCH 47.0
END DESCRIPTION:
XS GIS Cut Line= 3
        2477725.       13816575.        2477375.       13816575.
        2476175.       13817075.
#Sta/Elev= 30
  4655.1  421.57  4705.1  418.04  4745.1  410.79  4775.1   406.8  4834.6  402.39
  4895.1  398.53    4966   391.7  4966.5   391.2  4984.3   391.7  5080.9  394.44
  5096.6  395.57  5156.8  395.88  5197.4  394.04  5218.6  394.12  5232.6  394.78
  5297.6  395.04  5303.6   396.2    5309   395.4  5356.6  397.23  5380.5  399.75
  5462.8     402  5534.3   404.9  5871.2  409.48  6006.6  414.16  6045.1  416.41
  6077.6  416.87  6107.4   418.8  6242.8  423.06  6258.8  424.19  6305.1  426.39
#Mann= 6 ,-1 , 0
  4655.1     .12       0  4834.6      .1       0    4966     .05       0
  4984.3      .1       0  5218.6     .12       0  6258.8     .07       0
Bank Sta=4966,4984.3
XS Rating Curve= 0 ,0
Exp/Cntr=0.3,0.1

Type RM Length L Ch R = 1 ,29440   ,465,465,465
BEGIN DESCRIPTION:
BUCK BRANCH 46.0
END DESCRIPTION:
XS GIS Cut Line= 3
      2477675.03     13816074.99        2477075.       13816275.
      2476475.01     13816874.99
#Sta/Elev= 30
  4367.5   414.4  4369.2   414.4  4420.2  410.92  4515.1  406.75  4666.6   398.1
  4696.6  396.89  4715.4  395.77  4736.5  396.93  4801.4  397.22  4820.8  396.16
  4831.3  394.12  4852.4  392.45    4884  393.47  4989.4     392    5005  391.13
  5005.5  390.63  5023.3  391.13  5028.3  391.93  5127.3  392.95  5198.2   396.4
  5268.7  398.59    5312  401.37  5339.4  402.88  5353.5   405.3  5410.1  408.16
  5551.5  406.34  5650.5  407.71  5678.8  407.13  5735.4  407.87  5848.5  411.78
#Mann= 9 ,-1 , 0
  4367.5     .07       0  4369.2     .05       0  4666.6     .07       0
  4696.6      .1       0  4801.4     .12       0    5005     .05       0
  5023.3     .12       0  5198.2     .07       0    5312     .12       0
Bank Sta=5005,5023.3
XS Rating Curve= 0 ,0
Exp/Cntr=0.3,0.1

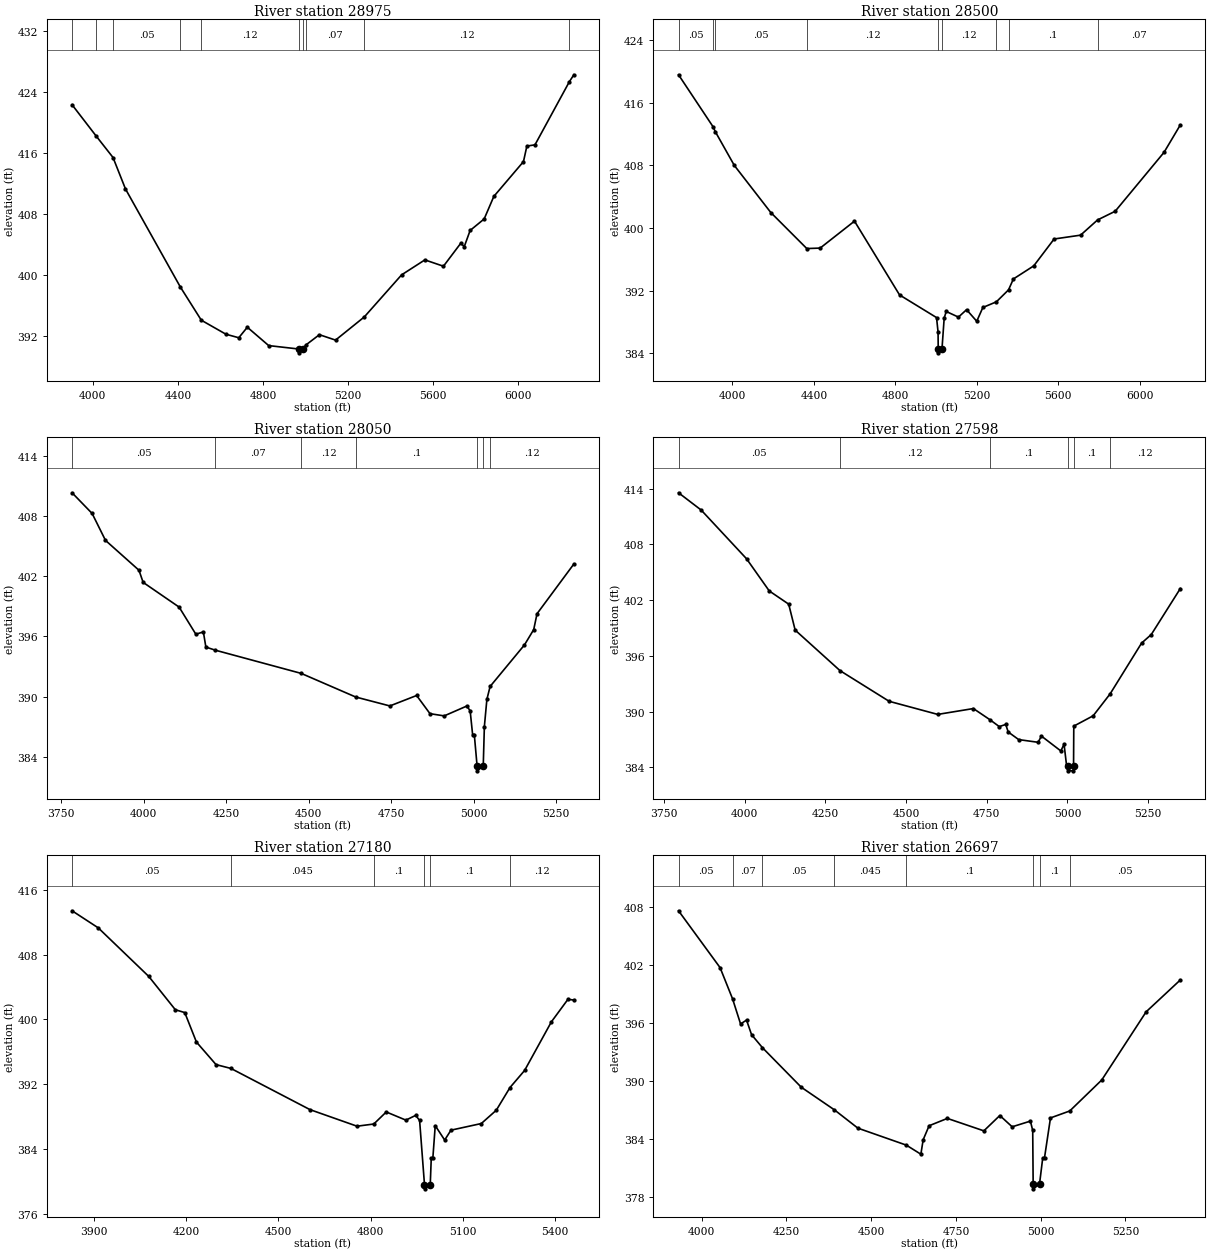
Type RM Length L Ch R = 1 ,28975   ,475,475,475
BEGIN DESCRIPTION:
BUCK BRANCH 45.0
END DESCRIPTION:
XS GIS Cut Line= 3
      2477874.99       13816025.        2476775.       13815925.
      2476175.01     13817024.98
#Sta/Elev= 30
  3902.9  422.39  4016.8  418.26  4095.3  415.47  4153.9  411.34  4411.5  398.49
  4510.1  394.13  4625.9  392.29  4686.1  391.83  4726.3  393.21  4826.7   390.8
  4968.2  390.35  4968.7  389.85  4986.5  390.35  5002.3   390.9  5064.9  392.23
  5140.8  391.52  5275.9  394.56  5451.2  400.08  5560.4  402.04  5647.7  401.21
  5729.3  404.23  5745.5  403.78    5773   405.9    5839  407.41  5884.5  410.37
  6023.6  414.93  6039.7  416.97  6077.7  417.13  6239.6  425.43  6260.4  426.32
#Mann= 10 ,-1 , 0
  3902.9     .12       0  4016.8     .07       0  4095.3     .05       0
  4411.5      .1       0  4510.1     .12       0  4968.2     .05       0
  4986.5     .12       0  5002.3     .07       0  5275.9     .12       0
  6239.6     .07       0
Bank Sta=4968.2,4986.5
XS Rating Curve= 0 ,0
Exp/Cntr=0.3,0.1

Type RM Length L Ch R = 1 ,28500   ,450,450,450
BEGIN DESCRIPTION:
BUCK BRANCH 44.0
END DESCRIPTION:
XS GIS Cut Line= 3
      2477874.99       13815925.        2476675.       13815525.
        2475475.       13815525.
#Sta/Elev= 30
  3735.2  419.56  3904.9  412.92  3915.4  412.32  4009.2  407.99  4188.4  401.98
  4365.3  397.38  4430.9  397.44  4599.5  400.88  4820.9  391.46  5002.6  388.57
  5010.1  386.71  5010.8  384.57  5011.3  384.07  5029.3  384.57  5040.1   388.5
  5050.1  389.35  5110.1  388.63  5150.1  389.58  5200.1   388.1  5230.1  389.86
  5296.5  390.58  5356.2  392.11  5380.1   393.5  5480.1  395.17  5580.1   398.6
  5710.1  399.09  5793.4  401.03  5880.1  402.14  6120.1  409.66  6200.1  413.16
#Mann= 9 ,-1 , 0
  3735.2     .05       0  3904.9     .07       0  3915.4     .05       0
  4365.3     .12       0  5010.8     .05       0  5029.3     .12       0
  5296.5     .12       0  5356.2      .1       0  5793.4     .07       0
Bank Sta=5010.8,5029.3
XS Rating Curve= 0 ,0
Exp/Cntr=0.3,0.1

Type RM Length L Ch R = 1 ,28050   ,452,452,452
BEGIN DESCRIPTION:
BUCK BRANCH 43.0
END DESCRIPTION:
XS GIS Cut Line= 3
      2477524.96     13815075.01        2476325.       13815275.
      2476024.95     13815224.99
#Sta/Elev= 30
    3783   410.3  3843.8  408.24  3884.3  405.56  3985.7  402.59  3998.4  401.38
  4107.4  398.92  4158.1  396.22  4180.9  396.45  4188.5  394.94  4217.2  394.63
  4477.4  392.32  4642.5  389.97  4746.1  389.08  4827.2  390.12  4867.7  388.31
  4910.8  388.09  4979.2  389.07  4989.4   388.6    4997  386.19  5002.1  386.19
  5010.4  383.12  5010.9  382.62  5029.1  383.12  5032.5  387.03  5040.1  389.73
  5049.9  391.02  5154.1  395.16    5182  396.68  5192.1  398.26  5303.7  403.21
#Mann= 7 ,-1 , 0
    3783     .05       0  4217.2     .07       0  4477.4     .12       0
  4642.5      .1       0  5010.4     .05       0  5029.1      .1       0
  5049.9     .12       0
Bank Sta=5010.4,5029.1
XS Rating Curve= 0 ,0
Exp/Cntr=0.3,0.1

Type RM Length L Ch R = 1 ,27598   ,418,418,418
BEGIN DESCRIPTION:
BUCK BRANCH 42.0
END DESCRIPTION:
XS GIS Cut Line= 3
        2477575.       13814975.        2476375.       13814875.
      2476024.96       13814875.
#Sta/Elev= 30
  3795.5  413.54  3865.7  411.68  4006.2  406.44  4076.5  402.98  4136.7  401.56
  4156.7  398.77  4295.6  394.41  4447.8  391.11  4598.3   389.7  4708.7  390.33
  4759.1  389.15  4788.9  388.39    4809  388.62  4816.5  387.81  4849.1  386.99
  4909.3   386.7  4919.4  387.37  4979.6  385.77  4989.6  386.49  4997.2  384.25
  5000.3  384.13  5000.8  383.63  5018.5  383.63    5019  384.13  5019.7  388.44
  5079.7  389.55  5132.3  391.91  5229.7  397.37  5259.7  398.29  5349.7  403.24
#Mann= 6 ,-1 , 0
  3795.5     .05       0  4295.6     .12       0  4759.1      .1       0
  5000.3     .05       0    5019      .1       0  5132.3     .12       0
Bank Sta=5000.3,5019
XS Rating Curve= 0 ,0
Exp/Cntr=0.3,0.1

Type RM Length L Ch R = 1 ,27180   ,483,483,483
BEGIN DESCRIPTION:
BUCK BRANCH 41.0
END DESCRIPTION:
XS GIS Cut Line= 3
      2477574.95     13814924.98        2476475.       13814525.
        2476025.       13814625.
#Sta/Elev= 30
  3829.2  413.41  3914.3   411.3  4078.5   405.3    4165  401.18  4195.6  400.83
  4233.5  397.19  4297.3   394.4  4345.6  393.93  4602.6  388.84  4755.6  386.79
  4810.1  387.06  4850.7  388.55  4914.5  387.54  4946.4  388.13  4959.1   387.5
    4975  379.55  4975.5  379.05  4993.7  379.55    4997  382.87  5002.2  382.87
  5009.9  386.86  5040.6  385.08  5061.1   386.3  5159.7  387.12  5208.3  388.76
    5253  391.57  5300.5  393.68  5387.6  399.69  5441.4  402.47  5460.6  402.38
#Mann= 6 ,-1 , 0
  3829.2     .05       0  4345.6    .045       0  4810.1      .1       0
    4975     .05       0  4993.7      .1       0    5253     .12       0
Bank Sta=4975,4993.7
XS Rating Curve= 0 ,0
Exp/Cntr=0.3,0.1

Type RM Length L Ch R = 1 ,26697   ,691,691,691
BEGIN DESCRIPTION:
BUCK BRANCH 40.0
END DESCRIPTION:
XS GIS Cut Line= 3
      2477374.96     13813675.02        2476375.       13814075.
        2475975.       13814125.
#Sta/Elev= 30
  3931.7  407.62  4054.2  401.73    4091   398.5  4114.7  395.89  4132.3  396.29
  4147.1  394.78  4179.2  393.43  4293.8  389.33  4391.7  386.98  4460.7  385.09
  4603.6  383.33  4646.5  382.39  4653.3  383.89  4670.8  385.34  4724.6   386.1
  4832.3  384.81  4879.4   386.4  4915.8  385.23  4969.6  385.82  4976.4  384.85
  4977.7   379.3  4978.2   378.8  4996.5   379.3    5006  382.02  5011.2  382.02
  5028.8  386.15  5085.6  386.87    5180  390.08    5311  397.15  5411.8  400.45
#Mann= 8 ,-1 , 0
  3931.7     .05       0    4091     .07       0  4179.2     .05       0
  4391.7    .045       0  4603.6      .1       0  4977.7     .05       0
  4996.5      .1       0  5085.6     .05       0
Bank Sta=4977.7,4996.5
XS Rating Curve= 0 ,0
Exp/Cntr=0.3,0.1

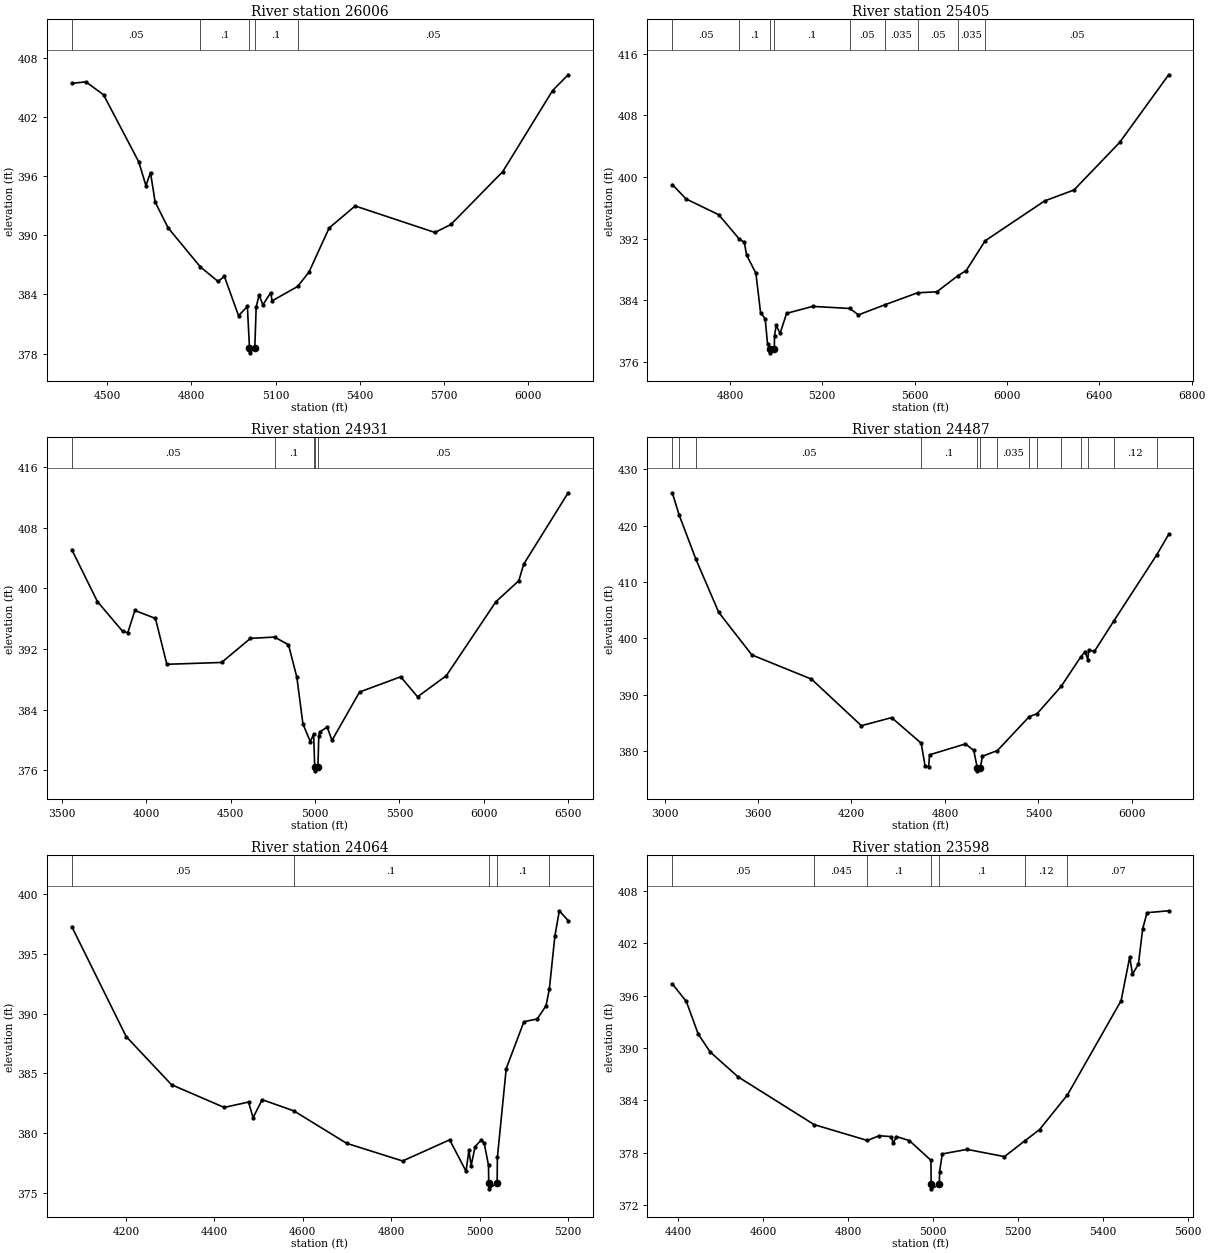
Type RM Length L Ch R = 1 ,26006   ,601,601,601
BEGIN DESCRIPTION:
X18364
END DESCRIPTION:
XS GIS Cut Line= 3
      2477323.14     13813323.86      2476427.34     13813594.69
      2475792.63     13814130.54
#Sta/Elev= 30
  4374.8  405.43  4425.1  405.58  4487.8  404.27  4613.1  397.46  4638.6  395.05
  4654.9  396.37  4671.5  393.37  4717.6  390.76  4832.2   386.8  4895.2  385.32
  4917.8  385.83  4968.3  381.84  4999.7  382.78  5007.2  378.57  5007.7  378.07
  5026.1  378.57    5031  382.72  5041.5  383.95  5054.8  382.93  5082.6  384.18
  5087.8  383.35  5178.7  384.81  5219.1  386.28  5290.7  390.75  5383.3  392.98
  5667.1  390.29  5723.9   391.1  5908.6  396.47  6085.9   404.7  6141.3   406.3
#Mann= 5 ,-1 , 0
  4374.8     .05       0  4832.2      .1       0  5007.2     .05       0
  5026.1      .1       0  5178.7     .05       0
Bank Sta=5007.2,5026.1
XS Rating Curve= 0 ,0
Exp/Cntr=0.3,0.1

Type RM Length L Ch R = 1 ,25405   ,474,474,474
BEGIN DESCRIPTION:
BUCK BRANCH 39.0
END DESCRIPTION:
XS GIS Cut Line= 3
      2477024.96       13812975.        2476575.       13813025.
      2475374.99     13814225.01
#Sta/Elev= 30
  4550.5  399.01  4610.8  397.14  4751.7   395.1  4840.7  391.95  4862.4   391.5
  4872.4  389.86  4912.7   387.5  4932.8   382.4  4952.9  381.59    4963  378.33
  4973.7  377.67  4974.2  377.17  4992.6  377.67  4993.2   379.4  5000.7  380.72
  5017.4  379.71  5045.7   382.3  5158.8   383.2    5319  382.93  5356.8   382.1
  5471.2  383.41  5613.2  384.97  5696.2  385.09    5786  387.15  5823.5  387.85
  5905.3  391.71  6162.9  396.89  6290.2  398.31  6488.2  404.49  6700.3  413.27
#Mann= 9 ,-1 , 0
  4550.5     .05       0  4840.7      .1       0  4973.7     .05       0
  4992.6      .1       0    5319     .05       0  5471.2    .035       0
  5613.2     .05       0    5786    .035       0  5905.3     .05       0
Bank Sta=4973.7,4992.6
XS Rating Curve= 0 ,0
Exp/Cntr=0.3,0.1

Type RM Length L Ch R = 1 ,24931   ,444,444,444
BEGIN DESCRIPTION:
BUCK BRANCH 38.0
END DESCRIPTION:
XS GIS Cut Line= 3
      2477374.99       13812025.        2476175.       13812825.
      2475275.01     13814024.99
#Sta/Elev= 30
  3557.8   405.1  3709.5  398.25  3859.8   394.3  3889.8  394.15  3931.9  397.07
  4053.6  396.02  4121.2  389.97  4445.7  390.21  4616.9  393.39  4759.5  393.56
  4842.3  392.55  4891.8  388.26  4927.9  382.09  4971.5  379.77  4991.1  380.74
  4997.9  376.41  4998.4  375.91  5016.8  376.41  5021.9  380.57  5028.1  381.06
  5071.9  381.68    5100  379.93  5263.6  386.31  5507.3  388.32  5607.3  385.68
  5778.1  388.47  6071.9  398.23  6207.3  400.99  6236.5  403.18    6500   412.6
#Mann= 5 ,-1 , 0
  3557.8     .05       0  4759.5      .1       0  4991.1     .05       0
  4997.9     .05       0  5016.8     .05       0
Bank Sta=4997.9,5016.8
XS Rating Curve= 0 ,0
Exp/Cntr=0.3,0.1

Type RM Length L Ch R = 1 ,24487   ,423,423,423
BEGIN DESCRIPTION:
BUCK BRANCH 37.0
END DESCRIPTION:
XS GIS Cut Line= 3
      2477625.01     13811824.99        2475825.       13812575.
      2474625.05     13812874.99
#Sta/Elev= 30
  3049.7  425.82  3093.4  421.91  3201.4  414.03  3348.2  404.62  3560.5  397.09
  3943.5   392.8  4263.6  384.55    4458  385.98  4648.2  381.44    4672  377.49
  4695.8  377.23  4701.3  379.39    4932  381.32  4985.1  380.18  5008.3  377.05
  5008.8  376.55  5027.2  377.05  5040.9  379.14  5137.5  380.15    5342  386.17
  5391.8  386.67  5546.5  391.51  5670.8  396.68  5700.6  397.68  5717.2  396.26
  5723.8  397.95  5759.9  397.71  5886.1  403.17  6160.1  414.82  6236.6  418.44
#Mann= 14 ,-1 , 0
  3049.7     .12       0  3093.4    .035       0  3201.4     .05       0
  4648.2      .1       0  5008.3     .05       0  5027.2      .1       0
  5137.5    .035       0    5342     .07       0  5391.8     .05       0
  5546.5     .07       0  5670.8      .1       0  5717.2     .07       0
  5886.1     .12       0  6160.1     .07       0
Bank Sta=5008.3,5027.2
XS Rating Curve= 0 ,0
Exp/Cntr=0.3,0.1

Type RM Length L Ch R = 1 ,24064   ,466,466,466
BEGIN DESCRIPTION:
BUCK BRANCH 36.0
END DESCRIPTION:
XS GIS Cut Line= 3
      2476725.01       13812025.        2475825.       13812225.
      2475624.97       13812225.
#Sta/Elev= 30
  4077.7  397.27  4200.6  388.08  4303.1  384.05  4422.2  382.15  4477.2   382.6
  4487.5  381.29    4508   382.8  4579.7  381.86  4698.8  379.15  4825.5  377.67
  4931.8  379.44  4968.9  376.81  4975.3  378.55  4980.5  377.29  4989.4  378.87
  5002.2  379.39  5009.7   379.2  5019.7   377.3  5020.1  375.84  5020.6  375.34
  5039.2  375.84  5039.7  377.97  5059.7   385.4  5099.7  389.32  5129.7  389.55
  5149.7  390.65  5157.2  392.06  5169.7  396.48  5179.7   398.6  5199.7  397.78
#Mann= 5 ,-1 , 0
  4077.7     .05       0  4579.7      .1       0  5020.1     .05       0
  5039.2      .1       0  5157.2     .07       0
Bank Sta=5020.1,5039.2
XS Rating Curve= 0 ,0
Exp/Cntr=0.3,0.1

Type RM Length L Ch R = 1 ,23598   ,467,467,467
BEGIN DESCRIPTION:
BUCK BRANCH 35.0
END DESCRIPTION:
XS GIS Cut Line= 3
      2476725.02       13811975.        2476125.       13811875.
      2475575.01       13811975.
#Sta/Elev= 30
  4386.7  397.37  4419.7  395.34  4447.5  391.62  4475.4  389.56  4541.3  386.69
  4720.4   381.2  4845.6  379.38  4873.3  379.93  4901.2  379.82  4906.3  379.09
  4913.9  379.83  4944.3  379.37    4995   377.1  4995.5  374.33    4996  373.83
  5014.8  374.33  5015.3  375.79  5021.7  377.84  5080.1  378.36  5167.8  377.53
  5215.5  379.33  5250.4  380.63  5316.1  384.62  5442.2  395.43  5462.5  400.45
  5468.9  398.47  5482.9  399.62    5493   403.7  5503.2  405.53    5554  405.75
#Mann= 7 ,-1 , 0
  4386.7     .05       0  4720.4    .045       0  4845.6      .1       0
  4995.5     .05       0  5014.8      .1       0  5215.5     .12       0
  5316.1     .07       0
Bank Sta=4995.5,5014.8
XS Rating Curve= 0 ,0
Exp/Cntr=0.3,0.1

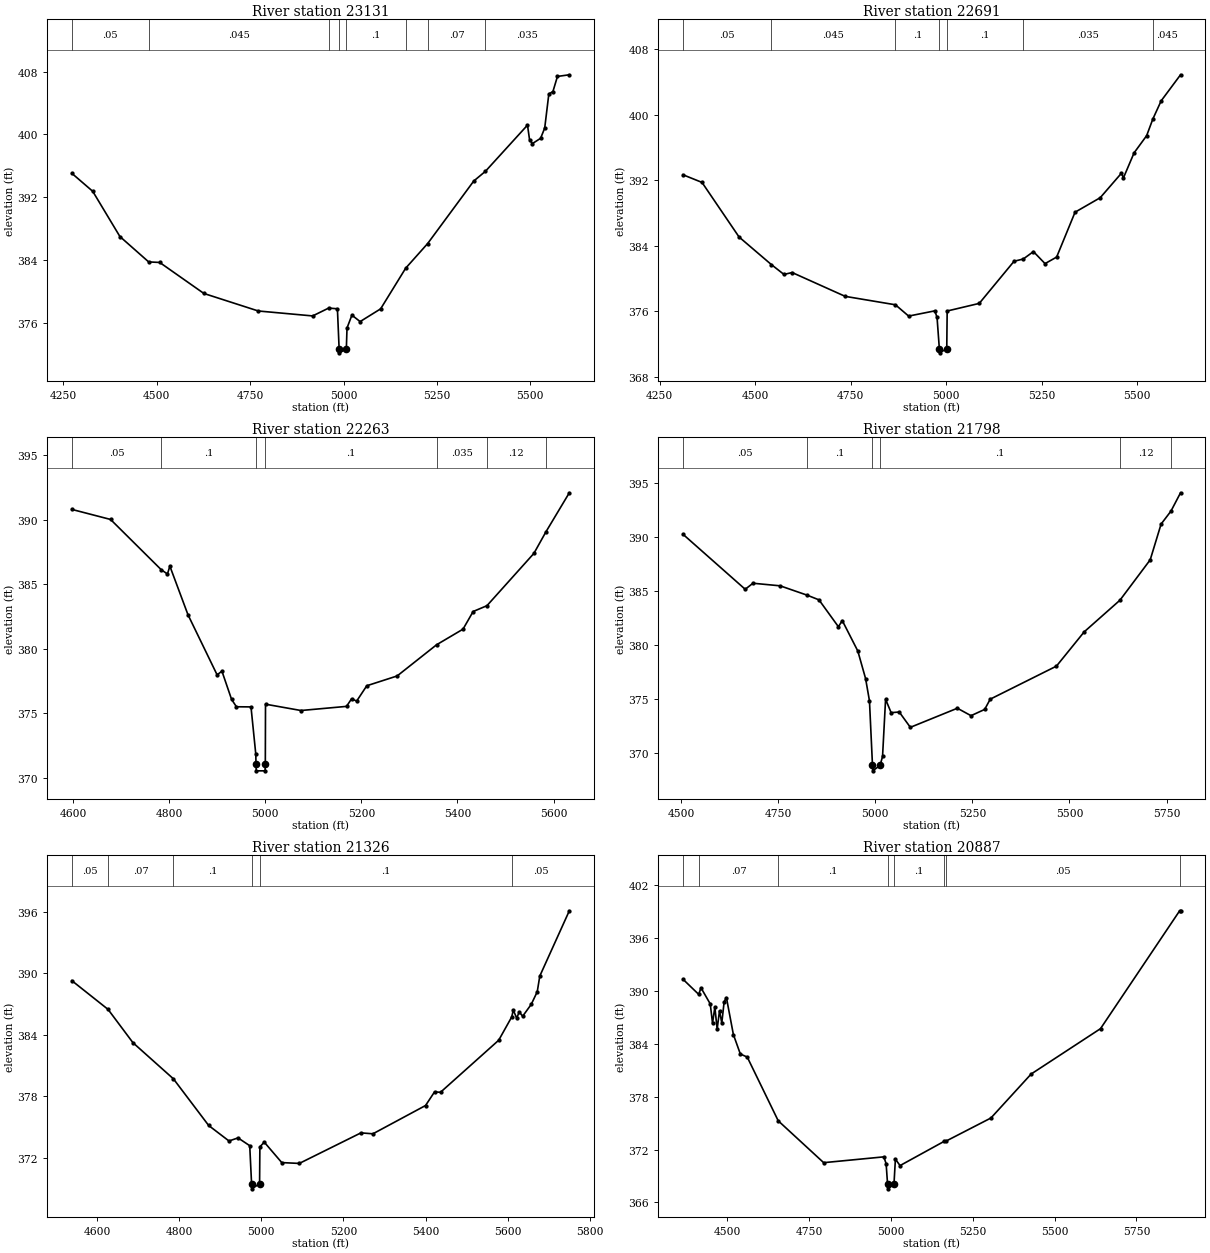
Type RM Length L Ch R = 1 ,23131   ,440,440,440
BEGIN DESCRIPTION:
BUCK BRANCH 34.0
END DESCRIPTION:
XS GIS Cut Line= 3
      2476774.96     13811624.99        2476075.       13811425.
      2475525.02     13811175.01
#Sta/Elev= 30
  4272.4  395.05  4328.3  392.76  4401.1     387  4478.1  383.77  4507.7   383.7
    4626  379.75  4771.6  377.52  4917.2  376.89  4960.1  377.89  4983.5   377.8
  4988.1  372.69  4988.6  372.19  5007.4  372.69  5009.2  375.35  5022.3  376.99
  5044.3  376.17  5099.2  377.79  5166.3  382.97  5225.2  386.11  5348.6  394.07
  5379.9  395.31  5492.5  401.19    5498  399.33  5505.7  398.84  5527.6  399.51
  5538.6  400.82  5549.6  405.15  5560.6  405.47  5572.7  407.39  5604.5   407.6
#Mann= 8 ,-1 , 0
  4272.4     .05       0  4478.1    .045       0  4960.1      .1       0
  4988.1     .05       0  5007.4      .1       0  5166.3     .12       0
  5225.2     .07       0  5379.9    .035       0
Bank Sta=4988.1,5007.4
XS Rating Curve= 0 ,0
Exp/Cntr=0.3,0.1

Type RM Length L Ch R = 1 ,22691   ,428,428,428
BEGIN DESCRIPTION:
BUCK BRANCH 33.0
END DESCRIPTION:
XS GIS Cut Line= 3
      2476824.96     13811424.98        2476225.       13811075.
      2475624.95     13810974.99
#Sta/Elev= 30
  4311.2  392.67  4360.8  391.74  4457.9  385.07  4542.5   381.7  4575.4   380.5
  4596.9  380.73  4735.8  377.82  4867.4  376.79    4902  375.41  4970.6  376.05
  4976.4  375.24  4982.4  371.42  4982.9  370.92  5001.8  371.42  5002.9  376.03
  5086.9  376.96  5178.1  382.11  5202.1  382.38  5228.8  383.29  5259.2  381.82
  5289.6  382.62  5337.8   388.1  5403.7  389.87  5459.4  392.87  5464.5  392.29
  5492.4  395.35  5525.3  397.45  5541.6  399.49  5563.4  401.71  5614.1  404.89
#Mann= 7 ,-1 , 0
  4311.2     .05       0  4542.5    .045       0  4867.4      .1       0
  4982.4     .05       0  5001.8      .1       0  5202.1    .035       0
  5541.6    .045       0
Bank Sta=4982.4,5001.8
XS Rating Curve= 0 ,0
Exp/Cntr=0.3,0.1

Type RM Length L Ch R = 1 ,22263   ,465,465,465
BEGIN DESCRIPTION:
BUCK BRANCH 32.0
END DESCRIPTION:
XS GIS Cut Line= 3
      2476774.97       13810675.        2476375.       13810725.
      2475775.04     13810924.99
#Sta/Elev= 30
  4597.3  390.81  4677.9  390.03  4783.4  386.13  4796.3   385.8  4801.3  386.41
  4839.1  382.63  4899.6  377.98  4909.7  378.26  4929.8  376.07  4939.9   375.5
  4970.2  375.49  4980.2  371.81  4980.6  371.03  4981.1  370.53  4999.5  370.53
    5000  371.03  5000.4   375.7  5074.2  375.21    5169  375.53  5179.6  376.12
  5190.1  375.94  5211.2  377.13  5274.4  377.89  5356.5  380.31  5411.5  381.52
  5432.6  382.89  5461.3  383.34  5559.1   387.4  5583.8  389.05  5632.8   392.1
#Mann= 7 ,-1 , 0
  4597.3     .05       0  4783.4      .1       0  4980.6     .05       0
    5000      .1       0  5356.5    .035       0  5461.3     .12       0
  5583.8    .035       0
Bank Sta=4980.6,5000
XS Rating Curve= 0 ,0
Exp/Cntr=0.3,0.1

Type RM Length L Ch R = 1 ,21798   ,472,472,472
BEGIN DESCRIPTION:
BUCK BRANCH 31.0
END DESCRIPTION:
XS GIS Cut Line= 3
      2476825.04       13810275.        2476325.       13810275.
      2475724.98     13810775.02
#Sta/Elev= 30
    4505  390.28    4665  385.19    4685  385.75    4755  385.51  4824.8  384.64
    4855  384.21    4905  381.72    4915  382.29    4955  379.47    4975  376.92
    4985  374.86  4992.8  368.87  4993.3  368.37  5012.3  368.87  5018.7   369.7
  5026.5     375  5040.8  373.76  5061.7  373.82  5090.3   372.4  5211.4  374.17
  5246.5  373.48  5281.7  374.06    5296  375.01  5466.5  378.07  5538.1  381.25
  5630.1  384.18    5708  387.92    5736  391.23  5761.4  392.43  5786.1  394.13
#Mann= 6 ,-1 , 0
    4505     .05       0  4824.8      .1       0  4992.8     .05       0
  5012.3      .1       0  5630.1     .12       0  5761.4    .045       0
Bank Sta=4992.8,5012.3
XS Rating Curve= 0 ,0
Exp/Cntr=0.3,0.1

Type RM Length L Ch R = 1 ,21326   ,439,439,439
BEGIN DESCRIPTION:
BUCK BRANCH 30.0
END DESCRIPTION:
XS GIS Cut Line= 3
      2476375.01     13809574.99        2476075.       13809925.
      2475624.99     13810525.01
#Sta/Elev= 30
  4538.8  389.28  4626.9  386.48  4687.5  383.23  4786.1   379.7  4871.9  375.15
  4921.3  373.64  4943.3  373.94  4971.8  373.18  4976.3  369.47  4976.8  368.97
  4995.8  369.47  4996.5  373.06  5007.1  373.53  5049.8  371.53  5092.5  371.45
  5242.5  374.43  5271.7  374.34  5399.8   377.1  5421.7  378.43  5436.2  378.39
  5577.9  383.47  5609.7  385.75  5613.3  386.41  5621.7  385.63  5627.9  386.23
  5636.2  385.81  5657.1  386.97  5671.7   388.2  5677.9  389.73  5749.8   396.1
#Mann= 6 ,-1 , 0
  4538.8     .05       0  4626.9     .07       0  4786.1      .1       0
  4976.3     .05       0  4995.8      .1       0  5609.7     .05       0
Bank Sta=4976.3,4995.8
XS Rating Curve= 0 ,0
Exp/Cntr=0.3,0.1

Type RM Length L Ch R = 1 ,20887   ,473,473,473
BEGIN DESCRIPTION:
X18365
END DESCRIPTION:
XS GIS Cut Line= 3
      2476172.15     13809224.88      2475682.55     13809724.89
      2475573.18     13810537.36
#Sta/Elev= 30
    4365  391.32  4412.8  389.61  4419.7  390.36    4448  388.53    4455  386.34
  4462.1  388.16  4469.1  385.66  4476.3  387.75  4483.3  386.36  4490.4  388.76
  4497.4  389.25  4518.7  385.05  4539.9  382.85  4561.1  382.49  4655.7  375.26
  4794.5  370.51  4978.3  371.17  4985.3  370.39  4989.7  368.04  4990.2  367.54
  5009.2  368.04  5013.6  370.91  5027.8  370.18  5163.5  372.95  5169.4  372.98
  5305.4  375.58  5428.2  380.57  5640.1  385.72  5881.9   399.1  5884.6   399.1
#Mann= 8 ,-1 , 0
    4365     .05       0  4412.8     .07       0  4655.7      .1       0
  4989.7     .05       0  5009.2      .1       0  5163.5    .045       0
  5169.4     .05       0  5881.9    .045       0
Bank Sta=4989.7,5009.2
XS Rating Curve= 0 ,0
Exp/Cntr=0.3,0.1

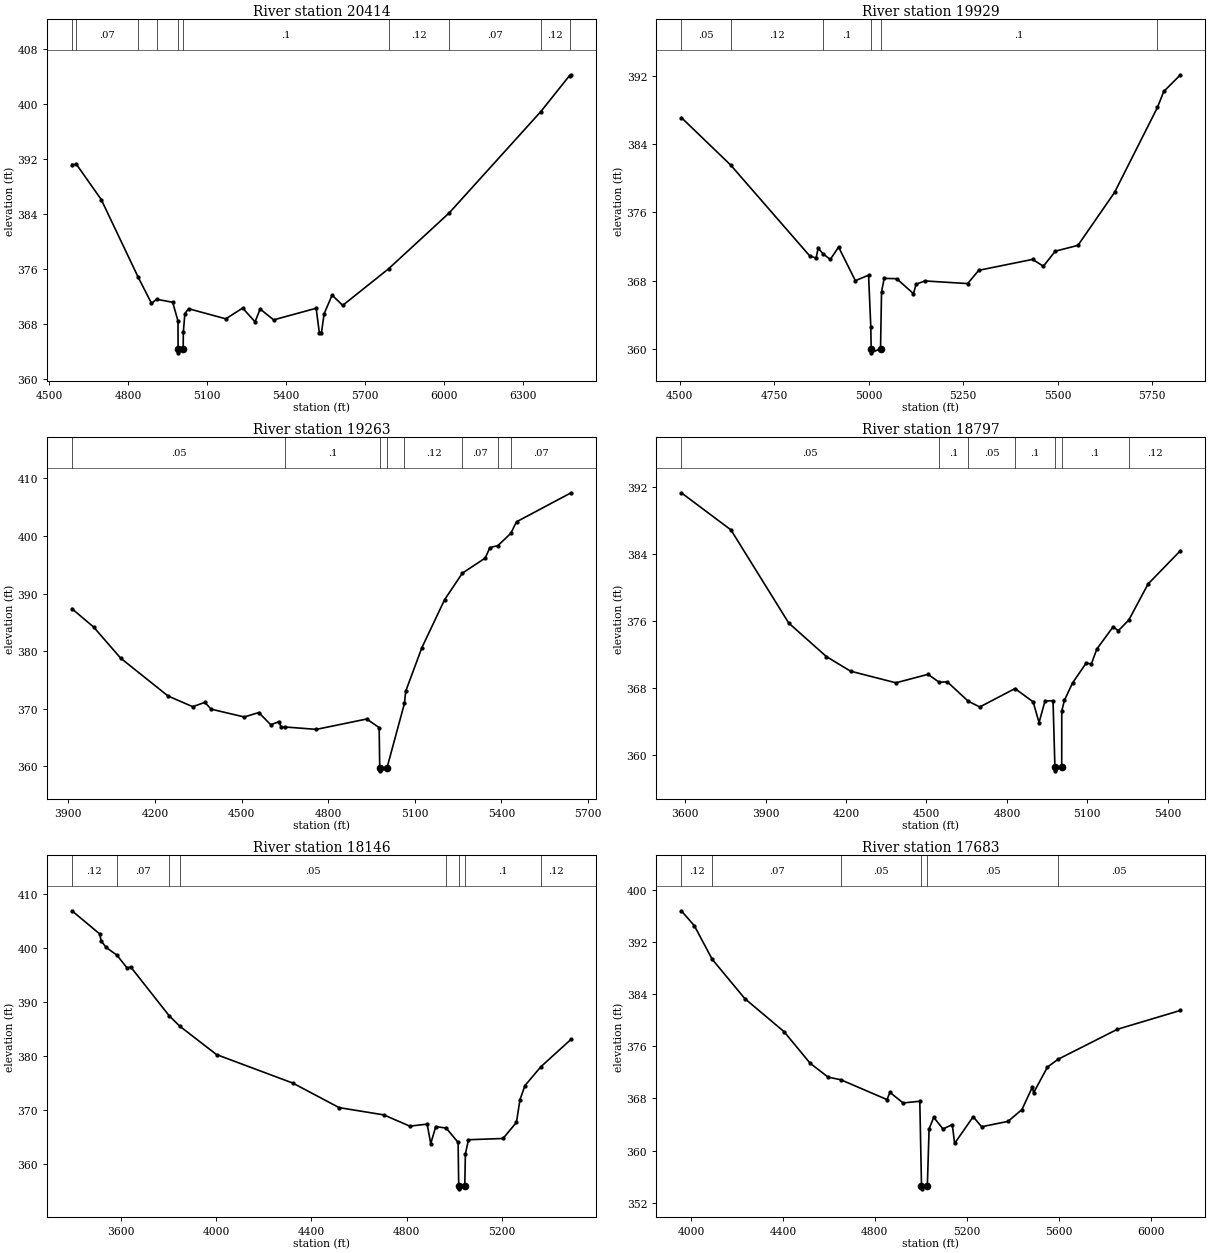
Type RM Length L Ch R = 1 ,20414   ,485,485,485
BEGIN DESCRIPTION:
BUCK BRANCH 29.0
END DESCRIPTION:
XS GIS Cut Line= 3
      2476135.68     13809214.48      2475786.72     13809250.94
       2474255.5      13809037.4
#Sta/Elev= 30
  4586.9  391.16  4604.1  391.19  4698.2  386.07  4838.3  374.79  4889.2  370.96
  4908.9  371.55  4969.8  371.11    4990  368.37  4990.3  364.25  4990.8  363.75
  5009.8  364.25  5010.2  366.73  5016.1  369.47  5030.4  370.17  5171.7   368.7
  5235.7  370.27  5282.8  368.26  5302.2  370.13  5353.5  368.55    5515  370.24
    5527  366.71  5535.2  366.67  5545.3  369.44  5575.6  372.15    5616  370.66
    5790  375.98    6021  384.13  6368.8  398.87  6478.2  404.12  6483.8  404.23
#Mann= 10 ,-1 , 0
  4586.9     .05       0  4604.1     .07       0  4838.3     .12       0
  4908.9      .1       0  4990.3     .05       0  5009.8      .1       0
    5790     .12       0    6021     .07       0  6368.8     .12       0
  6478.2     .07       0
Bank Sta=4990.3,5009.8
XS Rating Curve= 0 ,0
Exp/Cntr=0.3,0.1

Type RM Length L Ch R = 1 ,19929   ,666,666,666
BEGIN DESCRIPTION:
BUCK BRANCH 28.0
END DESCRIPTION:
XS GIS Cut Line= 3
      2476075.02     13809025.01        2475625.       13808825.
      2474875.01     13808475.01
#Sta/Elev= 30
  4504.4  387.09  4635.2  381.52  4843.7  370.92  4860.8  370.64  4866.2  371.81
  4879.8  371.13  4898.4  370.49  4920.3  371.94  4964.7  368.01  4999.6  368.65
  5005.5  362.63  5006.5  360.07    5007  359.57  5031.3  360.07  5033.9   366.7
    5041  368.28  5074.1  368.24  5118.3  366.49  5125.3  367.59  5148.2  367.98
  5261.7  367.67  5290.9  369.22  5433.5   370.5  5461.9   369.7  5493.5  371.46
  5553.4  372.14  5650.3  378.34  5763.6  388.27  5780.4  390.14  5824.5  392.09
#Mann= 6 ,-1 , 0
  4504.4     .05       0  4635.2     .12       0  4879.8      .1       0
  5006.5     .05       0  5031.3      .1       0  5763.6     .12       0
Bank Sta=5006.5,5031.3
XS Rating Curve= 0 ,0
Exp/Cntr=0.3,0.1

Type RM Length L Ch R = 1 ,19263   ,466,466,466
BEGIN DESCRIPTION:
X18366
END DESCRIPTION:
XS GIS Cut Line= 3
      2476114.83     13808990.51      2475573.17     13808276.98
       2474760.7     13808094.69
#Sta/Elev= 30
  3912.5  387.36  3987.6  384.18  4081.1  378.78  4245.4   372.2  4330.7  370.35
  4372.4  371.09  4395.2  369.91  4509.5  368.56  4559.5  369.33  4601.1  367.21
  4630.2  367.76  4636.5  366.77  4651.2  366.82  4759.1  366.41  4933.1  368.21
  4976.4  366.72  4978.4  359.71  4978.9  359.21  5003.4  359.71  5064.1  370.94
  5068.2  373.01  5124.2  380.58  5203.3  388.95  5264.7  393.54  5343.6  396.15
  5359.9  397.97  5387.7  398.32  5432.2  400.44  5452.1  402.45    5641  407.49
#Mann= 8 ,-1 , 0
  3912.5     .05       0  4651.2      .1       0  4978.4     .05       0
  5003.4      .1       0  5064.1     .12       0  5264.7     .07       0
  5387.7     .12       0  5432.2     .07       0
Bank Sta=4978.4,5003.4
XS Rating Curve= 0 ,0
Exp/Cntr=0.3,0.1

Type RM Length L Ch R = 1 ,18797   ,651,651,651
BEGIN DESCRIPTION:
BUCK BRANCH 27.0
END DESCRIPTION:
XS GIS Cut Line= 3
        2476225.       13809125.        2475575.       13807875.
        2475625.     13807424.96
#Sta/Elev= 30
  3585.7  391.33  3770.8  386.89  3986.3  375.75  4126.7  371.74  4216.9  369.99
    4386   368.6  4505.6  369.61  4547.5  368.67  4577.6  368.72  4655.7   366.4
  4698.9  365.71  4830.3  367.91  4897.9  366.32    4920  363.84  4942.1  366.42
  4972.1  366.46  4979.1  358.57  4979.6  358.07  5004.5  358.57  5004.7  365.24
  5014.7  366.51  5044.9  368.58  5095.2  370.94  5115.3  370.88  5135.5  372.64
  5195.8  375.28  5215.9  374.84  5254.8  376.11  5326.6  380.42  5447.4  384.41
#Mann= 7 ,-1 , 0
  3585.7     .05       0  4547.5      .1       0  4655.7     .05       0
  4830.3      .1       0  4979.1     .05       0  5004.5      .1       0
  5254.8     .12       0
Bank Sta=4979.1,5004.5
XS Rating Curve= 0 ,0
Exp/Cntr=0.3,0.1

Type RM Length L Ch R = 1 ,18146   ,463,463,463
BEGIN DESCRIPTION:
BUCK BRANCH 26.0
END DESCRIPTION:
XS GIS Cut Line= 3
        2477025.       13809325.      2476094.01     13807875.94
      2475874.98     13807574.97
#Sta/Elev= 30
  3395.9  406.82  3512.5  402.54  3518.4  401.25  3539.6  400.04  3584.3  398.64
  3627.4  396.26  3642.6  396.44  3803.6  387.45  3848.2  385.51  4002.6  380.26
    4323  374.99  4517.2  370.46  4704.7  369.12  4813.7  367.04  4886.4  367.41
  4901.6  363.82  4922.7  366.96  4966.7  366.68  5016.5  364.03    5019  355.96
  5019.5  355.46  5044.5  355.96  5046.9  361.86  5059.9  364.53  5204.9  364.76
  5261.3  367.74    5276  371.92  5296.9  374.52  5363.7  378.01  5490.5  383.08
#Mann= 8 ,-1 , 0
  3395.9     .12       0  3584.3     .07       0  3803.6     .12       0
  3848.2     .05       0  4966.7      .1       0    5019     .05       0
  5044.5      .1       0  5363.7     .12       0
Bank Sta=5019,5044.5
XS Rating Curve= 0 ,0
Exp/Cntr=0.3,0.1

Type RM Length L Ch R = 1 ,17683   ,510,510,510
BEGIN DESCRIPTION:
BUCK BRANCH 25.0
END DESCRIPTION:
XS GIS Cut Line= 3
      2477225.03     13808825.03      2476583.59     13808073.85
      2476422.14     13806902.01
#Sta/Elev= 30
  3958.3   396.8  4014.9  394.51  4092.3  389.37  4234.5  383.32  4405.4  378.24
  4518.8  373.39  4596.8  371.27  4651.9  370.87  4852.5  367.83  4865.7  368.93
  4922.8  367.31  4995.4  367.57  5002.8  354.63  5003.3  354.13  5028.3  354.63
  5035.8  363.34    5056   365.1  5096.3  363.32  5136.7  363.99  5146.8   361.1
  5227.6   365.2  5264.2  363.66    5379  364.48  5439.6  366.29  5485.1  369.76
  5490.2  368.86  5550.6  372.82  5597.1  374.02    5855  378.62    6129  381.51
#Mann= 6 ,-1 , 0
  3958.3     .12       0  4092.3     .07       0  4651.9     .05       0
  5002.8     .05       0  5028.3     .05       0  5597.1     .05       0
Bank Sta=5002.8,5028.3
XS Rating Curve= 0 ,0
Exp/Cntr=0.3,0.1