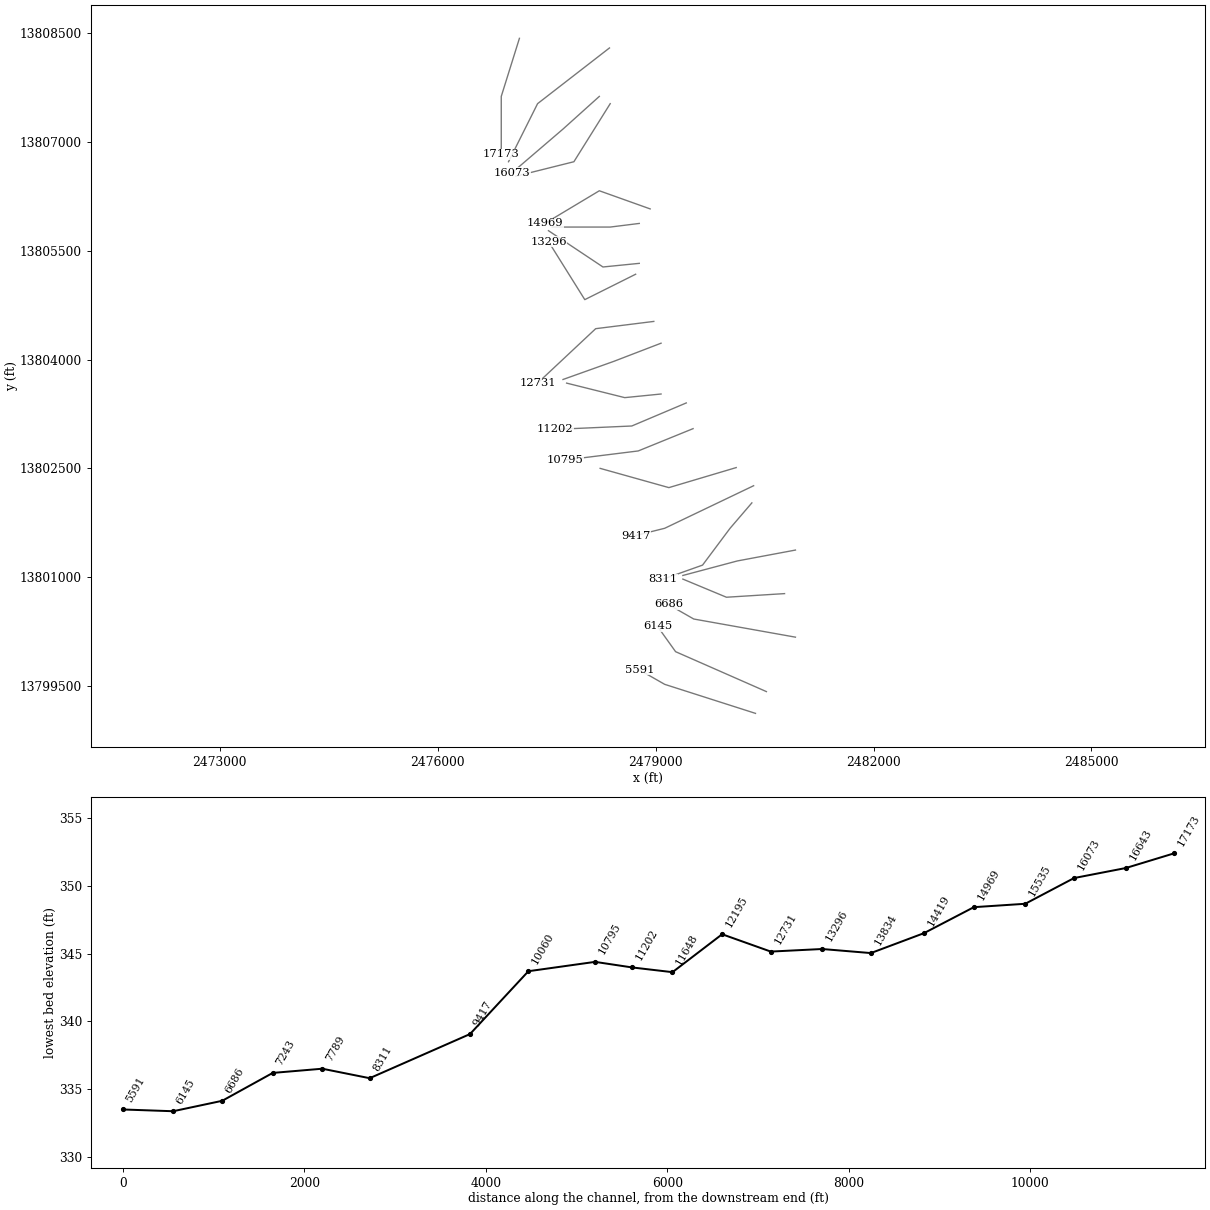
HEC-RAS study BUCK BRANCH.prj: BUCK BRANCH Base Level Engineering

--- BUCK BRANCH.g01 (geometry) --- (continued)

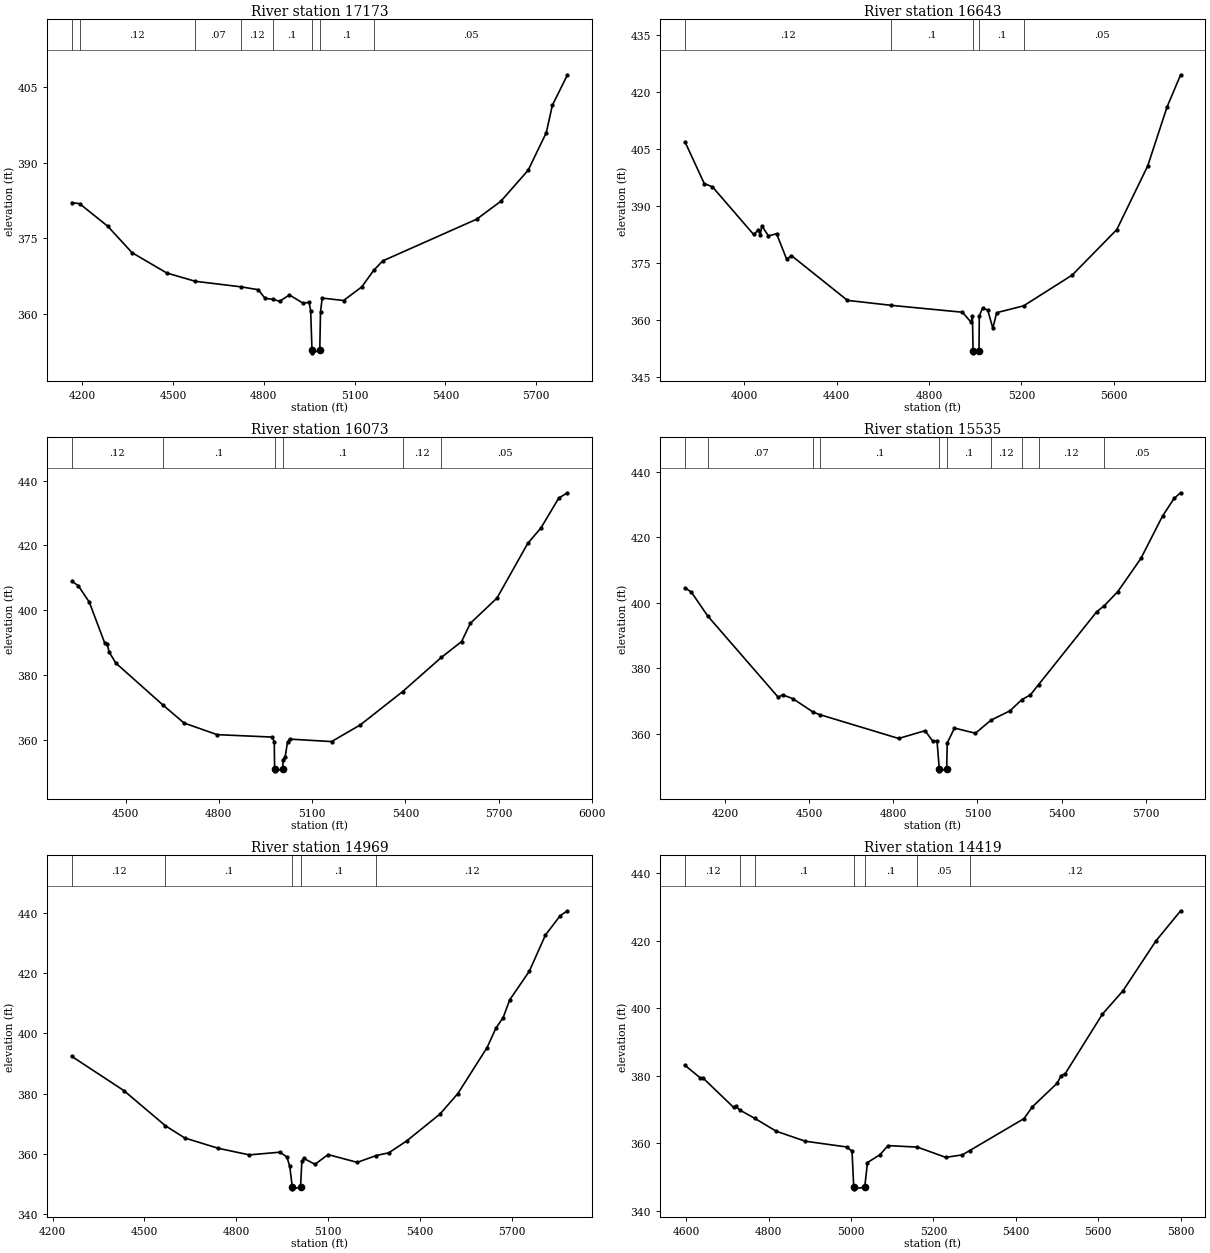
Type RM Length L Ch R = 1 ,17173   ,530,530,530
BEGIN DESCRIPTION:
BUCK BRANCH 24.0
END DESCRIPTION:
XS GIS Cut Line= 3
      2477125.01     13808425.04        2476875.       13807625.
        2476875.       13806825.
#Sta/Elev= 30
  4165.5  382.09  4191.4  381.87  4284.5  377.41  4364.6   372.2  4479.3  368.18
  4573.4  366.54  4724.9  365.44  4782.1  364.87  4804.6  363.14  4828.9  363.01
  4852.3  362.58  4884.8  363.84  4930.4  362.19  4949.7  362.39    4955  360.72
  4959.4   352.9  4959.9   352.4  4985.1   352.9  4987.5  360.51  4993.2  363.22
  5063.7  362.74  5123.7  365.42  5164.4  368.79  5193.7  370.58  5503.7  378.81
  5583.7  382.36  5673.7  388.48  5733.7  395.91  5753.7  401.31  5803.7  407.34
#Mann= 8 ,-1 , 0
  4165.5     .07       0  4191.4     .12       0  4573.4     .07       0
  4724.9     .12       0  4828.9      .1       0  4959.4     .05       0
  4985.1      .1       0  5164.4     .05       0
Bank Sta=4959.4,4985.1
XS Rating Curve= 0 ,0
Exp/Cntr=0.3,0.1

Type RM Length L Ch R = 1 ,16643   ,570,570,570
BEGIN DESCRIPTION:
BUCK BRANCH 23.0
END DESCRIPTION:
XS GIS Cut Line= 3
      2478364.82     13808292.58        2477375.       13807525.
        2476975.     13806724.99
#Sta/Elev= 30
  3742.9  406.95  3826.8  395.91  3862.1  395.06  4040.4  382.51  4061.3  383.68
  4069.4  382.29  4075.7   384.8  4104.7  382.13    4140   382.7  4183.5  375.98
  4204.3  376.94  4446.9  365.14  4637.4  363.83  4944.8  362.02  4981.9  359.41
  4988.2  360.99    4991  351.82  4991.5  351.32  5016.7  351.82  5017.8  361.06
  5031.8  363.06  5054.2  362.62  5076.5  357.81  5093.3   361.9  5210.1  363.71
  5420.3  371.81  5613.2  383.77  5747.3  400.56  5831.2  416.12  5889.9  424.58
#Mann= 5 ,-1 , 0
  3742.9     .12       0  4637.4      .1       0    4991     .05       0
  5016.7      .1       0  5210.1     .05       0
Bank Sta=4991,5016.7
XS Rating Curve= 0 ,0
Exp/Cntr=0.3,0.1

Type RM Length L Ch R = 1 ,16073   ,538,538,538
BEGIN DESCRIPTION:
BUCK BRANCH 22.0
END DESCRIPTION:
XS GIS Cut Line= 3
      2478225.02     13807625.02        2477725.       13807175.
      2477024.98     13806574.98
#Sta/Elev= 30
  4326.8  409.02  4348.1  407.57  4383.3  402.52  4433.3  389.82  4440.1  389.73
  4447.5   387.1  4468.5  383.78    4620  370.86  4688.2   365.3  4794.3  361.73
  4971.5  360.98  4978.2  359.55  4979.4  351.08  4979.9  350.58  5005.5  351.08
  5006.6  354.06  5013.2  354.84  5020.9  359.45  5027.5  360.36  5162.5  359.59
  5254.7  364.71  5390.8  374.96    5516  385.54  5580.7  390.39  5609.2  396.04
  5694.8  403.81  5793.6  420.62  5836.4  425.44  5893.5  434.61  5921.5  436.23
#Mann= 6 ,-1 , 0
  4326.8     .12       0    4620      .1       0  4979.4     .05       0
  5005.5      .1       0  5390.8     .12       0    5516     .05       0
Bank Sta=4979.4,5005.5
XS Rating Curve= 0 ,0
Exp/Cntr=0.3,0.1

Type RM Length L Ch R = 1 ,15535   ,566,566,566
BEGIN DESCRIPTION:
BUCK BRANCH 21.0
END DESCRIPTION:
XS GIS Cut Line= 3
      2478374.98     13807524.97        2477875.       13806725.
      2477074.98       13806525.
#Sta/Elev= 30
  4056.6  404.55  4079.6  403.25  4138.1  395.93  4389.7  371.12    4405  371.89
  4441.6  370.72  4513.9  366.62  4536.9  365.86  4818.9  358.56  4913.3  360.94
    4941  357.67  4955.7  357.88  4963.9  349.18  4964.4  348.68  4990.1  349.18
  4992.3   357.2    5018  361.74  5092.7  360.16  5148.3  364.15  5216.4  367.03
  5258.2  370.42  5288.6  371.85  5317.8  374.99  5525.7  397.29  5551.5  399.02
  5600.4  403.38  5682.8  413.51  5760.2  426.48  5801.4  431.87  5824.6  433.57
#Mann= 10 ,-1 , 0
  4056.6     .12       0  4138.1     .07       0  4513.9     .12       0
  4536.9      .1       0  4963.9     .05       0  4990.1      .1       0
  5148.3     .12       0  5258.2     .07       0  5317.8     .12       0
  5551.5     .05       0
Bank Sta=4963.9,4990.1
XS Rating Curve= 0 ,0
Exp/Cntr=0.3,0.1

Type RM Length L Ch R = 1 ,14969   ,550,550,550
BEGIN DESCRIPTION:
BUCK BRANCH 20.0
END DESCRIPTION:
XS GIS Cut Line= 3
      2478925.02     13806074.99        2478225.       13806325.
      2477474.97     13805874.98
#Sta/Elev= 30
  4262.8  392.38  4432.7  381.04  4568.7  369.34  4631.8   365.3  4740.7  361.89
  4842.1   359.7  4942.4  360.59  4965.2  358.96  4974.3  355.86  4982.7  348.93
  4983.2  348.43  5009.4  348.93  5013.9  357.59  5019.7  358.54  5056.7  356.57
  5099.4   359.8  5194.7  357.21  5256.6  359.49  5297.7  360.39    5356  364.33
  5464.8  373.26  5523.1  380.06  5618.4  395.31  5647.5  401.81  5670.8  405.23
  5692.2  411.12  5756.4  420.67  5808.8  432.63  5857.4   439.1  5880.8  440.69
#Mann= 5 ,-1 , 0
  4262.8     .12       0  4568.7      .1       0  4982.7     .05       0
  5009.4      .1       0  5256.6     .12       0
Bank Sta=4982.7,5009.4
XS Rating Curve= 0 ,0
Exp/Cntr=0.3,0.1

Type RM Length L Ch R = 1 ,14419   ,585,585,585
BEGIN DESCRIPTION:
BUCK BRANCH 19.0
END DESCRIPTION:
XS GIS Cut Line= 3
      2478774.96       13805875.        2478375.       13805825.
      2477574.98       13805825.
#Sta/Elev= 30
    4597  383.12  4634.8  379.33  4639.8  379.48  4715.4  370.62  4720.4  370.93
  4731.8  369.75  4766.3  367.41  4818.7  363.58  4889.2  360.62    4990  358.91
  5002.6  357.64  5006.7  347.01  5007.2  346.51  5033.4  347.01  5040.1   354.3
  5070.1   356.6  5090.1  359.32  5161.2  358.87  5230.1  355.84  5270.1  356.57
  5287.9  357.83  5420.1  367.33  5440.1  370.79  5500.1  377.77  5510.1  380.03
  5520.1  380.66  5610.1  398.25  5660.1  405.18  5740.1  419.96  5800.1   428.9
#Mann= 7 ,-1 , 0
    4597     .12       0  4731.8     .07       0  4766.3      .1       0
  5006.7     .05       0  5033.4      .1       0  5161.2     .05       0
  5287.9     .12       0
Bank Sta=5006.7,5033.4
XS Rating Curve= 0 ,0
Exp/Cntr=0.3,0.1

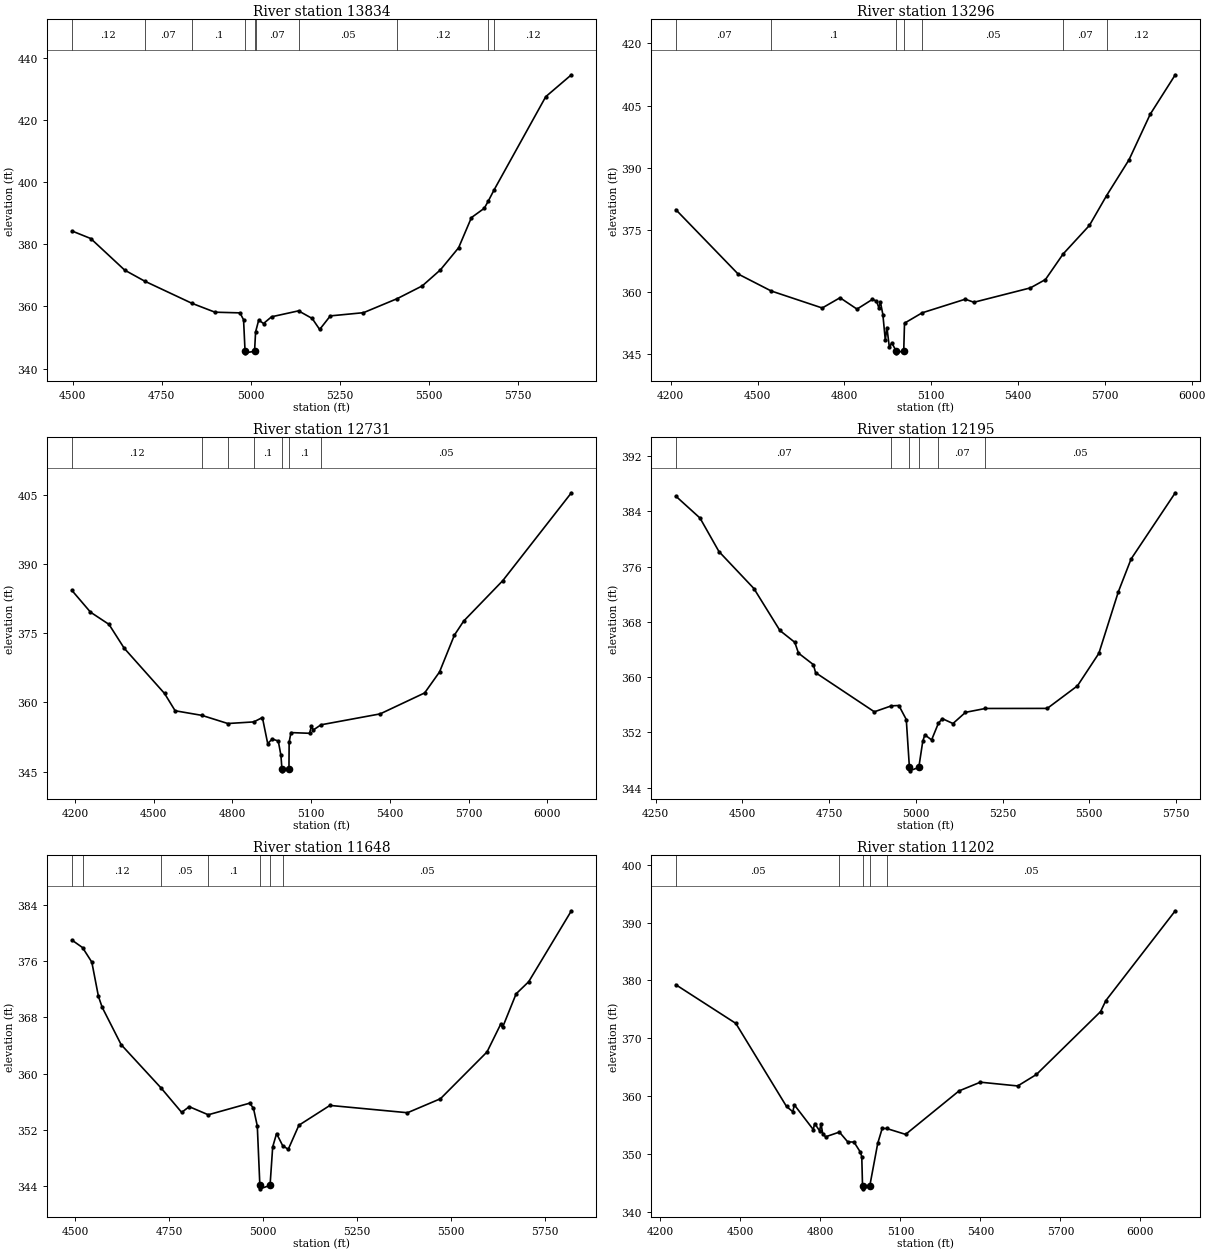
Type RM Length L Ch R = 1 ,13834   ,538,538,538
BEGIN DESCRIPTION:
BUCK BRANCH 18.0
END DESCRIPTION:
XS GIS Cut Line= 3
        2478775.       13805325.        2478275.       13805275.
      2477524.98     13805775.01
#Sta/Elev= 30
  4497.5  384.25  4550.3  381.82  4645.7  371.66  4702.1   368.1  4834.3     361
  4899.5  358.12  4969.8   357.9  4979.9  355.67  4984.1  345.54  4984.6  345.04
  5010.8  345.54  5013.7  351.76  5022.5   355.6    5036  354.47  5058.6  356.64
  5134.4  358.55  5172.8   356.1  5193.8  352.56  5223.8  356.93    5317  357.96
    5412  362.49  5482.2  366.58  5533.3  371.75  5584.4  378.86  5620.4  388.56
  5656.5  391.55    5668  393.92  5684.3  397.51  5829.3  427.46  5901.4  434.51
#Mann= 10 ,-1 , 0
  4497.5     .12       0  4702.1     .07       0  4834.3      .1       0
  4984.1     .05       0  5010.8      .1       0  5013.7     .07       0
  5134.4     .05       0    5412     .12       0    5668     .05       0
  5684.3     .12       0
Bank Sta=4984.1,5010.8
XS Rating Curve= 0 ,0
Exp/Cntr=0.3,0.1

Type RM Length L Ch R = 1 ,13296   ,565,565,565
BEGIN DESCRIPTION:
BUCK BRANCH 17.0
END DESCRIPTION:
XS GIS Cut Line= 3
      2478724.97     13805174.99        2478025.       13804825.
      2477524.99     13805625.01
#Sta/Elev= 30
  4217.4  379.88  4432.6  364.36  4547.1  360.26  4723.3  356.16  4784.8  358.63
  4843.5  355.89  4896.6  358.23  4910.5  357.84  4918.9  356.27  4924.5  357.55
  4932.9  354.58  4941.3   348.4  4946.9  351.45  4955.3  346.67  4963.7  347.77
  4978.2  345.84  4978.7  345.34    5005  345.84  5007.7   352.5  5068.5  354.99
  5217.6  358.28  5247.6  357.54  5442.8  361.01  5494.7  363.02  5555.7  369.18
  5646.8  376.09  5706.1  383.28  5783.6  391.92  5856.7  402.89  5943.4  412.42
#Mann= 7 ,-1 , 0
  4217.4     .07       0  4547.1      .1       0  4978.2     .05       0
    5005      .1       0  5068.5     .05       0  5555.7     .07       0
  5706.1     .12       0
Bank Sta=4978.2,5005
XS Rating Curve= 0 ,0
Exp/Cntr=0.3,0.1

Type RM Length L Ch R = 1 ,12731   ,536,536,536
BEGIN DESCRIPTION:
BUCK BRANCH 16.0
END DESCRIPTION:
XS GIS Cut Line= 3
      2478975.04     13804525.01        2478175.       13804425.
      2477374.97     13803674.97
#Sta/Elev= 30
    4189   384.3  4259.6  379.59  4330.1  376.94  4388.1  371.76  4541.8  361.94
  4582.1  358.19    4684  357.19  4782.9  355.42  4881.8  355.77  4914.6  356.72
  4934.8  351.08  4952.4  352.06  4975.1  351.62  4985.2  348.52  4988.9  345.65
  4989.4  345.15  5015.8  345.65  5016.5  351.35  5023.4  353.45  5094.2   353.3
  5101.5  354.83  5108.4  354.01  5137.8  355.14  5363.3  357.51  5532.8  362.06
  5589.5  366.61  5646.1   374.6  5681.3  377.64  5830.3  386.42  6091.9   405.5
#Mann= 7 ,-1 , 0
    4189     .12       0    4684      .1       0  4782.9     .07       0
  4881.8      .1       0  4988.9     .05       0  5015.8      .1       0
  5137.8     .05       0
Bank Sta=4988.9,5015.8
XS Rating Curve= 0 ,0
Exp/Cntr=0.3,0.1

Type RM Length L Ch R = 1 ,12195   ,547,547,547
BEGIN DESCRIPTION:
BUCK BRANCH 15.0
END DESCRIPTION:
XS GIS Cut Line= 3
      2479075.02     13804225.01        2478425.       13803975.
      2477725.04     13803725.02
#Sta/Elev= 30
  4308.1   386.2  4377.8  383.03  4432.4  378.18  4533.1  372.83  4608.1  366.75
    4651  365.04  4661.7  363.47  4704.5  361.81    4711  360.64  4880.3  354.98
  4929.4  355.84    4951  355.89  4972.4  353.86  4981.4  346.93  4981.9  346.43
  5008.5  346.93  5019.9   350.7  5025.8  351.64  5045.4  350.91  5064.9  353.31
  5076.2  353.99    5107  353.28  5143.1   354.9  5200.4  355.46  5378.8  355.47
  5465.9  358.74  5527.5  363.44  5583.8  372.37  5620.4   377.1  5747.8  386.69
#Mann= 6 ,-1 , 0
  4308.1     .07       0  4929.4      .1       0  4981.4     .05       0
  5008.5      .1       0  5064.9     .07       0  5200.4     .05       0
Bank Sta=4981.4,5008.5
XS Rating Curve= 0 ,0
Exp/Cntr=0.3,0.1

Type RM Length L Ch R = 1 ,11648   ,446,446,446
BEGIN DESCRIPTION:
BUCK BRANCH 14.0
END DESCRIPTION:
XS GIS Cut Line= 3
      2479075.02       13803525.        2478575.       13803475.
      2477775.03     13803674.99
#Sta/Elev= 30
  4492.1  378.99  4520.2  377.93  4544.9  375.86  4562.5  370.98  4572.5  369.43
  4622.8  364.13  4728.9  357.97  4783.6   354.5  4803.7  355.31  4854.3  354.16
  4964.5  355.81  4974.5  355.06  4984.6  352.57  4991.4  344.13  4991.9  343.63
  5018.5  344.13  5025.5  349.59  5035.8  351.49  5051.9  349.78  5066.8  349.24
  5095.1  352.67  5177.6  355.49  5383.7  354.45  5471.3  356.44    5595  363.09
  5631.1  367.01  5636.3  366.58  5672.3  371.35  5705.8  373.08  5819.2  383.16
#Mann= 7 ,-1 , 0
  4492.1     .05       0  4520.2     .12       0  4728.9     .05       0
  4854.3      .1       0  4991.4     .05       0  5018.5      .1       0
  5051.9     .05       0
Bank Sta=4991.4,5018.5
XS Rating Curve= 0 ,0
Exp/Cntr=0.3,0.1

Type RM Length L Ch R = 1 ,11202   ,407,407,407
BEGIN DESCRIPTION:
X18367
END DESCRIPTION:
XS GIS Cut Line= 3
      2479422.14     13803401.98      2478672.13     13803084.27
      2477614.79     13803037.39
#Sta/Elev= 30
  4257.5  379.25  4482.5  372.57  4672.6  358.21  4696.3   357.3  4701.7   358.5
  4772.8  354.23  4778.2  355.26  4796.5  354.01  4801.9  355.22  4808.3  353.54
  4819.1  352.97  4870.9  353.79    4902   352.1  4925.7  352.06  4949.4  350.33
  4954.8  349.52  4957.6  344.48  4958.1  343.98  4984.8  344.48  5014.6  351.84
  5031.3  354.41  5047.9  354.41  5119.2  353.39  5319.4   360.9  5399.5  362.41
  5539.6  361.76  5609.7  363.74  5850.3  374.61  5869.9   376.5  6130.4  392.03
#Mann= 5 ,-1 , 0
  4257.5     .05       0  4870.9      .1       0  4957.6     .05       0
  4984.8      .1       0  5047.9     .05       0
Bank Sta=4957.6,4984.8
XS Rating Curve= 0 ,0
Exp/Cntr=0.3,0.1

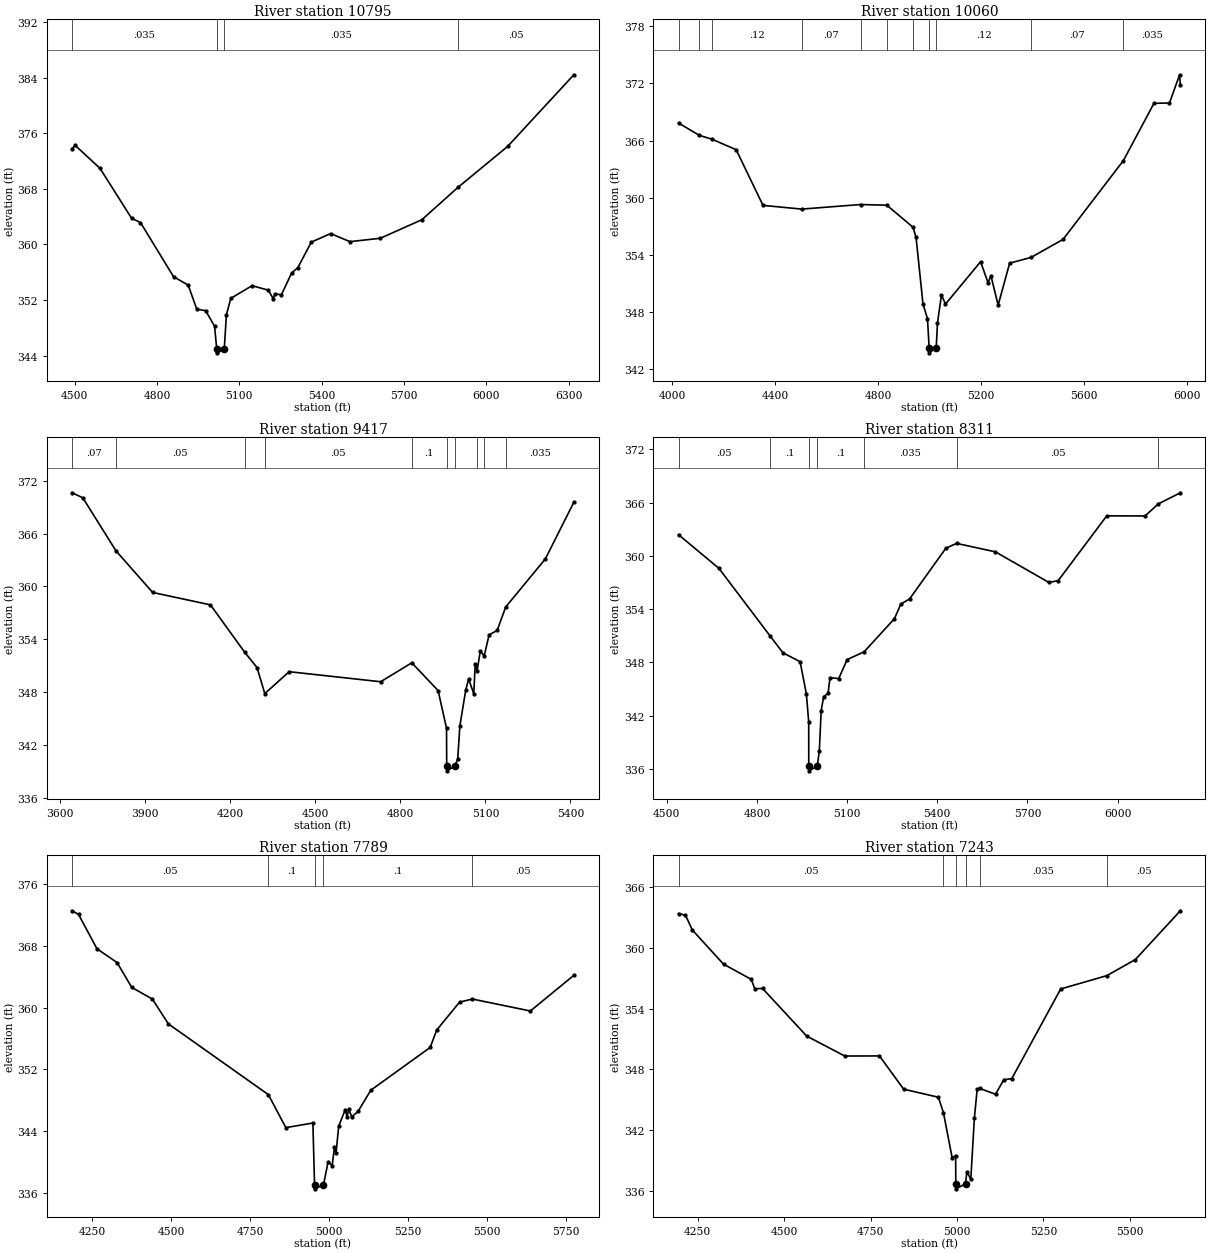
Type RM Length L Ch R = 1 ,10795   ,735,735,735
BEGIN DESCRIPTION:
X18368
END DESCRIPTION:
XS GIS Cut Line= 3
      2479515.91     13803047.82      2478760.67     13802740.52
      2477755.48     13802615.52
#Sta/Elev= 30
  4490.7  373.81  4502.5  374.25  4592.6  370.95  4707.6  363.77    4740  363.15
  4860.3  355.36  4913.8  354.14  4945.1  350.68  4977.5  350.46  5009.9  348.22
  5017.9  344.89  5018.4  344.39  5045.1  344.89  5053.1  349.88    5069  352.23
  5146.5  354.06  5205.5  353.42  5224.1  352.16  5229.5  352.86  5253.6  352.77
  5290.6  355.88  5313.5  356.66  5362.2  360.33  5432.7  361.56  5503.2   360.4
  5614.1  360.89  5765.2  363.56  5896.6  368.21  6077.6  374.11    6319  384.43
#Mann= 4 ,-1 , 0
  4490.7    .035       0  5017.9    .035       0  5045.1    .035       0
  5896.6     .05       0
Bank Sta=5017.9,5045.1
XS Rating Curve= 0 ,0
Exp/Cntr=0.3,0.1

Type RM Length L Ch R = 1 ,10060   ,643,643,643
BEGIN DESCRIPTION:
BUCK BRANCH 13.0
END DESCRIPTION:
XS GIS Cut Line= 3
      2480109.61     13802511.35      2479182.55     13802235.31
      2478236.28     13802500.47
#Sta/Elev= 30
  4023.5  367.84  4104.7  366.54  4151.7  366.16  4247.4  365.04  4351.8  359.19
  4502.2   358.8    4731  359.28  4832.9  359.21  4934.8  356.89  4946.5  355.83
  4973.5  348.83  4990.8   347.3  4997.6   344.2  4998.1   343.7  5024.8   344.2
  5029.8  346.85  5045.3  349.79  5060.9  348.82  5197.3  353.27  5226.2  351.07
  5237.5   351.8  5265.5  348.71  5310.2  353.12  5393.2  353.72  5517.9  355.62
  5752.3   363.9    5871  369.91  5931.4  369.95  5970.7  372.91  5973.5   371.8
#Mann= 11 ,-1 , 0
  4023.5     .12       0  4104.7     .07       0  4151.7     .12       0
  4502.2     .07       0    4731     .12       0  4832.9     .07       0
  4934.8     .12       0  4997.6     .05       0  5024.8     .12       0
  5393.2     .07       0  5752.3    .035       0
Bank Sta=4997.6,5024.8
XS Rating Curve= 0 ,0
Exp/Cntr=0.3,0.1

Type RM Length L Ch R = 1 ,9417    ,1106,1106,1106
BEGIN DESCRIPTION:
BUCK BRANCH 12.0
END DESCRIPTION:
XS GIS Cut Line= 3
      2480349.21     13802261.35        2479125.       13801675.
        2478725.       13801575.
#Sta/Elev= 30
  3642.3  370.64  3680.2  370.07  3797.3  364.04  3926.5  359.32  4130.4  357.91
  4250.6  352.55  4294.6  350.79    4322  347.83  4407.9  350.32  4730.7  349.18
  4840.4  351.33  4933.2  348.18  4962.9  343.89  4963.6  339.56  4964.1  339.06
  4991.5  339.56  5002.3  340.38    5010  344.17  5030.6  348.22  5040.9   349.5
    5059   347.8  5064.1  351.23  5070.8  350.43  5082.1   352.7  5095.7   352.1
  5113.1  354.51  5141.4     355  5171.6  357.67  5311.5  363.13    5412  369.57
#Mann= 10 ,-1 , 0
  3642.3     .07       0  3797.3     .05       0  4250.6     .12       0
    4322     .05       0  4840.4      .1       0  4963.6     .05       0
  4991.5      .1       0  5070.8    .035       0  5095.7     .07       0
  5171.6    .035       0
Bank Sta=4963.6,4991.5
XS Rating Curve= 0 ,0
Exp/Cntr=0.3,0.1

Type RM Length L Ch R = 1 ,8311    ,522,522,522
BEGIN DESCRIPTION:
BUCK BRANCH 11.0
END DESCRIPTION:
XS GIS Cut Line= 4
      2480324.99     13802024.99        2480025.       13801675.
      2479646.09      13801167.6      2479104.39     13800974.88
#Sta/Elev= 30
  4539.3  362.39  4673.7   358.6    4844  350.98  4886.7  349.09  4943.7  348.09
  4964.6  344.45  4972.3  341.32  4972.5   336.3    4973   335.8  5000.6   336.3
  5007.6  338.02  5013.8  342.59  5022.2  344.17  5036.8  344.51    5043  346.29
  5072.2  346.19  5100.1  348.33  5156.6   349.2  5257.7  352.94  5278.6  354.58
  5307.8  355.15  5428.6  360.87  5464.4  361.41  5593.3  360.46  5771.5  357.01
  5802.3  357.22  5963.7  364.51  6091.1   364.5  6135.4  365.86  6208.5  367.11
#Mann= 7 ,-1 , 0
  4539.3     .05       0    4844      .1       0  4972.5     .05       0
  5000.6      .1       0  5156.6    .035       0  5464.4     .05       0
  6135.4     .07       0
Bank Sta=4972.5,5000.6
XS Rating Curve= 0 ,0
Exp/Cntr=0.3,0.1

Type RM Length L Ch R = 1 ,7789    ,546,546,546
BEGIN DESCRIPTION:
BUCK BRANCH 10.0
END DESCRIPTION:
XS GIS Cut Line= 3
      2480925.02       13801375.        2480125.       13801225.
      2479374.97     13801024.99
#Sta/Elev= 30
  4185.7  372.57  4206.1   372.1  4264.6  367.64  4328.2  365.86  4374.8  362.63
  4440.1  361.12  4490.9   357.9  4807.7  348.72  4863.2  344.44  4948.8  345.04
  4954.2     337  4954.7   336.5  4982.4     337  4997.1  340.01    5010  339.51
  5017.1  341.87  5022.3  341.17  5030.7  344.63  5051.4  346.78  5057.2  345.84
  5062.4  346.81  5072.1  345.84  5092.2  346.55  5132.3  349.29  5320.5  354.84
  5341.2   357.1  5413.6  360.72  5454.4  361.12  5638.1  359.57  5775.9   364.2
#Mann= 5 ,-1 , 0
  4185.7     .05       0  4807.7      .1       0  4954.2    .035       0
  4982.4      .1       0  5454.4     .05       0
Bank Sta=4954.2,4982.4
XS Rating Curve= 0 ,0
Exp/Cntr=0.3,0.1

Type RM Length L Ch R = 1 ,7243    ,557,557,557
BEGIN DESCRIPTION:
BUCK BRANCH 9.0
END DESCRIPTION:
XS GIS Cut Line= 3
      2480775.04       13800775.        2479975.       13800725.
        2479375.       13800975.
#Sta/Elev= 30
  4194.5  363.41  4214.6  363.24  4234.6  361.77  4324.8   358.4  4404.9   356.9
    4415  355.97  4437.5     356  4565.3  351.29  4675.5  349.32  4775.7  349.33
  4845.8  346.04    4946  345.25  4960.8  343.73  4986.1  339.24  4996.1  339.48
  4996.6  336.69  4997.1  336.19  5024.8  336.69  5028.6  337.88    5040  337.13
  5050.3  343.19  5058.4  346.03  5066.4  346.11  5111.5  345.54  5135.3  346.97
  5158.6  347.09    5300  355.95  5433.7  357.27  5516.1  358.86  5646.1  363.68
#Mann= 6 ,-1 , 0
  4194.5     .05       0  4960.8      .1       0  4996.6     .05       0
  5024.8      .1       0  5066.4    .035       0  5433.7     .05       0
Bank Sta=4996.6,5024.8
XS Rating Curve= 0 ,0
Exp/Cntr=0.3,0.1

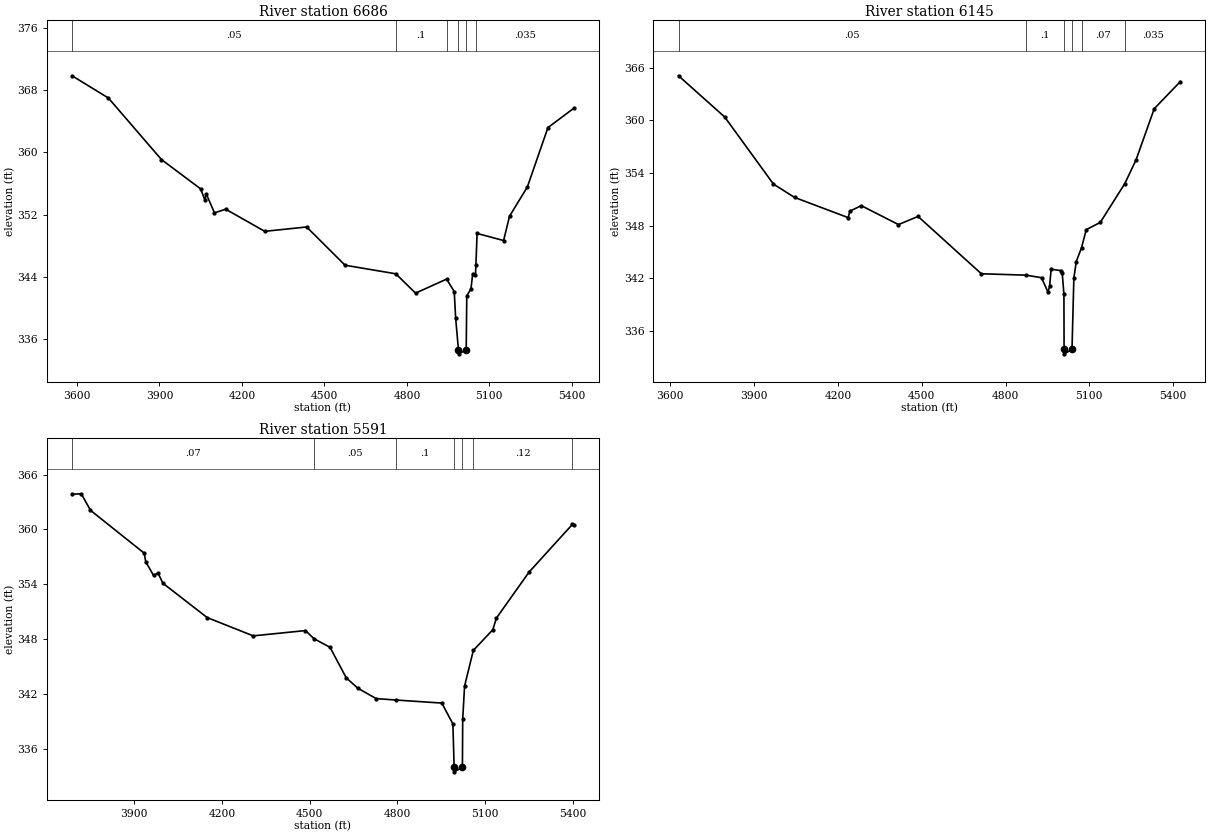
Type RM Length L Ch R = 1 ,6686    ,541,541,541
BEGIN DESCRIPTION:
BUCK BRANCH 8.0
END DESCRIPTION:
XS GIS Cut Line= 3
      2480925.03       13800175.        2479525.       13800425.
      2479174.99     13800625.01
#Sta/Elev= 30
  3582.1  369.81  3714.2  366.96  3907.2  359.06  4049.4  355.31  4065.1  353.89
  4070.2  354.65  4100.2  352.22  4140.8  352.69    4283  349.85  4435.4  350.41
  4575.1   345.5  4759.7   344.4  4831.6  341.92  4944.5  343.72  4972.3  342.12
  4977.4  338.72  4987.6  334.63  4988.1  334.13  5015.8  334.63  5017.9  341.58
  5033.1  342.47  5039.5  344.43  5049.6  344.19    5051  345.49  5055.4  349.58
  5151.8  348.67  5173.4  351.79  5238.2  355.54  5313.1  363.16  5407.4  365.65
#Mann= 6 ,-1 , 0
  3582.1     .05       0  4759.7      .1       0  4944.5     .07       0
  4987.6     .05       0  5015.8     .07       0    5051    .035       0
Bank Sta=4987.6,5015.8
XS Rating Curve= 0 ,0
Exp/Cntr=0.3,0.1

Type RM Length L Ch R = 1 ,6145    ,554,554,554
BEGIN DESCRIPTION:
BUCK BRANCH 7.0
END DESCRIPTION:
XS GIS Cut Line= 3
      2480525.03     13799424.99        2479275.       13799975.
        2479025.       13800325.
#Sta/Elev= 30
  3629.8  365.09  3795.2  360.38  3969.5  352.73    4045  351.21  4237.2   348.9
  4242.6  349.64  4283.9  350.27  4416.9  348.11    4487  349.04  4713.4   342.5
  4872.7  342.34  4928.9  342.05  4951.8   340.4  4957.7  341.05  4963.2  343.02
  4998.6  342.85  5002.9  342.58    5009  340.18  5009.6  333.86  5010.1  333.36
  5037.9  333.86  5044.6     342  5053.2  343.89  5072.3  345.49  5088.9  347.53
  5139.3  348.36  5226.8  352.78  5267.1  355.49  5332.2  361.33  5425.6  364.43
#Mann= 6 ,-1 , 0
  3629.8     .05       0  4872.7      .1       0  5009.6     .05       0
  5037.9      .1       0  5072.3     .07       0  5226.8    .035       0
Bank Sta=5009.6,5037.9
XS Rating Curve= 0 ,0
Exp/Cntr=0.3,0.1

Type RM Length L Ch R = 1 ,5591    ,549,549,549
BEGIN DESCRIPTION:
BUCK BRANCH 6.0
END DESCRIPTION:
XS GIS Cut Line= 3
      2480374.98     13799125.01        2479125.       13799525.
      2478775.02     13799724.99
#Sta/Elev= 30
  3687.6  363.85  3719.1   363.9  3750.6  362.09    3934  357.41  3939.6  356.45
  3966.1  354.98  3981.6  355.22  3998.3  354.11  4149.6  350.36    4307  348.36
  4485.5  348.94    4515  348.04  4569.5  347.11    4625  343.77    4664  342.65
    4727   341.5  4796.4  341.34  4951.8  341.01  4989.5  338.73  4993.8  333.99
  4994.3  333.49  5022.1  333.99  5023.1  339.28  5029.5  342.87  5059.4  346.77
    5126  349.03  5138.2   350.3  5249.8  355.33    5398  360.55  5403.1  360.46
#Mann= 7 ,-1 , 0
  3687.6     .07       0    4515     .05       0  4796.4      .1       0
  4993.8     .05       0  5022.1      .1       0  5059.4     .12       0
    5398     .05       0
Bank Sta=4993.8,5022.1
XS Rating Curve= 0 ,0
Exp/Cntr=0.3,0.1