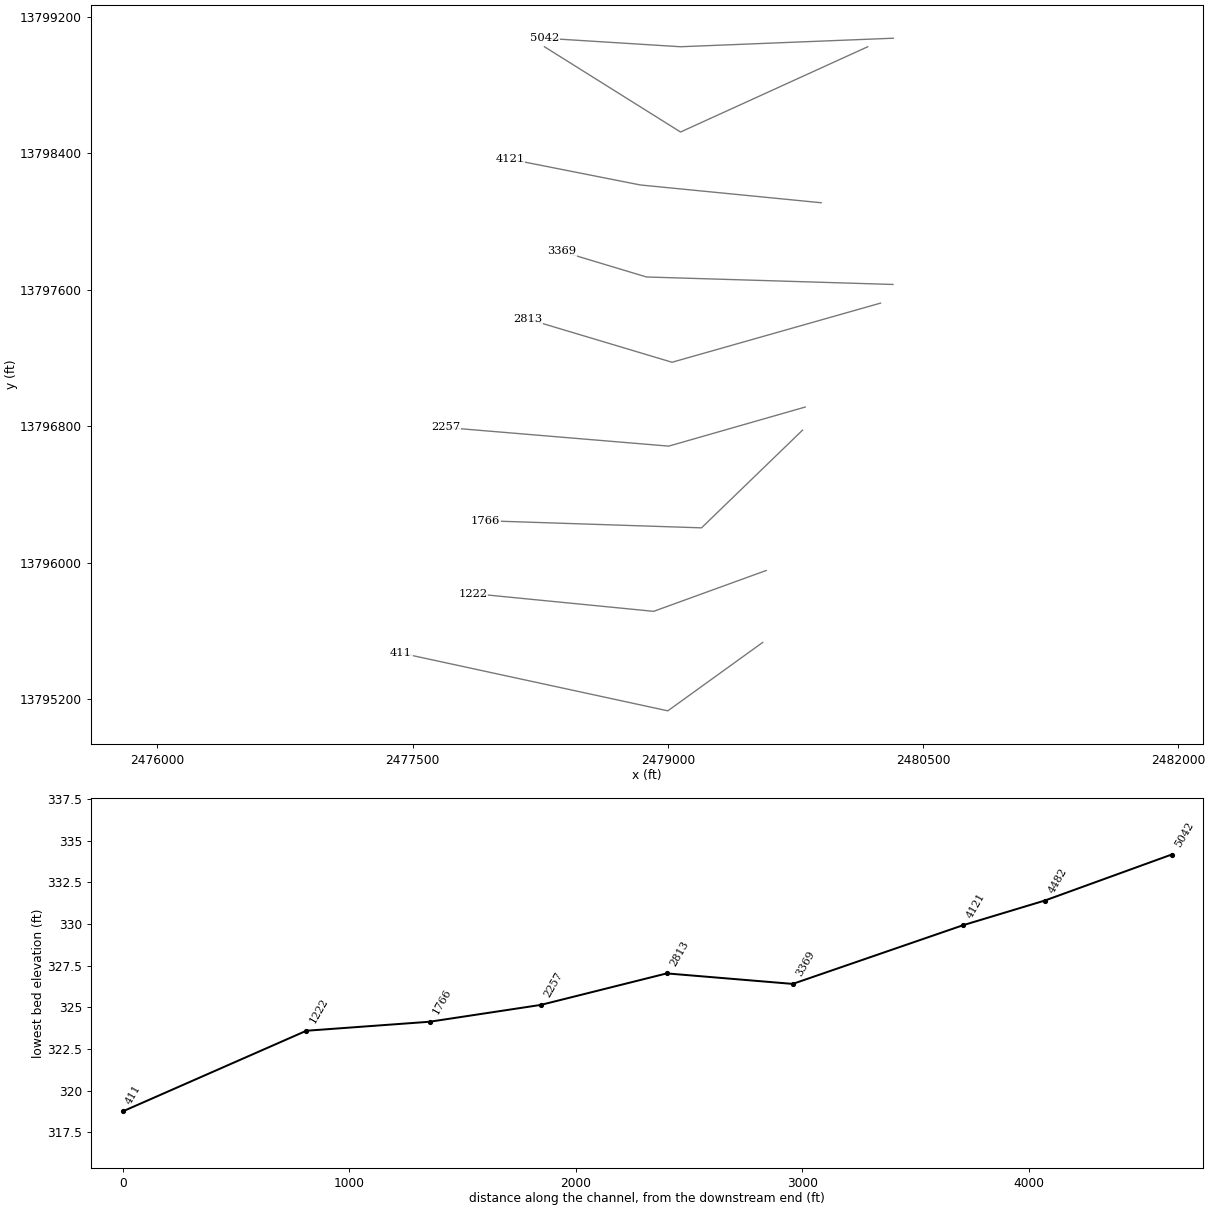
HEC-RAS study BUCK BRANCH.prj: BUCK BRANCH Base Level Engineering

--- BUCK BRANCH.g01 (geometry) --- (continued)

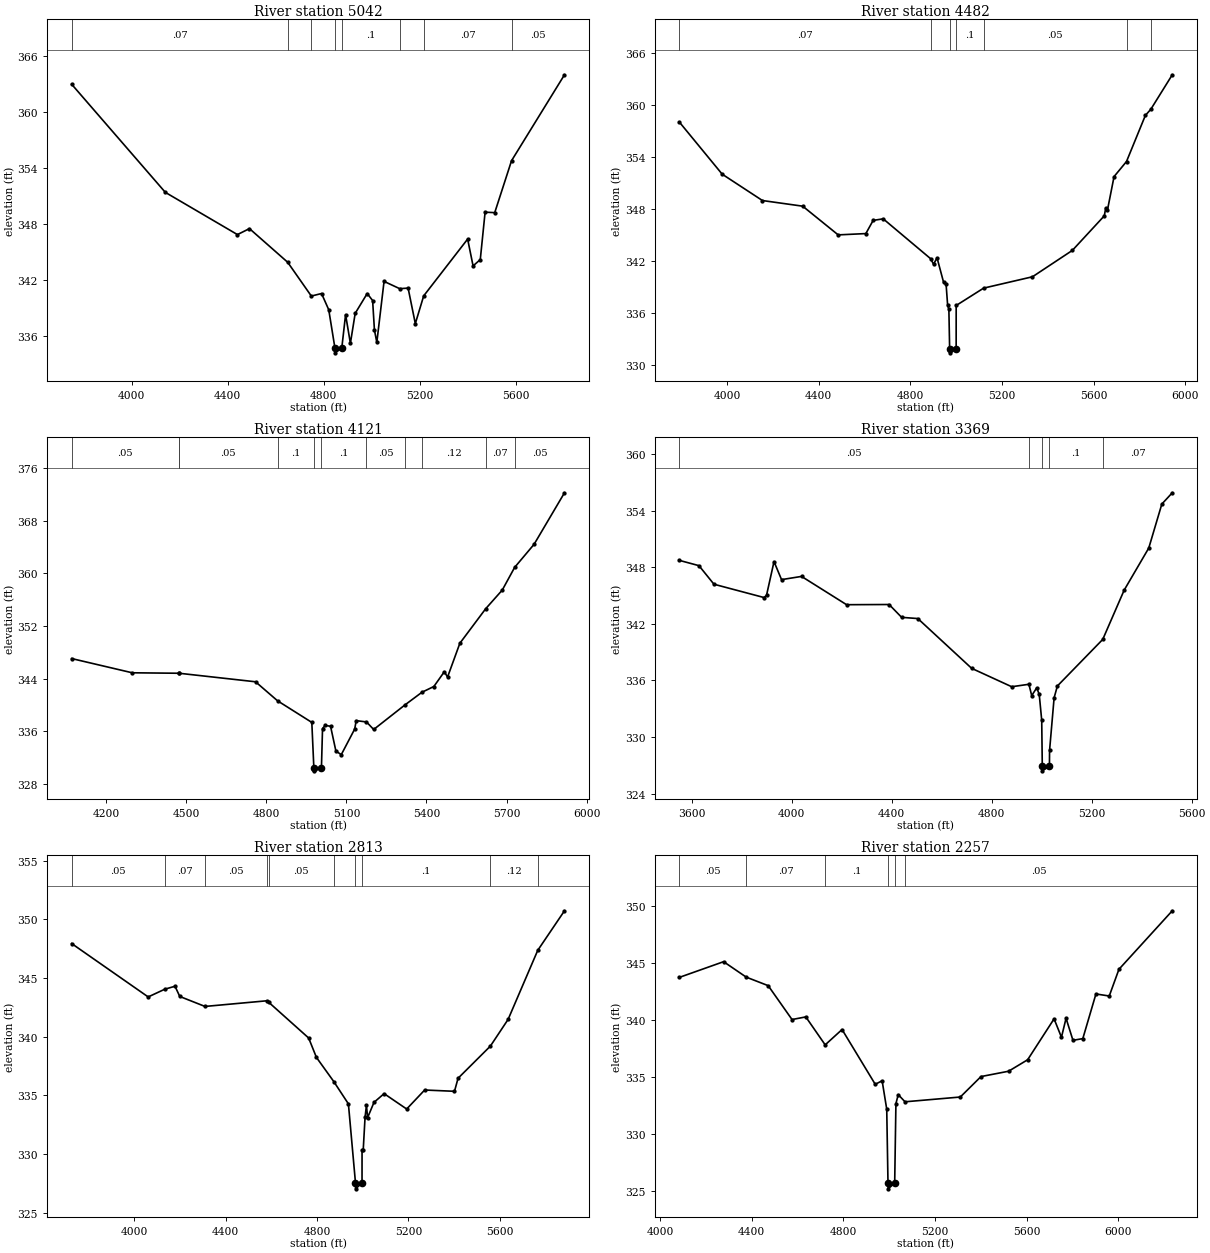
Type RM Length L Ch R = 1 ,5042    ,560,560,560
BEGIN DESCRIPTION:
BUCK BRANCH 5.0
END DESCRIPTION:
XS GIS Cut Line= 3
      2480324.96       13799075.        2479075.       13799025.
      2478275.02       13799075.
#Sta/Elev= 30
  3749.8  362.93  4140.1  351.35  4440.3  346.83  4490.4  347.47  4649.5  343.87
    4748  340.25  4790.6  340.52  4820.6  338.78  4846.4  334.67  4846.9  334.17
  4874.8  334.67  4890.7  338.26  4910.7  335.19  4930.7   338.4  4980.7  340.52
  5003.3  339.77  5010.8  336.62  5020.8  335.29  5050.9  341.82  5116.1  341.04
  5151.1   341.1  5181.1   337.3    5216  340.27    5399  346.35  5421.6  343.48
  5451.6  344.15  5471.7  349.23  5511.8  349.18  5581.8  354.74  5802.3  363.94
#Mann= 8 ,-1 , 0
  3749.8     .07       0  4649.5     .12       0    4748      .1       0
  4846.4     .05       0  4874.8      .1       0  5116.1     .05       0
    5216     .07       0  5581.8     .05       0
Bank Sta=4846.4,4874.8
XS Rating Curve= 0 ,0
Exp/Cntr=0.3,0.1

Type RM Length L Ch R = 1 ,4482    ,361,361,361
BEGIN DESCRIPTION:
BUCK BRANCH 4.0
END DESCRIPTION:
XS GIS Cut Line= 3
      2480174.98     13799024.99        2479075.       13798525.
      2478274.98     13799025.01
#Sta/Elev= 30
  3791.7  358.01  3978.4  352.01  4154.2  348.97  4329.9  348.32  4484.8  345.01
  4605.6  345.16  4637.5  346.68  4681.4  346.86  4888.6  342.26  4901.1  341.63
  4916.5  342.36  4945.1  339.53    4956  339.31  4962.6  336.92  4968.1  336.44
  4971.4  331.91  4971.9  331.41  4999.9  331.91    5000  336.87  5119.7  338.87
  5333.1  340.18  5507.1  343.22  5646.8  347.21  5652.7  348.12  5660.4  347.87
  5689.2  351.73  5743.6  353.47    5826  358.79  5849.7  359.49  5943.4  363.47
#Mann= 7 ,-1 , 0
  3791.7     .07       0  4888.6      .1       0  4971.4     .05       0
  4999.9      .1       0  5119.7     .05       0  5743.6     .07       0
  5849.7     .05       0
Bank Sta=4971.4,4999.9
XS Rating Curve= 0 ,0
Exp/Cntr=0.3,0.1

Type RM Length L Ch R = 1 ,4121    ,752,752,752
BEGIN DESCRIPTION:
X18369
END DESCRIPTION:
XS GIS Cut Line= 3
       2479901.3     13798110.31       2478838.8     13798214.48
      2478073.15     13798365.52
#Sta/Elev= 30
  4069.4  347.04  4296.8  344.87    4472   344.8  4472.4   344.8    4759   343.5
  4841.6   340.6    4970  337.31  4977.6  330.43  4978.1  329.93  5006.1  330.43
  5010.2  336.38  5020.2  336.85  5040.3  336.72  5060.4  332.93  5080.5   332.4
  5130.8   336.3  5136.4  337.58    5175  337.38    5202  336.23  5318.8  339.96
  5383.2  341.91  5427.6  342.78    5467  345.04  5478.9  344.21  5525.1  349.37
  5621.7  354.62  5684.2  357.48  5730.5  360.93  5803.4  364.45  5917.4   372.3
#Mann= 11 ,-1 , 0
  4069.4     .05       0    4472     .07       0  4472.4     .05       0
  4841.6      .1       0  4977.6     .05       0  5006.1      .1       0
    5175     .05       0  5318.8    .035       0  5383.2     .12       0
  5621.7     .07       0  5730.5     .05       0
Bank Sta=4977.6,5006.1
XS Rating Curve= 0 ,0
Exp/Cntr=0.3,0.1

Type RM Length L Ch R = 1 ,3369    ,556,556,556
BEGIN DESCRIPTION:
BUCK BRANCH 3.0
END DESCRIPTION:
XS GIS Cut Line= 3
      2480323.17     13797631.14        2478875.       13797675.
      2478374.96     13797825.01
#Sta/Elev= 30
  3551.6  348.73  3629.8  348.17  3689.8   346.2  3889.9  344.79  3899.9  345.02
  3929.9   348.6    3960  346.69    4040  347.03  4220.1  344.03  4390.2  344.05
  4440.2  342.69    4505  342.56  4720.3  337.28  4880.4  335.33  4949.2  335.59
  4960.4  334.39  4980.4  335.21  4990.4  334.53  5000.4  331.78  5002.7  326.91
  5003.2  326.41  5031.3  326.91  5031.8  328.57    5050  334.16  5063.1  335.41
  5244.5  340.35  5330.2  345.58  5428.5  350.04  5480.7   354.7  5522.5   355.9
#Mann= 5 ,-1 , 0
  3551.6     .05       0  4949.2      .1       0  5002.7     .05       0
  5031.3      .1       0  5244.5     .07       0
Bank Sta=5002.7,5031.3
XS Rating Curve= 0 ,0
Exp/Cntr=0.3,0.1

Type RM Length L Ch R = 1 ,2813    ,556,556,556
BEGIN DESCRIPTION:
BUCK BRANCH 2.0
END DESCRIPTION:
XS GIS Cut Line= 3
      2480250.29     13797521.78        2479025.       13797175.
      2478178.72     13797427.61
#Sta/Elev= 30
  3726.6  347.94  4061.6  343.39  4134.5  344.05    4179   344.3  4199.8  343.43
  4310.2  342.58    4580  343.06  4589.3  342.93  4763.8  339.89  4797.7  338.24
  4873.7  336.18  4937.7  334.28  4968.7  327.54  4969.2  327.04  4997.3  327.54
  4997.4  330.37  5002.6  330.37  5010.5  333.12  5016.6  334.15  5021.8  333.11
  5049.7  334.41  5093.9  335.15  5192.7  333.84  5271.4  335.46  5401.9  335.35
  5417.5  336.46  5558.9   339.2  5636.6  341.48  5766.2  347.36  5883.2  350.73
#Mann= 10 ,-1 , 0
  3726.6     .05       0  4134.5     .07       0  4310.2     .05       0
    4580     .07       0  4589.3     .05       0  4873.7      .1       0
  4968.7     .05       0  4997.3      .1       0  5558.9     .12       0
  5766.2     .07       0
Bank Sta=4968.7,4997.3
XS Rating Curve= 0 ,0
Exp/Cntr=0.3,0.1

Type RM Length L Ch R = 1 ,2257    ,491,491,491
BEGIN DESCRIPTION:
X18370
END DESCRIPTION:
XS GIS Cut Line= 3
      2479807.55     13796912.39      2479005.47     13796683.23
        2477693.      13796792.6
#Sta/Elev= 30
    4084  343.76  4276.9  345.14  4375.7  343.78  4471.5  343.03  4575.5  340.05
  4635.7  340.28  4720.2  337.82  4793.9  339.17  4938.7  334.35  4968.8  334.66
  4988.9  332.16  4994.4  325.65  4994.9  325.15  5023.6  325.65    5029  332.65
  5039.1  333.44  5068.7  332.81    5310  333.23  5400.3  335.03  5520.7   335.5
  5603.9  336.51  5719.3  340.11  5751.5  338.49  5771.6  340.16  5801.7  338.22
  5844.7  338.37    5902   342.3  5960.1  342.12  6002.4  344.47  6235.2  349.62
#Mann= 6 ,-1 , 0
    4084     .05       0  4375.7     .07       0  4720.2      .1       0
  4994.4     .05       0  5023.6      .1       0  5068.7     .05       0
Bank Sta=4994.4,5023.6
XS Rating Curve= 0 ,0
Exp/Cntr=0.3,0.1

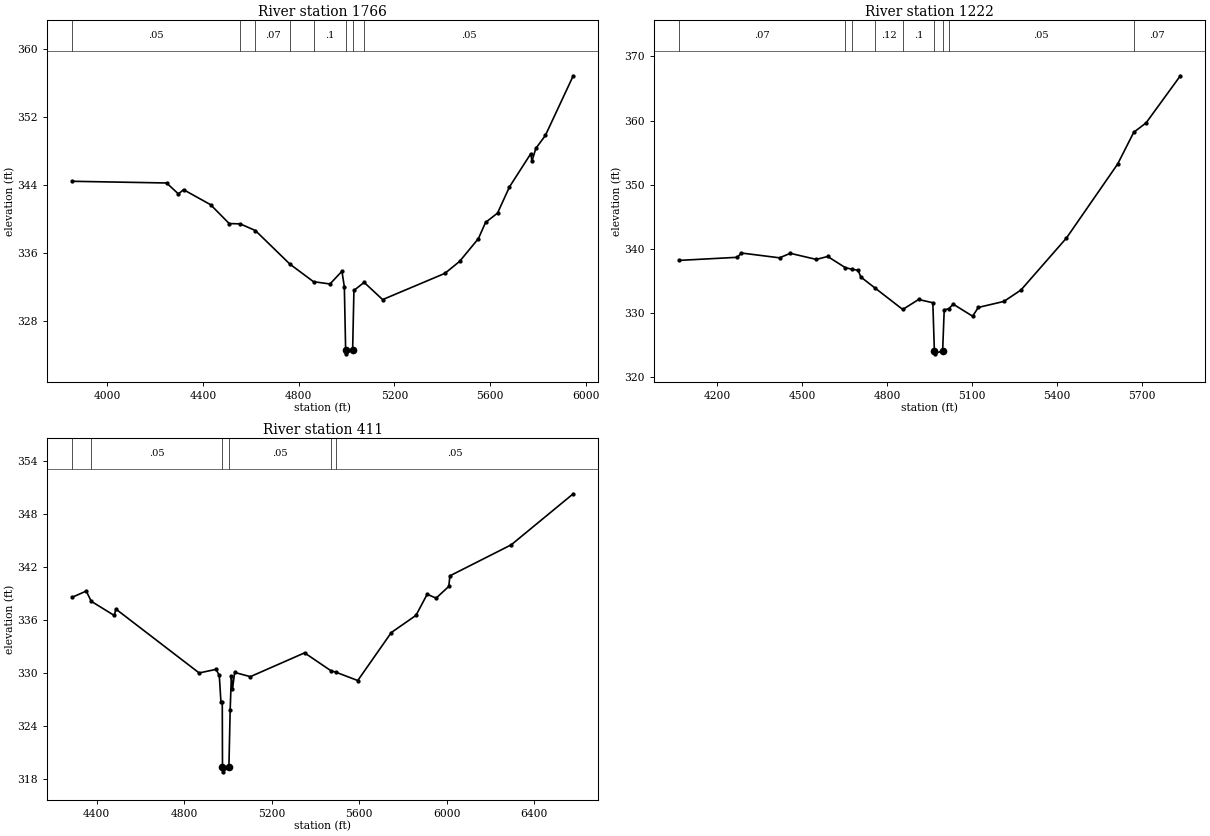
Type RM Length L Ch R = 1 ,1766    ,544,544,544
BEGIN DESCRIPTION:
X18371
END DESCRIPTION:
XS GIS Cut Line= 3
      2479791.93     13796776.99      2479198.17     13796204.06
      2477928.66     13796245.68
#Sta/Elev= 30
    3852  344.47  4247.3  344.27  4296.7  342.98  4318.1  343.48  4431.3  341.71
    4509  339.49  4555.3  339.45  4618.3  338.67  4762.9  334.71  4861.5  332.64
  4930.4  332.37  4980.4  333.87  4990.4  332.04  4995.8  324.64  4996.3  324.14
  5025.1  324.64  5030.5  331.61  5073.1  332.56  5150.5  330.53  5410.7  333.62
  5472.2  335.03  5550.7  337.71  5580.8  339.62  5630.8  340.72  5680.8  343.81
  5769.8  347.72  5774.8  346.84  5790.9  348.34  5830.9  349.87  5947.3   356.9
#Mann= 8 ,-1 , 0
    3852     .05       0  4555.3    .035       0  4618.3     .07       0
  4762.9     .12       0  4861.5      .1       0  4995.8     .05       0
  5025.1      .1       0  5073.1     .05       0
Bank Sta=4995.8,5025.1
XS Rating Curve= 0 ,0
Exp/Cntr=0.3,0.1

Type RM Length L Ch R = 1 ,1222    ,811,811,811
BEGIN DESCRIPTION:
X18372
END DESCRIPTION:
XS GIS Cut Line= 3
       2479578.4     13795954.07      2478916.92     13795714.48
      2477854.45     13795818.64
#Sta/Elev= 30
  4065.8  338.18  4271.5  338.66  4285.4  339.33  4420.4  338.58  4458.6  339.28
  4550.5  338.33  4590.6  338.79  4652.5  337.06  4676.5  336.79  4698.3  336.64
  4707.6  335.59  4756.1  333.93  4855.9  330.52  4911.9  332.08  4962.2  331.57
  4967.6   324.1  4968.1   323.6  4996.9   324.1  5002.4  330.46  5018.6  330.64
  5034.2  331.35  5102.8  329.47  5122.9  330.84  5213.4  331.78  5273.7  333.56
  5434.4  341.67  5615.3  353.21  5672.3  358.17  5715.8  359.63  5836.9  366.98
#Mann= 9 ,-1 , 0
  4065.8     .07       0  4652.5     .12       0  4676.5     .07       0
  4756.1     .12       0  4855.9      .1       0  4967.6     .05       0
  4996.9      .1       0  5018.6     .05       0  5672.3     .07       0
Bank Sta=4967.6,4996.9
XS Rating Curve= 0 ,0
Exp/Cntr=0.3,0.1

Type RM Length L Ch R = 1 ,411     ,0,0,0
BEGIN DESCRIPTION:
BUCK BRANCH 1.0
END DESCRIPTION:
XS GIS Cut Line= 3
      2479557.57      13795532.2      2479000.26     13795131.14
      2477432.51     13795469.69
#Sta/Elev= 30
  4287.8  338.56  4352.6  339.27  4375.7  338.11  4480.9   336.5  4488.1  337.23
  4868.8  329.98  4946.1  330.39  4960.8   329.7  4968.4  326.63  4974.4  326.63
  4975.4  319.26  4975.9  318.76  5004.7  319.26  5010.5  325.83    5016  329.59
  5021.1  328.15  5030.9  330.04  5102.6  329.56  5350.6  332.26  5472.2  330.21
  5492.3  330.08  5593.6  329.12  5747.1  334.57  5859.6  336.51  5910.8  338.91
  5951.7  338.47  6009.6   339.8  6014.7     341    6295  344.52  6578.3  350.31
#Mann= 6 ,-1 , 0
  4287.8     .07       0  4375.7     .05       0  4975.4     .05       0
  5004.7     .05       0  5472.2    .035       0  5492.3     .05       0
Bank Sta=4975.4,5004.7
XS Rating Curve= 0 ,0
Exp/Cntr=0.3,0.1

Chan Stop Cuts=-1
Use User Specified Reach Order=0
Composite Channel Slope=5