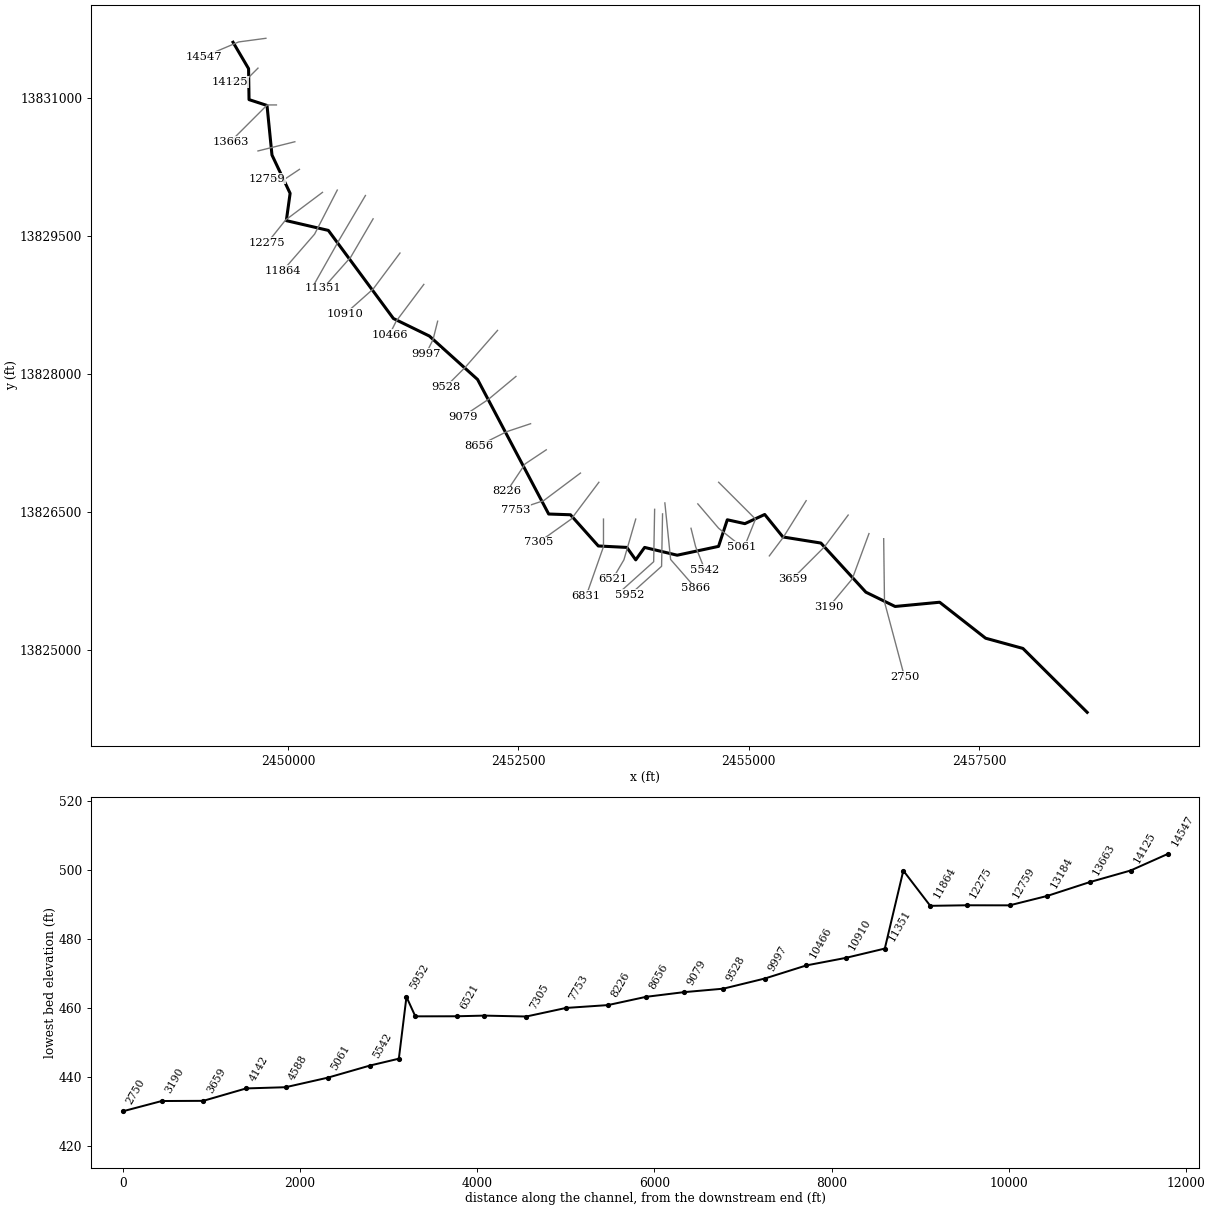
--- Bear Gulch.prj (project) ---

Proj Title=Bear Gulch Base Level Engineering
Current Plan=p01
Default Exp/Contr=0.3,0.1
English Units
Geom File=g01
Flow File=f01
Plan File=p01
Y Axis Title=Elevation
X Axis Title(PF)=Main Channel Distance
X Axis Title(XS)=Station
BEGIN DESCRIPTION:
Bear Gulch
END DESCRIPTION:
DSS Export Rating Curves= 0
DSS Export Rating Curve Sorted= 0
DSS Export Volume Flow Curves= 0
DXF OffsetX= 0
DXF OffsetY= 0
DXF ScaleX= 1
DXF ScaleY= 10

--- Bear Gulch.p01 (plan) ---

Plan Title=Multiple Run
Short Identifier=Multiple
Geom File=g01
Flow File=f01
Subcritical Flow
K Sum by GR= 0
Std Step Tol= 0.01
Critical Tol= 0.01
Num of Std Step Trials= 20
Max Error Tol= 0.3
Flow Tol Ratio= 0.001
Split Flow NTrial= 30
Split Flow Tol= 0.02
Split Flow Ratio= 0.02
Log Output Level= 0
Friction Slope Method= 1
Unsteady Friction Slope Method= 2
Unsteady Bridges Friction Slope Method= 1
Parabolic Critical Depth
Global Vel Dist=  1 , 1 , 1
Global Log Level= 0
CheckData=True
Encroach Param= -1, 0, 0, 0
BEGIN DESCRIPTION:
Multiple Run
END DESCRIPTION:

--- Bear Gulch.f01 (steady flow) ---

Flow Title=Multiple
Number of Profiles=7
Profile Names=10-year,25-year,50-year,1pct_min,100-year,1pct_plu,500-year
River Rch & RM= Bear Gulch,Reach-1,14547
     890    1468    2003    1324    2642    5271    4549
River Rch & RM= Bear Gulch,Reach-1,12275
    1242    2085    2879    1923    3836    7654    6748
River Rch & RM= Bear Gulch,Reach-1,9528
    1426    2401    3320    2219    4427    8833    7799
River Rch & RM= Bear Gulch,Reach-1,4142
    2221    3819    5355    3625    7232   14430   13074
Boundary for River Rch & Prof#=Bear Gulch,Reach-1,1
Up Type=0
Dn Type=3
Dn Slope=0.005
Boundary for River Rch & Prof#=Bear Gulch,Reach-1,2
Up Type=0
Dn Type=3
Dn Slope=0.005
Boundary for River Rch & Prof#=Bear Gulch,Reach-1,3
Up Type=0
Dn Type=3
Dn Slope=0.005
Boundary for River Rch & Prof#=Bear Gulch,Reach-1,4
Up Type=0
Dn Type=3
Dn Slope=0.005
Boundary for River Rch & Prof#=Bear Gulch,Reach-1,5
Up Type=0
Dn Type=3
Dn Slope=0.005
Boundary for River Rch & Prof#=Bear Gulch,Reach-1,6
Up Type=0
Dn Type=3
Dn Slope=0.005
Boundary for River Rch & Prof#=Bear Gulch,Reach-1,7
Up Type=0
Dn Type=3
Dn Slope=0.005

--- Bear Gulch.g01 (geometry) ---

Geom Title=Existing Conditions
Program Version=4.10

River Reach=Bear Gulch      ,Reach-1
Reach XY= 30
      2449404.23     13831606.16      2449572.93     13831319.14
      2449577.91     13830982.91      2449773.03     13830919.35
      2449826.83      13830381.1      2450023.78      13829964.5
      2449982.75     13829667.84      2450438.67     13829561.77
      2451144.73     13828604.49      2451534.68     13828414.22
      2452058.54     13827941.75      2452830.08     13826480.03
       2453066.7     13826471.93      2453368.83     13826132.86
      2453678.58     13826117.12        2453775.      13825981.9
      2453871.42     13826117.12      2454225.01     13826032.53
      2454673.81     13826128.45      2454768.92     13826417.53
      2454959.73     13826375.38        2455175.       13826475.
      2455372.45     13826230.73       2455784.8     13826164.52
       2456272.7     13825630.83      2456590.21     13825475.51
      2457073.54     13825521.47      2457572.57     13825130.52
      2457977.43     13825019.48        2458675.       13824325.

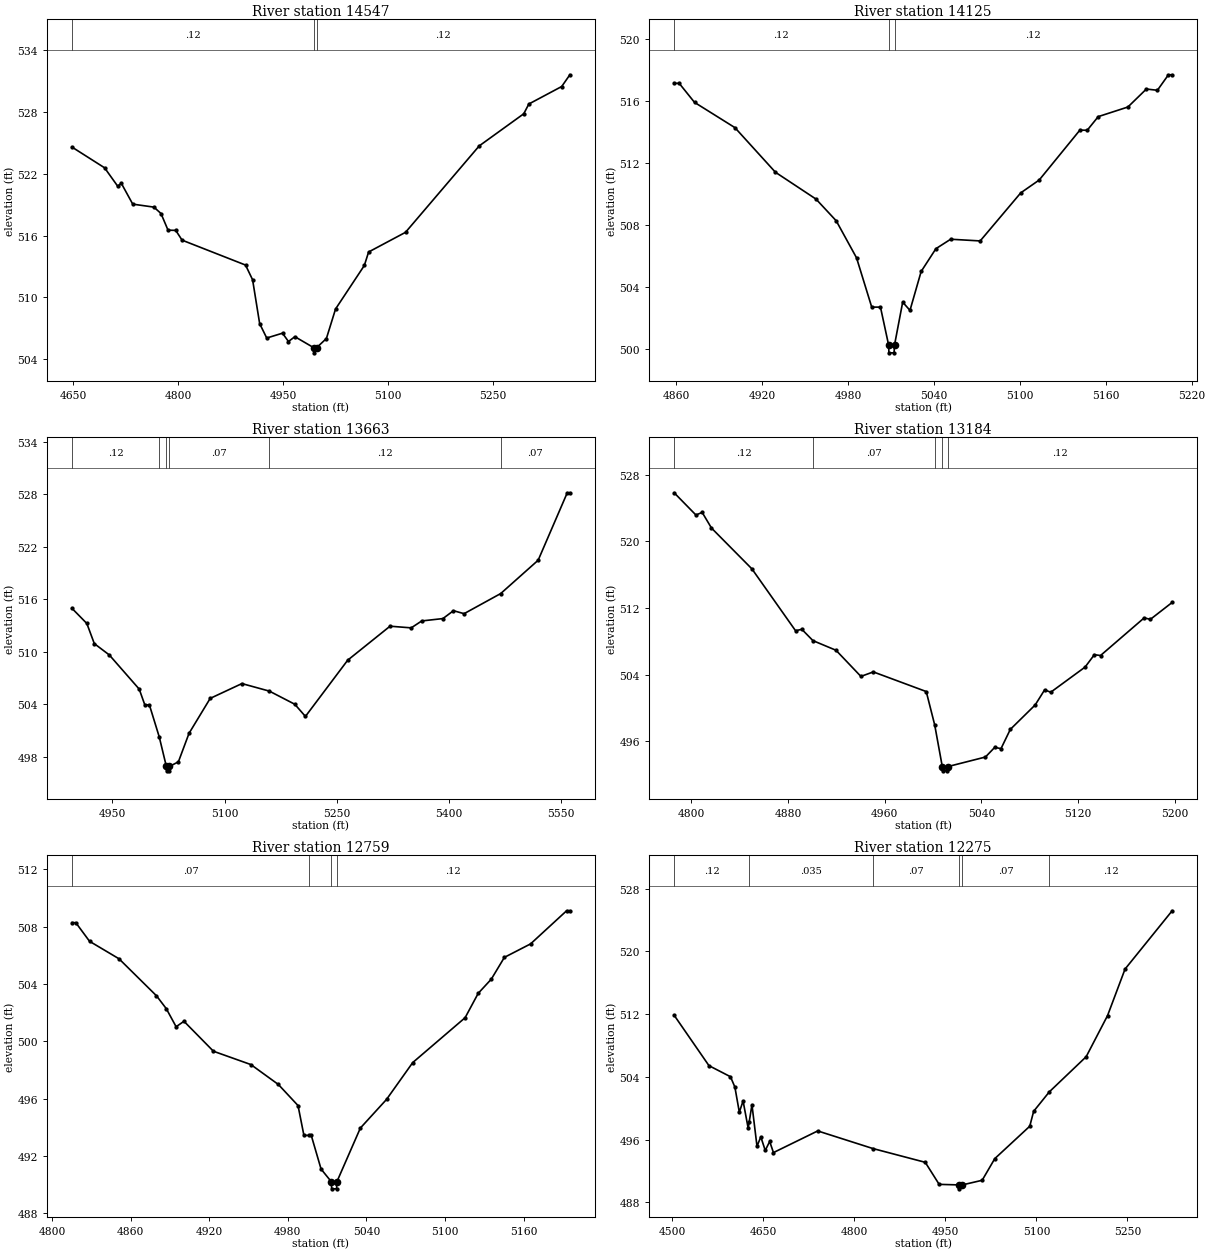
Type RM Length L Ch R = 1 ,14547   ,422,422,422
BEGIN DESCRIPTION:
X18162
END DESCRIPTION:
XS GIS Cut Line= 3
      2449761.33     13831649.23      2449465.59     13831609.52
      2449084.25     13831447.83
#Sta/Elev= 30
  4647.8   524.6  4694.6  522.58  4713.4  520.79  4718.5  521.08  4734.9  519.05
  4765.2  518.76  4775.3  518.14  4785.4  516.52  4796.4   516.5  4805.5  515.55
  4896.3  513.13  4906.4   511.7  4916.5  507.44  4926.6  506.04  4949.2  506.51
  4957.7   505.7  4966.9  506.17  4993.9   505.1  4994.2   504.6    4998   505.1
    5012  505.99  5025.1  508.86  5066.3  513.09  5072.4   514.4  5125.2  516.31
  5230.7  524.71  5294.4  527.83  5301.7  528.78  5348.7  530.48  5360.4  531.62
#Mann= 3 ,-1 , 0
  4647.8     .12       0  4993.9     .05       0    4998     .12       0
Bank Sta=4993.9,4998
XS Rating Curve= 0 ,0
Exp/Cntr=0.3,0.1

Type RM Length L Ch R = 1 ,14125   ,462,462,462
BEGIN DESCRIPTION:
Bear Gulch 29.0
END DESCRIPTION:
XS GIS Cut Line= 3
      2449675.01     13831325.01        2449575.       13831225.
      2449374.99       13831175.
#Sta/Elev= 30
  4858.7  517.17  4862.2  517.17  4872.9  515.94  4901.1  514.31  4929.4  511.43
  4957.7   509.7  4971.8   508.3    4986  505.91  4996.6  502.73  5002.7  502.73
  5008.4  500.28  5008.6  499.78  5012.2  499.78  5012.5  500.28  5018.2  503.05
  5023.3  502.52  5031.1  505.03  5041.4   506.5  5051.7  507.11  5072.3     507
  5100.6   510.1  5113.5  510.93  5141.9  514.15    5147  514.14  5154.7  515.02
  5175.4  515.64  5188.3   516.8    5196  516.72  5203.7  517.72  5206.3  517.72
#Mann= 3 ,-1 , 0
  4858.7     .12       0  5008.4     .05       0  5012.5     .12       0
Bank Sta=5008.4,5012.5
XS Rating Curve= 0 ,0
Exp/Cntr=0.3,0.1

Type RM Length L Ch R = 1 ,13663   ,479,479,479
BEGIN DESCRIPTION:
Bear Gulch 28.0
END DESCRIPTION:
XS GIS Cut Line= 3
      2449875.02       13830925.        2449775.       13830925.
        2449375.       13830525.
#Sta/Elev= 30
  4895.9  514.98  4915.9  513.24  4925.9  510.94  4945.9  509.65  4985.9  505.75
  4993.4  503.95  4999.5  503.95  5012.7  500.29  5022.2  496.92  5022.4  496.42
    5026  496.42  5026.3  496.92  5038.3  497.45  5052.5   500.7  5080.8  504.69
  5123.2  506.38  5159.9  505.52  5193.9  504.02  5208.1  502.63  5264.6  509.05
  5321.2  512.93  5349.5  512.74  5363.6  513.53  5391.9   513.8    5406   514.7
  5420.2  514.36  5469.2  516.66  5519.2  520.46  5558.1  528.16  5561.6  528.16
#Mann= 6 ,-1 , 0
  4895.9     .12       0  5012.7     .07       0  5022.2     .05       0
  5026.3     .07       0  5159.9     .12       0  5469.2     .07       0
Bank Sta=5022.2,5026.3
XS Rating Curve= 0 ,0
Exp/Cntr=0.3,0.1

Type RM Length L Ch R = 1 ,13184   ,425,425,425
BEGIN DESCRIPTION:
Bear Gulch 27.0
END DESCRIPTION:
XS GIS Cut Line= 3
        2450075.       13830525.        2449875.       13830475.
      2449675.01       13830425.
#Sta/Elev= 30
  4785.7  525.85  4803.7  523.18  4808.9  523.49  4816.6  521.61  4850.1   516.7
  4886.2  509.27  4891.4  509.44  4900.6  508.08  4919.7  506.92  4940.3  503.78
  4950.6  504.32  4994.4  501.96  5001.4  497.95  5007.7  492.93    5008  492.43
  5011.7  492.43    5012  492.93  5043.4  494.09  5051.1  495.25  5056.3   495.1
    5064  497.41  5084.6  500.35  5092.4  502.16  5097.5  501.88  5125.9   504.9
  5133.6  506.39  5138.7  506.29  5174.8  510.81    5180  510.64    5198  512.67
#Mann= 5 ,-1 , 0
  4785.7     .12       0  4900.6     .07       0  5001.4     .12       0
  5007.7     .05       0    5012     .12       0
Bank Sta=5007.7,5012
XS Rating Curve= 0 ,0
Exp/Cntr=0.3,0.1

Type RM Length L Ch R = 1 ,12759   ,484,484,484
BEGIN DESCRIPTION:
Bear Gulch 26.0
END DESCRIPTION:
XS GIS Cut Line= 3
      2450124.98     13830224.99        2449975.       13830125.
      2449774.95       13830125.
#Sta/Elev= 30
  4815.1  508.28  4818.1  508.28  4828.6  506.98  4851.1  505.76  4879.7  503.18
  4887.2  502.28  4894.7  501.02  4900.7   501.4  4923.2  499.31  4951.8  498.38
  4972.8  496.99  4987.8  495.52  4992.3  493.44  4996.2  493.44  4997.9  493.44
  5005.4  491.09  5013.2  490.21  5013.5  489.71  5017.2  489.71  5017.5  490.21
  5035.4  493.95  5055.4  495.95  5075.4  498.52  5115.4  501.65  5125.4  503.35
  5135.4  504.34  5145.4  505.86  5165.4   506.8  5192.9  509.11  5195.4  509.11
#Mann= 4 ,-1 , 0
  4815.1     .07       0  4996.2     .12       0  5013.2     .05       0
  5017.5     .12       0
Bank Sta=5013.2,5017.5
XS Rating Curve= 0 ,0
Exp/Cntr=0.3,0.1

Type RM Length L Ch R = 1 ,12275   ,411,411,411
BEGIN DESCRIPTION:
Bear Gulch 25.0
END DESCRIPTION:
XS GIS Cut Line= 3
      2450374.99     13829974.99        2449975.       13829675.
      2449775.03     13829425.03
#Sta/Elev= 30
  4503.5  511.85  4560.8  505.43  4596.2  504.02  4603.5   502.7  4610.8   499.5
    4617  500.93  4625.4  497.45  4627.1  498.27  4631.6  500.45  4639.9  495.16
  4646.2  496.35  4653.5  494.62  4660.8  495.77    4667  494.35  4739.9  497.11
  4830.6  494.87    4917  493.11  4939.9   490.3  4972.7  490.23  4973.1  489.73
    4978  490.23  5010.7  490.82  5031.5  493.58  5089.1  497.71  5095.5  499.61
  5121.3  502.09    5182  506.57  5217.2  511.81    5246  517.74  5323.6  525.17
#Mann= 6 ,-1 , 0
  4503.5     .12       0  4627.1    .035       0  4830.6     .07       0
  4972.7     .05       0    4978     .07       0  5121.3     .12       0
Bank Sta=4972.7,4978
XS Rating Curve= 0 ,0
Exp/Cntr=0.3,0.1

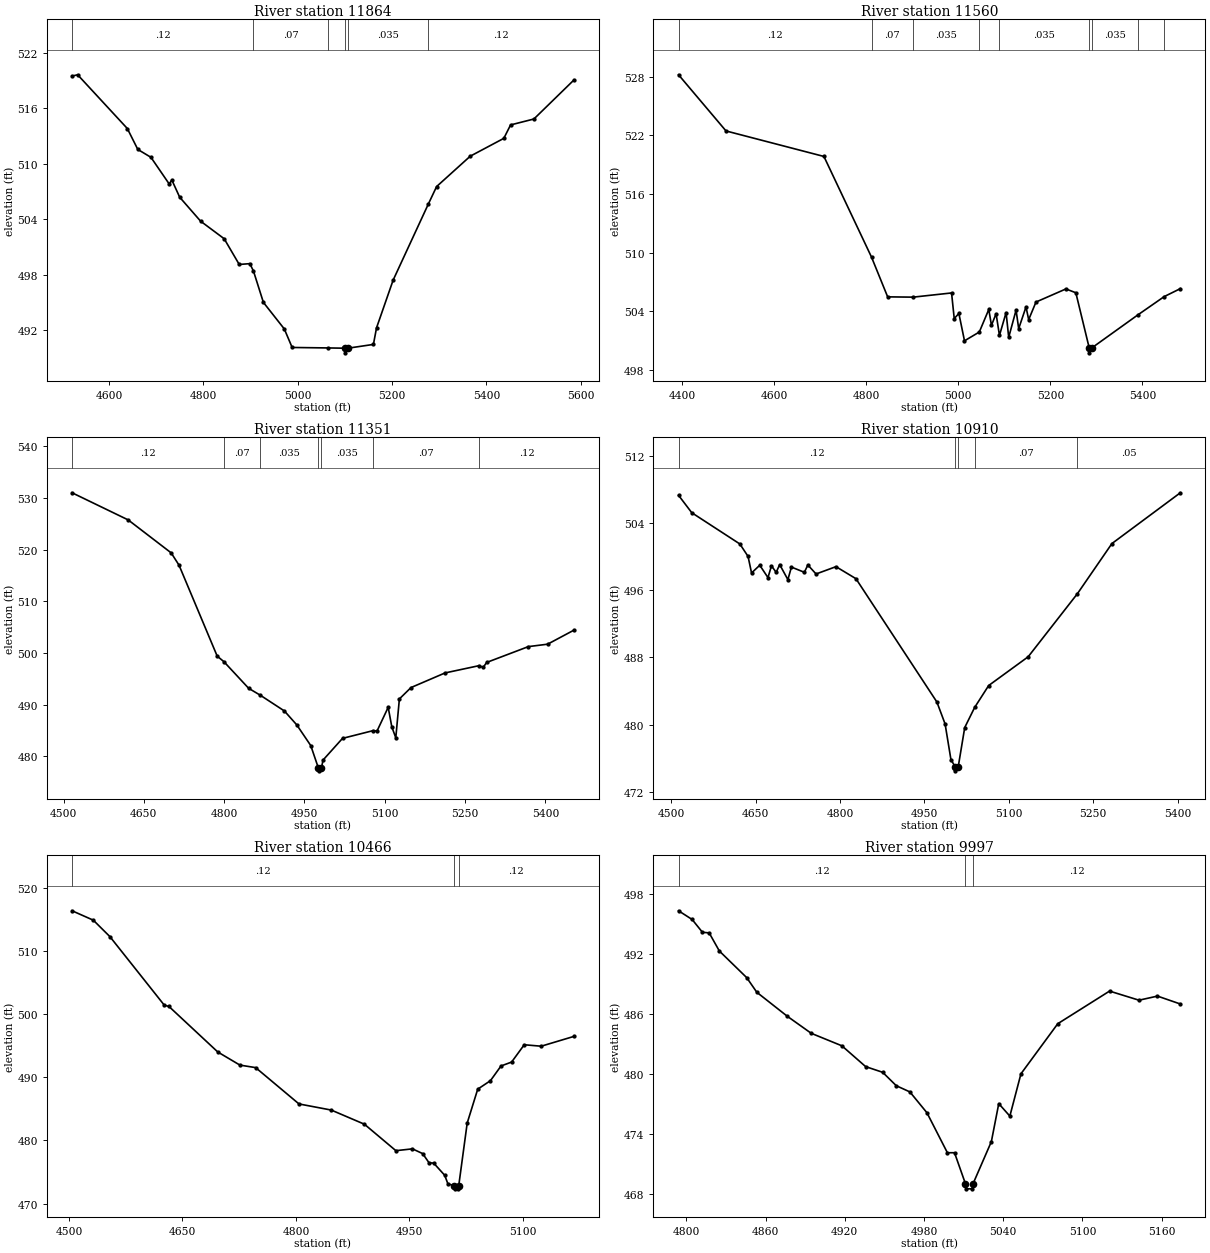
Type RM Length L Ch R = 1 ,11864   ,304,304,304
BEGIN DESCRIPTION:
Bear Gulch 24.0
END DESCRIPTION:
XS GIS Cut Line= 3
      2450535.71     13829999.98      2450289.16     13829520.77
      2449945.39     13829124.91
#Sta/Elev= 30
    4522  519.48  4533.8  519.62  4639.1  513.81  4661.3  511.55  4689.1   510.7
  4727.8  507.82  4733.4  508.25    4750  506.39  4794.3   503.8  4844.3   501.9
  4876.2  499.12  4898.7  499.21  4906.4   498.4  4927.4  495.02  4971.7  492.15
  4988.3  490.15  5064.1   490.1  5100.8  490.07  5101.2  489.57  5106.3  490.07
  5160.5  490.48  5167.1  492.27  5202.3  497.43  5276.5  505.61  5294.4  507.54
  5365.6  510.82  5436.8  512.75  5451.1   514.2  5500.5  514.84  5585.2  519.05
#Mann= 6 ,-1 , 0
    4522     .12       0  4906.4     .07       0  5064.1    .035       0
  5100.8     .05       0  5106.3    .035       0  5276.5     .12       0
Bank Sta=5100.8,5106.3
XS Rating Curve= 0 ,0
Exp/Cntr=0.3,0.1

Type RM Length L Ch R = 1 ,11560   ,209,209,209
BEGIN DESCRIPTION:
X18161
END DESCRIPTION:
XS GIS Cut Line= 3
      2450841.25     13829940.93      2450556.52     13829458.27
      2450296.08     13828996.43
#Sta/Elev= 30
  4391.9  528.21  4495.1  522.46  4707.9  519.85  4811.3  509.55  4846.4  505.48
  4901.8  505.45  4985.3  505.88  4991.1  503.26  5001.2  503.78  5013.4  500.98
  5045.6  501.88  5066.2  504.19    5072  502.57  5082.1  503.75  5089.4  501.53
  5103.8  503.87  5109.5  501.34  5125.5  504.12  5131.2  502.23  5147.1  504.45
  5152.9  503.15  5168.8  504.95  5233.8  506.29  5255.4   505.9  5284.5  500.25
    5285  499.75    5290  500.25  5390.1  503.63  5447.6  505.51  5482.5  506.32
#Mann= 9 ,-1 , 0
  4391.9     .12       0  4811.3     .07       0  4901.8    .035       0
  5045.6     .07       0  5089.4    .035       0  5284.5    .035       0
    5290    .035       0  5390.1     .12       0  5447.6    .035       0
Bank Sta=5284.5,5290
XS Rating Curve= 0 ,0
Exp/Cntr=0.3,0.1

Type RM Length L Ch R = 1 ,11351   ,441,441,441
BEGIN DESCRIPTION:
Bear Gulch 23.0
END DESCRIPTION:
XS GIS Cut Line= 3
      2450924.59     13829687.46      2450681.52     13829270.77
      2450379.71      13828930.8
#Sta/Elev= 30
    4516     531  4620.8  525.75    4701  519.38  4715.7     517    4787   499.4
  4799.5  498.33  4845.7  493.18  4867.6  491.83  4912.5  488.79  4935.6   486.1
  4961.7   482.1  4976.1  477.71  4976.6  477.21  4981.6  477.71  4984.6  479.29
    5021  483.49  5078.2  484.99  5085.4   484.9  5106.3   489.5  5113.1  485.69
  5120.5  483.61  5127.2  491.12  5148.9  493.32  5212.5  496.15  5276.2  497.56
  5283.6  497.21  5290.2  498.18    5368  501.24    5404  501.71    5453  504.42
#Mann= 7 ,-1 , 0
    4516     .12       0  4799.5     .07       0  4867.6    .035       0
  4976.1    .035       0  4981.6    .035       0  5078.2     .07       0
  5276.2     .12       0
Bank Sta=4976.1,4981.6
XS Rating Curve= 0 ,0
Exp/Cntr=0.3,0.1

Type RM Length L Ch R = 1 ,10910   ,444,444,444
BEGIN DESCRIPTION:
Bear Gulch 22.0
END DESCRIPTION:
XS GIS Cut Line= 3
      2451216.21     13829315.87        2450925.       13828925.
      2450622.51      13828656.2
#Sta/Elev= 30
  4512.8  507.29  4536.3  505.22  4621.8   501.5  4636.4  500.02  4642.6  498.05
  4657.2  498.97  4671.8   497.5    4678   498.9  4686.4  498.12  4692.6  499.05
  4707.2  497.26  4713.5  498.75  4736.5  498.13  4742.7     499  4757.3  497.93
  4792.7   498.8  4828.2  497.37  4972.1   482.7  4986.7  480.09  4997.1  475.84
  5004.5  475.01    5005  474.51  5010.1  475.01  5021.6  479.66  5039.3  482.06
  5064.2  484.66  5134.4  488.08    5222  495.59  5283.3  501.55  5404.9  507.59
#Mann= 5 ,-1 , 0
  4512.8     .12       0  5004.5     .05       0  5010.1     .12       0
  5039.3     .07       0    5222     .05       0
Bank Sta=5004.5,5010.1
XS Rating Curve= 0 ,0
Exp/Cntr=0.3,0.1

Type RM Length L Ch R = 1 ,10466   ,469,469,469
BEGIN DESCRIPTION:
Bear Gulch 21.0
END DESCRIPTION:
XS GIS Cut Line= 4
        2451475.       13828975.        2451175.       13828575.
        2451125.       13828475.      2451101.93     13828428.85
#Sta/Elev= 30
  4504.1  516.36  4532.2  514.87  4554.1  512.27    4626  501.42  4632.2  501.21
  4696.8     494    4726  491.93  4746.8  491.53  4804.1  485.78  4846.8  484.81
  4890.6  482.57  4932.2  478.38  4954.1  478.67  4967.6  477.92    4976  476.47
  4982.2  476.41  4996.8  474.48    5001  473.12  5009.6  472.84  5010.1  472.34
  5014.8  472.34  5015.3  472.84  5026.5  482.76  5040.4  488.12  5057.2  489.46
  5071.2  491.79  5085.2  492.41  5101.9  495.15  5124.3  494.92  5167.5  496.47
#Mann= 3 ,-1 , 0
  4504.1     .12       0  5009.6     .05       0  5015.3     .12       0
Bank Sta=5009.6,5015.3
XS Rating Curve= 0 ,0
Exp/Cntr=0.3,0.1

Type RM Length L Ch R = 1 ,9997    ,469,469,469
BEGIN DESCRIPTION:
Bear Gulch 20.0
END DESCRIPTION:
XS GIS Cut Line= 4
        2451625.     13828575.02        2451575.       13828375.
        2451525.       13828275.      2451497.26     13828219.52
#Sta/Elev= 30
  4794.1  496.35  4804.4  495.48  4812.2   494.2  4817.3  494.14    4825  492.33
  4845.7  489.67  4853.4   488.2  4876.6  485.79  4894.6   484.1  4917.8  482.85
  4935.8  480.77  4948.7   480.2    4959  478.86  4969.3  478.24  4982.2  476.16
  4997.7  472.16  5003.1  472.16  5011.4  469.05  5011.8  468.55  5016.6  468.55
  5017.1  469.05    5031  473.27  5036.6  477.07    5045  475.82  5053.4  480.05
  5081.3  485.06  5120.5  488.32  5142.8  487.41  5156.8  487.82  5174.1  487.03
#Mann= 3 ,-1 , 0
  4794.1     .12       0  5011.4     .05       0  5017.1     .12       0
Bank Sta=5011.4,5017.1
XS Rating Curve= 0 ,0
Exp/Cntr=0.3,0.1

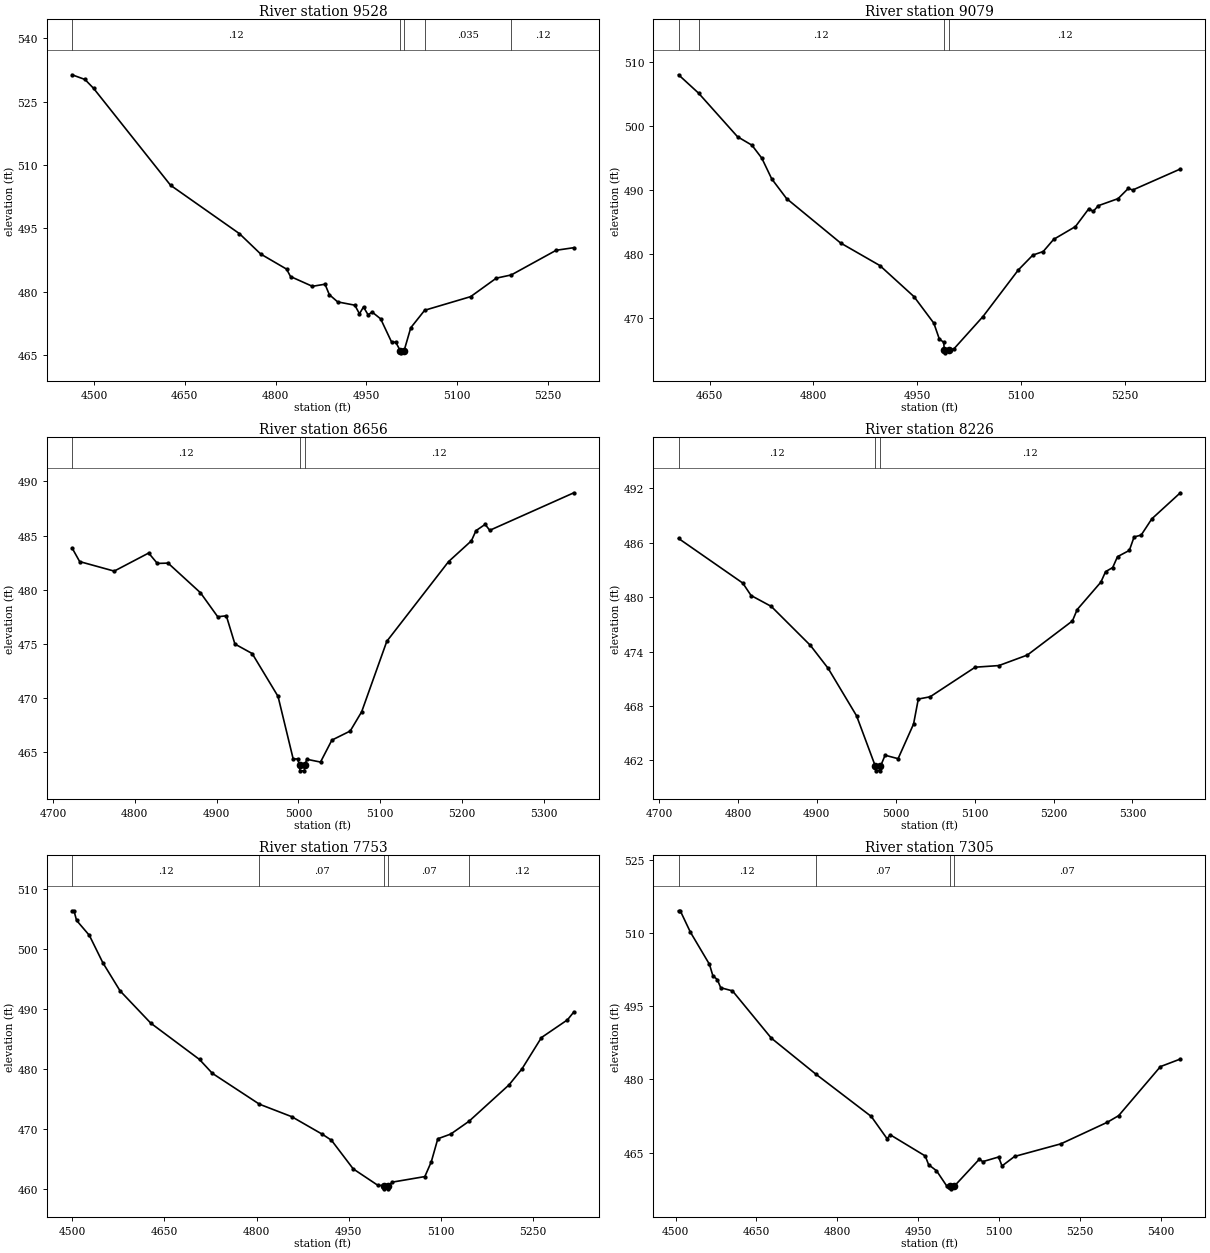
Type RM Length L Ch R = 1 ,9528    ,449,449,449
BEGIN DESCRIPTION:
Bear Gulch 19.0
END DESCRIPTION:
XS GIS Cut Line= 4
      2452274.99     13828474.99        2451925.       13828075.
        2451775.       13827925.      2451714.35     13827864.35
#Sta/Elev= 30
  4463.7  531.32    4485  530.21  4499.3  528.11  4626.5  505.21  4740.4  493.77
  4775.5  488.96  4818.2   485.4  4824.8  483.64  4860.9  481.33  4881.8  481.83
  4888.9  479.36  4902.7  477.65  4931.1  476.87  4938.7  474.84  4945.4  476.45
    4953  474.59  4959.6  475.26  4973.8  473.63  4991.9  468.13  4998.7  468.13
  5006.2  466.11  5006.7  465.61  5012.5  466.11  5023.5  471.53  5046.5  475.67
  5122.5  478.89  5164.9  483.26  5189.7  484.02  5263.9  489.85  5293.1  490.46
#Mann= 5 ,-1 , 0
  4463.7     .12       0  5006.2     .05       0  5012.5     .12       0
  5046.5    .035       0  5189.7     .12       0
Bank Sta=5006.2,5012.5
XS Rating Curve= 0 ,0
Exp/Cntr=0.3,0.1

Type RM Length L Ch R = 1 ,9079    ,423,423,423
BEGIN DESCRIPTION:
Bear Gulch 18.0
END DESCRIPTION:
XS GIS Cut Line= 4
      2452475.02     13827975.01        2452175.       13827725.
        2452025.       13827625.      2451896.37     13827539.25
#Sta/Elev= 30
    4605  508.03    4634  505.16  4690.3  498.35  4711.1  497.03  4725.4     495
  4739.7  491.77  4761.2  488.69  4839.3  481.75    4896  478.23  4945.4  473.37
  4974.1  469.22  4981.9  466.78  4988.4  466.22  4989.1  465.09  4989.6  464.59
  4995.5  465.09    5003   465.2  5045.1  470.26  5096.2  477.54  5117.2  479.86
  5132.2  480.42  5147.3  482.32  5178.8  484.32  5198.3  487.13  5204.4  486.68
  5211.9  487.58  5240.4  488.68  5255.4   490.3  5261.4  490.02  5330.4  493.31
#Mann= 4 ,-1 , 0
    4605    .035       0    4634     .12       0  4989.1     .05       0
  4995.5     .12       0
Bank Sta=4989.1,4995.5
XS Rating Curve= 0 ,0
Exp/Cntr=0.3,0.1

Type RM Length L Ch R = 1 ,8656    ,430,430,430
BEGIN DESCRIPTION:
Bear Gulch 17.0
END DESCRIPTION:
XS GIS Cut Line= 5
      2452633.82     13827461.27        2452525.       13827425.
        2452375.       13827375.        2452175.       13827275.
      2452070.56     13827222.78
#Sta/Elev= 30
  4723.3  483.85  4732.6  482.59  4774.8  481.71  4816.9  483.38  4827.5  482.42
  4840.6  482.45  4880.2  479.71  4901.3  477.49  4911.8  477.58  4922.3  474.97
  4943.4  474.09    4975  470.13  4993.5  464.35  4998.9  464.35  5001.3  463.75
  5001.8  463.25  5007.2  463.25  5007.7  463.75  5010.1  464.32  5026.9  464.06
  5040.8  466.09  5063.2  466.93  5077.2  468.71  5107.9  475.22  5183.4  482.59
  5211.3  484.51  5216.9  485.45  5228.1  486.03  5233.7  485.48  5336.5  488.95
#Mann= 3 ,-1 , 0
  4723.3     .12       0  5001.3     .05       0  5007.7     .12       0
Bank Sta=5001.3,5007.7
XS Rating Curve= 0 ,0
Exp/Cntr=0.3,0.1

Type RM Length L Ch R = 1 ,8226    ,473,473,473
BEGIN DESCRIPTION:
Bear Gulch 16.0
END DESCRIPTION:
XS GIS Cut Line= 4
        2452804.     13827177.67        2452725.       13827125.
        2452575.       13827025.      2452374.99     13826724.98
#Sta/Elev= 30
  4724.8  486.47  4806.2  481.55  4816.7  480.18  4842.3  478.98  4891.9  474.68
  4914.4  472.15  4950.4  466.92  4974.2  461.36  4974.7  460.86  4980.2  460.86
  4980.7  461.36  4986.5  462.58    5003   462.2  5022.6  466.02  5028.6  468.77
  5043.6  469.02  5100.7  472.28  5130.7  472.46  5166.8  473.62  5223.9  477.38
  5229.9  478.63  5259.9  481.65  5265.9  482.81  5274.9  483.26    5281  484.46
    5296  485.15    5302  486.63    5311  486.84  5324.5  488.63  5360.6   491.5
#Mann= 3 ,-1 , 0
  4724.8     .12       0  4974.2     .05       0  4980.7     .12       0
Bank Sta=4974.2,4980.7
XS Rating Curve= 0 ,0
Exp/Cntr=0.3,0.1

Type RM Length L Ch R = 1 ,7753    ,448,448,448
BEGIN DESCRIPTION:
Bear Gulch 15.0
END DESCRIPTION:
XS GIS Cut Line= 3
        2453175.       13826925.        2452775.       13826625.
      2452475.03     13826525.01
#Sta/Elev= 30
    4500  506.32  4503.1  506.32  4507.3  504.72  4528.1  502.23    4550  497.68
  4578.1  492.99  4628.1  487.61  4707.3  481.57  4728.1  479.27  4804.7  474.13
  4857.3  472.05  4907.3  469.11  4921.9  468.13  4957.3  463.36  4996.9  460.66
  5007.3  460.54  5007.8  460.04  5013.3  460.04  5013.8  460.54  5021.1  461.16
  5073.8  462.08  5084.3  464.54  5094.9  468.37    5116  469.16  5145.7  471.29
  5210.8  477.35  5231.9  480.02  5263.5  485.22  5305.7  488.16  5316.2  489.48
#Mann= 5 ,-1 , 0
    4500     .12       0  4804.7     .07       0  5007.3     .05       0
  5013.8     .07       0  5145.7     .12       0
Bank Sta=5007.3,5013.8
XS Rating Curve= 0 ,0
Exp/Cntr=0.3,0.1

Type RM Length L Ch R = 1 ,7305    ,474,474,474
BEGIN DESCRIPTION:
Bear Gulch 14.0
END DESCRIPTION:
XS GIS Cut Line= 3
      2453375.02     13826825.03        2453075.       13826425.
      2452724.96     13826174.97
#Sta/Elev= 30
  4505.6   514.5  4508.8   514.5  4527.5  510.14  4562.9  503.54  4569.2  501.21
  4577.5  500.41  4583.8  498.74  4605.6   498.1  4677.5  488.43  4759.9  481.07
  4862.9  472.38  4892.1  467.84  4898.3  468.61  4962.9  464.29  4969.2   462.5
  4983.8  461.27  5002.5  458.19  5009.7  458.06  5010.2  457.56  5016.4  458.06
  5063.4  463.65  5069.5  463.13    5099  464.08  5105.2  462.24  5128.5  464.19
  5214.5  466.78  5300.6   471.2  5321.5  472.55  5398.9  482.59  5435.8  484.14
#Mann= 4 ,-1 , 0
  4505.6     .12       0  4759.9     .07       0  5009.7     .05       0
  5016.4     .07       0
Bank Sta=5009.7,5016.4
XS Rating Curve= 0 ,0
Exp/Cntr=0.3,0.1

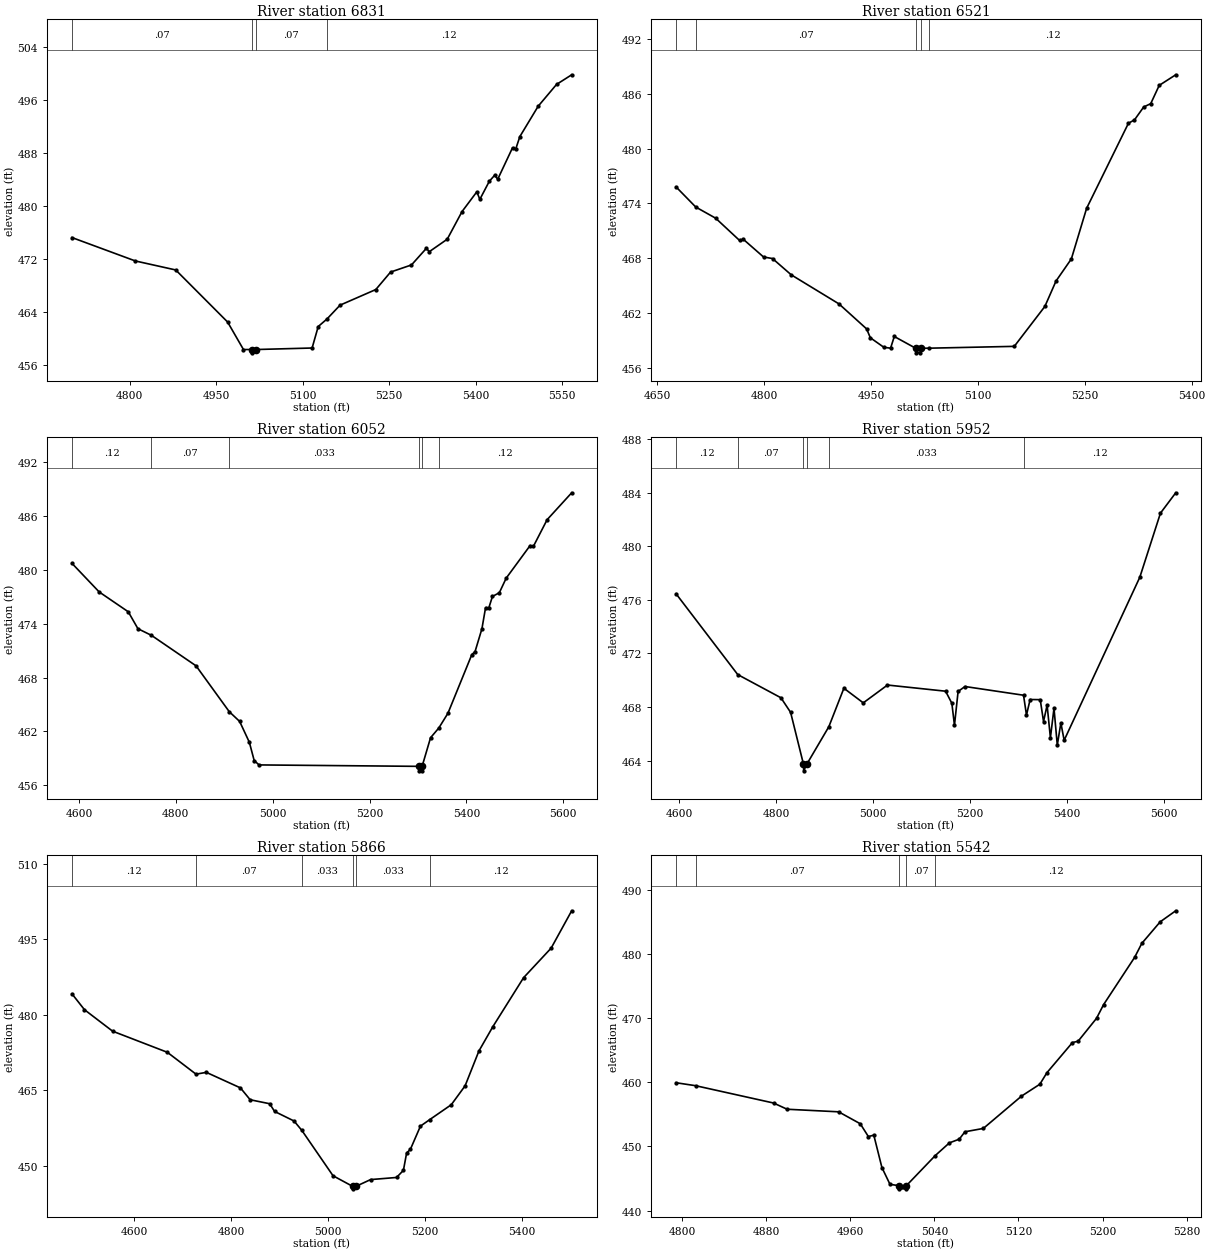
Type RM Length L Ch R = 1 ,6831    ,310,310,310
BEGIN DESCRIPTION:
Bear Gulch 13.0
END DESCRIPTION:
XS GIS Cut Line= 3
        2453425.     13826425.01        2453425.       13826125.
      2453237.06     13825590.17
#Sta/Elev= 30
  4699.9  475.25  4809.9  471.71  4879.9  470.35  4969.9  462.48  4997.4  458.32
  5011.9  458.32  5012.4  457.82  5018.8  458.32  5116.5  458.55  5127.1   461.8
  5142.1  462.92    5165  465.03    5227  467.39  5252.6  470.03  5288.9  471.11
  5314.6  473.61  5319.9  473.12  5350.9     475  5376.6  479.18  5402.2  482.16
  5407.5  481.03  5423.9  483.76  5433.2  484.67  5438.5  484.07  5464.2  488.83
  5469.5  488.57  5476.9  490.52  5508.7  495.11  5540.5   498.4  5566.8  499.86
#Mann= 4 ,-1 , 0
  4699.9     .07       0  5011.9     .05       0  5018.8     .07       0
  5142.1     .12       0
Bank Sta=5011.9,5018.8
XS Rating Curve= 0 ,0
Exp/Cntr=0.3,0.1

Type RM Length L Ch R = 1 ,6521    ,469,469,469
BEGIN DESCRIPTION:
Bear Gulch 12.0
END DESCRIPTION:
XS GIS Cut Line= 3
      2453775.01     13826425.04      2453646.79     13825982.57
      2453525.02     13825775.03
#Sta/Elev= 30
  4676.3  475.81    4704   473.6  4731.9  472.38  4765.5  469.94  4770.7  470.07
  4799.1  468.13  4811.7  467.96  4837.9  466.18    4905  462.99  4943.8  460.25
    4949  459.28  4967.9  458.24  4977.4  458.14  4982.6  459.42  5012.7  458.13
  5013.2  457.63  5019.2  457.63  5019.7  458.13  5031.5  458.14    5151  458.34
  5193.9  462.71  5209.6   465.5  5231.1  467.92  5252.5  473.46  5311.2  482.78
  5319.7  483.15  5332.6  484.56  5342.5  484.93  5354.4  486.93  5377.6  488.09
#Mann= 5 ,-1 , 0
  4676.3     .12       0    4704     .07       0  5012.7     .05       0
  5019.7     .07       0  5031.5     .12       0
Bank Sta=5012.7,5019.7
XS Rating Curve= 0 ,0
Exp/Cntr=0.3,0.1

Type RM Length L Ch R = 1 ,6052    ,100,100,100
BEGIN DESCRIPTION:
X18160
END DESCRIPTION:
XS GIS Cut Line= 3
      2453980.13     13826531.16      2453969.71     13825961.74
        2453626.     13825652.74
#Sta/Elev= 30
  4585.6  480.75  4641.8  477.56  4701.8  475.35  4721.8  473.46  4749.7  472.72
  4841.8  469.32  4910.3  464.21  4931.8  463.12  4951.8   460.8  4961.8  458.76
  4971.8  458.27  5301.5  458.11    5302  457.61    5308  457.61  5308.5  458.11
  5325.9   461.3    5343  462.39  5361.8  464.03  5411.1  470.57  5417.8  470.91
    5432  473.46  5439.5  475.81  5446.2  475.78  5453.7  477.06  5467.9  477.47
  5482.1   479.1  5531.4  482.73  5538.2  482.64  5566.6  485.62  5617.3  488.62
#Mann= 6 ,-1 , 0
  4585.6     .12       0  4749.7     .07       0  4910.3    .033       0
  5301.5    .033       0  5308.5    .033       0    5343     .12       0
Bank Sta=5301.5,5308.5
XS Rating Curve= 0 ,0
Exp/Cntr=0.3,0.1

Type RM Length L Ch R = 1 ,5952    ,86,86,86
BEGIN DESCRIPTION:
Bear Gulch 11.5
END DESCRIPTION:
XS GIS Cut Line= 3
      2454066.04     13826481.53      2454055.63      13825912.1
      2453711.85     13825603.04
#Sta/Elev= 30
  4593.1  476.45  4720.5  470.42  4809.7  468.69  4829.7   467.6  4856.2  463.74
  4856.7  463.24  4863.2  463.74  4908.6  466.53  4939.7   469.4  4979.7  468.31
  5029.7  469.64  5149.7  469.18  5162.6  468.28    5168  466.64  5175.5  469.16
  5189.7  469.53  5310.6  468.88  5316.7   467.4  5324.2  468.56  5345.1  468.55
  5351.9  466.92  5359.3  468.14  5366.1   465.7  5373.5  467.91  5380.3  465.16
  5387.7  466.81  5394.5  465.52  5550.7  477.68  5593.3  482.46  5624.9  483.98
#Mann= 6 ,-1 , 0
  4593.1     .12       0  4720.5     .07       0  4856.2    .033       0
  4863.2     .07       0  4908.6    .033       0  5310.6     .12       0
Bank Sta=4856.2,4863.2
XS Rating Curve= 0 ,0
Exp/Cntr=0.3,0.1

Type RM Length L Ch R = 1 ,5866    ,324,324,324
BEGIN DESCRIPTION:
Bear Gulch 11.0
END DESCRIPTION:
XS GIS Cut Line= 3
      2454091.24     13826600.65      2454153.74     13825986.04
      2454425.01     13825674.99
#Sta/Elev= 30
  4471.9  484.15  4497.7  480.99  4555.7  476.72  4668.6  472.52  4727.7  468.17
    4749  468.53  4819.3  465.44  4839.4  463.08  4879.6  462.29  4889.7  460.76
  4929.9  458.85    4946  456.98  5010.3  447.96  5050.6  445.86  5051.1  445.36
  5057.6  445.86  5087.7   447.2  5141.2  447.62  5155.4  449.04    5162  452.49
  5169.7   453.2  5190.5  457.83  5209.5  459.12  5254.1  462.09  5282.6  465.85
  5311.1  472.78  5339.6  477.58  5403.2  487.36  5460.1  493.25  5502.4  500.67
#Mann= 6 ,-1 , 0
  4471.9     .12       0  4727.7     .07       0    4946    .033       0
  5050.6    .033       0  5057.6    .033       0  5209.5     .12       0
Bank Sta=5050.6,5057.6
XS Rating Curve= 0 ,0
Exp/Cntr=0.3,0.1

Type RM Length L Ch R = 1 ,5542    ,481,481,481
BEGIN DESCRIPTION:
Bear Gulch 10.0
END DESCRIPTION:
XS GIS Cut Line= 3
      2454374.99     13826325.05        2454425.       13826125.
      2454525.01     13825874.96
#Sta/Elev= 30
  4794.2  459.92  4812.8  459.46    4887  456.76  4899.9  455.79  4948.9  455.39
  4969.5  453.53  4977.2  451.54  4982.4  451.75  4990.1  446.71  4997.8  444.09
  5006.2  443.89  5006.7  443.39  5012.9  443.39  5013.4  443.89  5040.9  448.58
  5054.3  450.55  5063.7  451.13  5069.1  452.28  5086.6   452.8  5122.9  457.83
  5140.4  459.69  5147.1  461.48  5171.4  466.18  5176.8  466.39  5194.3  469.95
    5201  472.08  5230.6  479.46  5237.4  481.63  5254.9  484.99  5269.7  486.71
#Mann= 5 ,-1 , 0
  4794.2     .12       0  4812.8     .07       0  5006.2     .05       0
  5013.4     .07       0  5040.9     .12       0
Bank Sta=5006.2,5013.4
XS Rating Curve= 0 ,0
Exp/Cntr=0.3,0.1

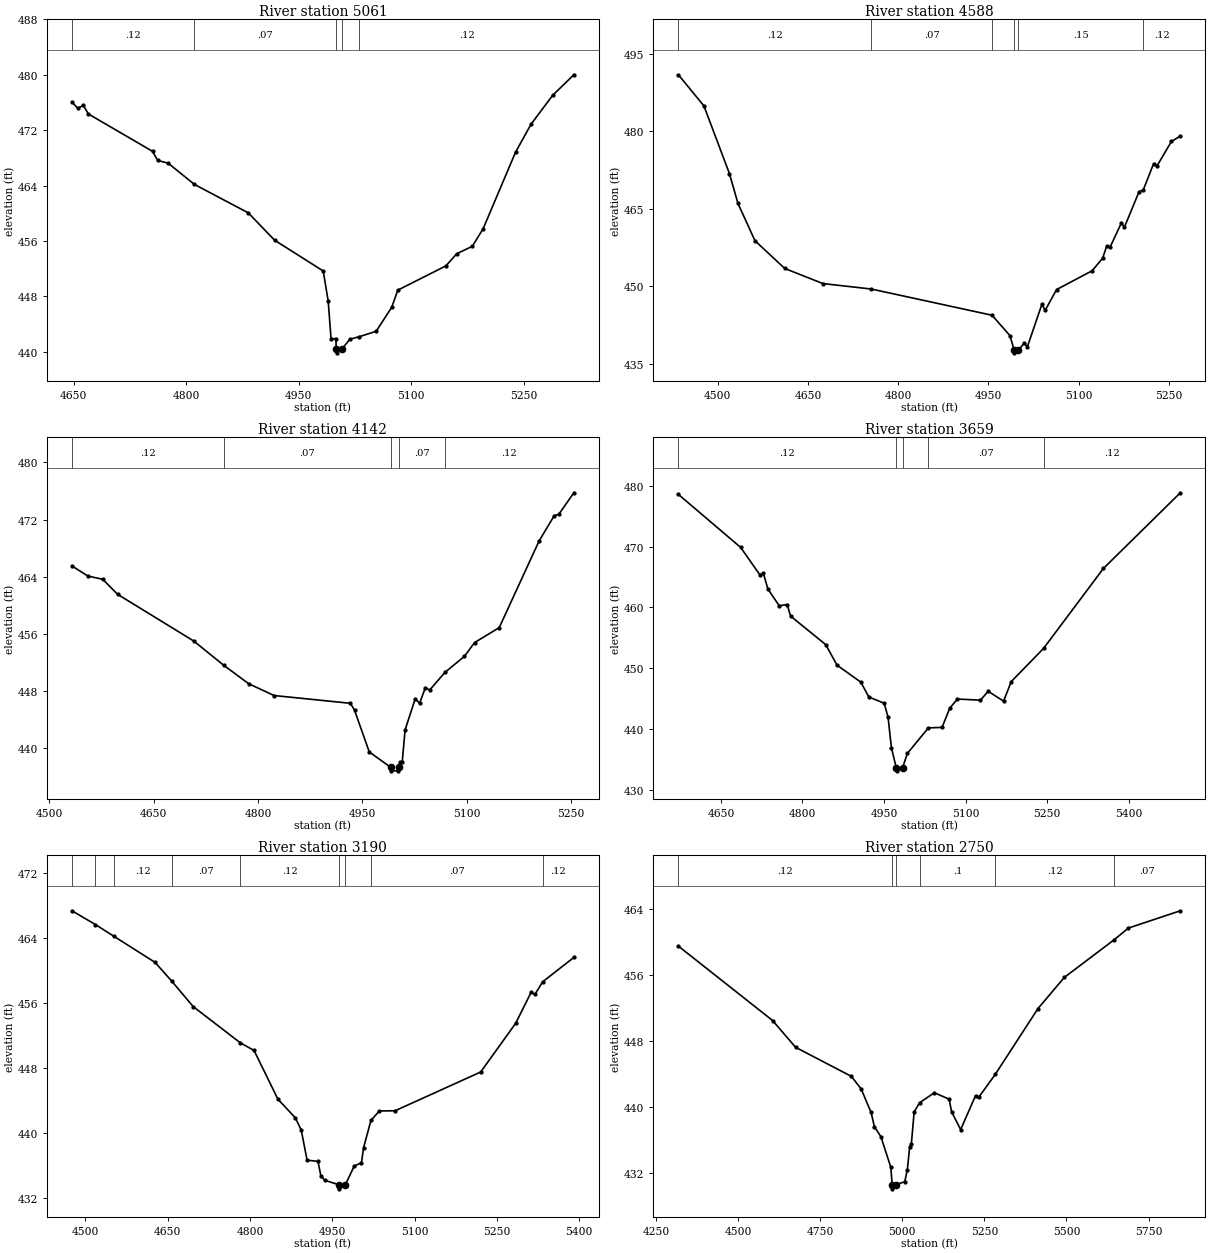
Type RM Length L Ch R = 1 ,5061    ,473,473,473
BEGIN DESCRIPTION:
Bear Gulch 9.0
END DESCRIPTION:
XS GIS Cut Line= 3
      2454448.89     13826590.19        2454675.       13826325.
      2454925.03     13826124.97
#Sta/Elev= 30
  4647.8  476.07  4655.4  475.16  4663.1  475.57  4669.6  474.34  4755.3  468.93
  4761.9  467.63  4776.1  467.22    4811  464.16  4882.7  460.06  4917.8  456.11
  4982.6  451.66  4989.2  447.32    4993   441.9  4999.5   441.9  4999.9  440.35
  5000.4  439.85  5007.1  440.35  5017.9   441.8  5030.9  442.19  5053.1  442.96
  5073.9  446.43  5081.9   448.9    5146   452.4  5160.4  454.15  5181.2  455.23
  5195.6  457.76  5238.8  468.81  5259.6  472.88  5288.4  477.04  5316.5  479.99
#Mann= 5 ,-1 , 0
  4647.8     .12       0    4811     .07       0  4999.9     .05       0
  5007.1     .07       0  5030.9     .12       0
Bank Sta=4999.9,5007.1
XS Rating Curve= 0 ,0
Exp/Cntr=0.3,0.1

Type RM Length L Ch R = 1 ,4588    ,446,446,446
BEGIN DESCRIPTION:
Bear Gulch 8.0
END DESCRIPTION:
XS GIS Cut Line= 3
        2454675.       13826825.        2455075.       13826425.
      2454975.02     13826175.04
#Sta/Elev= 30
  4434.4  490.98  4476.8  484.96  4519.3  471.83  4533.4  466.07  4561.7  458.84
  4611.2  453.46  4674.8  450.53  4755.4  449.47  4956.2  444.39  4985.9  440.44
  4992.9  437.61  4993.4  437.11  5000.1  437.61  5009.5  438.99  5014.9  438.28
  5039.1  446.54  5044.5  445.34  5063.4  449.36  5122.6  453.01  5140.1  455.45
  5146.8  457.78  5152.2  457.53  5171.1  462.23  5176.4  461.48  5200.7  468.33
  5207.4  468.59  5224.9  473.77  5230.3  473.28  5254.5  478.06  5269.3   479.1
#Mann= 6 ,-1 , 0
  4434.4     .12       0  4755.4     .07       0  4956.2     .15       0
  4992.9     .05       0  5000.1     .15       0  5207.4     .12       0
Bank Sta=4992.9,5000.1
XS Rating Curve= 0 ,0
Exp/Cntr=0.3,0.1

Type RM Length L Ch R = 1 ,4142    ,483,483,483
BEGIN DESCRIPTION:
Bear Gulch 7.0
END DESCRIPTION:
XS GIS Cut Line= 3
      2455625.02     13826625.03        2455375.       13826225.
      2455225.02     13826025.03
#Sta/Elev= 30
  4532.5  465.49  4555.5  464.07  4576.8  463.62    4598  461.52  4707.7  454.96
  4750.5  451.58  4786.7  448.97  4823.2  447.32  4932.9  446.23  4938.8  445.27
    4960  439.41  4990.8  437.26  4991.3  436.76  5001.9  436.76  5002.4  437.26
  5004.2  437.96  5007.4  437.96  5011.5  442.49  5026.1  446.87  5032.4  446.23
  5040.7  448.44  5046.9  448.09  5068.7  450.55  5096.9  452.82  5111.5  454.75
  5146.9  456.84  5204.2  468.99  5226.1  472.56  5232.4  472.71  5254.2  475.75
#Mann= 5 ,-1 , 0
  4532.5     .12       0  4750.5     .07       0  4990.8     .05       0
  5002.4     .07       0  5068.7     .12       0
Bank Sta=4990.8,5002.4
XS Rating Curve= 0 ,0
Exp/Cntr=0.3,0.1

Type RM Length L Ch R = 1 ,3659    ,469,469,469
BEGIN DESCRIPTION:
Bear Gulch 6.0
END DESCRIPTION:
XS GIS Cut Line= 3
      2456080.83      13826468.7        2455825.       13826125.
      2455475.03     13825775.03
#Sta/Elev= 30
  4571.8  478.57  4686.4  469.86  4721.8  465.34  4728.1   465.6  4736.5  463.02
  4757.3  460.28  4771.9  460.49  4778.1  458.59  4842.8   453.9  4863.6  450.53
  4907.5  447.73  4922.1  445.29  4950.4  444.28  4957.5  441.96  4963.7  436.95
  4972.6  433.67  4973.1  433.17  4984.2  433.67    4993  436.03  5031.7  440.23
  5056.8   440.3    5071  443.46  5085.1  444.96  5127.5  444.78  5141.7  446.23
    5170  444.62  5184.1  447.82  5243.7  453.29  5353.8  466.42  5495.2  478.84
#Mann= 5 ,-1 , 0
  4571.8     .12       0  4972.6     .05       0  4984.2     .12       0
  5031.7     .07       0  5243.7     .12       0
Bank Sta=4972.6,4984.2
XS Rating Curve= 0 ,0
Exp/Cntr=0.3,0.1

Type RM Length L Ch R = 1 ,3190    ,440,440,440
BEGIN DESCRIPTION:
Bear Gulch 5.0
END DESCRIPTION:
XS GIS Cut Line= 3
      2456306.51     13826267.27        2456125.       13825775.
      2455874.99     13825474.98
#Sta/Elev= 30
  4475.3  467.32    4518  465.63  4551.2  464.21  4626.9  460.97  4657.1  458.68
  4696.3  455.54  4782.3  451.08  4807.4  450.14  4850.8  444.15  4882.7  441.85
  4893.4  440.34  4904.1  436.64  4923.9   436.5  4929.2  434.73    4936  434.18
  4962.1  433.62  4962.6  433.12  4973.8  433.62  4990.1  435.93  5003.2  436.33
  5007.1  438.19  5020.5  441.53  5035.8   442.7  5064.4  442.72  5220.6  447.49
  5284.4  453.48  5312.4  457.27  5319.5  457.04  5333.7  458.59  5390.5  461.58
#Mann= 9 ,-1 , 0
  4475.3     .12       0    4518     .07       0  4551.2     .12       0
  4657.1     .07       0  4782.3     .12       0  4962.1     .05       0
  4973.8     .12       0  5020.5     .07       0  5333.7     .12       0
Bank Sta=4962.1,4973.8
XS Rating Curve= 0 ,0
Exp/Cntr=0.3,0.1

Type RM Length L Ch R = 1 ,2750    ,431,431,431
BEGIN DESCRIPTION:
Bear Gulch 4.0
END DESCRIPTION:
XS GIS Cut Line= 3
      2456466.24     13826211.78        2456475.       13825525.
      2456691.92     13824711.77
#Sta/Elev= 30
  4318.2  459.51    4605  450.51    4675  447.27    4845  443.75    4875  442.21
    4905  439.38    4915  437.66    4935  436.44    4965  432.75  4969.1  430.64
  4969.6  430.14  4980.9  430.64  5007.6  431.01  5015.4  432.48  5022.5  435.23
  5027.7  435.61  5036.1  439.46  5052.8  440.56  5097.5  441.77  5142.8  440.99
  5149.9  439.49  5177.7  437.31    5223  441.41  5232.7  441.22  5282.9  443.98
  5413.1  451.95  5493.3  455.72  5644.7  460.27  5688.7   461.7  5846.7  463.79
#Mann= 6 ,-1 , 0
  4318.2     .12       0  4969.1     .05       0  4980.9     .12       0
  5052.8      .1       0  5282.9     .12       0  5644.7     .07       0
Bank Sta=4969.1,4980.9
XS Rating Curve= 0 ,0
Exp/Cntr=0.3,0.1