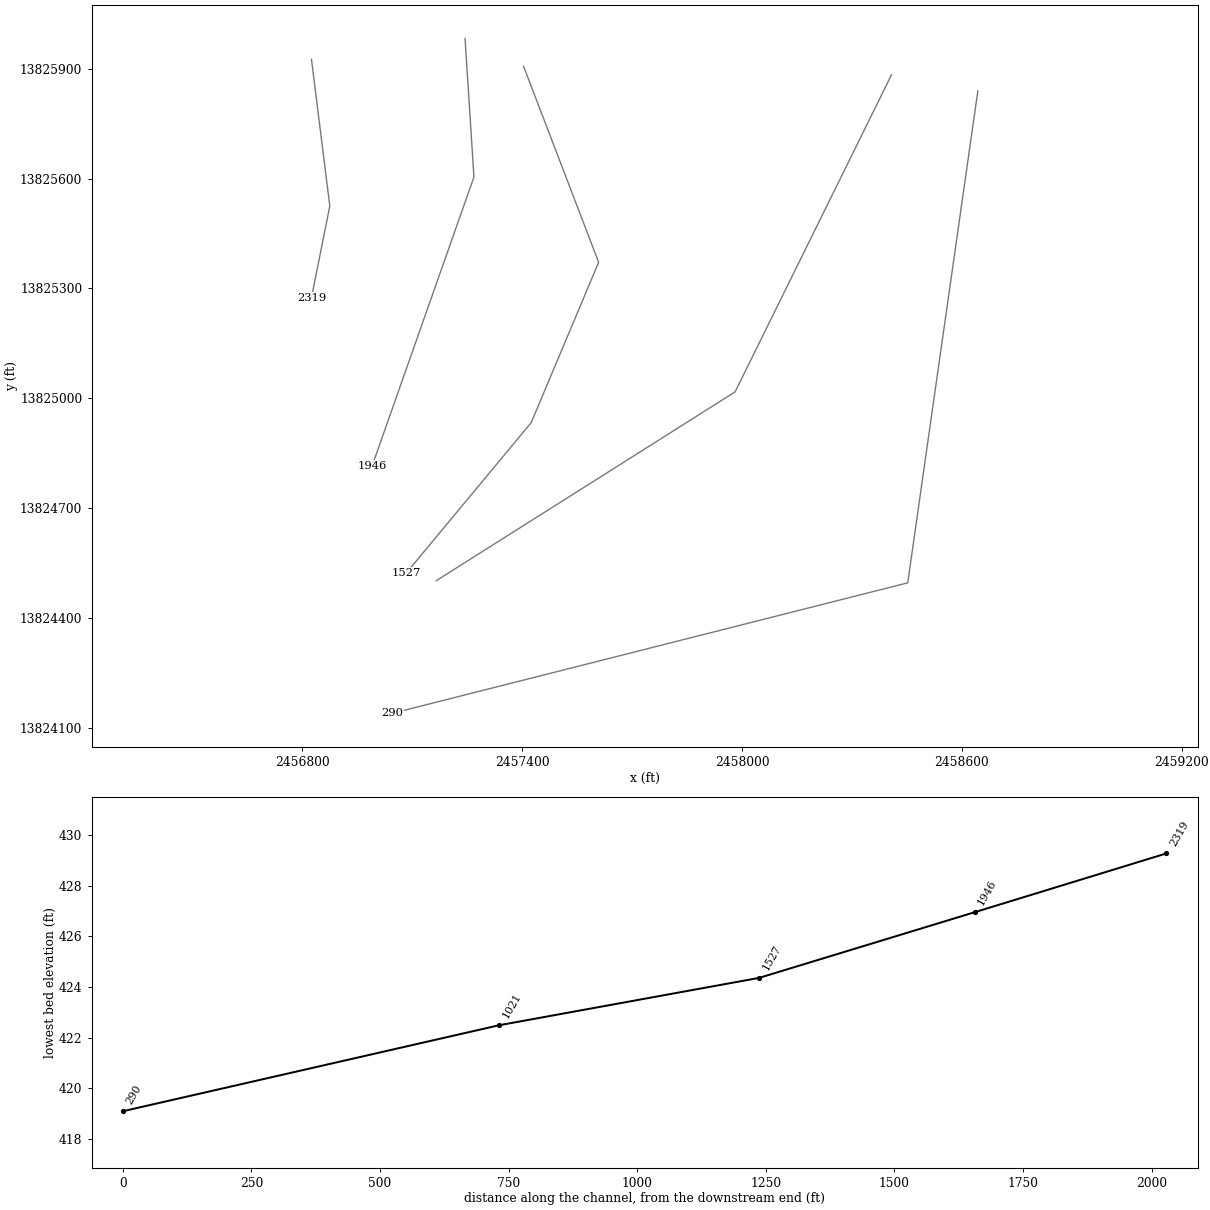
HEC-RAS study Bear Gulch.prj: Bear Gulch Base Level Engineering

--- Bear Gulch.g01 (geometry) --- (continued)

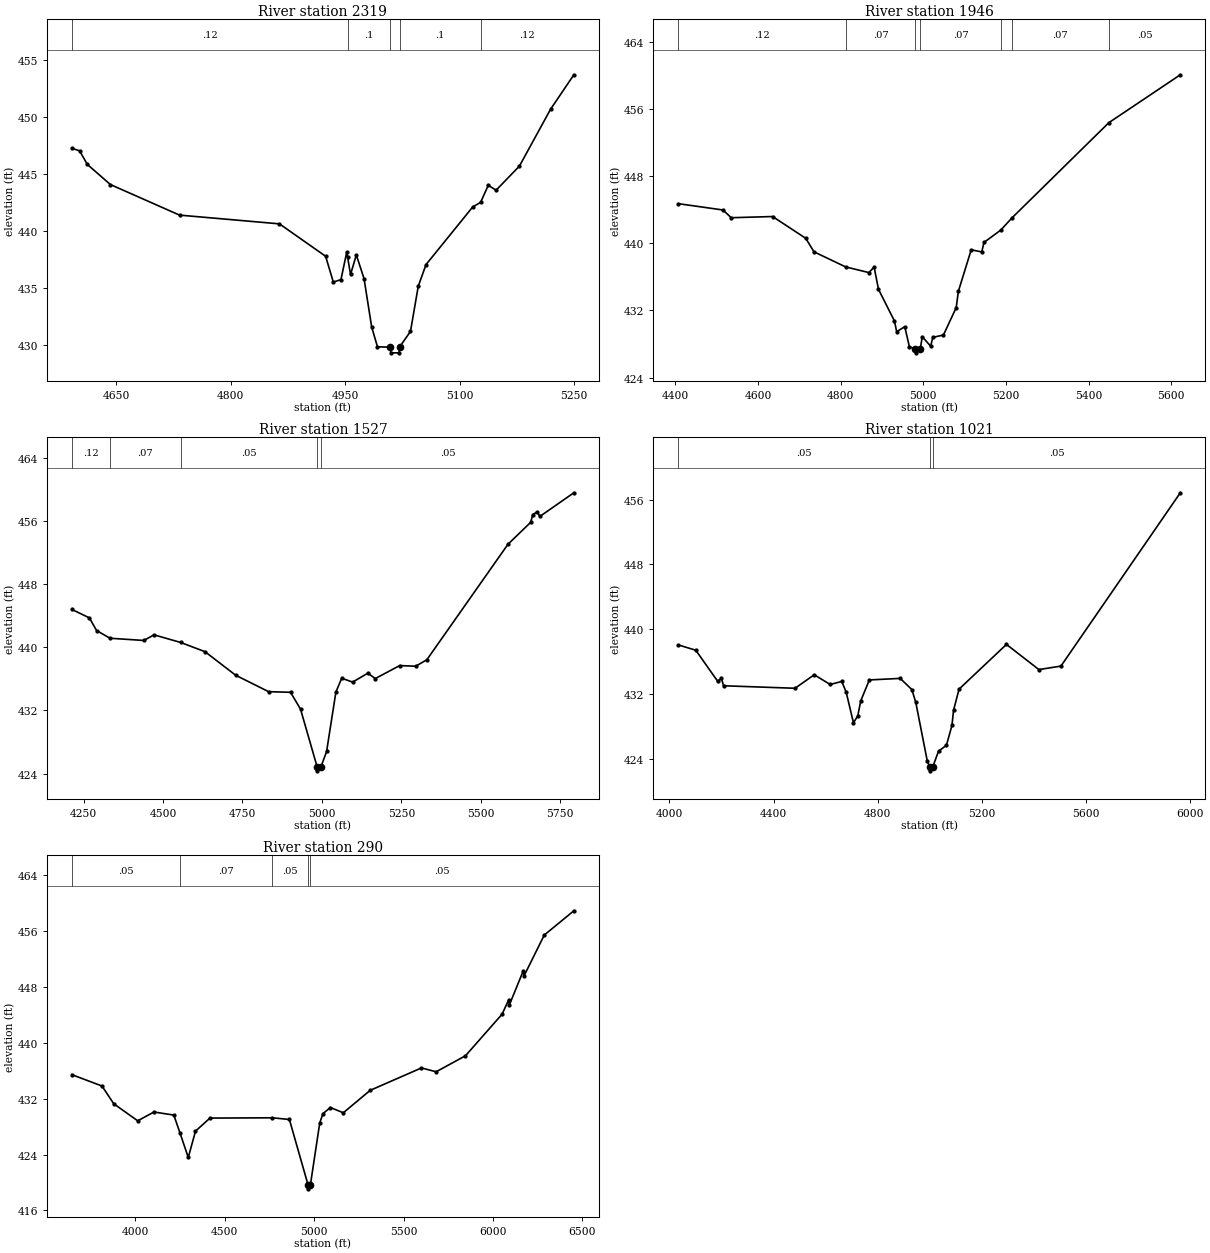
Type RM Length L Ch R = 1 ,2319    ,373,373,373
BEGIN DESCRIPTION:
Bear Gulch 3.0
END DESCRIPTION:
XS GIS Cut Line= 3
        2456825.       13825925.        2456875.       13825525.
      2456824.99     13825274.97
#Sta/Elev= 30
  4591.7  447.27  4601.8  447.04  4611.9  445.85  4642.1  444.08  4732.8  441.39
  4863.8  440.62  4924.3  437.77  4934.4   435.5  4944.4  435.71    4952  438.13
  4953.1   437.7    4957  436.17  4964.6  437.88  4974.7   435.8  4984.7  431.54
  4992.3   429.8  5009.3  429.77  5009.8  429.27  5020.7  429.27  5021.2  429.77
  5035.6  431.16  5045.8  435.14    5056  437.04  5117.2  442.11  5127.5  442.51
  5137.6  444.02  5147.8  443.58  5178.4   445.7  5219.2   450.7  5249.8  453.74
#Mann= 5 ,-1 , 0
  4591.7     .12       0  4953.1      .1       0  5009.3     .05       0
  5021.2      .1       0  5127.5     .12       0
Bank Sta=5009.3,5021.2
XS Rating Curve= 0 ,0
Exp/Cntr=0.3,0.1

Type RM Length L Ch R = 1 ,1946    ,419,419,419
BEGIN DESCRIPTION:
X18159
END DESCRIPTION:
XS GIS Cut Line= 3
      2457244.02     13825982.54      2457268.32      13825604.1
      2456990.55     13824815.93
#Sta/Elev= 30
  4407.2   444.7    4515  443.95    4535  443.03  4635.2  443.17  4715.4  440.58
  4735.4  438.97  4811.8  437.18  4868.3   436.5  4880.9  437.16  4891.5  434.51
  4930.2  430.73  4935.5  429.47  4955.1  430.06  4966.4  427.65  4980.8  427.45
  4981.3  426.95  4992.7  427.45  4997.5  428.87  5017.7  427.74    5023  428.79
  5048.7  429.07  5079.6  432.33  5084.9  434.28  5115.9  439.21  5141.5  438.96
  5146.8  440.09  5187.3  441.55  5214.2  442.99  5449.1  454.34  5622.1  460.04
#Mann= 7 ,-1 , 0
  4407.2     .12       0  4811.8     .07       0  4980.8     .05       0
  4992.7     .07       0  5187.3     .05       0  5214.2     .07       0
  5449.1     .05       0
Bank Sta=4980.8,4992.7
XS Rating Curve= 0 ,0
Exp/Cntr=0.3,0.1

Type RM Length L Ch R = 1 ,1527    ,506,506,506
BEGIN DESCRIPTION:
X18158
END DESCRIPTION:
XS GIS Cut Line= 4
      2457403.74     13825906.19       2457608.6     13825371.46
      2457424.57     13824933.96      2457084.27     13824524.21
#Sta/Elev= 30
  4213.2  444.78    4268  443.72  4290.7  442.12  4332.9  441.14  4439.4  440.86
  4471.5  441.57  4555.2  440.61  4632.1  439.44  4728.5  436.46  4832.3  434.38
  4901.3   434.3  4932.7  432.17    4985  424.86  4985.5  424.36    4997  424.86
  5014.8  426.81    5044  434.32  5062.3  436.08  5096.9  435.59  5144.4  436.72
  5168.1  436.04  5244.8  437.68  5295.3   437.6  5330.4  438.42  5585.6  453.03
  5657.2  455.81  5663.7  456.79  5678.1  457.15  5685.9  456.55  5793.1  459.55
#Mann= 5 ,-1 , 0
  4213.2     .12       0  4332.9     .07       0  4555.2     .05       0
    4985     .05       0    4997     .05       0
Bank Sta=4985,4997
XS Rating Curve= 0 ,0
Exp/Cntr=0.3,0.1

Type RM Length L Ch R = 1 ,1021    ,731,731,731
BEGIN DESCRIPTION:
Bear Gulch 2.0
END DESCRIPTION:
XS GIS Cut Line= 3
      2458407.84     13825883.36      2457980.95     13825017.83
      2457165.45     13824502.62
#Sta/Elev= 30
  4034.4  438.04  4101.2  437.39  4185.4  433.55  4199.8  433.91  4207.9     433
  4482.9  432.69  4556.6  434.36  4617.6  433.16  4662.5  433.53  4679.3  432.22
  4707.4  428.43  4723.9  429.27  4735.5  431.14  4768.5  433.72  4887.1  433.91
    4932  432.53  4946.9  430.96  4991.5  423.66  5000.5  422.99    5001  422.49
  5012.5  422.99  5034.5  424.92    5065  425.65  5086.2  428.12  5092.1  429.95
  5113.3  432.58  5295.6  438.11  5420.3     435  5505.1  435.43  5964.1  456.84
#Mann= 3 ,-1 , 0
  4034.4     .05       0  5000.5     .05       0  5012.5     .05       0
Bank Sta=5000.5,5012.5
XS Rating Curve= 0 ,0
Exp/Cntr=0.3,0.1

Type RM Length L Ch R = 1 ,290     ,0,0,0
BEGIN DESCRIPTION:
Bear Gulch 1.0
END DESCRIPTION:
XS GIS Cut Line= 3
      2458643.33     13825839.15      2458451.98     13824496.75
      2457044.83     13824140.55
#Sta/Elev= 30
  3644.7  435.44  3812.8  433.82  3878.5  431.28  4012.5  428.84  4103.4   430.1
  4214.6  429.66  4248.7  427.12  4295.4  423.59  4335.8  427.36  4416.6  429.23
  4765.9  429.27    4861  429.03  4966.1   419.6  4966.6   419.1  4978.1   419.6
  5030.9  428.55  5049.1  429.88  5090.4  430.74  5162.6  429.99  5312.8   433.2
  5599.8  436.41  5681.9  435.86  5845.9  438.15  6050.9  444.11  6086.8  446.11
  6091.9  445.46  6168.8  450.28  6173.9  449.61  6286.6  455.43  6452.2  458.91
#Mann= 5 ,-1 , 0
  3644.7     .05       0  4248.7     .07       0  4765.9     .05       0
  4966.1     .05       0  4978.1     .05       0
Bank Sta=4966.1,4978.1
XS Rating Curve= 0 ,0
Exp/Cntr=0.3,0.1

Chan Stop Cuts=-1
Use User Specified Reach Order=0
Composite Channel Slope=5