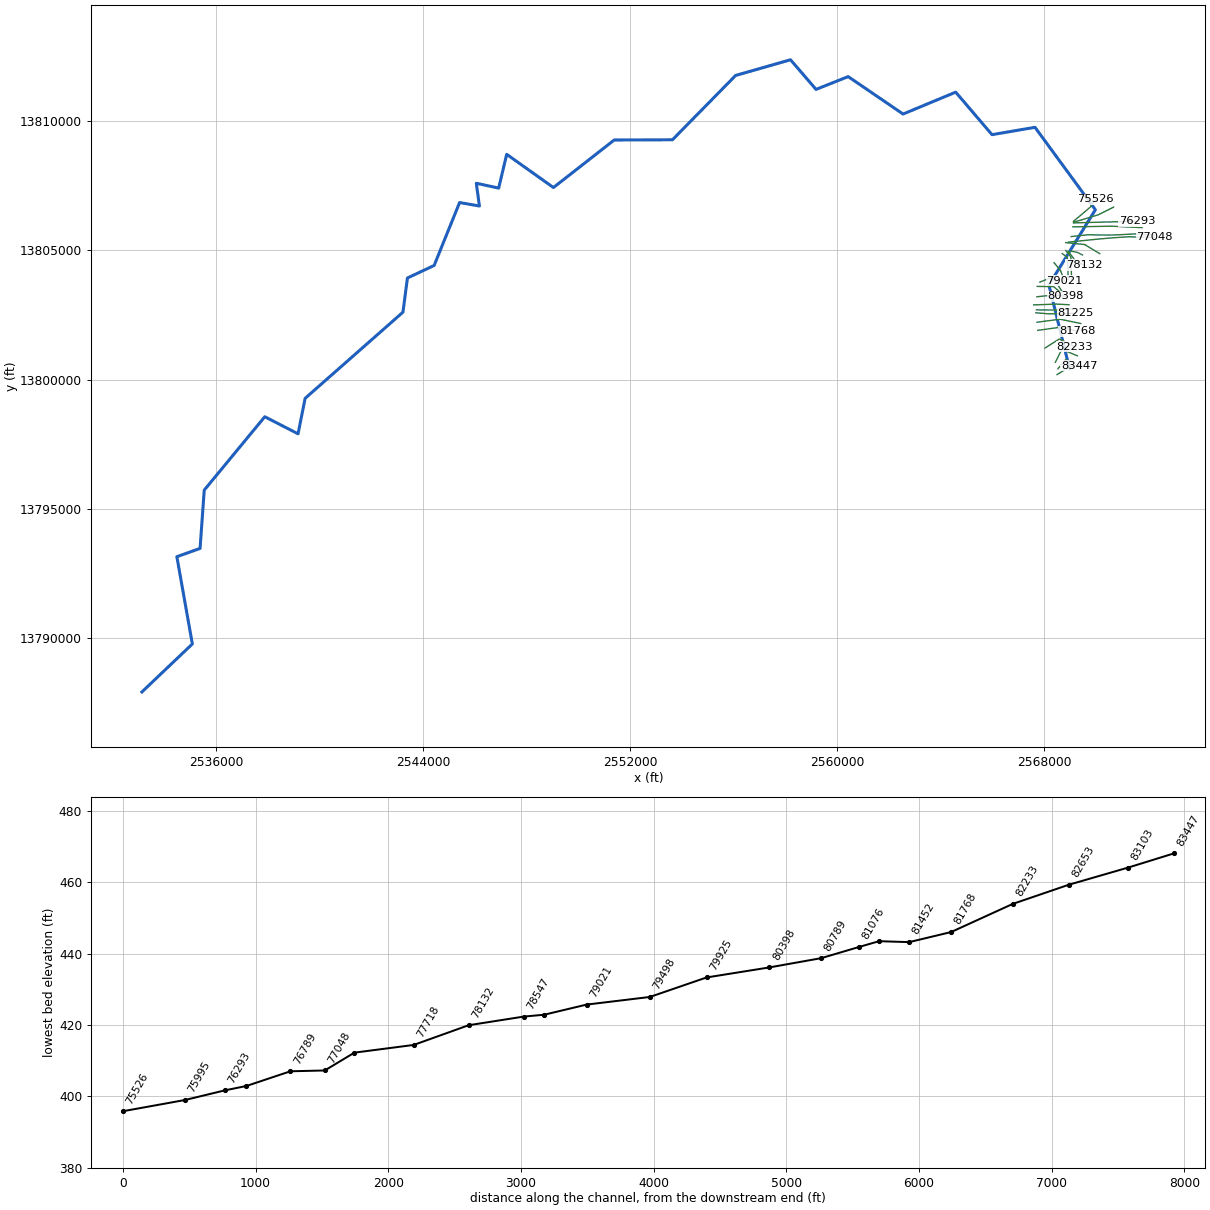
--- Big Fivemile Creek.prj (project) ---

Proj Title=Big Fivemile Creek Base Level Engineering
Current Plan=p01
Default Exp/Contr=0.3,0.1
English Units
Geom File=g01
Flow File=f01
Plan File=p01
Y Axis Title=Elevation
X Axis Title(PF)=Main Channel Distance
X Axis Title(XS)=Station
BEGIN DESCRIPTION:
Big Fivemile Creek
END DESCRIPTION:
DSS Export Rating Curves= 0
DSS Export Rating Curve Sorted= 0
DSS Export Volume Flow Curves= 0
DXF OffsetX= 0
DXF OffsetY= 0
DXF ScaleX= 1
DXF ScaleY= 10

--- Big Fivemile Creek.p01 (plan) ---

Plan Title=Multiple Run
Program Version=4.10
Short Identifier=Multiple
Geom File=g01
Flow File=f01
Subcritical Flow
K Sum by GR= 0
Std Step Tol= 0.01
Critical Tol= 0.01
Num of Std Step Trials= 20
Max Error Tol= 0.3
Flow Tol Ratio= 0.001
Split Flow NTrial= 30
Split Flow Tol= 0.02
Split Flow Ratio= 0.02
Log Output Level= 0
Friction Slope Method= 1
Unsteady Friction Slope Method= 2
Unsteady Bridges Friction Slope Method= 1
Parabolic Critical Depth
Global Vel Dist= 1 , 1 , 1
Global Log Level= 0
CheckData=True
Encroach Param=-1 ,0,0, 0
BEGIN DESCRIPTION:
Multiple Run
END DESCRIPTION:
Computation Interval=1HOUR
Output Interval=1HOUR
Run HTab= 0
Run UNet= 0
Run PostProcess= 0
Run WQNet= 0
UNET Theta= 1
UNET Theta Warmup= 1
UNET ZTol= 0.02
UNET ZSATol= 0.05
UNET MxIter= 20
UNET MaxInSteps= 0
UNET DtIC= 0
UNET DtMin= 0
UNET MaxCRTS= 20
UNET WFStab= 2
UNET SFStab= 1
UNET WFX= 1
UNET SFX= 1
UNET DSS MLevel= 4
UNET DZMax Abort= 100
UNET Convert EG Bridges= 0
UNET Use Existing IB Tables=-1
UNET Froude Reduction=False
UNET Froude Limit= 1
UNET Froude Power= 10
UNET Time Slicing=0,0, 5
UNET Junction Losses=0
Instantaneous Interval=1HOUR
Write IC File= 0
Write IC File at Sim End=0
Echo Input=False
Echo Parameters=False
Echo Output=False
Write Detailed= 0
WQ AD Non Conservative
WQ ULTIMATE=-1
WQ Max Comp Step=1HOUR
WQ Output Interval=15MIN
WQ Output Selected Increments= 0
WQ Output face flow=0
WQ Output face velocity=0
WQ Output face area=0
WQ Output face dispersion=0
WQ Output cell volume=0
WQ Output cell surface area=0
WQ Output cell continuity=0
WQ Output cumulative cell continuity=0
WQ Output face conc=0
WQ Output face dconc_dx=0
WQ Output face courant=0
WQ Output face peclet=0
WQ Output face adv mass=0
WQ Output face disp mass=0
WQ Output cell mass=0
WQ Output cell source sink temp=0
WQ Output cell source sink nsm=0
WQ Output MaxMinRange=-1
WQ Daily Max Min Mean=-1
WQ Daily Range=0
WQ Daily Time=0
WQ Create Restart=0
WQ Fixed Restart=0
WQ System Summary=0
WQ Use Fixed Temperature=0
Sorting and Armoring Iterations= 10
XS Update Threshold= 0.02
Hydraulics Update Threshold= 0.02
Energy Slope Method= 1
Volume Change Method= 0
XS Weighting Method= 0
Number of US Weighted Cross Sections= 1
Number of DS Weighted Cross Sections= 1
Upstream XS Weight=0.25
Main XS Weight=0.5
Downstream XS Weight=0.25
Number of DS XS's Weighted with US Boundary= 1
Upstream Boundary Weight= 1
Weight of XSs Associated with US Boundary= 0
Number of US XS's Weighted with DS Boundary= 1
Downstream Boundary Weight= 0.5
Weight of XSs Associated with DS Boundary= 0.5
Sediment Output Level= 4
Mass or Volume Output= 0
Output Increment Type= 1
Profile and TS Output Increment= 10
XS Output Flag= 0
XS Output Increment= 10
Disregard all LS=0
Disregard all Conn=0
Disregard all Breaches=0
Disregard all Pumps=0

--- Big Fivemile Creek.f01 (steady flow) ---

Flow Title=Multiple
Number of Profiles=7
Profile Names=10-year,25-year,50-year,1pct_min,100-year,1pct_plu,500-year
River Rch & RM= Big Fivemile Cre,Reach-1,83447
     156     224     279     169     338     674     487
River Rch & RM= Big Fivemile Cre,Reach-1,81768
     350     536     695     438     873    1742    1361
River Rch & RM= Big Fivemile Cre,Reach-1,77048
     834    1351    1821    1188    2371    4730    3977
River Rch & RM= Big Fivemile Cre,Reach-1,75114
     976    1596    2165    1421    2836    5659    4817
River Rch & RM= Big Fivemile Cre,Reach-1,71412
    1633    2725    3746    2486    4960    9896    8611
River Rch & RM= Big Fivemile Cre,Reach-1,64921
    1786    2987    4111    2731    5449   10872    9480
River Rch & RM= Big Fivemile Cre,Reach-1,62986
    1883    3136    4303    2847    5681   11335    9807
River Rch & RM= Big Fivemile Cre,Reach-1,54738
    2520    4249    5879    3920    7821   15605   13709
River Rch & RM= Big Fivemile Cre,Reach-1,51644
    2553    4290    5920    3935    7852   15667   13684
River Rch & RM= Big Fivemile Cre,Reach-1,44902
    2567    4308    5941    3946    7873   15708   13693
River Rch & RM= Big Fivemile Cre,Reach-1,43817
    3271    5528    7659    5107   10190   20331   17865
River Rch & RM= Big Fivemile Cre,Reach-1,38902
    4363    7417   10318    6902   13771   27476   24289
River Rch & RM= Big Fivemile Cre,Reach-1,30047
    4324    7327   10170    6786   13540   27016   23766
River Rch & RM= Big Fivemile Cre,Reach-1,21248
    6667   11411   15948   10706   21362   42622   37932
Boundary for River Rch & Prof#=Big Fivemile Cre,Reach-1,1
Up Type=0
Dn Type=3
Dn Slope=0.0005
Boundary for River Rch & Prof#=Big Fivemile Cre,Reach-1,2
Up Type=0
Dn Type=3
Dn Slope=0.0005
Boundary for River Rch & Prof#=Big Fivemile Cre,Reach-1,3
Up Type=0
Dn Type=3
Dn Slope=0.0005
Boundary for River Rch & Prof#=Big Fivemile Cre,Reach-1,4
Up Type=0
Dn Type=3
Dn Slope=0.0005
Boundary for River Rch & Prof#=Big Fivemile Cre,Reach-1,5
Up Type=0
Dn Type=3
Dn Slope=0.0005
Boundary for River Rch & Prof#=Big Fivemile Cre,Reach-1,6
Up Type=0
Dn Type=3
Dn Slope=0.0005
Boundary for River Rch & Prof#=Big Fivemile Cre,Reach-1,7
Up Type=0
Dn Type=3
Dn Slope=0.0005

--- Big Fivemile Creek.g01 (geometry) ---

Geom Title=Existing Conditions
Program Version=4.10

River Reach=Big Fivemile Cre,Reach-1
Reach XY= 30
        2568975.       13800425.      2568175.76     13803664.31
      2569971.49     13806573.75      2567638.33     13809761.67
      2565976.25     13809478.35      2564573.64     13811121.96
      2562540.54     13810275.54      2560419.15     13811722.94
      2559176.49     13811228.45      2558190.09     13812374.81
      2556068.62     13811767.68      2553627.29     13809280.07
       2551376.5     13809271.39      2549028.31     13807433.02
      2547221.38     13808717.52      2546911.56     13807411.36
      2546047.55     13807598.84       2546167.2     13806718.79
      2545401.03      13806852.5      2544417.19     13804418.79
      2543386.07     13803935.08      2543211.63     13802611.68
      2539432.48     13799281.06      2539158.75     13797907.87
      2537872.66     13798569.28      2535532.86     13795731.19
      2535371.46     13793476.46      2534474.74     13793155.06
      2535073.33     13789781.13        2533125.       13787925.

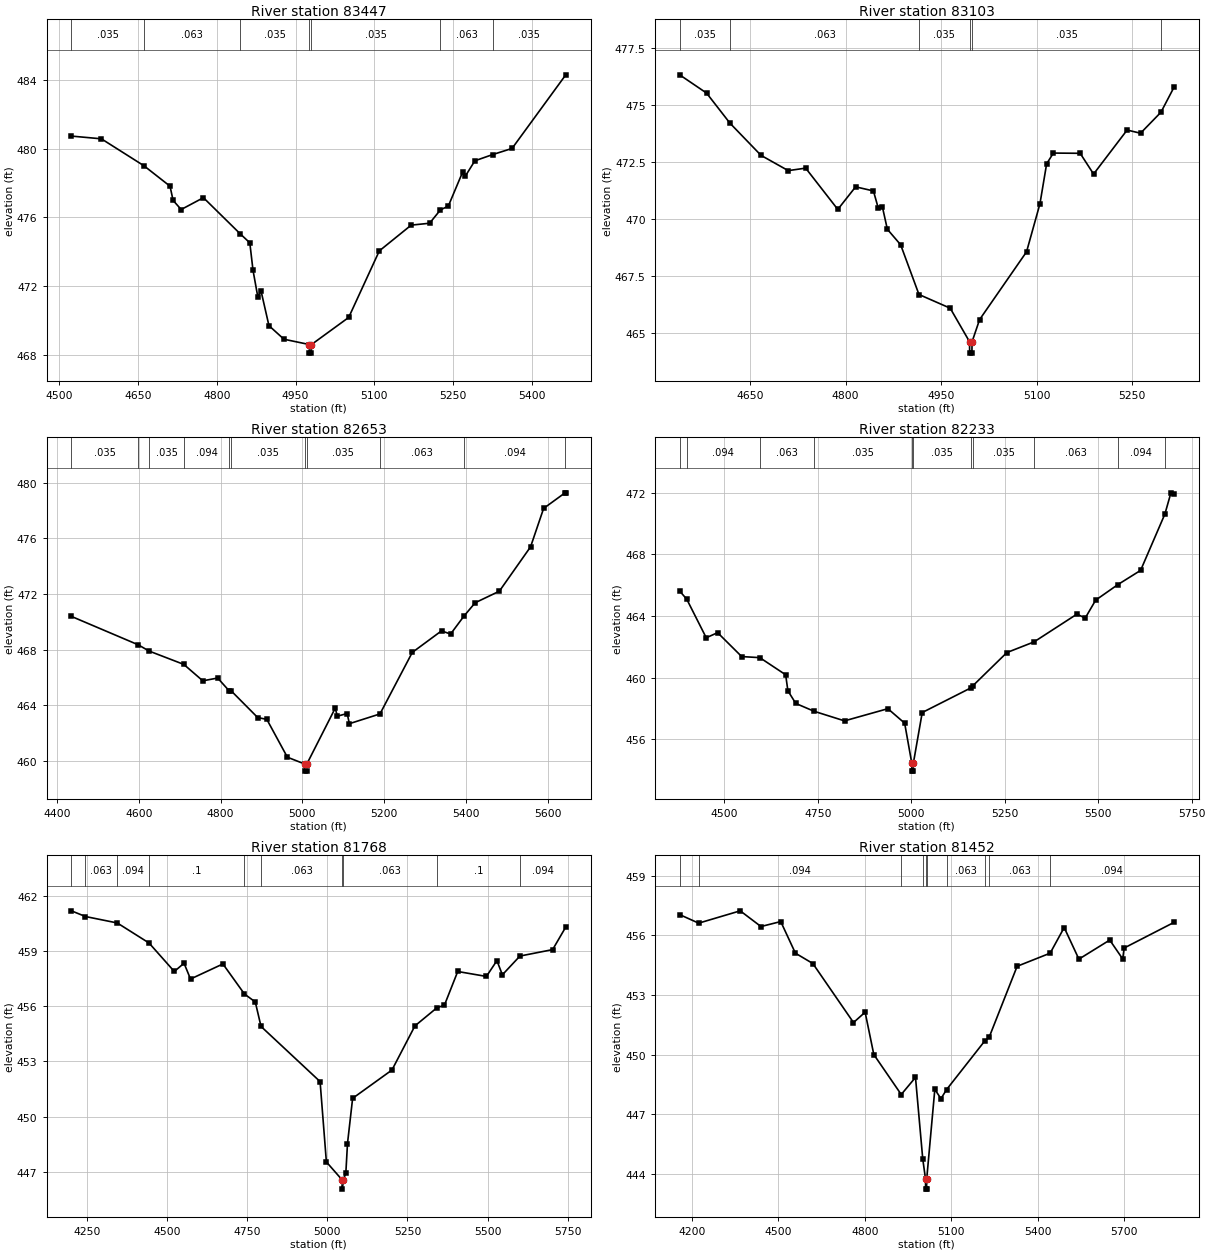
Type RM Length L Ch R = 1 ,83447   ,344,344,344
BEGIN DESCRIPTION:
X18231
END DESCRIPTION:
XS GIS Cut Line= 3
      2568491.68     13800199.51      2568953.16     13800488.71
      2569346.18     13800550.12
#Sta/Elev= 30
  4522.8  480.73    4580  480.57  4661.1     479  4710.8  477.81  4716.7  476.98
  4732.1  476.45  4774.5  477.14  4844.7  475.03  4862.9  474.51    4869  472.91
  4878.2  471.35  4884.1  471.73  4899.4  469.68    4928  468.89  4976.4  468.58
  4976.6  468.08  4980.1  468.08  4980.4  468.58  5051.4  470.16  5109.8  474.04
  5170.5  475.54  5205.6  475.65  5226.3  476.43  5241.3  476.65  5268.4  478.62
  5273.4  478.38  5291.9  479.29  5325.6  479.65  5362.8  480.01  5465.2   484.3
#Mann= 7 ,-1 , 0
  4522.8    .035       0  4661.1    .063       0  4844.7    .035       0
  4976.4    .035       0  4980.4    .035       0  5226.3    .063       0
  5325.6    .035       0
Bank Sta=4976.4,4980.4
XS Rating Curve= 0 ,0
Exp/Cntr=0.3,0.1

Type RM Length L Ch R = 1 ,83103   ,450,450,450
BEGIN DESCRIPTION:
Big Fivemile Creek 114.0
END DESCRIPTION:
XS GIS Cut Line= 3
        2568525.       13800425.        2568825.       13800775.
        2569125.       13800675.
#Sta/Elev= 30
    4539  476.32  4581.3  475.52  4618.1   474.2  4666.9  472.79  4709.7  472.12
  4737.1  472.23  4787.6  470.42  4815.6  471.41  4843.6  471.23  4851.3  470.47
  4857.8  470.52  4865.5  469.55  4886.4  468.87  4915.2  466.69  4964.3  466.09
  4994.7  464.62  4994.9  464.12  4998.4  464.12  4998.7  464.62  5010.5  465.59
  5084.3  468.56  5105.4  470.67  5115.9  472.42  5126.5  472.89  5168.6  472.88
  5189.7  471.97  5242.4   473.9  5263.5  473.76  5295.6  474.68  5316.2  475.78
#Mann= 6 ,-1 , 0
    4539    .035       0  4618.1    .063       0  4915.2    .035       0
  4994.7    .035       0  4998.7    .035       0  5295.6    .063       0
Bank Sta=4994.7,4998.7
XS Rating Curve= 0 ,0
Exp/Cntr=0.3,0.1

Type RM Length L Ch R = 1 ,82653   ,420,420,420
BEGIN DESCRIPTION:
Big Fivemile Creek 113.0
END DESCRIPTION:
XS GIS Cut Line= 3
      2568425.02     13800675.04        2568675.       13801175.
      2569275.02     13800924.99
#Sta/Elev= 30
  4435.1   470.4  4598.4  468.36  4625.1  467.91    4710  466.95  4756.5  465.77
  4792.8  465.97  4821.6  465.03  4826.5  465.03  4890.7  463.13    4913     463
  4963.3  460.28  5006.7  459.78    5007  459.28  5010.5  459.28  5010.7  459.78
  5080.2   463.8  5085.6  463.23  5109.5  463.42  5114.9  462.69  5189.7  463.39
  5268.7  467.81  5340.2  469.36  5362.4  469.13  5394.8  470.41  5422.5  471.38
  5481.6  472.21    5558   475.4  5589.9  478.16  5642.3  479.28  5644.1  479.28
#Mann= 11 ,-1 , 0
  4435.1    .035       0  4598.4    .063       0  4625.1    .035       0
    4710    .094       0  4821.6    .063       0  4826.5    .035       0
  5006.7    .035       0  5010.7    .035       0  5189.7    .063       0
  5394.8    .094       0  5642.3    .063       0
Bank Sta=5006.7,5010.7
XS Rating Curve= 0 ,0
Exp/Cntr=0.3,0.1

Type RM Length L Ch R = 1 ,82233   ,465,465,465
BEGIN DESCRIPTION:
Big Fivemile Creek 112.0
END DESCRIPTION:
XS GIS Cut Line= 3
      2568024.99     13801224.99        2568575.       13801575.
      2569175.04     13801274.98
#Sta/Elev= 30
  4380.1  465.62  4399.1  465.09  4451.2  462.59  4481.7  462.92  4546.1  461.37
  4594.6   461.3  4663.7  460.19  4669.7  459.15  4690.8  458.33    4740  457.82
  4821.2   457.2  4937.2  457.99  4982.1  457.05  5001.3  454.44  5001.5  453.94
    5005  453.94  5005.3  454.44  5029.1  457.74  5158.6  459.33  5165.2  459.49
  5255.6  461.63  5328.2  462.32  5442.9  464.12  5465.3  463.87  5493.2  465.03
  5552.7  466.04  5613.4  466.96  5678.5  470.62  5694.5  471.99  5702.9  471.89
#Mann= 11 ,-1 , 0
  4380.1    .063       0  4399.1    .094       0  4594.6    .063       0
    4740    .035       0  5001.3    .035       0  5005.3    .035       0
  5158.6    .063       0  5165.2    .035       0  5328.2    .063       0
  5552.7    .094       0  5678.5    .063       0
Bank Sta=5001.3,5005.3
XS Rating Curve= 0 ,0
Exp/Cntr=0.3,0.1

Type RM Length L Ch R = 1 ,81768   ,316,316,316
BEGIN DESCRIPTION:
Big Fivemile Creek 111.0
END DESCRIPTION:
XS GIS Cut Line= 3
      2567747.22     13801910.01        2568575.       13802025.
      2569265.12     13801879.63
#Sta/Elev= 30
  4202.4  461.19  4246.3  460.88  4345.4  460.53  4444.4  459.44  4523.2  457.89
  4553.5  458.34  4573.7  457.48  4674.7   458.3  4741.6  456.67  4775.6  456.23
  4793.5   454.9  4977.6   451.9  4997.2  447.53  5046.4  446.55  5046.6  446.05
  5050.4  446.55  5057.9  446.94    5063  448.53    5079  450.99  5201.6  452.53
  5273.2  454.93  5341.3  455.91  5365.2  456.06  5406.6  457.89    5496  457.62
  5528.7  458.48  5545.8  457.71  5600.5  458.73  5702.4  459.08  5743.4  460.31
#Mann= 10 ,-1 , 0
  4202.4    .035       0  4246.3    .063       0  4345.4    .094       0
  4444.4      .1       0  4741.6    .094       0  4793.5    .063       0
  5046.4     .05       0  5050.4    .063       0  5341.3      .1       0
  5600.5    .094       0
Bank Sta=5046.4,5050.4
XS Rating Curve= 0 ,0
Exp/Cntr=0.3,0.1

Type RM Length L Ch R = 1 ,81452   ,227,227,227
BEGIN DESCRIPTION:
Big Fivemile Creek 110.0
END DESCRIPTION:
XS GIS Cut Line= 3
      2567716.49     13802223.81       2568608.6      13802340.7
      2569408.49     13802174.57
#Sta/Elev= 30
  4156.9  457.04  4222.9  456.61  4367.2  457.23  4439.2  456.44  4507.9  456.69
  4558.8   455.1  4619.3  454.58  4760.5  451.61  4800.9  452.13  4831.1     450
  4926.3  447.99  4975.8  448.85    5001  444.75  5010.7  443.73  5010.9  443.23
  5014.4  443.23  5014.7  443.73  5042.9  448.25  5064.2  447.78  5083.8  448.24
  5216.1  450.68  5231.6  450.87  5328.7  454.44  5443.4   455.1  5492.1  456.39
  5543.2   454.8  5650.3  455.76  5695.3  454.81  5700.4  455.36  5873.6  456.65
#Mann= 10 ,-1 , 0
  4156.9    .063       0  4222.9    .094       0  4926.3    .063       0
    5001    .094       0  5010.7     .05       0  5014.7    .094       0
  5083.8    .063       0  5216.1    .094       0  5231.6    .063       0
  5443.4    .094       0
Bank Sta=5010.7,5014.7
XS Rating Curve= 0 ,0
Exp/Cntr=0.3,0.1

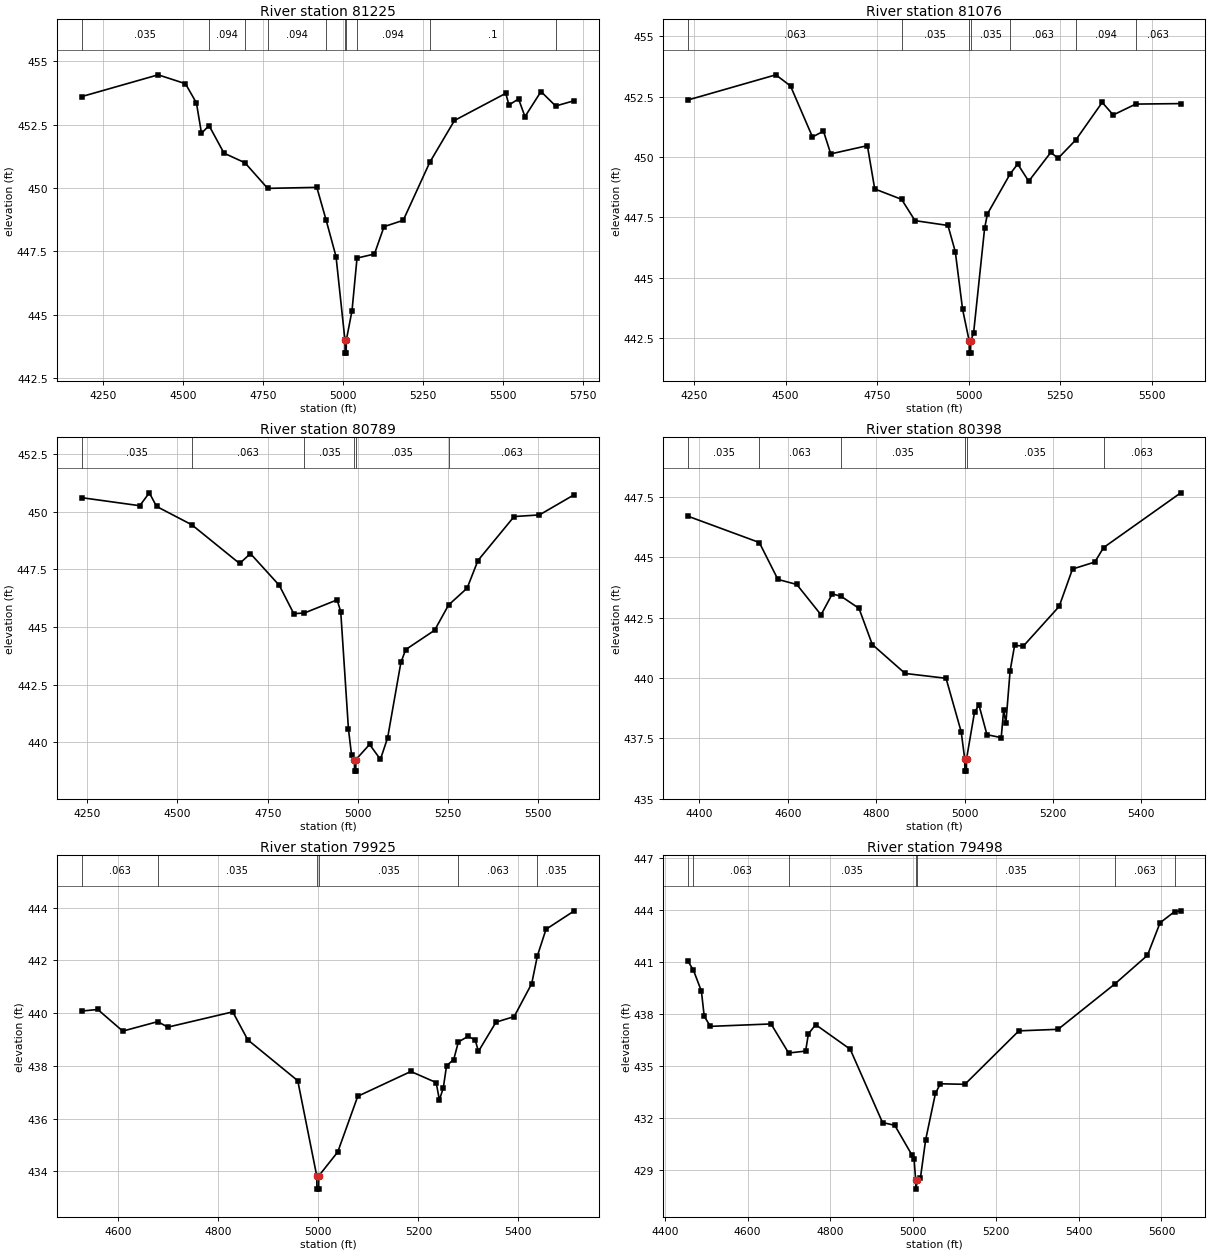
Type RM Length L Ch R = 1 ,81225   ,149,149,149
BEGIN DESCRIPTION:
X18230
END DESCRIPTION:
XS GIS Cut Line= 4
       2567671.5     13802590.16      2568153.41     13802549.45
      2568684.66     13802549.45      2569209.02     13802573.75
#Sta/Elev= 30
  4182.1  453.61  4421.5  454.47  4506.8  454.12  4541.1  453.36  4556.9  452.16
  4580.4  452.47  4627.2  451.38  4692.7     451  4763.7  449.99  4917.3  450.03
  4946.1  448.75  4977.3   447.3  5005.3  443.99  5005.6  443.49  5009.1  443.49
  5009.3  443.99  5027.3  445.17  5042.9  447.24  5097.3   447.4  5127.3  448.48
  5187.3  448.73  5270.3  451.02  5347.5  452.67  5507.7  453.74  5517.7  453.28
  5547.7  453.52  5567.7  452.82  5617.8  453.81  5663.6  453.24  5721.9  453.45
#Mann= 10 ,-1 , 0
  4182.1    .035       0  4580.4    .094       0  4692.7    .063       0
  4763.7    .094       0  4946.1    .035       0  5005.3    .035       0
  5009.3    .035       0  5042.9    .094       0  5270.3      .1       0
  5663.6    .094       0
Bank Sta=5005.3,5009.3
XS Rating Curve= 0 ,0
Exp/Cntr=0.3,0.1

Type RM Length L Ch R = 1 ,81076   ,287,287,287
BEGIN DESCRIPTION:
Big Fivemile Creek 109.5
END DESCRIPTION:
XS GIS Cut Line= 3
      2567695.09     13802702.22      2568458.97     13802695.28
      2569038.83     13802743.89
#Sta/Elev= 30
  4233.7  452.36  4473.5   453.4  4513.6  452.94  4573.6  450.83  4603.6  451.07
  4623.6  450.13  4723.6  450.47  4743.6  448.68    4817  448.25  4853.6  447.37
  4943.6  447.17  4963.6  446.09  4983.6   443.7  5001.7  442.39  5001.9  441.89
  5005.4  441.89  5005.7  442.39  5013.7  442.73  5043.8  447.06  5051.5  447.65
  5113.8  449.31  5134.1  449.71  5164.2     449  5224.4  450.19  5244.5  449.95
  5292.9  450.71  5364.9  452.26    5395  451.74  5456.4  452.19  5579.5  452.21
#Mann= 7 ,-1 , 0
  4233.7    .063       0    4817    .035       0  5001.7    .035       0
  5005.7    .035       0  5113.8    .063       0  5292.9    .094       0
  5456.4    .063       0
Bank Sta=5001.7,5005.7
XS Rating Curve= 0 ,0
Exp/Cntr=0.3,0.1

Type RM Length L Ch R = 1 ,80789   ,391,391,391
BEGIN DESCRIPTION:
Big Fivemile Creek 109.0
END DESCRIPTION:
XS GIS Cut Line= 3
      2567587.28     13802894.46      2568473.24     13802925.22
      2568951.62     13802900.69
#Sta/Elev= 30
  4234.2  450.62  4395.5  450.27    4422  450.83    4442  450.24  4539.9  449.44
  4672.2  447.76  4702.2  448.19  4782.2  446.81  4822.3  445.58  4851.9  445.61
  4942.3  446.18  4952.4  445.67  4973.8  440.57  4982.4  439.44  4990.4  439.24
  4990.6  438.74  4994.1  438.74  4994.4  439.24  5032.4   439.9  5062.4  439.25
  5082.4  440.19  5119.1  443.46  5132.5  444.02  5212.6  444.86  5251.4  445.96
  5302.7  446.69  5332.7  447.89  5432.9   449.8    5503  449.87  5599.7  450.75
#Mann= 6 ,-1 , 0
  4234.2    .035       0  4539.9    .063       0  4851.9    .035       0
  4990.4    .035       0  4994.4    .035       0  5251.4    .063       0
Bank Sta=4990.4,4994.4
XS Rating Curve= 0 ,0
Exp/Cntr=0.3,0.1

Type RM Length L Ch R = 1 ,80398   ,473,473,473
BEGIN DESCRIPTION:
Big Fivemile Creek 108.0
END DESCRIPTION:
XS GIS Cut Line= 3
       2567710.3     13803208.25      2568405.56     13803282.08
      2568817.79     13803226.71
#Sta/Elev= 30
  4374.3  446.71  4535.6  445.62  4577.7  444.09  4620.4  443.88  4675.3  442.62
  4700.8  443.49  4720.7  443.39  4761.2  442.89  4791.3  441.39  4865.6  440.19
  4958.2  439.99  4992.5  437.77  5000.5  436.64  5000.8  436.14  5004.3  436.14
  5004.5  436.64  5022.6  438.58  5032.7  438.88  5050.8  437.65    5083  437.53
  5088.6  438.66  5093.6  438.13  5103.2   440.3  5113.3  441.35  5133.4  441.33
  5214.2  442.97  5244.4  444.52  5294.9  444.81  5314.7  445.41  5489.4  447.68
#Mann= 6 ,-1 , 0
  4374.3    .035       0  4535.6    .063       0  4720.7    .035       0
  5000.5    .035       0  5004.5    .035       0  5314.7    .063       0
Bank Sta=5000.5,5004.5
XS Rating Curve= 0 ,0
Exp/Cntr=0.3,0.1

Type RM Length L Ch R = 1 ,79925   ,427,427,427
BEGIN DESCRIPTION:
Big Fivemile Creek 107.0
END DESCRIPTION:
XS GIS Cut Line= 3
      2567722.61     13803608.18      2568356.34     13803602.03
        2568625.       13803375.
#Sta/Elev= 30
  4526.3  440.08  4558.7  440.14  4608.7  439.32  4678.8  439.68  4698.7  439.47
  4828.7  440.05  4858.7  438.99  4958.7  437.44  4996.7  433.83    4997  433.33
  5000.5  433.33  5000.7  433.83  5038.7  434.74  5078.7  436.85  5184.9  437.79
  5235.5  437.37    5242  436.71  5249.8  437.17  5256.3  438.01  5270.6  438.24
  5279.9  438.91  5299.2  439.12  5313.5  438.99    5320  438.55  5355.2  439.66
  5391.5  439.87  5426.6  441.12  5437.9  442.17  5455.2  443.18  5511.8  443.88
#Mann= 6 ,-1 , 0
  4526.3    .063       0  4678.8    .035       0  4996.7    .035       0
  5000.7    .035       0  5279.9    .063       0  5437.9    .035       0
Bank Sta=4996.7,5000.7
XS Rating Curve= 0 ,0
Exp/Cntr=0.3,0.1

Type RM Length L Ch R = 1 ,79498   ,477,477,477
BEGIN DESCRIPTION:
Big Fivemile Creek 106.0
END DESCRIPTION:
XS GIS Cut Line= 3
      2567824.97     13803774.99        2568325.       13803975.
      2568675.02     13803424.97
#Sta/Elev= 30
  4456.1  441.04  4469.3  440.52  4488.4  439.32  4495.2  437.87    4510  437.28
  4656.7  437.42  4699.2  435.74  4740.2  435.85  4746.9  436.84  4764.4  437.38
  4847.9  435.96    4926  431.72  4955.6  431.56  4997.6  429.82  5002.3  429.59
  5006.2  428.37  5006.4  427.87  5010.2  428.37  5017.5   428.5  5030.2  430.72
  5053.9  433.41  5065.8  433.96    5125  433.93  5255.4  437.02  5350.2  437.11
  5487.2  439.73  5566.1  441.39  5596.6  443.27  5631.5  443.91  5646.6  443.96
#Mann= 7 ,-1 , 0
  4456.1     .12       0  4469.3    .063       0  4699.2    .035       0
  5006.2    .035       0  5010.2    .035       0  5487.2    .063       0
  5631.5    .035       0
Bank Sta=5006.2,5010.2
XS Rating Curve= 0 ,0
Exp/Cntr=0.3,0.1

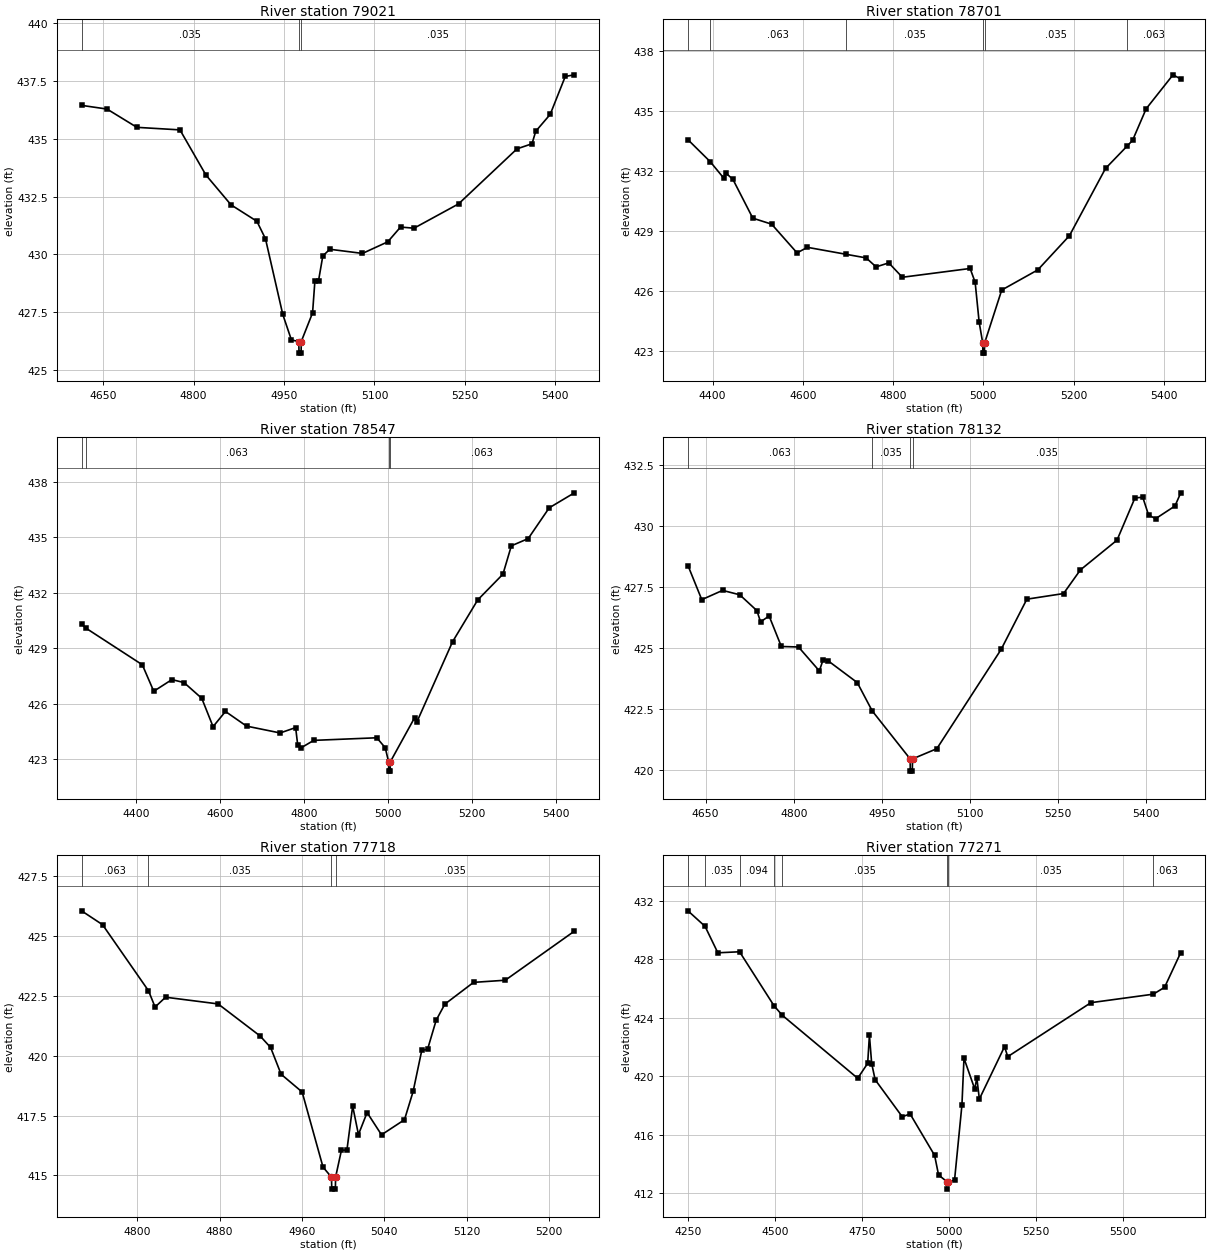
Type RM Length L Ch R = 1 ,79021   ,320,320,320
BEGIN DESCRIPTION:
Big Fivemile Creek 105.0
END DESCRIPTION:
XS GIS Cut Line= 3
      2568375.01     13804524.99        2568625.       13804225.
        2568775.     13803824.99
#Sta/Elev= 30
    4614  436.44  4656.3  436.28  4705.8  435.49  4777.3  435.38  4820.3  433.43
    4862  432.14  4904.9  431.43  4919.2  430.67  4947.9   427.4  4962.2   426.3
  4974.5  426.23  4974.8  425.73  4978.3  425.73  4978.5  426.23  4997.3  427.47
  5001.2  428.86  5007.2  428.86  5014.3  429.93  5025.9  430.22  5080.1  430.04
    5122  430.54  5143.3  431.18  5165.6  431.13  5239.5  432.18  5336.5  434.56
  5361.4  434.78  5367.6  435.32  5391.6  436.05  5416.6  437.69  5431.7  437.76
#Mann= 3 ,-1 , 0
    4614    .035       0  4974.5    .035       0  4978.5    .035       0
Bank Sta=4974.5,4978.5
XS Rating Curve= 0 ,0
Exp/Cntr=0.3,0.1

Type RM Length L Ch R = 1 ,78701   ,154,154,154
BEGIN DESCRIPTION:
X18229
END DESCRIPTION:
XS GIS Cut Line= 4
      2568688.95     13804878.41      2568888.19     13804732.73
      2568907.47     13804460.67      2568920.28     13803888.28
#Sta/Elev= 30
  4345.5  433.58  4394.8  432.48  4424.3  431.67  4430.5  431.89  4445.2  431.59
  4489.2  429.65  4530.9  429.35  4587.3  427.91  4610.1  428.19    4696  427.84
  4740.4  427.66  4762.4  427.21  4790.5  427.41  4820.6  426.69  4970.8  427.13
  4981.9  426.44  4990.8  424.44  4998.8  423.39    4999  422.89  5002.5  422.89
  5002.8  423.39  5040.8  426.05  5120.8  427.06  5190.8  428.77  5270.8  432.14
  5317.8  433.24  5330.8  433.55  5360.9  435.13  5420.4  436.83  5437.6  436.62
#Mann= 6 ,-1 , 0
  4345.5    .035       0  4394.8    .063       0    4696    .035       0
  4998.8    .035       0  5002.8    .035       0  5317.8    .063       0
Bank Sta=4998.8,5002.8
XS Rating Curve= 0 ,0
Exp/Cntr=0.3,0.1

Type RM Length L Ch R = 1 ,78547   ,415,415,415
BEGIN DESCRIPTION:
Big Fivemile Creek 104.5
END DESCRIPTION:
XS GIS Cut Line= 3
      2568826.06     13804998.37      2569023.15     13804752.01
      2569053.14     13803895.13
#Sta/Elev= 30
    4270  430.31  4279.5   430.1  4414.6  428.11  4441.8  426.68    4485  427.31
  4513.8  427.15  4556.1   426.3    4583  424.77  4612.5  425.59  4662.6   424.8
  4742.6  424.43  4779.5  424.72  4784.5  423.77  4792.6  423.63  4822.6  424.03
  4972.7  424.17  4992.8  423.63  5000.8  422.87    5001  422.37  5004.5  422.37
  5004.8  422.87  5062.6  425.25  5067.6     425  5152.9  429.35  5212.9  431.61
  5272.9     433  5292.9  434.53    5333  434.92    5383  436.58  5442.9  437.39
#Mann= 4 ,-1 , 0
    4270    .035       0  4279.5    .063       0  5000.8     .05       0
  5004.8    .063       0
Bank Sta=5000.8,5004.8
XS Rating Curve= 0 ,0
Exp/Cntr=0.3,0.1

Type RM Length L Ch R = 1 ,78132   ,414,414,414
BEGIN DESCRIPTION:
Big Fivemile Creek 104.0
END DESCRIPTION:
XS GIS Cut Line= 3
      2568916.06     13804979.05      2569218.08     13804576.35
      2569524.06      13804439.4
#Sta/Elev= 30
  4619.9  428.38  4643.4  426.98  4678.8  427.36    4708  427.18  4737.2  426.53
  4743.4  426.07    4758  426.31  4778.8  425.06    4808  425.04  4843.4  424.06
    4850  424.52    4858  424.48    4908  423.58  4933.4  422.42    4998  420.45
  4998.2  419.95  5001.7  419.95    5002  420.45  5043.4  420.87  5152.8  424.94
  5196.6     427    5259  427.23  5287.7   428.2    5350  429.42  5380.5  431.15
  5393.8  431.18  5403.7  430.45  5415.7   430.3  5448.6  430.82  5458.5  431.36
#Mann= 4 ,-1 , 0
  4619.9    .063       0  4933.4    .035       0    4998    .035       0
    5002    .035       0
Bank Sta=4998,5002
XS Rating Curve= 0 ,0
Exp/Cntr=0.3,0.1

Type RM Length L Ch R = 1 ,77718   ,447,447,447
BEGIN DESCRIPTION:
Big Fivemile Creek 103.0
END DESCRIPTION:
XS GIS Cut Line= 3
        2569025.       13804975.        2569275.       13804925.
      2569475.04     13804824.98
#Sta/Elev= 30
  4745.9  426.06  4766.3  425.48  4810.9  422.72  4817.3  422.04  4827.5  422.45
  4878.5  422.17  4919.3  420.83  4929.5  420.35  4939.7  419.23  4960.1  418.49
  4980.4  415.35  4988.6  414.93  4988.9  414.43  4992.4  414.43  4992.6  414.93
  4998.3  416.06  5003.6  416.06  5009.2   417.9  5014.8  416.71  5023.2  417.63
  5037.2   416.7  5059.5  417.33  5067.9  418.51  5076.3  420.23  5081.9  420.27
  5090.3  421.49  5098.7  422.16  5126.6  423.07  5157.4  423.16  5224.5  425.21
#Mann= 4 ,-1 , 0
  4745.9    .063       0  4810.9    .035       0  4988.6    .035       0
  4992.6    .035       0
Bank Sta=4988.6,4992.6
XS Rating Curve= 0 ,0
Exp/Cntr=0.3,0.1

Type RM Length L Ch R = 1 ,77271   ,223,223,223
BEGIN DESCRIPTION:
Big Fivemile Creek 102.0
END DESCRIPTION:
XS GIS Cut Line= 5
      2568829.59       13805303.      2569567.72     13805227.43
        2569575.       13805225.      2569577.18     13805216.29
      2570140.99     13804876.56
#Sta/Elev= 30
  4249.8   431.3  4298.9  430.24  4335.7  428.43  4398.2   428.5  4497.5   424.8
  4520.9  424.16  4737.8  419.85  4766.5  420.87  4771.5  422.79    4778  420.86
    4788  419.75  4865.9  417.22  4888.5  417.41  4958.9  414.58  4970.3  413.24
  4994.8  412.77  4995.1  412.27  4998.8  412.77  5016.2  412.87  5037.5  418.02
  5043.4  421.22  5074.4  419.11  5080.3  419.89  5087.6  418.43  5159.9  422.01
  5169.3  421.33  5408.4  425.02  5587.7   425.6  5620.1  426.07  5666.7  428.45
#Mann= 8 ,-1 , 0
  4249.8    .063       0  4298.9    .035       0  4398.2    .094       0
  4497.5    .063       0  4520.9    .035       0  4994.8    .035       0
  4998.8    .035       0  5587.7    .063       0
Bank Sta=4994.8,4998.8
XS Rating Curve= 0 ,0
Exp/Cntr=0.3,0.1

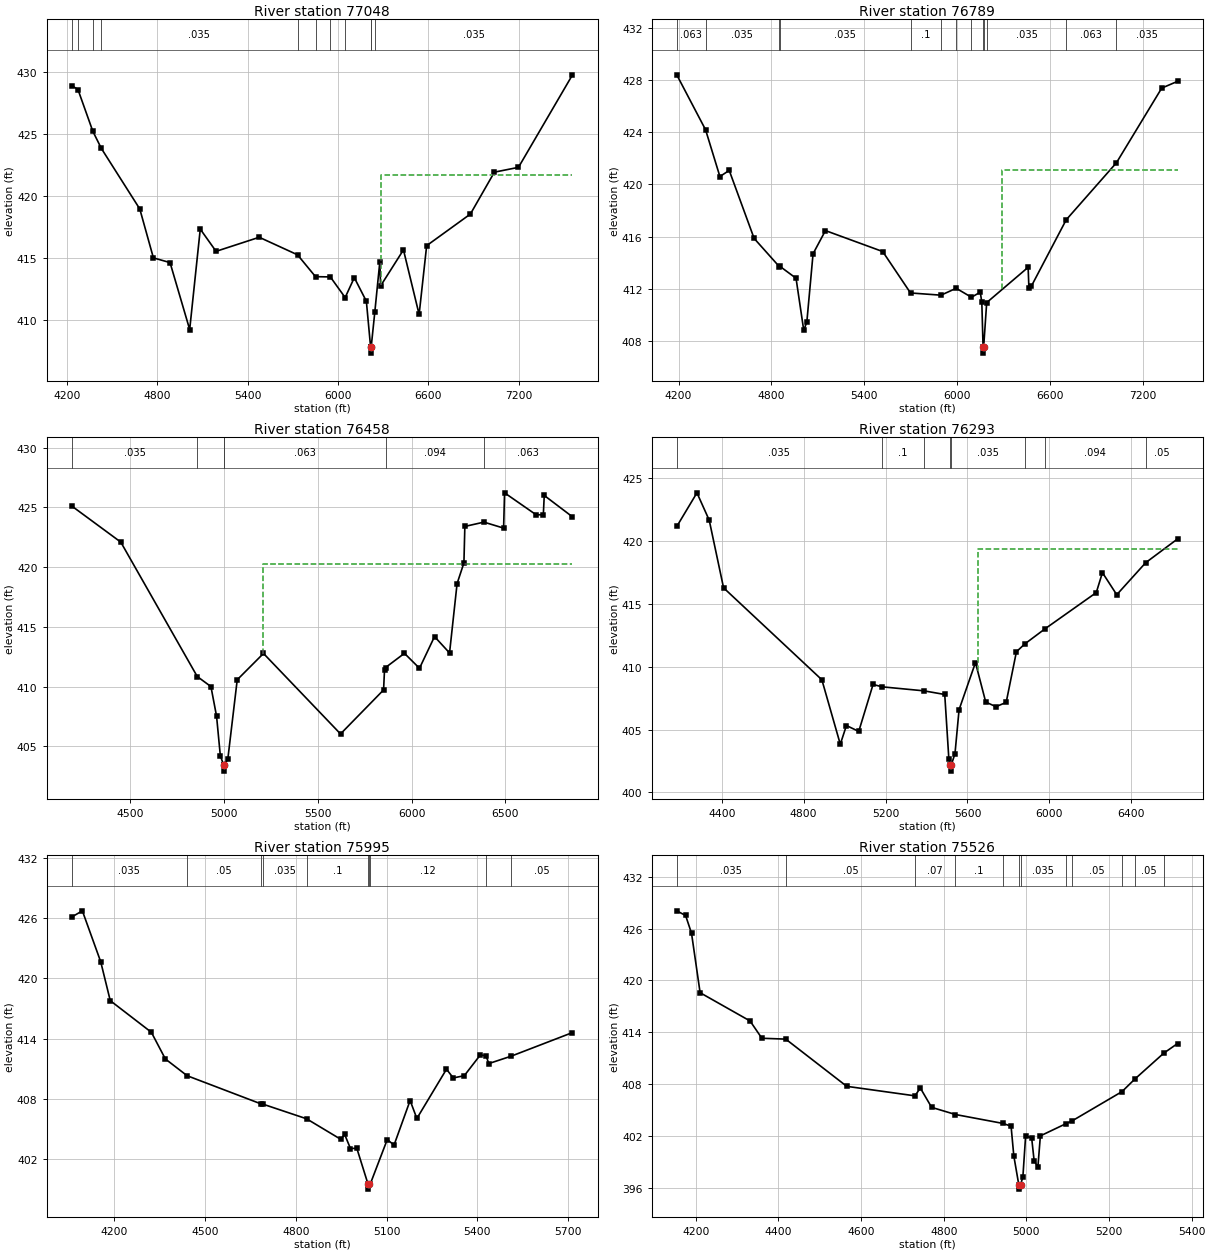
Type RM Length L Ch R = 1 ,77048   ,259,259,259
BEGIN DESCRIPTION:
Big Fivemile Creek 97.0
END DESCRIPTION:
XS GIS Cut Line= 5
      2568934.64     13805323.75      2570139.52     13805445.28
      2570677.72     13805490.42      2571264.52     13805528.61
       2572254.1     13805500.84
#Sta/Elev= 30
  4229.7  428.94  4271.3  428.62  4370.1  425.24  4426.8  423.85  4682.3  418.95
  4772.8  414.99  4883.4  414.61    5014  409.19  5084.3  417.32  5189.4  415.52
  5476.3  416.66  5730.8  415.24  5850.4  413.47    5949  413.45  6047.5  411.78
  6108.3  413.39  6188.5  411.48  6216.6  407.78  6216.8  407.28  6220.6  407.78
  6244.6   410.6    6278  414.68    6283  412.72  6435.1  415.64  6539.2  410.41
  6589.3  415.98  6880.1  418.54  7039.5  421.93  7199.6  422.32  7558.8  429.81
#Mann= 11 ,-1 , 0
  4229.7    .035       0  4271.3    .094       0  4370.1    .063       0
  4426.8    .035       0  5730.8    .094       0  5850.4      .1       0
    5949    .063       0  6047.5    .094       0  6216.6    .035       0
  6220.6    .094       0  6244.6    .035       0
#XS Ineff= 2 , 0
       0  3713.4  421.66  6286.6       0  421.66
Permanent Ineff=
       F       F
Bank Sta=6216.6,6220.6
XS Rating Curve= 0 ,0
Exp/Cntr=0.3,0.1

Type RM Length L Ch R = 1 ,76789   ,331,331,331
BEGIN DESCRIPTION:
Big Fivemile Creek 96.5
END DESCRIPTION:
XS GIS Cut Line= 6
      2569037.86     13805537.37      2569683.73     13805605.08
      2570511.86     13805594.66      2570866.02     13805605.08
      2571511.86     13805641.54      2572267.08     13805589.46
#Sta/Elev= 30
  4188.2  428.42  4374.4   424.2  4466.9  420.61  4527.2  421.08    4688  415.86
  4850.3   413.7  4855.2  413.71  4958.9   412.8  5008.9  408.79  5028.9  409.47
  5068.9  414.68  5148.9  416.46  5518.9  414.85  5698.5  411.67  5895.4   411.5
  5993.8  412.03  6092.3  411.34  6149.3  411.73  6159.3  410.95  6167.3  407.55
  6167.6  407.05  6171.3  407.55  6190.8  410.93  6458.5  413.64  6463.5  412.08
  6479.8   412.2  6704.7  417.29  7029.3  421.67  7321.7   427.4    7424  427.92
#Mann= 13 ,-1 , 0
  4188.2    .063       0  4374.4    .035       0  4850.3    .063       0
  4855.2    .035       0  5698.5      .1       0  5895.4    .063       0
  5993.8    .094       0  6092.3    .063       0  6167.3    .035       0
  6171.3    .063       0  6190.8    .035       0  6704.7    .063       0
  7029.3    .035       0
#XS Ineff= 2 , 0
       0  3707.5  421.08  6292.5       0  421.08
Permanent Ineff=
       F       F
Bank Sta=6167.3,6171.3
XS Rating Curve= 0 ,0
Exp/Cntr=0.3,0.1

Type RM Length L Ch R = 1 ,76458   ,165,165,165
BEGIN DESCRIPTION:
Big Fivemile Creek 96.0
END DESCRIPTION:
XS GIS Cut Line= 3
      2569103.76     13805912.12      2570595.58     13805938.12
      2571768.93     13805882.87
#Sta/Elev= 30
  4190.6  425.11  4451.9  422.09  4859.2  410.85    4932  410.01    4962  407.53
    4982  404.23  4999.9  403.44  5000.1  402.94  5004.1  403.44    5022  403.96
    5072  410.58  5211.8  412.78  5622.1  406.05  5851.3  409.73  5856.3  411.41
  5861.7   411.6  5962.4  412.79  6042.5  411.54  6122.6  414.19  6202.6  412.82
  6242.7  418.62  6279.1  420.35  6284.1   423.4  6385.7  423.76  6490.5  423.26
  6495.5  426.21  6663.2  424.38  6701.9  424.37  6706.9  425.99  6857.3   424.2
#Mann= 6 ,-1 , 0
  4190.6    .035       0  4859.2    .063       0  4999.9     .05       0
  5004.1    .063       0  5861.7    .094       0  6385.7    .063       0
#XS Ineff= 2 , 0
       0                  5209.7       0  420.23
Permanent Ineff=
       F       F
Bank Sta=4999.9,5004.1
XS Rating Curve= 0 ,0
Exp/Cntr=0.3,0.1

Type RM Length L Ch R = 1 ,76293   ,298,298,298
BEGIN DESCRIPTION:
Big Fivemile Creek 95.5
END DESCRIPTION:
XS GIS Cut Line= 3
      2569126.48     13806064.88      2570543.58     13806103.88
      2571571.96     13806123.34
#Sta/Elev= 30
  4180.1  421.16  4278.7  423.84  4338.7  421.66  4408.7  416.28  4888.9  408.96
  4978.9  403.83  5008.9  405.32    5069  404.85    5139  408.59  5182.8   408.4
  5387.6  408.08  5489.1  407.79  5509.1  402.68    5517  402.19  5517.3  401.69
  5521.2  402.19  5539.1  403.08  5559.1  406.58  5639.2  410.33  5689.2  407.19
  5739.2  406.82  5789.2  407.16  5839.2  411.19  5879.9  411.81  5978.4  413.01
  6229.3   415.9  6259.3  417.49  6329.3  415.73  6470.7  418.28  6626.3  420.17
#Mann= 8 ,-1 , 0
  4180.1    .035       0  5182.8      .1       0  5387.6    .035       0
    5517    .035       0  5521.2    .035       0  5879.9    .063       0
  5978.4    .094       0  6470.7     .05       0
#XS Ineff= 2 , 0
       0                  5649.7       0  419.36
Permanent Ineff=
       F       F
Bank Sta=5517,5521.2
XS Rating Curve= 0 ,0
Exp/Cntr=0.3,0.1

Type RM Length L Ch R = 1 ,75995   ,469,469,469
BEGIN DESCRIPTION:
Big Fivemile Creek 95.0
END DESCRIPTION:
XS GIS Cut Line= 4
      2569132.98     13806090.87      2570075.05     13806374.83
        2570075.       13806375.      2570674.97     13806674.99
#Sta/Elev= 30
  4059.7  426.12  4094.9  426.74  4155.6  421.66  4187.1  417.79  4322.9  414.64
  4369.2  411.98  4441.1  410.31  4684.7  407.51  4691.3  407.48  4835.8  406.02
  4949.6  403.96  4961.4  404.48  4980.9  403.05  5001.8  403.09  5038.9  399.51
  5039.2  399.01  5043.2  399.51  5046.2  399.51  5102.5  403.95  5124.9   403.4
    5178  407.84  5200.3  406.05  5298.2  410.96  5320.5  410.09  5356.9  410.31
    5410  412.38    5429   412.3  5437.9  411.52  5512.2  412.26  5714.6  414.61
#Mann= 10 ,-1 , 0
  4059.7    .035       0  4441.1     .05       0  4684.7     .07       0
  4691.3    .035       0  4835.8      .1       0  5038.9     .05       0
  5043.2      .1       0  5046.2     .12       0    5429     .07       0
  5512.2     .05       0
Bank Sta=5038.9,5043.2
XS Rating Curve= 0 ,0
Exp/Cntr=0.3,0.1

Type RM Length L Ch R = 1 ,75526   ,412,412,412
BEGIN DESCRIPTION:
Big Fivemile Creek 94.0
END DESCRIPTION:
XS GIS Cut Line= 3
      2569125.04     13806125.03        2569775.       13806675.
      2569975.01     13806975.02
#Sta/Elev= 30
  4153.9  428.05  4175.3  427.51  4189.6  425.46  4210.4  418.58  4331.3  415.31
  4359.9  413.31  4417.7  413.21  4565.3  407.75  4730.4  406.65  4743.3  407.56
  4770.7  405.32  4828.4  404.49  4943.3  403.46    4963  403.14  4969.6  399.71
  4981.7  396.36    4982  395.86  4986.1  396.36  4991.6   397.3  4998.2     402
  5012.8  401.79  5018.8  399.14  5027.9  398.41  5033.9  402.02  5095.4  403.42
    5111  403.76  5231.5  407.14  5262.3  408.58  5332.6  411.59  5365.9   412.7
#Mann= 12 ,-1 , 0
  4153.9    .035       0  4417.7     .05       0  4730.4     .07       0
  4828.4      .1       0  4943.3    .035       0  4981.7    .035       0
  4986.1    .035       0  5095.4      .1       0    5111     .05       0
  5231.5     .07       0  5262.3     .05       0  5332.6     .07       0
Bank Sta=4981.7,4986.1
XS Rating Curve= 0 ,0
Exp/Cntr=0.3,0.1