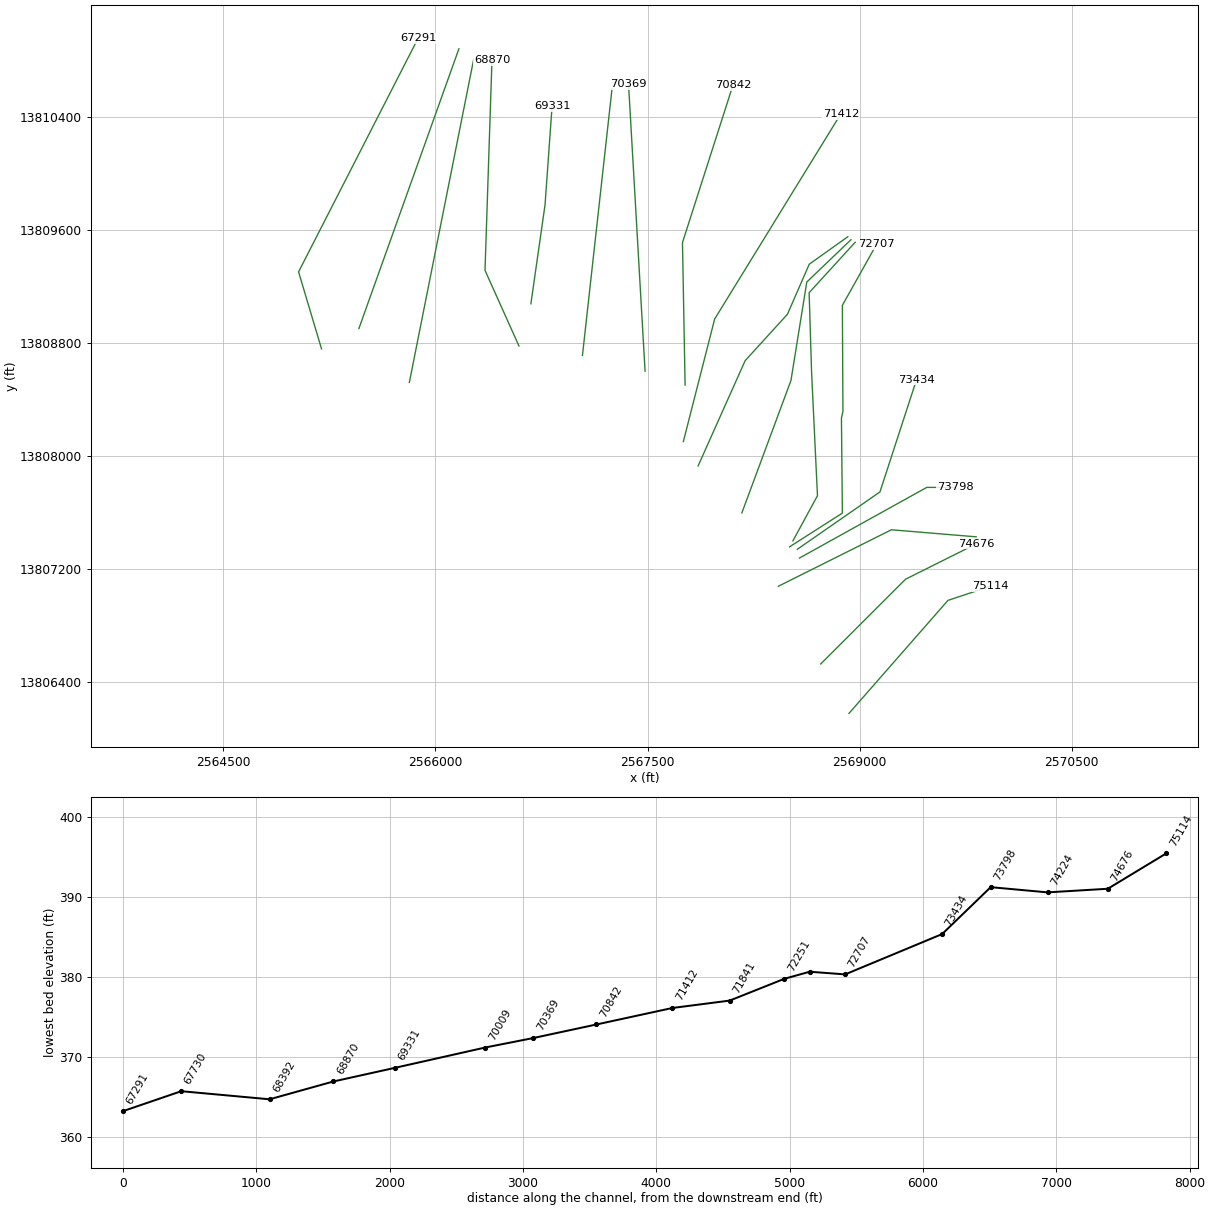
HEC-RAS study Big Fivemile Creek.prj: Big Fivemile Creek Base Level Engineering

--- Big Fivemile Creek.g01 (geometry) --- (continued)

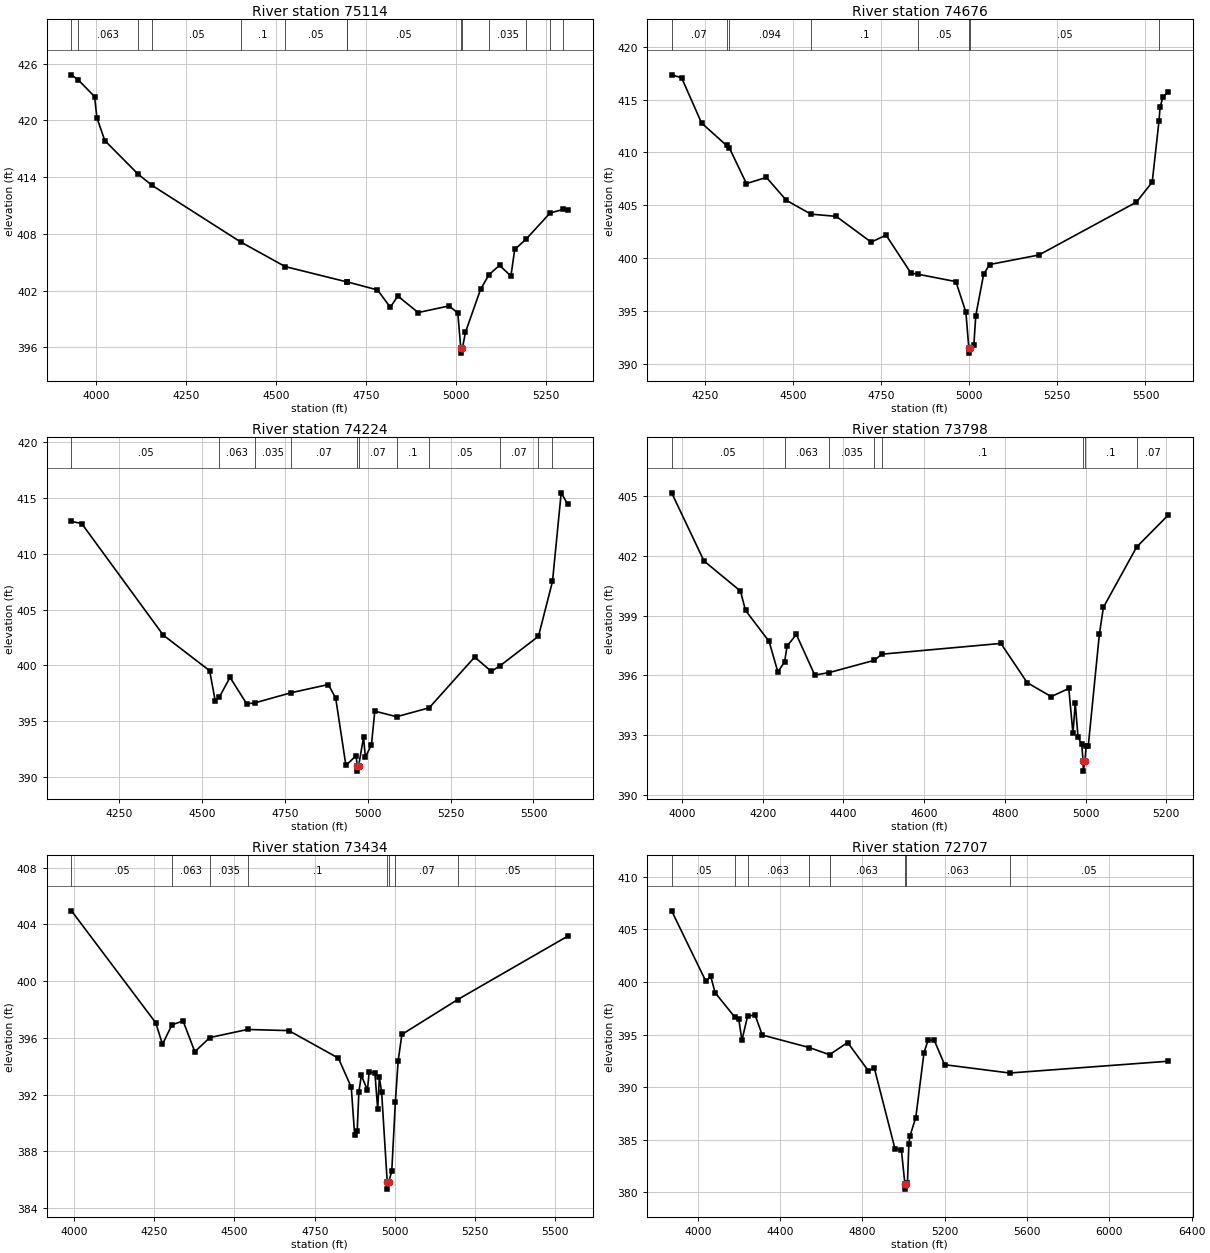
Type RM Length L Ch R = 1 ,75114   ,438,438,438
BEGIN DESCRIPTION:
Big Fivemile Creek 93.0
END DESCRIPTION:
XS GIS Cut Line= 3
      2568924.98     13806174.98        2569625.       13806975.
      2569925.03     13807075.01
#Sta/Elev= 30
    3932  424.82  3951.4  424.26  3996.1  422.52  4002.7  420.27  4024.6  417.87
  4117.4  414.31    4156  413.13  4402.2  407.15  4525.8  404.55  4697.3  402.93
  4698.3  402.93  4782.4  402.08    4818  400.25  4838.9  401.43  4895.4  399.69
  4981.3  400.39  5005.6  399.64  5013.9   395.9  5014.2   395.4  5018.3   395.9
  5026.7  397.59  5068.8  402.14  5092.3   403.7  5121.5  404.68  5153.2  403.55
  5163.7  406.36  5195.2  407.44  5261.9  410.21  5298.1  410.59  5311.3  410.53
#Mann= 14 ,-1 , 0
    3932    .094       0  3951.4    .063       0  4117.4    .035       0
    4156     .05       0  4402.2      .1       0  4525.8     .05       0
  4697.3     .07       0  4698.3     .05       0  5013.9     .05       0
  5018.3     .05       0  5092.3    .035       0  5195.2     .05       0
  5261.9     .07       0  5298.1     .05       0
Bank Sta=5013.9,5018.3
XS Rating Curve= 0 ,0
Exp/Cntr=0.3,0.1

Type RM Length L Ch R = 1 ,74676   ,452,452,452
BEGIN DESCRIPTION:
Big Fivemile Creek 92.0
END DESCRIPTION:
XS GIS Cut Line= 3
      2568725.02     13806525.02        2569325.       13807125.
      2569824.98     13807374.99
#Sta/Elev= 30
  4156.3  417.34  4184.6  417.06  4241.1  412.78  4312.1  410.65  4320.3   410.4
  4368.4  407.04    4425  407.63  4481.5  405.46  4551.3  404.15    4623  403.94
    4722   401.5  4764.4  402.16  4835.1  398.56    4855  398.46  4962.4  397.76
  4990.7  394.87    4999  391.49  4999.3  390.99  5003.5  391.49  5013.2  391.72
  5018.8  394.55  5041.1  398.46  5057.9  399.38  5197.7  400.28  5474.4  405.29
  5519.1  407.18  5538.3  412.96  5541.5  414.29  5549.8  415.27  5563.8  415.69
#Mann= 8 ,-1 , 0
  4156.3     .07       0  4312.1     .05       0  4320.3    .094       0
  4551.3      .1       0    4855     .05       0    4999     .05       0
  5003.5     .05       0  5538.3     .07       0
Bank Sta=4999,5003.5
XS Rating Curve= 0 ,0
Exp/Cntr=0.3,0.1

Type RM Length L Ch R = 1 ,74224   ,426,426,426
BEGIN DESCRIPTION:
Big Fivemile Creek 91.0
END DESCRIPTION:
XS GIS Cut Line= 3
      2568424.97     13807074.98        2569225.       13807475.
      2569824.96       13807425.
#Sta/Elev= 30
    4107  412.89  4137.8   412.7  4383.8  402.71  4523.5  399.53  4540.3  396.85
  4552.4  397.15    4585  398.93  4635.3  396.56    4661  396.66  4769.6  397.56
  4881.3  398.29  4903.6  397.08  4934.4  391.05  4965.1  391.92  4968.5  391.04
  4968.8  390.54    4973  391.04  4987.5  393.56  4993.1  391.78  5011.5  392.92
  5021.5  395.91  5087.2  395.41  5185.7  396.21  5322.6  400.75  5372.7  399.47
  5398.8  399.96    5515  402.61  5557.3  407.52  5583.5  415.45  5603.5  414.41
#Mann= 11 ,-1 , 0
    4107     .05       0  4552.4    .063       0    4661    .035       0
  4769.6     .07       0  4968.5     .05       0    4973     .07       0
  5087.2      .1       0  5185.7     .05       0  5398.8     .07       0
    5515     .05       0  5557.3     .07       0
Bank Sta=4968.5,4973
XS Rating Curve= 0 ,0
Exp/Cntr=0.3,0.1

Type RM Length L Ch R = 1 ,73798   ,364,364,364
BEGIN DESCRIPTION:
Big Fivemile Creek 90.0
END DESCRIPTION:
XS GIS Cut Line= 3
      2568575.01     13807275.01        2569475.       13807775.
      2569674.95       13807775.
#Sta/Elev= 30
  3974.5  405.16  4054.6  401.74  4144.9  400.23  4157.5  399.26  4215.9   397.7
  4237.6  396.17  4254.2  396.67  4260.5  397.47  4283.4  398.05  4329.1  396.01
  4365.2  396.14  4476.2  396.75  4495.1  397.06  4790.1   397.6  4855.3  395.63
  4914.8  394.93  4958.3  395.34  4968.6  393.09  4974.3  394.59  4981.2   392.9
  4990.3  392.53  4993.8  391.69  4994.1  391.19  4998.3  391.69  5001.2  392.44
  5006.5  392.44    5034  398.05    5044  399.41  5126.4  402.44    5204  404.03
#Mann= 8 ,-1 , 0
  3974.5     .05       0  4254.2    .063       0  4365.2    .035       0
  4476.2     .07       0  4495.1      .1       0  4993.8     .05       0
  4998.3      .1       0  5126.4     .07       0
Bank Sta=4993.8,4998.3
XS Rating Curve= 0 ,0
Exp/Cntr=0.3,0.1

Type RM Length L Ch R = 1 ,73434   ,727,727,727
BEGIN DESCRIPTION:
X18228
END DESCRIPTION:
XS GIS Cut Line= 3
      2568559.41     13807336.81       2569143.9     13807742.87
      2569402.31     13808536.57
#Sta/Elev= 30
  3992.2  404.95  4254.7  397.06  4275.6  395.55  4305.4  396.92  4339.9  397.19
  4376.5  395.02  4423.1  396.02  4540.7  396.59  4669.3  396.51  4823.8  394.57
  4863.9  392.52  4874.4  389.16  4882.4  389.44  4887.6   392.2  4895.4  393.35
  4914.3  392.31  4919.6  393.58  4937.5  393.54  4946.2  390.98  4951.5  393.21
  4958.5  392.17  4975.9  385.84  4976.2  385.34  4980.5  385.84  4990.1  386.61
  5001.2  391.46  5010.1   394.4  5021.6  396.24  5195.8   398.7  5538.6  403.17
#Mann= 8 ,-1 , 0
  3992.2     .05       0  4305.4    .063       0  4423.1    .035       0
  4540.7      .1       0  4975.9     .05       0  4980.5      .1       0
  5001.2     .07       0  5195.8     .05       0
Bank Sta=4975.9,4980.5
XS Rating Curve= 0 ,0
Exp/Cntr=0.3,0.1

Type RM Length L Ch R = 1 ,72707   ,266,266,266
BEGIN DESCRIPTION:
X18227
END DESCRIPTION:
XS GIS Cut Line= 6
      2568504.91     13807354.21      2568878.18     13807592.93
      2568871.57     13808266.19       2568882.1     13808312.52
      2568878.18     13809064.28      2569120.59     13809497.17
#Sta/Elev= 30
  3873.1  406.77  4039.4  400.07  4063.1  400.53  4084.5  398.98  4181.6  396.63
  4199.5  396.44  4214.7  394.47  4241.9  396.74  4278.2  396.88  4313.5  394.96
    4542  393.77  4640.4  393.09  4728.3  394.25  4828.3  391.58  4858.3  391.79
  4958.3  384.15  4989.5  384.02  5006.5  380.81  5006.8  380.31  5011.1  380.81
    5019  380.91  5025.8  384.59    5031  385.35  5059.5  387.12  5099.5  393.29
  5119.5   394.5  5149.5  394.45  5199.5  392.14  5515.5  391.35  6284.9  392.47
#Mann= 8 ,-1 , 0
  3873.1     .05       0  4181.6    .035       0  4241.9    .063       0
    4542    .035       0  4640.4    .063       0  5006.5     .05       0
  5011.1    .063       0  5515.5     .05       0
Bank Sta=5006.5,5011.1
XS Rating Curve= 0 ,0
Exp/Cntr=0.3,0.1

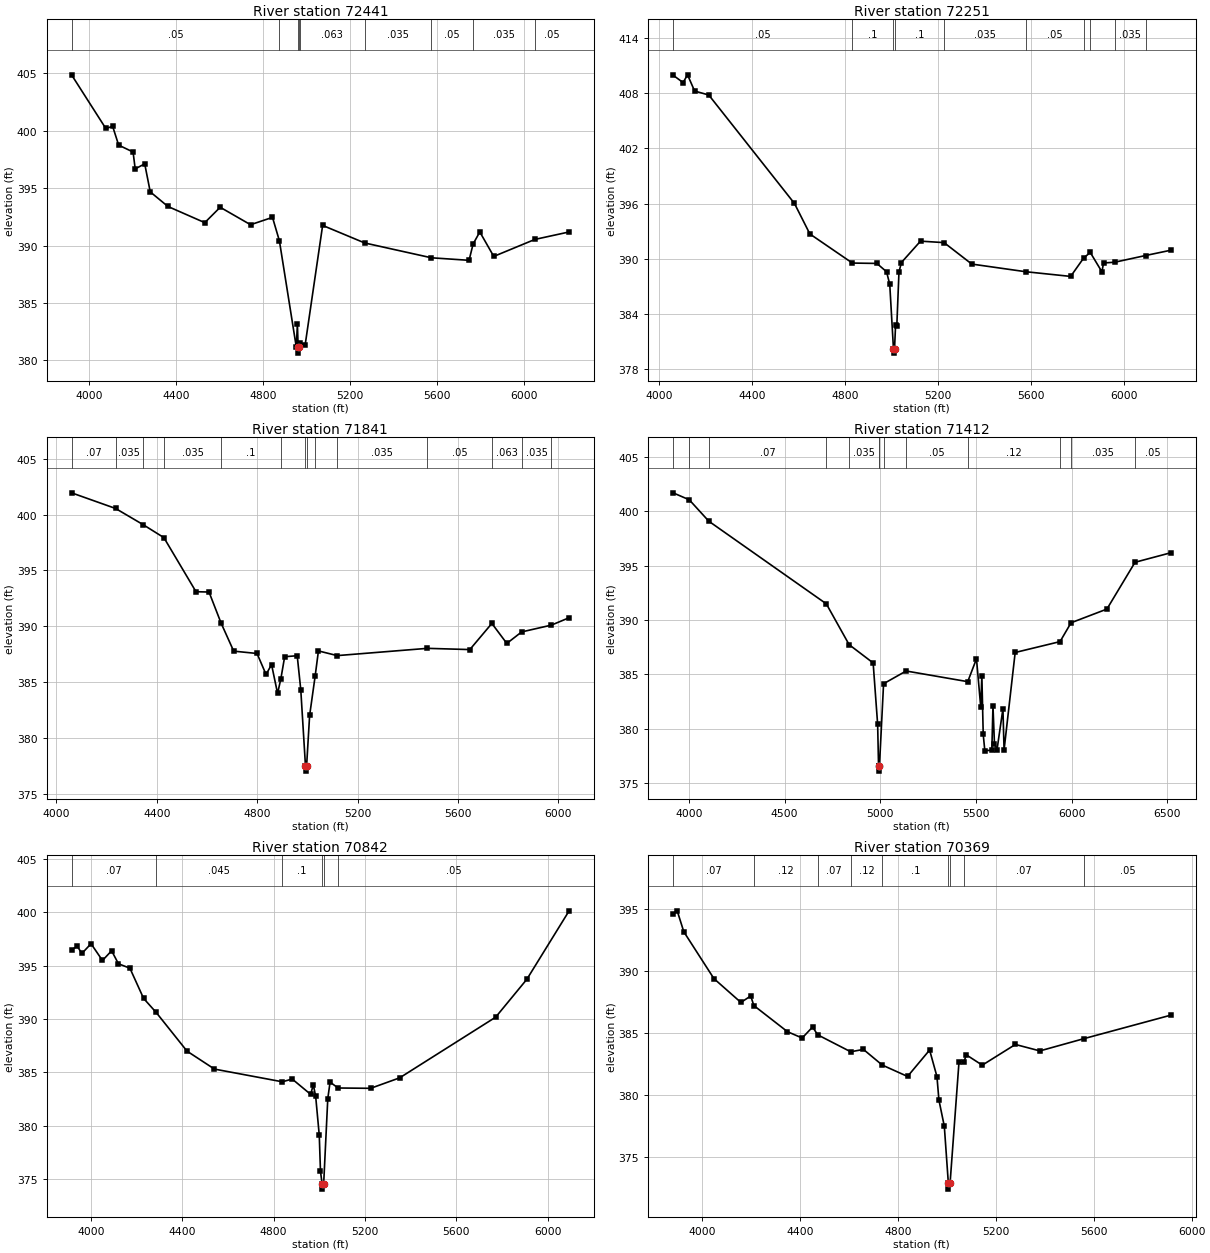
Type RM Length L Ch R = 1 ,72441   ,190,190,190
BEGIN DESCRIPTION:
X18226c
END DESCRIPTION:
XS GIS Cut Line= 5
      2568528.41     13807396.66      2568702.02     13807716.11
      2568660.36     13808591.11        2568643.     13809153.61
      2568968.83     13809510.64
#Sta/Elev= 30
  3919.4  404.87  4076.8   400.2  4108.3  400.38  4135.8  398.75    4202  398.15
  4211.8  396.68  4255.5  397.12  4280.9  394.68    4362  393.41  4531.4     392
  4602.2  393.34  4741.7  391.82  4842.5  392.46  4874.3  390.41  4951.9  381.16
  4956.9  383.17  4960.3  381.14  4960.6  380.64    4965  381.14  4968.9  381.51
  4992.7  381.38  5072.8  391.76  5266.2  390.23  5572.7  388.94  5745.4  388.72
  5764.2  390.15  5794.8  391.19  5858.9  389.06  6047.8  390.54  6205.1  391.19
#Mann= 9 ,-1 , 0
  3919.4     .05       0  4874.3      .1       0  4960.3     .05       0
    4965      .1       0  4968.9    .063       0  5266.2    .035       0
  5572.7     .05       0  5764.2    .035       0  6047.8     .05       0
Bank Sta=4960.3,4965
XS Rating Curve= 0 ,0
Exp/Cntr=0.3,0.1

Type RM Length L Ch R = 1 ,72251   ,410,410,410
BEGIN DESCRIPTION:
X18226
END DESCRIPTION:
XS GIS Cut Line= 4
       2568167.3     13807594.59      2568514.52     13808532.08
      2568626.44     13809229.21      2568938.93     13809528.68
#Sta/Elev= 30
  4060.9  409.94    4104  409.14  4123.1  409.98  4153.5  408.22  4214.3  407.79
  4582.7  396.01  4648.9   392.7  4831.6  389.54  4936.8   389.5  4978.4   388.6
  4992.2  387.23  5008.1  380.26  5008.4  379.76  5012.8  380.26  5017.3  382.82
  5022.6  382.76  5031.8  388.56  5042.3   389.6  5124.4  391.92  5225.7  391.76
  5344.8  389.43  5576.5   388.6  5769.7  388.09    5826   390.1  5854.1  390.69
    5904  388.59  5911.2  389.55  5958.9  389.63  6091.7  390.36  6199.5  390.93
#Mann= 10 ,-1 , 0
  4060.9     .05       0  4831.6      .1       0  5008.1     .05       0
  5012.8      .1       0  5225.7    .035       0  5576.5     .05       0
    5826    .035       0  5854.1    .063       0  5958.9    .035       0
  6091.7     .05       0
Bank Sta=5008.1,5012.8
XS Rating Curve= 0 ,0
Exp/Cntr=0.3,0.1

Type RM Length L Ch R = 1 ,71841   ,429,429,429
BEGIN DESCRIPTION:
X18225
END DESCRIPTION:
XS GIS Cut Line= 5
      2567857.95     13807927.45      2568190.21     13808671.95
      2568489.72     13809001.16       2568643.8     13809355.08
      2568916.93     13809550.17
#Sta/Elev= 30
  4060.4  401.95  4235.8  400.55  4344.9  399.11  4428.2  397.94  4556.1   393.1
    4608  393.07  4655.7  390.31  4706.3  387.78  4799.2  387.57  4835.2  385.69
  4857.1  386.58  4881.1  383.99  4894.2  385.31  4909.3  387.28  4959.3  387.37
  4973.5  384.32  4992.1  377.54  4992.5  377.04  4996.8  377.54  5008.7  382.02
  5030.7  385.54  5043.8   387.8  5118.6  387.38  5477.6  388.03  5646.9  387.92
  5734.6  390.26  5794.2  388.47  5853.3   389.5  5971.9  390.11  6042.4  390.77
#Mann= 14 ,-1 , 0
  4060.4     .07       0  4235.8    .035       0  4344.9     .07       0
  4428.2    .035       0  4655.7      .1       0  4894.2    .035       0
  4992.1    .035       0  4996.8    .035       0  5030.7      .1       0
  5118.6    .035       0  5477.6     .05       0  5734.6    .063       0
  5853.3    .035       0  5971.9     .05       0
Bank Sta=4992.1,4996.8
XS Rating Curve= 0 ,0
Exp/Cntr=0.3,0.1

Type RM Length L Ch R = 1 ,71412   ,570,570,570
BEGIN DESCRIPTION:
X18224
END DESCRIPTION:
XS GIS Cut Line= 3
      2567753.35     13808099.71      2567974.86     13808967.28
      2568866.99     13810419.31
#Sta/Elev= 30
  3917.2  401.69  4001.8  401.05  4104.1  399.08  4717.9  391.49    4837  387.74
  4962.5  386.06    4986  380.42  4990.7  376.62    4991  376.12  4995.5  376.62
    5017  384.15  5134.9  385.32  5456.7  384.34  5502.4  386.44  5524.6  382.02
  5530.5  384.88  5537.6  379.49  5545.9  378.01  5582.6  378.03  5588.5  382.13
  5596.3  378.64  5609.8   378.1  5640.6  381.85  5646.5  378.07  5704.5  387.02
    5939  388.02  5996.4  389.75  6183.8  391.01  6330.8  395.31  6516.8  396.18
#Mann= 13 ,-1 , 0
  3917.2     .07       0  4001.8    .035       0  4104.1     .07       0
  4717.9     .12       0    4837    .035       0  4990.7    .035       0
  4995.5    .035       0    5017      .1       0  5134.9     .05       0
  5456.7     .12       0    5939    .063       0  5996.4    .035       0
  6330.8     .05       0
Bank Sta=4990.7,4995.5
XS Rating Curve= 0 ,0
Exp/Cntr=0.3,0.1

Type RM Length L Ch R = 1 ,70842   ,473,473,473
BEGIN DESCRIPTION:
X18223
END DESCRIPTION:
XS GIS Cut Line= 3
      2567765.66     13808499.71      2567747.21     13809508.73
      2568103.69     13810621.22
#Sta/Elev= 30
  3916.1  396.48  3941.4  396.79  3961.4  396.13  4001.4  397.04  4051.4  395.47
  4091.4  396.38  4121.4  395.16  4171.4  394.75  4231.4  391.92  4286.6   390.6
  4421.5  386.98  4541.5   385.3  4838.6  384.11  4881.6  384.37  4962.7  382.93
  4973.9  383.85  4984.4  382.74  5000.1  379.11  5005.4  375.75  5012.4  374.56
  5012.9  374.06  5019.4  374.56  5037.4  382.54  5047.4  384.08  5082.5  383.53
    5225   383.5  5351.9  384.48  5771.9  390.16  5908.5  393.71  6093.5  400.12
#Mann= 6 ,-1 , 0
  3916.1     .07       0  4286.6    .045       0  4838.6      .1       0
  5012.4     .05       0  5019.4      .1       0  5082.5     .05       0
Bank Sta=5012.4,5019.4
XS Rating Curve= 0 ,0
Exp/Cntr=0.3,0.1

Type RM Length L Ch R = 1 ,70369   ,360,360,360
BEGIN DESCRIPTION:
X18222
END DESCRIPTION:
XS GIS Cut Line= 2
      2567482.63     13808598.15      2567365.73     13810628.59
#Sta/Elev= 30
  3880.3  394.58  3897.2  394.82  3924.2  393.13  4047.4  389.35  4157.6  387.43
  4197.7  387.95  4210.4  387.18  4347.9  385.07    4408  384.56  4450.6  385.45
  4471.3  384.82  4606.4  383.45  4658.4  383.64  4735.1  382.38  4838.7  381.46
  4928.9  383.59  4958.9  381.45  4966.9  379.56    4989  377.44  5005.4  372.87
  5005.9  372.37  5012.6  372.87  5049.1  382.65  5069.5  382.66  5079.1   383.2
  5144.1  382.37  5279.5  384.04  5379.6  383.52  5561.7  384.52  5914.1   386.4
#Mann= 9 ,-1 , 0
  3880.3     .07       0  4210.4     .12       0  4471.3     .07       0
  4606.4     .12       0  4735.1      .1       0  5005.4     .05       0
  5012.6      .1       0  5069.5     .07       0  5561.7     .05       0
Bank Sta=5005.4,5012.6
XS Rating Curve= 0 ,0
Exp/Cntr=0.3,0.1

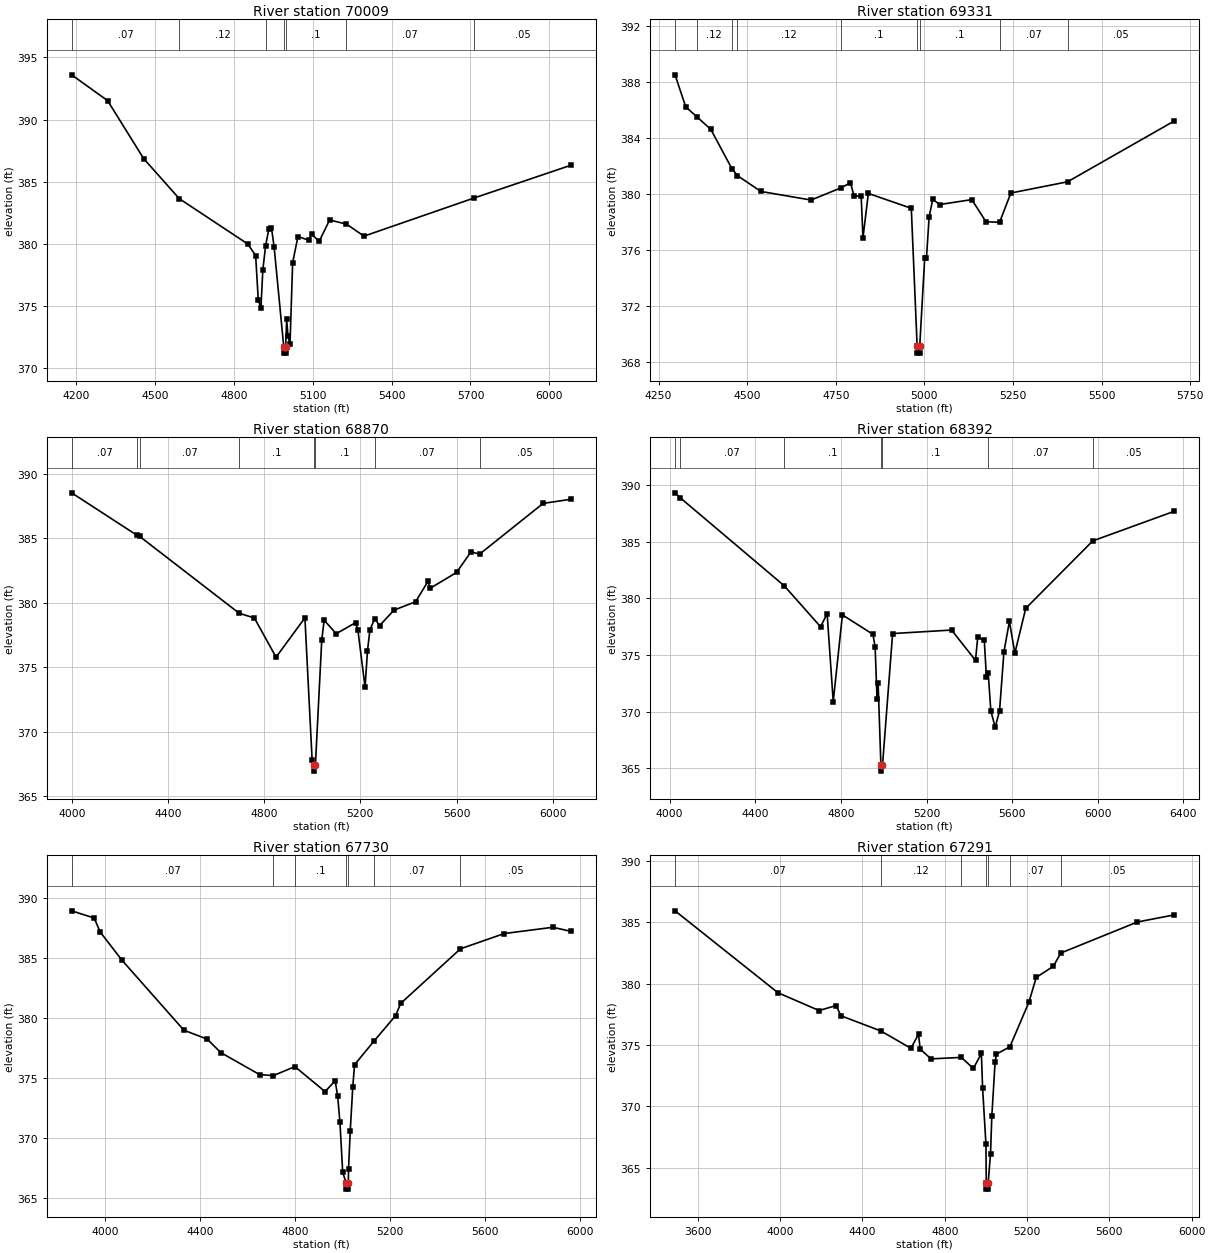
Type RM Length L Ch R = 1 ,70009   ,678,678,678
BEGIN DESCRIPTION:
X18221
END DESCRIPTION:
XS GIS Cut Line= 2
      2567039.63     13808708.88      2567248.82     13810597.73
#Sta/Elev= 30
  4181.9   393.6  4318.9  391.52  4456.2  386.85  4591.6  383.63  4852.1  379.98
  4882.3  379.05  4892.3  375.47  4902.4  374.83  4909.7   377.9  4920.3  379.85
  4932.6  381.19  4942.6  381.27  4952.7  379.72  4989.3  371.69  4989.8  371.19
    4996  371.19  4996.5  371.69  5000.4  373.91  5005.4  372.54  5013.1   371.9
  5023.1  378.47  5043.3  380.58  5083.5  380.29  5096.1  380.77  5123.7  380.18
    5164  381.91  5227.9  381.58  5294.8  380.61  5713.5  383.68  6082.3  386.32
#Mann= 7 ,-1 , 0
  4181.9     .07       0  4591.6     .12       0  4920.3      .1       0
  4989.3     .05       0  4996.5      .1       0  5227.9     .07       0
  5713.5     .05       0
Bank Sta=4989.3,4996.5
XS Rating Curve= 0 ,0
Exp/Cntr=0.3,0.1

Type RM Length L Ch R = 1 ,69331   ,461,461,461
BEGIN DESCRIPTION:
Big Fivemile Creek 81.0
END DESCRIPTION:
XS GIS Cut Line= 3
        2566675.     13809075.01        2566775.       13809775.
        2566825.     13810475.02
#Sta/Elev= 30
  4296.4   388.5  4326.7  386.21  4357.4  385.52  4397.4  384.61  4457.2  381.79
  4472.6  381.31  4538.8  380.18  4680.3  379.57  4763.9  380.43  4791.4   380.8
  4801.5  379.87  4821.7  379.83  4826.7  376.87  4841.9  380.04  4963.1  378.98
  4979.6  369.15  4980.1  368.65  4986.4  368.65  4986.9  369.15    5001  375.47
    5006  375.47  5013.5  378.39  5023.6  379.61  5043.6  379.25  5133.8   379.6
  5173.9  378.02  5212.2  377.98  5244.1  380.07    5404  380.87  5705.3  385.21
#Mann= 9 ,-1 , 0
  4296.4     .07       0  4357.4     .12       0  4457.2     .07       0
  4472.6     .12       0  4763.9      .1       0  4979.6     .05       0
  4986.9      .1       0  5212.2     .07       0    5404     .05       0
Bank Sta=4979.6,4986.9
XS Rating Curve= 0 ,0
Exp/Cntr=0.3,0.1

Type RM Length L Ch R = 1 ,68870   ,478,478,478
BEGIN DESCRIPTION:
X18220
END DESCRIPTION:
XS GIS Cut Line= 3
      2566590.48     13808776.54      2566350.52     13809311.84
      2566399.73      13810800.4
#Sta/Elev= 30
  3999.6  388.54  4271.9  385.24  4282.4  385.16  4696.1   379.2  4759.5  378.83
  4849.5  375.79  4969.6  378.84  4999.6  367.79    5006  367.45  5006.5  366.95
  5013.3  367.45  5039.6  377.13  5049.6  378.66  5099.7  377.61  5180.3  378.47
  5189.7  377.92  5219.7  373.46  5229.7  376.27  5239.7  377.89    5260  378.79
  5279.8  378.23  5339.8  379.44  5429.8  380.09  5481.7  381.69  5489.9  381.13
  5599.9  382.36    5660  383.96  5696.3  383.79  5960.1  387.72  6075.6  388.04
#Mann= 8 ,-1 , 0
  3999.6     .07       0  4271.9     .12       0  4282.4     .07       0
  4696.1      .1       0    5006     .05       0  5013.3      .1       0
    5260     .07       0  5696.3     .05       0
Bank Sta=5006,5013.3
XS Rating Curve= 0 ,0
Exp/Cntr=0.3,0.1

Type RM Length L Ch R = 1 ,68392   ,662,662,662
BEGIN DESCRIPTION:
X18219
END DESCRIPTION:
XS GIS Cut Line= 2
      2565815.23     13808518.14      2566270.26     13810805.62
#Sta/Elev= 30
  4025.1  389.33  4050.2  388.88  4534.9  381.12    4705  377.49  4735.6  378.65
  4764.1  370.87    4807  378.54  4949.7  376.82  4959.9  375.69  4968.6  371.14
  4973.7  372.54  4986.9  365.23  4987.4  364.73  4994.2  365.23  5041.5  376.89
  5316.8   377.2  5428.7  374.52  5439.1  376.57  5469.7  376.29  5479.8  373.01
  5487.9  373.43  5500.3  370.06  5520.7   368.6  5541.1  370.07  5561.5  375.28
  5587.1  377.96  5612.5  375.16  5663.4  379.12  5976.4  385.08  6357.4   387.7
#Mann= 7 ,-1 , 0
  4025.1    .035       0  4050.2     .07       0  4534.9      .1       0
  4986.9     .05       0  4994.2      .1       0  5487.9     .07       0
  5976.4     .05       0
Bank Sta=4986.9,4994.2
XS Rating Curve= 0 ,0
Exp/Cntr=0.3,0.1

Type RM Length L Ch R = 1 ,67730   ,439,439,439
BEGIN DESCRIPTION:
X18218
END DESCRIPTION:
XS GIS Cut Line= 2
      2565458.37     13808899.62      2566165.78     13810880.39
#Sta/Elev= 30
  3857.6  388.91  3952.6  388.31  3978.1  387.14  4070.5  384.78  4330.5  378.97
  4429.4  378.22  4485.7  377.11  4649.1  375.28  4707.2  375.19  4798.1  375.94
  4925.2  373.86  4967.7  374.76  4978.3  373.49  4987.9   371.3  4999.5  367.15
  5014.2  366.24  5014.7  365.74  5022.8  365.74  5023.3  366.24    5024  367.38
  5031.4  370.62    5042  374.28  5049.5   376.1  5131.6  378.07  5222.5  380.19
  5243.7   381.2  5495.7  385.75  5680.3  387.02  5885.2  387.54  5960.9   387.2
#Mann= 7 ,-1 , 0
  3857.6     .07       0  4707.2     .12       0  4798.1      .1       0
  5014.2     .05       0  5023.3      .1       0  5131.6     .07       0
  5495.7     .05       0
Bank Sta=5014.2,5023.3
XS Rating Curve= 0 ,0
Exp/Cntr=0.3,0.1

Type RM Length L Ch R = 1 ,67291   ,638,638,638
BEGIN DESCRIPTION:
X18217
END DESCRIPTION:
XS GIS Cut Line= 3
      2565194.31      13808755.4      2565031.82       13809301.
      2565876.76     13810954.66
#Sta/Elev= 30
  3489.5  385.93  3989.9  379.25  4189.5   377.8  4272.8  378.21    4295  377.38
  4490.4  376.13    4636  374.72  4672.7  375.87  4680.9  374.65  4733.8  373.86
  4880.5  373.98  4939.4  373.08  4978.2   374.3  4984.1   371.5  5000.4   366.9
    5002  363.74  5002.5  363.24  5010.7  363.24  5011.2  363.74  5022.6  366.12
    5029   369.2  5044.8  373.57  5051.5  374.25  5116.9  374.85  5208.7  378.46
  5244.8   380.5  5328.1  381.41  5364.3  382.49  5736.5  385.02  5915.8   385.6
#Mann= 7 ,-1 , 0
  3489.5     .07       0  4490.4     .12       0  4880.5      .1       0
    5002     .05       0  5011.2      .1       0  5116.9     .07       0
  5364.3     .05       0
Bank Sta=5002,5011.2
XS Rating Curve= 0 ,0
Exp/Cntr=0.3,0.1