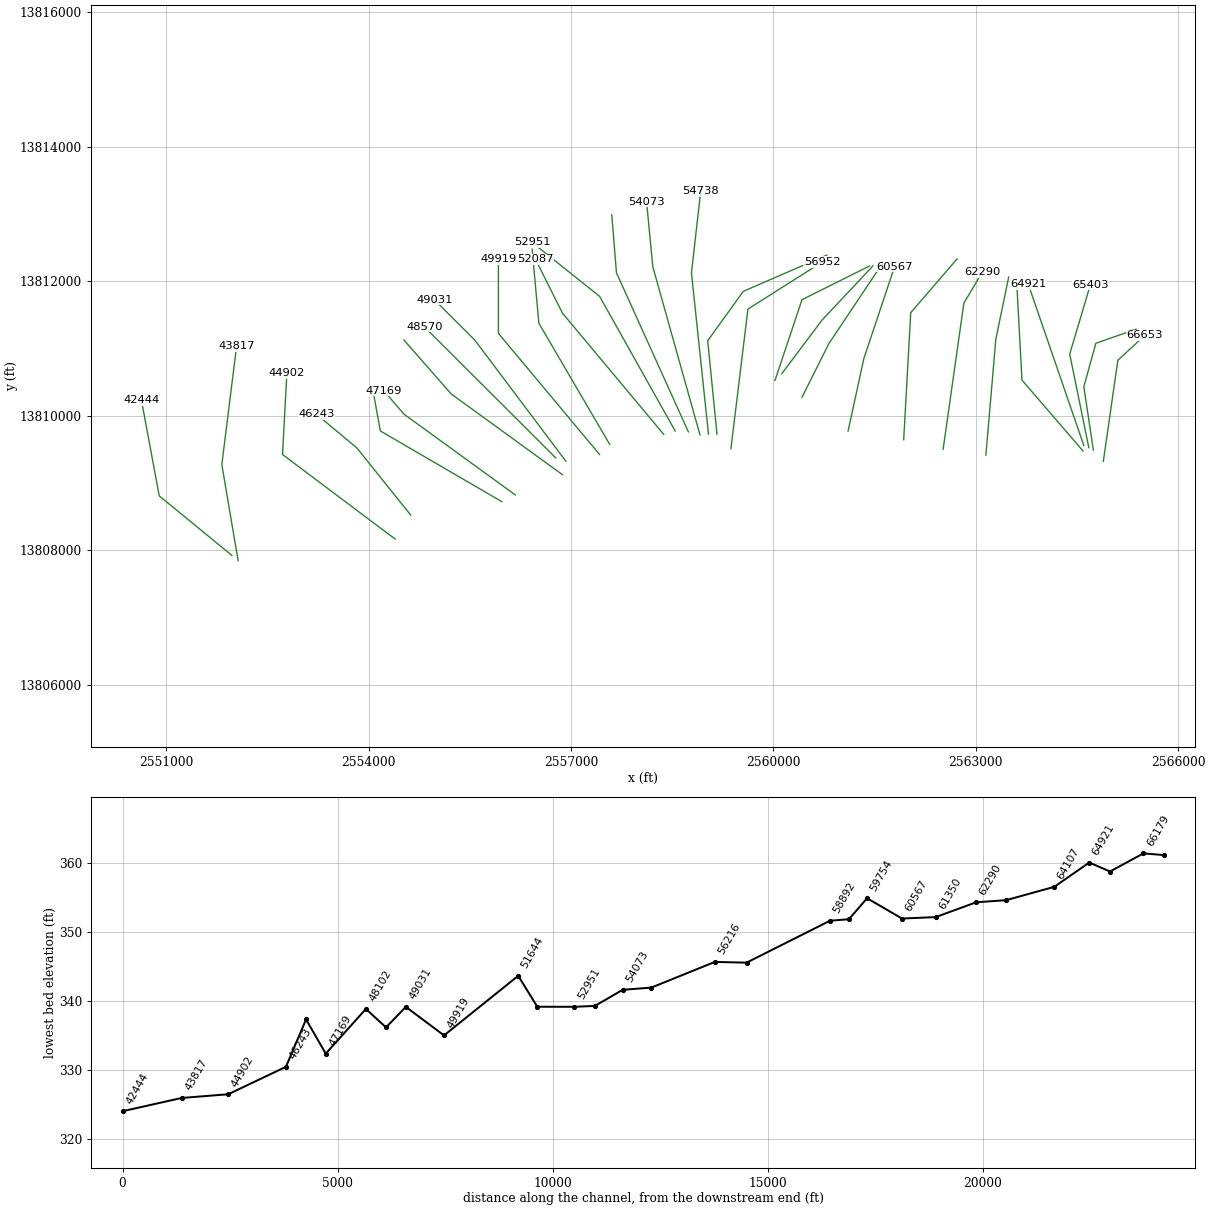
HEC-RAS study Big Fivemile Creek.prj: Big Fivemile Creek Base Level Engineering

--- Big Fivemile Creek.g01 (geometry) --- (continued)

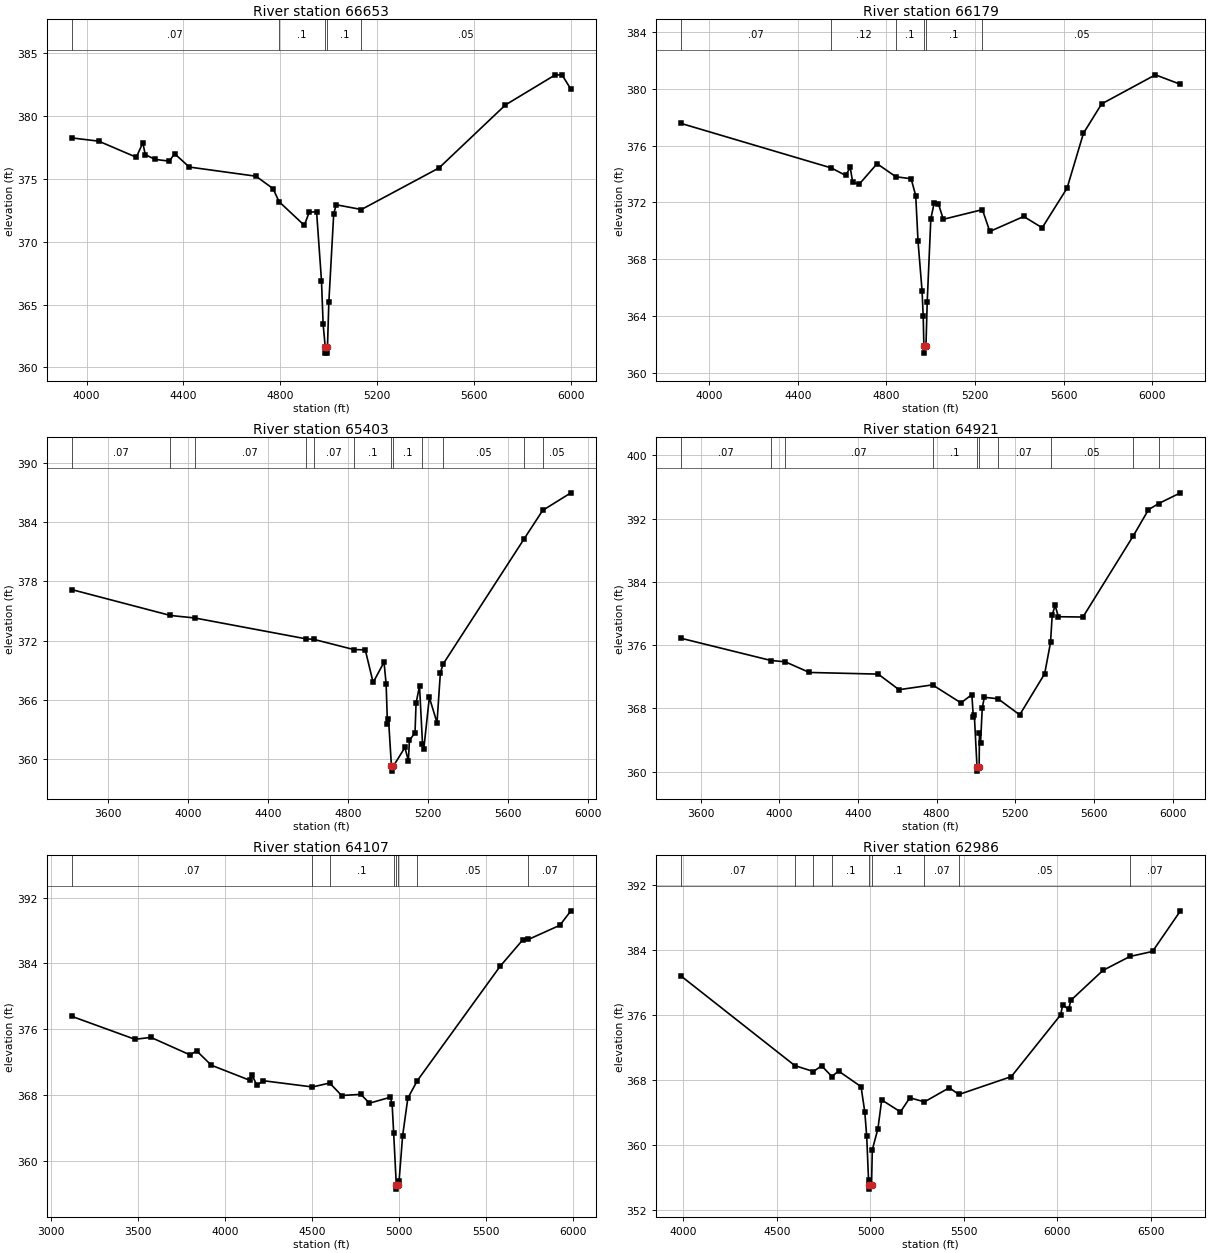
Type RM Length L Ch R = 1 ,66653   ,474,474,474
BEGIN DESCRIPTION:
X18216
END DESCRIPTION:
XS GIS Cut Line= 3
      2564892.31     13809324.19      2565107.65     13810825.43
       2565507.6     13811194.61
#Sta/Elev= 30
  3938.4  378.26  4050.3     378  4205.4  376.72  4232.2  377.87  4242.3  376.93
  4282.7  376.55  4341.5  376.41  4363.5     377  4424.1  375.94  4699.4  375.21
    4770  374.22  4794.3  373.19  4898.9   371.3  4919.1  372.35  4949.5  372.38
  4969.7   366.9  4976.6  363.41  4985.2  361.63  4985.7  361.13    4994  361.13
  4994.5  361.63    5000  365.16  5020.2  372.21  5030.3  372.94  5134.6  372.56
    5455  375.87  5728.8  380.88    5934  383.27  5962.4  383.28  5999.3  382.13
#Mann= 5 ,-1 , 0
  3938.4     .07       0  4794.3      .1       0  4985.2     .05       0
  4994.5      .1       0  5134.6     .05       0
Bank Sta=4985.2,4994.5
XS Rating Curve= 0 ,0
Exp/Cntr=0.3,0.1

Type RM Length L Ch R = 1 ,66179   ,776,776,776
BEGIN DESCRIPTION:
X18215
END DESCRIPTION:
XS GIS Cut Line= 4
      2564744.64     13809490.25      2564603.12     13810431.65
      2564781.55      13811077.7      2565378.34     13811286.88
#Sta/Elev= 30
  3873.2  377.57  4551.6  374.43  4616.2   373.9  4636.4  374.47    4648  373.42
  4676.9  373.28  4757.8  374.73  4842.9  373.81  4911.6  373.67  4932.4  372.48
  4942.8  369.25    4961  365.77  4966.2  363.97  4969.2  361.87  4969.7  361.37
  4978.6  361.87  4984.3     365  5000.6  370.85  5015.4  371.93  5034.9   371.9
  5056.9  370.81  5233.5  371.49  5266.9  369.95    5420  371.01  5503.4  370.21
  5615.6     373  5689.8  376.88  5771.9  378.95  6014.7     381  6127.8  380.33
#Mann= 6 ,-1 , 0
  3873.2     .07       0  4551.6     .12       0  4842.9      .1       0
  4969.2     .05       0  4978.6      .1       0  5233.5     .05       0
Bank Sta=4969.2,4978.6
XS Rating Curve= 0 ,0
Exp/Cntr=0.3,0.1

Type RM Length L Ch R = 1 ,65403   ,482,482,482
BEGIN DESCRIPTION:
X18214
END DESCRIPTION:
XS GIS Cut Line= 3
      2564676.96     13809527.16      2564393.92     13810917.72
      2564701.35     13811950.67
#Sta/Elev= 30
  3416.5  377.18  3910.6  374.55  4031.5   374.3  4588.1  372.18  4626.6  372.13
  4827.3  371.09  4884.9  371.06  4924.2  367.75  4978.8  369.81  4989.2   367.6
  4995.8  363.55    5001  364.07  5015.8  359.25  5016.3  358.75  5025.2  359.25
  5083.1  361.15  5100.5   359.8  5105.7  361.87  5133.7  362.65  5138.9  365.65
  5156.2  367.38  5171.1  361.54  5177.3  360.96  5205.3  366.23  5243.7  363.67
  5260.5  368.74  5274.6  369.63  5679.4  382.33  5772.2  385.22  5913.3     387
#Mann= 12 ,-1 , 0
  3416.5     .07       0  3910.6     .12       0  4031.5     .07       0
  4588.1      .1       0  4626.6     .07       0  4827.3      .1       0
  5015.8     .05       0  5025.2      .1       0  5171.1     .07       0
  5274.6     .05       0  5679.4     .07       0  5772.2     .05       0
Bank Sta=5015.8,5025.2
XS Rating Curve= 0 ,0
Exp/Cntr=0.3,0.1

Type RM Length L Ch R = 1 ,64921   ,814,814,814
BEGIN DESCRIPTION:
X18213
END DESCRIPTION:
XS GIS Cut Line= 2
      2564603.11     13809557.97      2563778.63     13811957.58
#Sta/Elev= 30
  3501.6  376.85  3958.6  374.04  4030.2  373.88  4153.1  372.53    4503  372.32
  4608.7  370.35  4779.1  370.96  4923.7  368.68  4978.8  369.73  4986.2  366.95
  4991.5  367.09  5005.1  360.55  5005.6  360.05  5015.9  360.55  5017.5  364.91
  5022.8  363.55  5031.7  368.02  5042.2  369.39  5111.9   369.2    5222  367.17
  5348.9  372.37  5378.6  376.32  5387.2  379.78  5401.7  381.04  5418.4  379.58
  5543.4  379.54    5800  389.84  5876.5  393.12  5928.6   393.9  6038.9  395.25
#Mann= 10 ,-1 , 0
  3501.6     .07       0  3958.6     .12       0  4030.2     .07       0
  4779.1      .1       0  5005.1     .05       0  5015.9      .1       0
  5111.9     .07       0  5378.6     .05       0    5800     .07       0
  5928.6     .05       0
Bank Sta=5005.1,5015.9
XS Rating Curve= 0 ,0
Exp/Cntr=0.3,0.1

Type RM Length L Ch R = 1 ,64107   ,1121,1121,1121
BEGIN DESCRIPTION:
X18212
END DESCRIPTION:
XS GIS Cut Line= 3
      2564590.81     13809477.96      2563686.35      13810530.1
      2563606.44     13812011.49
#Sta/Elev= 30
  3117.8  377.56  3481.9  374.76    3574  374.99  3800.1  372.85  3836.3  373.36
  3920.8  371.61  4141.4  369.78  4155.6   370.4  4183.1  369.16  4219.3  369.72
  4502.6  368.96  4601.6  369.44  4670.4  367.92  4780.6  368.06  4830.6  366.99
  4950.8  367.71  4960.8  366.85  4969.6  363.35  4984.7  357.03  4985.2  356.53
  4995.6  357.03  5000.9  357.57  5020.9  362.98    5051   367.6  5105.7  369.73
  5581.7  383.64  5711.9  386.86  5744.6  386.91    5925  388.63  5988.8  390.39
#Mann= 8 ,-1 , 0
  3117.8     .07       0  4502.6     .12       0  4601.6      .1       0
  4969.6     .07       0  4984.7     .05       0  4995.6     .07       0
  5105.7     .05       0  5744.6     .07       0
Bank Sta=4984.7,4995.6
XS Rating Curve= 0 ,0
Exp/Cntr=0.3,0.1

Type RM Length L Ch R = 1 ,62986   ,696,696,696
BEGIN DESCRIPTION:
X18211
END DESCRIPTION:
XS GIS Cut Line= 3
      2563151.06     13809416.44      2563298.72     13811139.23
      2563489.23     13812061.04
#Sta/Elev= 30
  3987.6  380.77  4595.9  369.77  4694.9  369.05  4738.9  369.75  4793.9  368.43
  4829.2  369.11  4949.7  367.19  4969.7  364.08  4979.8  361.16  4989.8  355.71
    4994   355.1  4994.5   354.6  5005.8   355.1  5009.9  359.43    5040  362.03
  5060.1  365.56  5160.4  364.09  5210.6  365.82  5288.9  365.32  5421.4  367.05
  5473.1  366.23  5753.2  368.42  6016.5  375.99  6028.9  377.25  6059.6  376.67
  6071.9   377.8  6243.4  381.47  6387.3  383.18  6508.7   383.8    6658  388.79
#Mann= 9 ,-1 , 0
  3987.6     .07       0  4595.9     .12       0  4694.9     .07       0
  4793.9      .1       0    4994     .05       0  5005.8      .1       0
  5288.9     .07       0  5473.1     .05       0  6387.3     .07       0
Bank Sta=4994,5005.8
XS Rating Curve= 0 ,0
Exp/Cntr=0.3,0.1

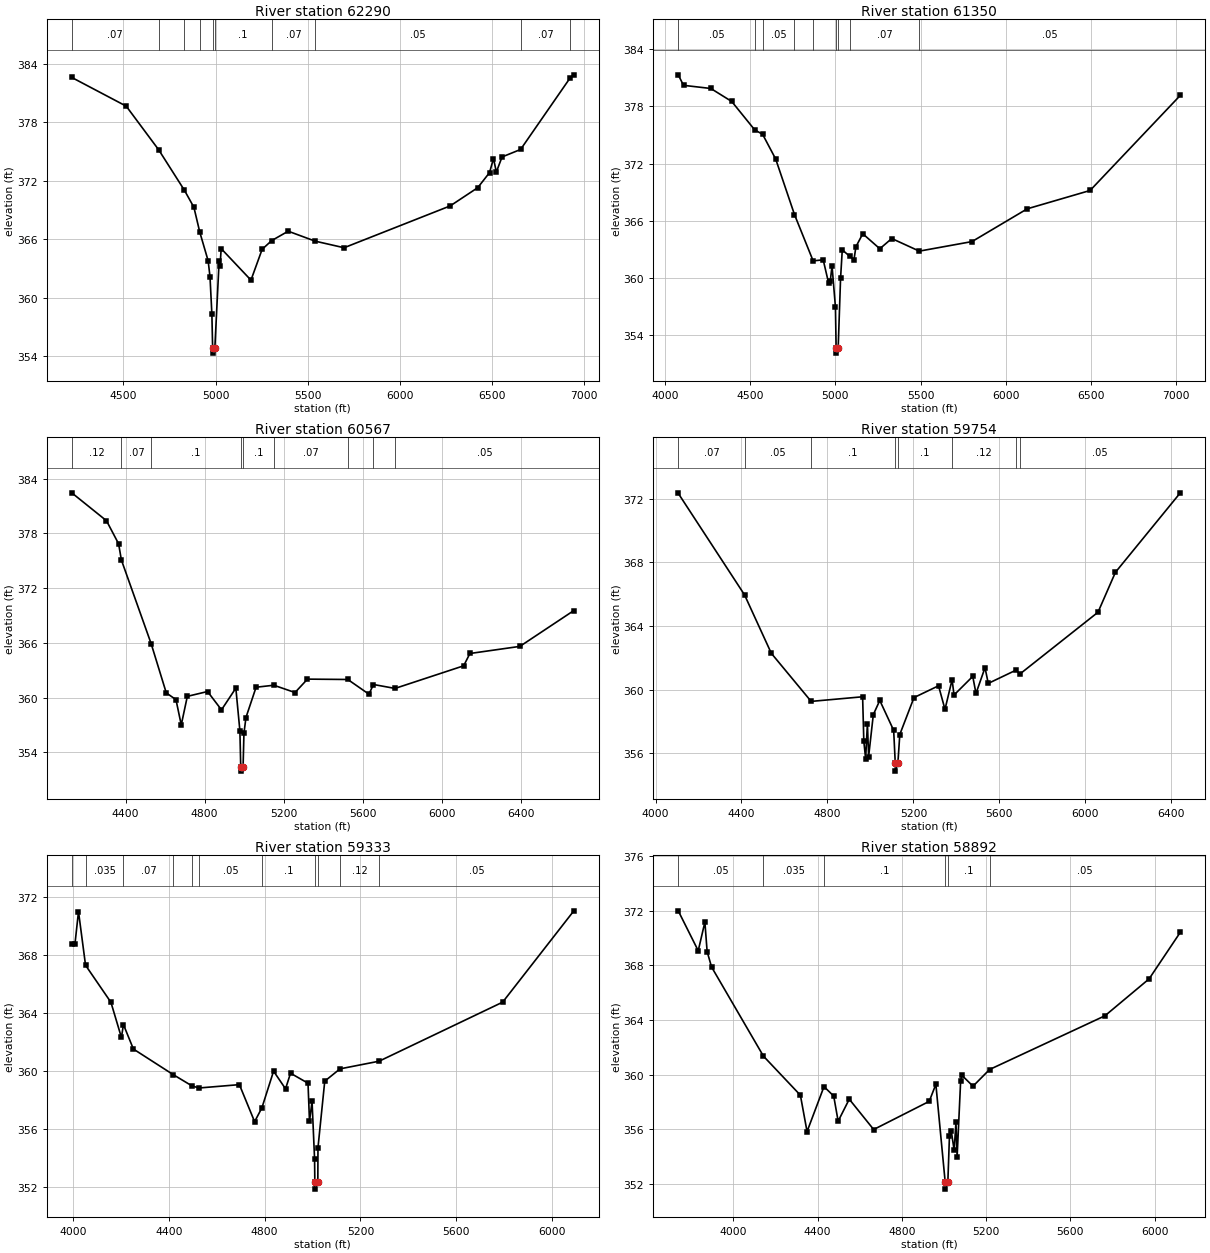
Type RM Length L Ch R = 1 ,62290   ,940,940,940
BEGIN DESCRIPTION:
X18210
END DESCRIPTION:
XS GIS Cut Line= 3
      2562517.31     13809502.57      2562824.96     13811674.52
      2563095.66     13812129.79
#Sta/Elev= 30
    4220  382.62  4515.4  379.67  4691.6  375.18  4830.9  371.03  4882.4  369.28
  4914.4  366.72  4959.7  363.78  4969.8  362.14  4979.9  358.33  4984.1  354.79
  4984.6  354.29    4996  354.79  5019.4   363.8  5024.4  363.29  5030.4  365.03
    5192  361.79  5252.6  364.96    5304  365.85    5394  366.82  5539.7   365.8
    5697  365.12  6272.7  369.42  6421.8  371.29    6486  372.84  6507.4  374.29
    6523   372.9  6553.8  374.45  6654.4  375.22  6924.1   382.6  6943.3  382.89
#Mann= 10 ,-1 , 0
    4220     .07       0  4691.6     .05       0  4830.9     .12       0
  4914.4      .1       0  4984.1     .05       0    4996      .1       0
    5304     .07       0  5539.7     .05       0  6654.4     .07       0
  6924.1     .05       0
Bank Sta=4984.1,4996
XS Rating Curve= 0 ,0
Exp/Cntr=0.3,0.1

Type RM Length L Ch R = 1 ,61350   ,783,783,783
BEGIN DESCRIPTION:
X18209
END DESCRIPTION:
XS GIS Cut Line= 3
       2561932.8     13809644.08       2562037.4     13811533.01
      2562725.28     13812331.44
#Sta/Elev= 30
  4078.2  381.29  4109.2  380.19  4269.4  379.86    4392   378.5  4526.7  375.53
  4573.3  375.06    4650  372.47  4760.2  366.66  4869.6  361.81  4928.7  361.92
  4960.5  359.48  4970.5  359.75  4980.5  361.29  5000.5  356.96  5004.6  352.65
  5005.1  352.15  5016.5  352.65  5030.6  359.98  5040.6  362.96    5085  362.28
  5109.2  361.92  5120.7  363.29  5160.8  364.65  5260.9  363.08    5331  364.15
  5492.6  362.83  5801.8  363.83  6125.8  367.26  6494.5  369.18  7023.9  379.14
#Mann= 9 ,-1 , 0
  4078.2     .05       0  4526.7     .07       0  4573.3     .05       0
  4760.2    .035       0  4869.6      .1       0  5004.6     .05       0
  5016.5      .1       0    5085     .07       0  5492.6     .05       0
Bank Sta=5004.6,5016.5
XS Rating Curve= 0 ,0
Exp/Cntr=0.3,0.1

Type RM Length L Ch R = 1 ,60567   ,813,813,813
BEGIN DESCRIPTION:
X18208
END DESCRIPTION:
XS GIS Cut Line= 3
      2561108.32     13809773.29      2561342.13     13810850.04
      2561797.45     13812216.01
#Sta/Elev= 30
  4127.7  382.46  4303.4   379.4  4364.8  376.87  4378.8   375.1  4530.1  365.88
  4606.1  360.52  4655.2  359.78    4682  357.01  4712.7  360.14  4815.1  360.67
  4885.6  358.66  4958.3  361.04  4978.8  356.36    4983  352.44  4983.5  351.94
    4995  352.44  4999.3  356.08  5009.5  357.82  5060.7  361.14  5150.6  361.36
  5257.8  360.56    5321  362.03  5525.1  361.99    5632  360.38    5655  361.44
  5764.1  361.01  6111.6  363.49  6143.2  364.84  6396.2  365.62  6669.4  369.55
#Mann= 9 ,-1 , 0
  4127.7     .12       0  4378.8     .07       0  4530.1      .1       0
    4983     .05       0    4995      .1       0  5150.6     .07       0
  5525.1      .1       0    5655     .07       0  5764.1     .05       0
Bank Sta=4983,4995
XS Rating Curve= 0 ,0
Exp/Cntr=0.3,0.1

Type RM Length L Ch R = 1 ,59754   ,421,421,421
BEGIN DESCRIPTION:
Big Fivemile Creek 66.0
END DESCRIPTION:
XS GIS Cut Line= 3
      2560425.01     13810275.01        2560825.       13811075.
      2561624.98     13812274.97
#Sta/Elev= 30
  4105.6  372.33  4414.2  365.95  4538.8  362.28  4724.2  359.26  4963.7  359.55
  4969.3  356.75  4977.7  355.66    4986  357.87  4991.6  355.79  5013.5  358.43
  5043.6  359.32  5108.2  357.44  5115.6  355.38  5116.1  354.88  5127.8  355.38
  5136.7  357.18  5202.8   359.5    5317  360.24    5347  358.76  5380.1  360.62
  5389.1  359.66  5476.2  360.83  5491.3  359.76  5533.3  361.38  5548.4  360.39
  5678.6  361.23  5694.8  360.97  6059.1  364.86  6140.3  367.37  6442.2  372.36
#Mann= 8 ,-1 , 0
  4105.6     .07       0  4414.2     .05       0  4724.2      .1       0
  5115.6     .05       0  5127.8      .1       0  5380.1     .12       0
  5678.6     .07       0  5694.8     .05       0
Bank Sta=5115.6,5127.8
XS Rating Curve= 0 ,0
Exp/Cntr=0.3,0.1

Type RM Length L Ch R = 1 ,59333   ,441,441,441
BEGIN DESCRIPTION:
Big Fivemile Creek 65.0
END DESCRIPTION:
XS GIS Cut Line= 3
        2560125.       13810625.        2560725.       13811425.
      2561475.01     13812225.01
#Sta/Elev= 30
  3994.8  368.77  4008.3  368.81  4022.9  371.02  4052.3  367.31  4158.3  364.75
  4202.1  362.32  4210.6  363.21  4252.1  361.52  4418.6  359.75  4498.1  358.96
  4527.1  358.83  4694.8  359.06  4758.3   356.5  4788.8  357.46  4837.5  359.99
  4887.5  358.77  4908.3  359.85  4981.3  359.16  4987.5  356.53  4998.2   357.9
  5008.7  353.93  5009.8  352.34  5010.3  351.84  5022.3  352.34  5022.9   354.7
  5051.2   359.3  5114.9  360.15  5278.2  360.68  5794.2  364.76  6091.4  371.07
#Mann= 11 ,-1 , 0
  3994.8     .05       0  4052.3    .035       0  4210.6     .07       0
  4418.6     .05       0  4498.1     .07       0  4527.1     .05       0
  4788.8      .1       0  5009.8     .05       0  5022.3      .1       0
  5114.9     .12       0  5278.2     .05       0
Bank Sta=5009.8,5022.3
XS Rating Curve= 0 ,0
Exp/Cntr=0.3,0.1

Type RM Length L Ch R = 1 ,58892   ,1940,1940,1940
BEGIN DESCRIPTION:
Big Fivemile Creek 64.0
END DESCRIPTION:
XS GIS Cut Line= 3
      2560024.99     13810524.96        2560425.       13811725.
      2561425.01     13812225.01
#Sta/Elev= 30
  3738.9  371.98  3833.8  369.06  3865.4  371.16    3876     369  3897.1  367.87
  4143.3  361.35  4318.7  358.49  4350.3  355.83  4430.7  359.12  4476.8  358.43
  4497.9  356.59  4550.6   358.2  4666.5  355.98  4930.1  358.04  4961.7  359.29
    5006  352.12  5006.5  351.62  5018.5  352.12  5026.2  355.52  5034.6  355.89
  5048.6  354.46    5057   356.5  5062.6     354  5079.3  359.54  5084.9  359.95
    5138  359.15  5216.5  360.37  5764.1   364.3  5973.7     367  6121.9  370.41
#Mann= 6 ,-1 , 0
  3738.9     .05       0  4143.3    .035       0  4430.7      .1       0
    5006     .05       0  5018.5      .1       0  5216.5     .05       0
Bank Sta=5006,5018.5
XS Rating Curve= 0 ,0
Exp/Cntr=0.3,0.1

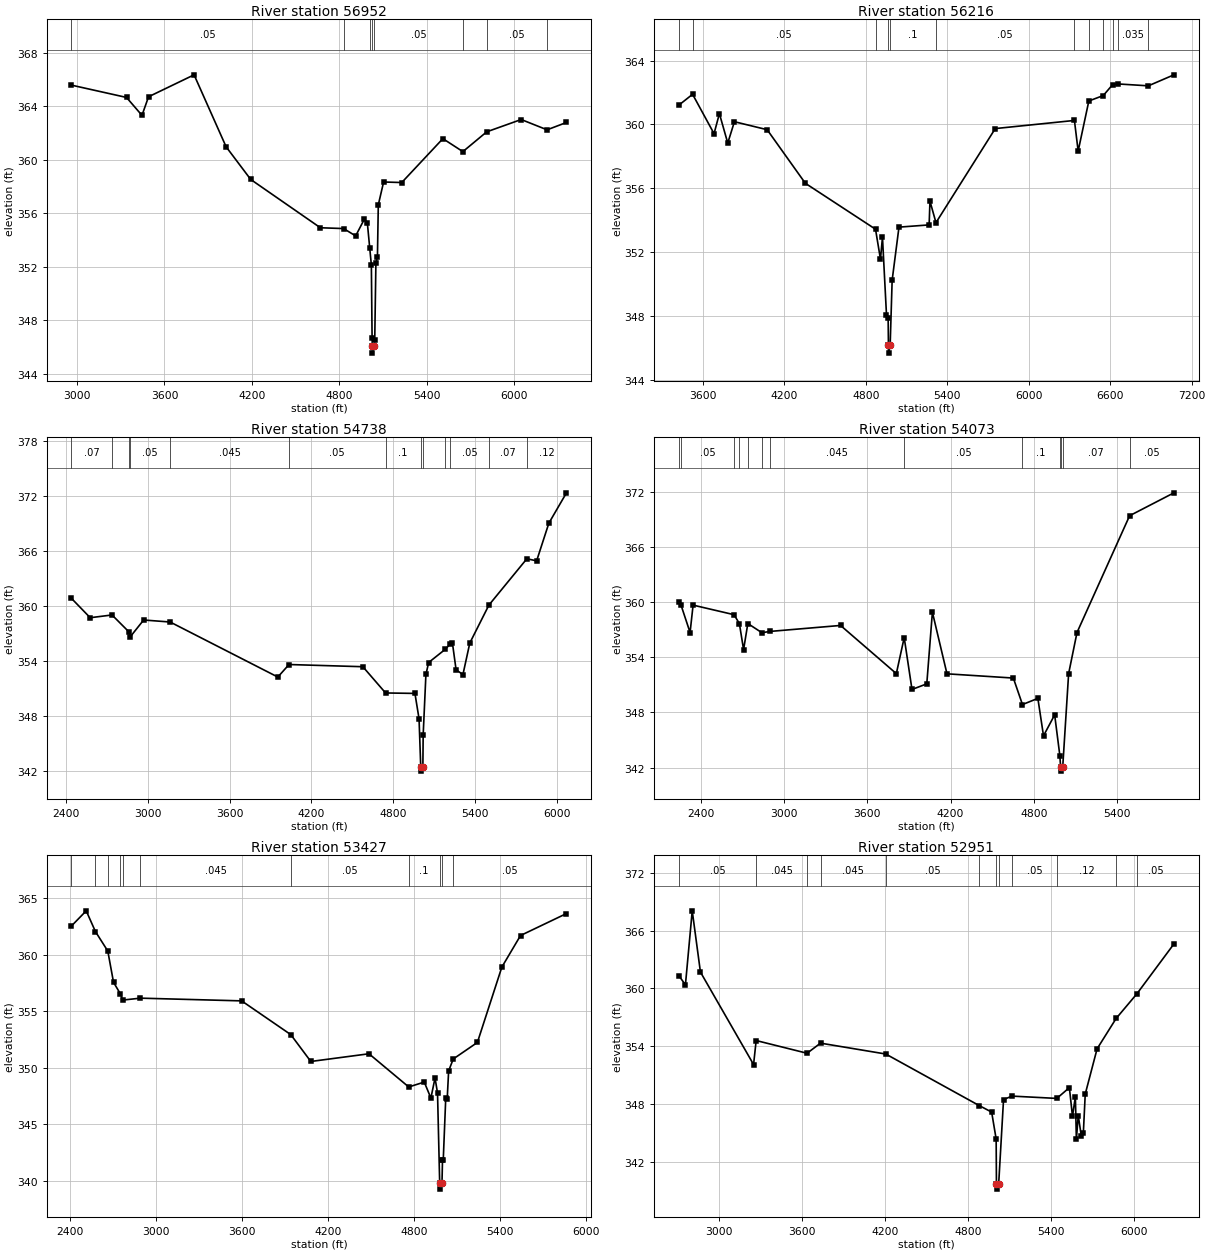
Type RM Length L Ch R = 1 ,56952   ,736,736,736
BEGIN DESCRIPTION:
Big Fivemile Creek 63.0
END DESCRIPTION:
XS GIS Cut Line= 3
      2559371.58     13809509.95      2559623.86     13811585.52
      2560724.68       13812285.
#Sta/Elev= 30
    2962  365.58  3339.8  364.66  3445.9  363.32  3490.9  364.71  3803.2  366.35
    4023  360.97  4191.6  358.53  4669.5  354.92  4828.8  354.86  4911.3  354.31
  4971.7  355.58  4991.9  355.24  5007.9  353.39    5019  352.14    5024  346.68
  5025.9  346.05  5026.4  345.55  5038.5  346.05  5042.2  346.56  5050.1  352.26
  5060.7  352.77  5066.6  356.63    5103  358.34  5227.5   358.3  5509.5  361.58
  5646.7  360.61  5810.1  362.09  6046.5  363.01  6224.1  362.24  6357.1  362.79
#Mann= 8 ,-1 , 0
    2962     .05       0  4828.8      .1       0  5007.9     .05       0
  5025.9     .05       0  5038.5     .05       0  5646.7    .035       0
  5810.1     .05       0  6224.1    .035       0
Bank Sta=5025.9,5038.5
XS Rating Curve= 0 ,0
Exp/Cntr=0.3,0.1

Type RM Length L Ch R = 1 ,56216   ,1478,1478,1478
BEGIN DESCRIPTION:
X18207
END DESCRIPTION:
XS GIS Cut Line= 4
      2559165.17     13809727.84      2559027.56     13811115.37
      2559555.06     13811849.27      2560791.78     13812387.47
#Sta/Elev= 30
    3422  361.21  3523.1  361.89  3681.2  359.42  3720.6  360.68  3782.2  358.83
  3831.2  360.17  4072.3  359.67  4353.7  356.31  4870.7  353.43  4907.2  351.55
  4921.9  352.93  4951.4  348.08  4963.7  347.88  4965.9  346.16  4966.4  345.66
  4978.6  346.16  4993.2  350.23  5043.5  353.56  5265.7   353.7  5271.8  355.19
    5316  353.84  5752.8  359.74    6336  360.25  6363.5  358.33  6442.1  361.47
  6548.3  361.81  6616.9  362.49  6654.4  362.54  6880.4  362.42  7068.9  363.11
#Mann= 12 ,-1 , 0
    3422     .07       0  3523.1     .05       0  4870.7      .1       0
  4965.9     .05       0  4978.6      .1       0    5316     .05       0
    6336    .035       0  6442.1     .12       0  6548.3    .035       0
  6616.9     .12       0  6654.4    .035       0  6880.4     .07       0
Bank Sta=4965.9,4978.6
XS Rating Curve= 0 ,0
Exp/Cntr=0.3,0.1

Type RM Length L Ch R = 1 ,54738   ,665,665,665
BEGIN DESCRIPTION:
X18206
END DESCRIPTION:
XS GIS Cut Line= 3
      2559039.03     13809727.85      2558786.75     13812124.49
      2558924.36     13813340.04
#Sta/Elev= 30
  2438.7  360.84  2576.6  358.72  2736.8  359.02  2858.1  357.21  2870.9  356.64
  2968.8  358.47  3163.2  358.25  3953.5  352.23  4035.6   353.6  4577.6  353.36
  4744.3  350.49  4959.8  350.44    4990  347.66  5002.3  342.44  5002.8  341.94
    5018  342.44  5020.2  345.89  5040.3  352.51  5060.4  353.82  5182.8  355.27
  5217.2  355.82  5234.8  355.97  5261.7  353.03    5312   352.5  5362.4  355.95
  5502.6   360.1  5781.3  365.17  5852.9  364.94  5942.6  369.06  6071.9  372.38
#Mann= 13 ,-1 , 0
  2438.7     .07       0  2736.8     .05       0  2858.1     .12       0
  2870.9     .05       0  3163.2    .045       0  4035.6     .05       0
  4744.3      .1       0  5002.3     .05       0    5018      .1       0
  5182.8     .07       0  5217.2     .05       0  5502.6     .07       0
  5781.3     .12       0
Bank Sta=5002.3,5018
XS Rating Curve= 0 ,0
Exp/Cntr=0.3,0.1

Type RM Length L Ch R = 1 ,54073   ,646,646,646
BEGIN DESCRIPTION:
Big Fivemile Creek 62.0
END DESCRIPTION:
XS GIS Cut Line= 3
      2558912.89     13809716.38      2558213.39     13812216.22
      2558121.65      13813179.5
#Sta/Elev= 30
  2244.2  360.02  2258.5  359.73  2324.9  356.69  2346.6  359.67  2641.3  358.63
  2679.9  357.66  2710.1  354.83  2740.6  357.67    2842  356.67  2900.1  356.81
  3408.2  357.46  3809.6  352.22  3866.2  356.14  3922.3   350.5  4028.8  351.11
  4069.2   358.9  4174.2   352.2  4651.9  351.74  4717.5  348.86  4828.4  349.53
    4869  345.46  4949.3  347.74  4986.7   343.3  4991.7  342.12  4992.2  341.62
  5007.5  342.12  5049.8  352.22  5110.1  356.69  5488.8  369.39  5807.7  371.88
#Mann= 13 ,-1 , 0
  2244.2     .07       0  2258.5     .05       0  2641.3     .12       0
  2679.9     .05       0  2740.6     .12       0    2842     .05       0
  2900.1    .045       0  3866.2     .05       0  4717.5      .1       0
  4986.7     .07       0  4991.7     .05       0  5007.5     .07       0
  5488.8     .05       0
Bank Sta=4991.7,5007.5
XS Rating Curve= 0 ,0
Exp/Cntr=0.3,0.1

Type RM Length L Ch R = 1 ,53427   ,476,476,476
BEGIN DESCRIPTION:
Big Fivemile Creek 61.0
END DESCRIPTION:
XS GIS Cut Line= 3
      2558740.87     13809762.26        2557675.       13812125.
      2557605.62     13812984.58
#Sta/Elev= 30
  2408.2  362.52  2511.5  363.86  2575.7  362.03    2662  360.31    2702  357.55
  2750.3  356.52    2766  355.98  2889.8  356.15    3596  355.91    3939  352.93
  4078.7  350.56  4484.6  351.24  4761.9  348.31  4870.3  348.74  4916.5  347.33
  4945.4   349.1  4962.8  347.78    4978  339.79  4978.5  339.29  4993.9  339.79
  4997.5  341.84  5002.7  341.84  5020.3  347.36  5030.3  347.25  5040.4  349.73
  5072.5  350.78    5241  352.24  5411.6  358.89    5542  361.68  5862.6  363.62
#Mann= 11 ,-1 , 0
  2408.2     .05       0  2575.7     .12       0    2662     .05       0
  2750.3     .12       0    2766     .05       0  2889.8    .045       0
    3939     .05       0  4761.9      .1       0    4978     .05       0
  4993.9      .1       0  5072.5     .05       0
Bank Sta=4978,4993.9
XS Rating Curve= 0 ,0
Exp/Cntr=0.3,0.1

Type RM Length L Ch R = 1 ,52951   ,864,864,864
BEGIN DESCRIPTION:
Big Fivemile Creek 60.0
END DESCRIPTION:
XS GIS Cut Line= 3
      2558545.96     13809773.67        2557425.       13811775.
        2556425.       13812575.
#Sta/Elev= 30
  2712.3  361.33  2759.7  360.37  2808.8  368.06  2868.1   361.7  3251.7   352.1
  3270.5  354.59  3638.1  353.27  3735.1  354.32  4206.3  353.19  4880.5  347.84
  4970.8  347.16  5003.3  344.36  5005.4  339.66  5005.9  339.16  5021.3  339.66
  5056.6  348.46  5117.4  348.82  5441.1  348.58    5532   349.7  5554.4  346.72
  5575.3  348.77  5582.5  344.35  5596.1   346.8  5618.5  344.65  5632.9     345
  5646.5  349.03  5732.1  353.73  5869.4  356.88  6019.8  359.45  6286.8  364.62
#Mann= 12 ,-1 , 0
  2712.3     .05       0  3270.5    .045       0  3638.1     .07       0
  3735.1    .045       0  4206.3     .05       0  4880.5      .1       0
  5005.4     .05       0  5021.3      .1       0  5117.4     .05       0
  5441.1     .12       0  5869.4     .07       0  6019.8     .05       0
Bank Sta=5005.4,5021.3
XS Rating Curve= 0 ,0
Exp/Cntr=0.3,0.1

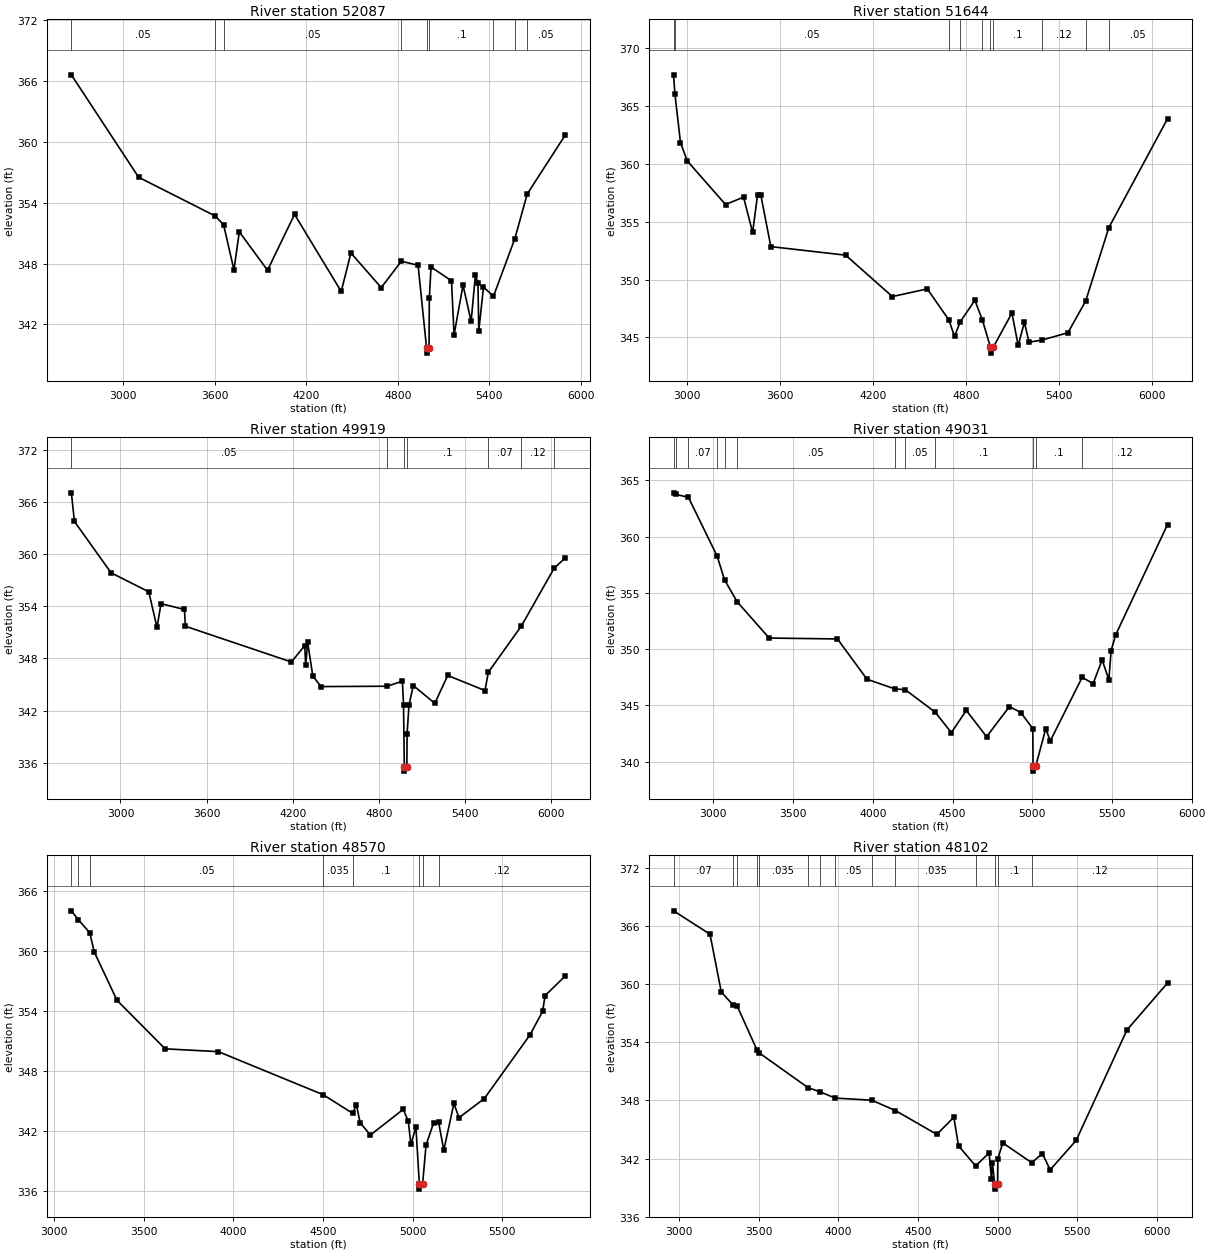
Type RM Length L Ch R = 1 ,52087   ,443,443,443
BEGIN DESCRIPTION:
Big Fivemile Creek 59.0
END DESCRIPTION:
XS GIS Cut Line= 3
      2558375.02     13809724.98        2556875.       13811525.
      2556475.01     13812324.97
#Sta/Elev= 30
    2661  366.61  3101.7  356.51  3601.8  352.71  3658.6  351.83  3726.5  347.38
  3761.6  351.13  3946.5  347.34  4123.5  352.85  4429.4  345.25  4493.2  349.04
  4691.7  345.63  4823.8  348.23  4933.2  347.83  4988.9  339.67  4989.4  339.17
  5004.9  339.67  5006.9   344.6  5018.1  347.66  5152.2   346.3    5169  340.96
  5227.7  345.88  5280.8   342.3  5308.8  346.84  5325.5  346.11  5331.1  341.37
  5361.9  345.68  5427.4  344.78  5567.2  350.45  5648.5  354.86  5898.5  360.69
#Mann= 9 ,-1 , 0
    2661     .05       0  3601.8     .07       0  3658.6     .05       0
  4823.8      .1       0  4988.9     .05       0  5004.9      .1       0
  5427.4     .12       0  5567.2     .07       0  5648.5     .05       0
Bank Sta=4988.9,5004.9
XS Rating Curve= 0 ,0
Exp/Cntr=0.3,0.1

Type RM Length L Ch R = 1 ,51644   ,1725,1725,1725
BEGIN DESCRIPTION:
Big Fivemile Creek 58.0
END DESCRIPTION:
XS GIS Cut Line= 3
      2557575.02     13809574.96        2556525.       13811375.
        2556425.     13812474.95
#Sta/Elev= 30
  2911.9  367.66  2921.2  365.98    2957  361.82    3000  360.24  3247.7  356.47
  3363.9  357.11  3422.6  354.06    3454  357.27  3475.5  357.28    3540  352.84
  4023.3   352.1  4324.3  348.53  4549.7  349.19  4688.8  346.52  4725.8  345.09
  4761.1  346.32  4856.9  348.21    4906  346.49  4957.7  344.15  4958.2  343.65
  4975.3  344.15  5096.2  347.11  5136.4  344.31  5176.6  346.31  5206.7   344.6
  5287.9  344.77  5457.7  345.41  5572.3  348.15  5721.6  354.48  6100.3  363.87
#Mann= 10 ,-1 , 0
  2911.9     .12       0  2921.2     .05       0  4688.8      .1       0
  4761.1     .05       0    4906      .1       0  4957.7     .05       0
  4975.3      .1       0  5287.9     .12       0  5572.3     .07       0
  5721.6     .05       0
Bank Sta=4957.7,4975.3
XS Rating Curve= 0 ,0
Exp/Cntr=0.3,0.1

Type RM Length L Ch R = 1 ,49919   ,888,888,888
BEGIN DESCRIPTION:
Big Fivemile Creek 57.0
END DESCRIPTION:
XS GIS Cut Line= 3
      2557424.98     13809425.03        2555925.       13811225.
        2555925.     13812324.96
#Sta/Elev= 30
  2657.6  367.08    2679  363.78  2934.2  357.87  3197.1  355.68  3254.4  351.57
  3282.4  354.31  3445.7  353.64  3452.3  351.71  4191.6  347.59    4284  349.49
  4290.6  347.21  4304.9  349.85    4340  345.99  4397.3  344.76    4859   344.8
  4964.8  345.39  4972.7  342.59  4978.2  335.52  4978.7  335.02  4995.8  335.52
  4997.4  339.31  5010.6  342.62  5040.6  344.88  5190.6  342.83  5280.6  346.04
  5540.6   344.3  5563.3   346.4  5794.3  351.75  6022.2  358.39  6100.6  359.59
#Mann= 7 ,-1 , 0
  2657.6     .05       0    4859      .1       0  4978.2     .05       0
  4995.8      .1       0  5563.3     .07       0  5794.3     .12       0
  6022.2     .07       0
Bank Sta=4978.2,4995.8
XS Rating Curve= 0 ,0
Exp/Cntr=0.3,0.1

Type RM Length L Ch R = 1 ,49031   ,461,461,461
BEGIN DESCRIPTION:
Big Fivemile Creek 56.0
END DESCRIPTION:
XS GIS Cut Line= 3
      2556925.02     13809324.97        2555575.       13811125.
      2554974.98     13811725.02
#Sta/Elev= 30
  2749.9  363.89    2766  363.75  2843.4  363.49  3023.9  358.25  3070.1  356.15
  3148.9  354.21  3349.9  350.98  3778.1   350.9  3963.5  347.32  4137.9  346.46
  4203.6  346.39    4392  344.38  4492.6  342.57  4586.4  344.55  4713.5  342.21
  4857.2  344.89  4928.1  344.36  5003.5  342.93  5005.2  339.65  5005.7  339.15
    5023  339.65  5084.8  342.93  5113.1  341.83  5313.3  347.49  5381.8  346.93
  5438.3  349.04  5480.8  347.28  5494.9  349.87  5523.2  351.26  5848.5  361.07
#Mann= 12 ,-1 , 0
  2749.9    .035       0    2766     .05       0  2843.4     .07       0
  3023.9     .05       0  3070.1     .07       0  3148.9     .05       0
  4137.9    .035       0  4203.6     .05       0    4392      .1       0
  5005.2     .05       0    5023      .1       0  5313.3     .12       0
Bank Sta=5005.2,5023
XS Rating Curve= 0 ,0
Exp/Cntr=0.3,0.1

Type RM Length L Ch R = 1 ,48570   ,468,468,468
BEGIN DESCRIPTION:
Big Fivemile Creek 55.0
END DESCRIPTION:
XS GIS Cut Line= 3
      2556775.01     13809374.99        2555425.       13810725.
      2554825.03     13811324.97
#Sta/Elev= 30
  3095.6  364.03  3134.5  363.14  3198.3  361.84  3222.9  359.93  3350.2  355.08
  3618.9  350.22  3915.9  349.94  4501.2  345.63  4666.4  343.76  4686.6  344.61
  4707.8  342.83  4764.4  341.59  4948.2  344.16  4976.5  342.97  4990.7  340.66
    5019  342.38  5038.2  336.68  5038.7  336.18  5056.2  336.68  5075.5  340.58
  5117.9  342.82  5145.8  342.88  5174.5  340.07  5231.1  344.75  5259.4  343.33
  5400.8  345.24  5655.3   351.6  5726.1  353.96  5740.2  355.55  5853.3  357.52
#Mann= 8 ,-1 , 0
  3095.6     .07       0  3134.5    .035       0  3198.3     .05       0
  4501.2    .035       0  4666.4      .1       0  5038.2     .05       0
  5056.2      .1       0  5145.8     .12       0
Bank Sta=5038.2,5056.2
XS Rating Curve= 0 ,0
Exp/Cntr=0.3,0.1

Type RM Length L Ch R = 1 ,48102   ,933,933,933
BEGIN DESCRIPTION:
Big Fivemile Creek 54.0
END DESCRIPTION:
XS GIS Cut Line= 3
      2556875.03     13809124.98        2555225.       13810325.
      2554524.98     13811125.02
#Sta/Elev= 30
  2964.1  367.58  3193.3  365.17  3264.4  359.19  3339.1  357.85  3363.9  357.76
  3488.2  353.22  3500.2  352.94  3808.8  349.33  3885.9  348.89  3978.8  348.25
  4209.3  348.03  4358.4  346.96  4618.3   344.5    4725  346.27  4754.4  343.32
    4862  341.24  4946.8  342.59  4961.5   339.9  4967.7  341.52  4981.8  339.35
  4982.3  338.85  4999.8  339.35  5001.3  341.96  5032.4  343.62  5214.3  341.58
    5281  342.52  5330.4  340.85  5493.6  343.88  5812.5  355.28  6067.4  360.13
#Mann= 14 ,-1 , 0
  2964.1     .07       0  3339.1    .035       0  3363.9     .05       0
  3488.2     .07       0  3500.2    .035       0  3808.8     .05       0
  3885.9    .035       0  3978.8     .05       0  4209.3     .07       0
  4358.4    .035       0    4862      .1       0  4981.8     .05       0
  4999.8      .1       0  5214.3     .12       0
Bank Sta=4981.8,4999.8
XS Rating Curve= 0 ,0
Exp/Cntr=0.3,0.1

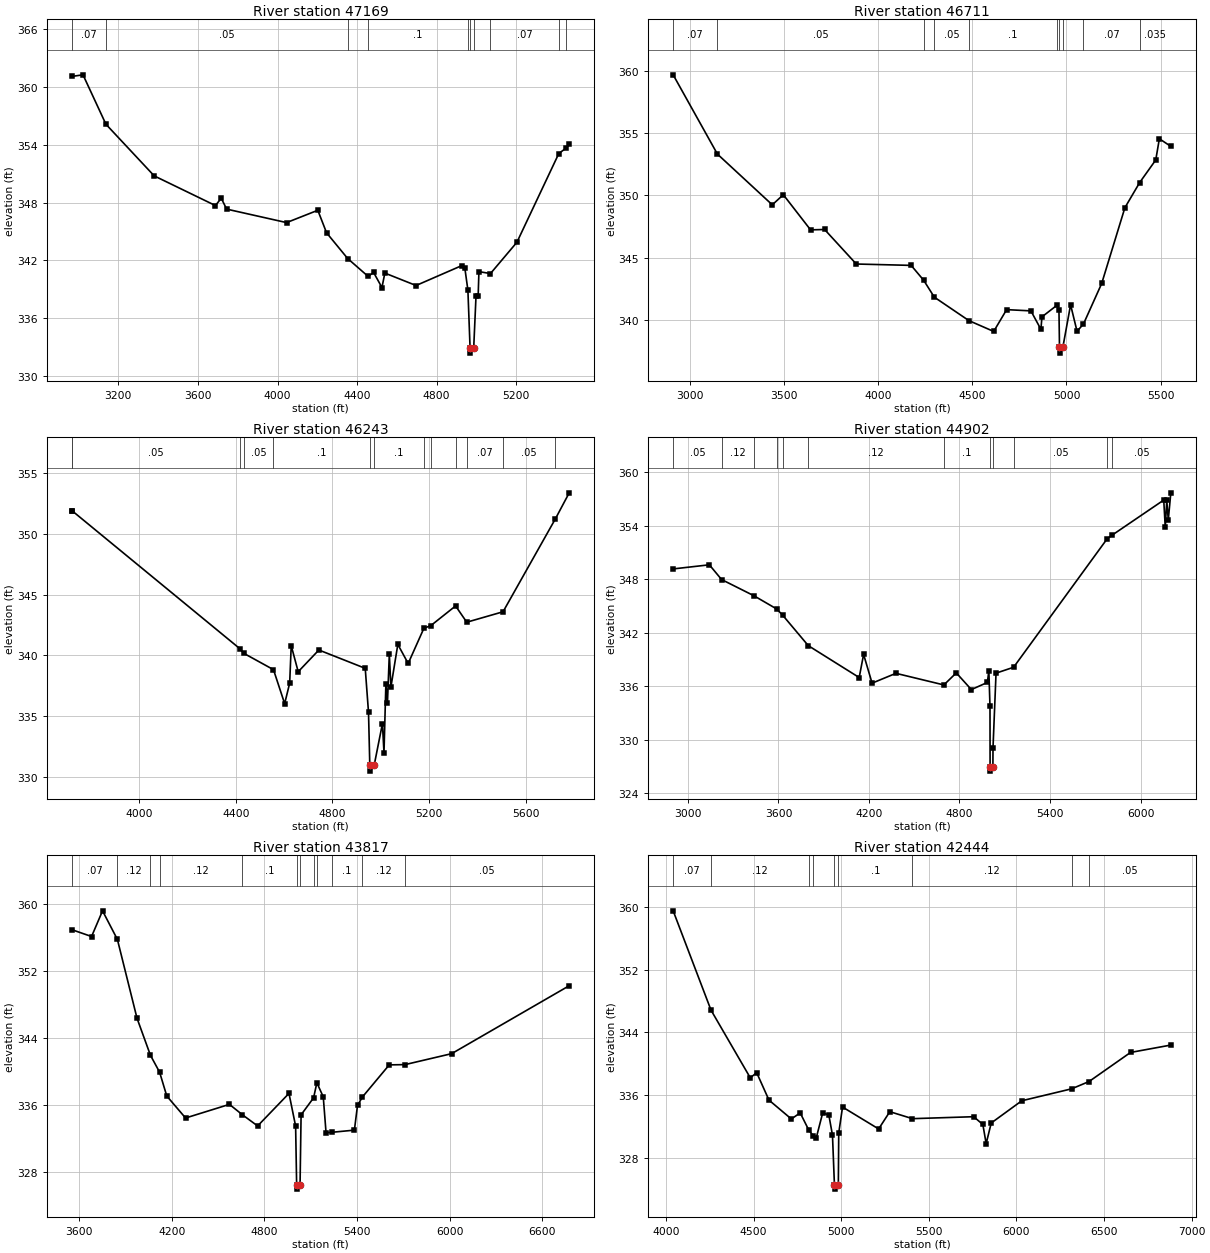
Type RM Length L Ch R = 1 ,47169   ,458,458,458
BEGIN DESCRIPTION:
Big Fivemile Creek 53.0
END DESCRIPTION:
XS GIS Cut Line= 3
      2556175.03     13808824.98        2554525.       13810025.
      2554225.02     13810374.97
#Sta/Elev= 30
  2964.9   361.1  3022.5  361.27  3137.7  356.14  3380.3  350.78  3687.9   347.7
  3717.3  348.46  3744.3  347.33  4045.7  345.93  4202.6  347.21  4246.6  344.87
  4352.7   342.2  4455.2  340.35  4483.1  340.75  4524.9  339.19  4539.5  340.69
  4696.4   339.4  4926.7  341.47  4941.4  341.23  4956.9  338.92  4967.9  332.88
  4968.4  332.38    4986  332.88  4997.8  338.35  5008.5  338.33  5012.3  340.84
  5070.3  340.64  5203.3  343.89  5413.8   353.1  5450.1  353.66  5466.1  354.04
#Mann= 10 ,-1 , 0
  2964.9     .07       0  3137.7     .05       0  4352.7    .035       0
  4455.2      .1       0  4956.9     .12       0  4967.9     .05       0
    4986     .12       0  5070.3     .07       0  5413.8    .035       0
  5450.1     .07       0
Bank Sta=4967.9,4986
XS Rating Curve= 0 ,0
Exp/Cntr=0.3,0.1

Type RM Length L Ch R = 1 ,46711   ,468,468,468
BEGIN DESCRIPTION:
Big Fivemile Creek 52.0
END DESCRIPTION:
XS GIS Cut Line= 3
      2555974.97     13808725.02        2554175.       13809775.
      2554075.01     13810324.96
#Sta/Elev= 30
  2911.5  359.66  3146.5   353.3  3437.8  349.23  3496.5  350.04  3641.2  347.22
  3715.7  347.25  3883.9  344.48  4175.4  344.37  4241.6  343.18  4298.4  341.82
  4481.8  339.94  4613.7  339.07  4682.3  340.82  4811.3  340.72  4864.3  339.24
    4870  340.24  4948.7  341.16  4960.2   340.8  4963.1  337.83  4963.6  337.33
  4981.3  337.83    5022  341.21  5056.3  339.08  5090.5  339.67  5187.2  342.92
  5310.4     349    5389  351.02  5474.3  352.83  5493.4  354.53  5554.3  353.92
#Mann= 10 ,-1 , 0
  2911.5     .07       0  3146.5     .05       0  4241.6    .035       0
  4298.4     .05       0  4481.8      .1       0  4948.7     .12       0
  4963.1     .05       0  4981.3     .12       0  5090.5     .07       0
    5389    .035       0
Bank Sta=4963.1,4981.3
XS Rating Curve= 0 ,0
Exp/Cntr=0.3,0.1

Type RM Length L Ch R = 1 ,46243   ,1341,1341,1341
BEGIN DESCRIPTION:
Big Fivemile Creek 51.0
END DESCRIPTION:
XS GIS Cut Line= 3
        2554625.       13808525.        2553825.       13809525.
      2553225.04     13810024.97
#Sta/Elev= 30
  3719.4  351.91  3722.3  351.91  4416.5  340.56  4432.6  340.18  4555.9  338.83
  4602.2  336.03    4623  337.72  4629.4  340.81  4658.3  338.66  4743.9  340.45
    4936  338.94  4949.6  335.31  4954.9  330.97  4955.4  330.47  4973.2  330.97
  5007.2  334.38  5013.7  331.99  5021.5  337.64    5028  336.07  5035.8  340.11
  5042.3  337.39    5071  340.91  5113.9  339.34    5179  342.24  5207.8  342.46
  5310.3  344.08  5356.6  342.74  5506.9   343.6  5724.1  351.27    5781   353.4
#Mann= 13 ,-1 , 0
  3719.4    .035       0  3722.3     .05       0  4416.5    .035       0
  4432.6     .05       0  4555.9      .1       0  4954.9     .05       0
  4973.2      .1       0    5179     .12       0  5207.8     .07       0
  5310.3     .12       0  5356.6     .07       0  5506.9     .05       0
  5724.1     .07       0
Bank Sta=4954.9,4973.2
XS Rating Curve= 0 ,0
Exp/Cntr=0.3,0.1

Type RM Length L Ch R = 1 ,44902   ,1085,1085,1085
BEGIN DESCRIPTION:
Big Fivemile Creek 48.0
END DESCRIPTION:
XS GIS Cut Line= 3
      2554394.82     13808168.26        2552725.       13809425.
      2552789.28     13810631.88
#Sta/Elev= 30
  2902.2  349.14    3142   349.6  3223.3  347.95  3437.1  346.14  3587.9  344.66
    3628  343.96  3797.8  340.55  4135.2  336.98  4164.4  339.57  4220.6  336.35
  4378.8  337.45  4696.4  336.15  4778.7   337.5  4878.6  335.63  4984.8  336.43
  4994.6  337.74  5002.1  333.75  5002.8     327  5003.3   326.5  5021.4     327
  5022.1  329.11  5042.2  337.47  5158.7  338.13    5779  352.52  5810.5  352.91
  6153.8  356.85  6163.8   353.8  6173.8  356.82  6183.8  354.63  6200.7  357.66
#Mann= 12 ,-1 , 0
  2902.2     .05       0  3223.3     .12       0  3437.1     .05       0
  3587.9     .12       0    3628    .035       0  3797.8     .12       0
  4696.4      .1       0  5002.8     .05       0  5021.4      .1       0
  5158.7     .05       0    5779     .07       0  5810.5     .05       0
Bank Sta=5002.8,5021.4
XS Rating Curve= 0 ,0
Exp/Cntr=0.3,0.1

Type RM Length L Ch R = 1 ,43817   ,1373,1373,1373
BEGIN DESCRIPTION:
Big Fivemile Creek 47.0
END DESCRIPTION:
XS GIS Cut Line= 3
      2552066.94     13807847.23        2551825.       13809275.
      2552044.01      13811035.1
#Sta/Elev= 30
  3551.8  356.98  3681.4  356.15  3752.4  359.22  3848.6   355.8  3975.5  346.39
  4062.4  341.96    4122  339.93  4168.2  337.09  4289.9  334.46  4573.9  336.09
  4657.7  334.85  4756.5  333.51  4959.4   337.4  5002.4  333.49    5009  326.46
  5009.5  325.96  5031.1  326.46  5037.8  334.84  5118.7  336.87  5139.9  338.67
  5181.3  336.99  5199.4   332.7  5235.8  332.75  5382.9  333.01    5403  335.96
  5434.8  336.97  5608.5  340.81  5710.4  340.84  6012.5  342.15  6773.6  350.27
#Mann= 12 ,-1 , 0
  3551.8     .07       0  3848.6     .12       0  4062.4     .07       0
    4122     .12       0  4657.7      .1       0    5009     .05       0
  5031.1      .1       0  5118.7     .12       0  5139.9    .035       0
  5235.8      .1       0  5434.8     .12       0  5710.4     .05       0
Bank Sta=5009,5031.1
XS Rating Curve= 0 ,0
Exp/Cntr=0.3,0.1

Type RM Length L Ch R = 1 ,42444   ,1352,1352,1352
BEGIN DESCRIPTION:
Big Fivemile Creek 46.0
END DESCRIPTION:
XS GIS Cut Line= 3
      2551975.03     13807924.97      2550897.28     13808810.45
      2550633.76     13810231.16
#Sta/Elev= 30
  4041.3  359.47  4257.2  346.83  4481.4  338.21  4517.8  338.87  4588.1  335.37
  4715.8  332.97  4766.1  333.75  4816.2  331.51  4840.7  330.84  4857.9  330.57
  4894.5  333.74  4929.6  333.48  4950.4  330.91  4961.6  324.54  4962.1  324.04
  4983.8  324.54  4986.1  331.18  5007.8  334.49  5213.8   331.7  5277.6   333.9
  5406.7  333.01  5756.1  333.26  5808.5  332.27  5827.3  329.83  5856.3  332.46
  6030.7  335.29  6315.1  336.81  6414.6  337.74  6651.1  341.44  6881.1  342.38
#Mann= 9 ,-1 , 0
  4041.3     .07       0  4257.2     .12       0  4816.2     .07       0
  4840.7      .1       0  4961.6     .05       0  4983.8      .1       0
  5406.7     .12       0  6315.1     .07       0  6414.6     .05       0
Bank Sta=4961.6,4983.8
XS Rating Curve= 0 ,0
Exp/Cntr=0.3,0.1