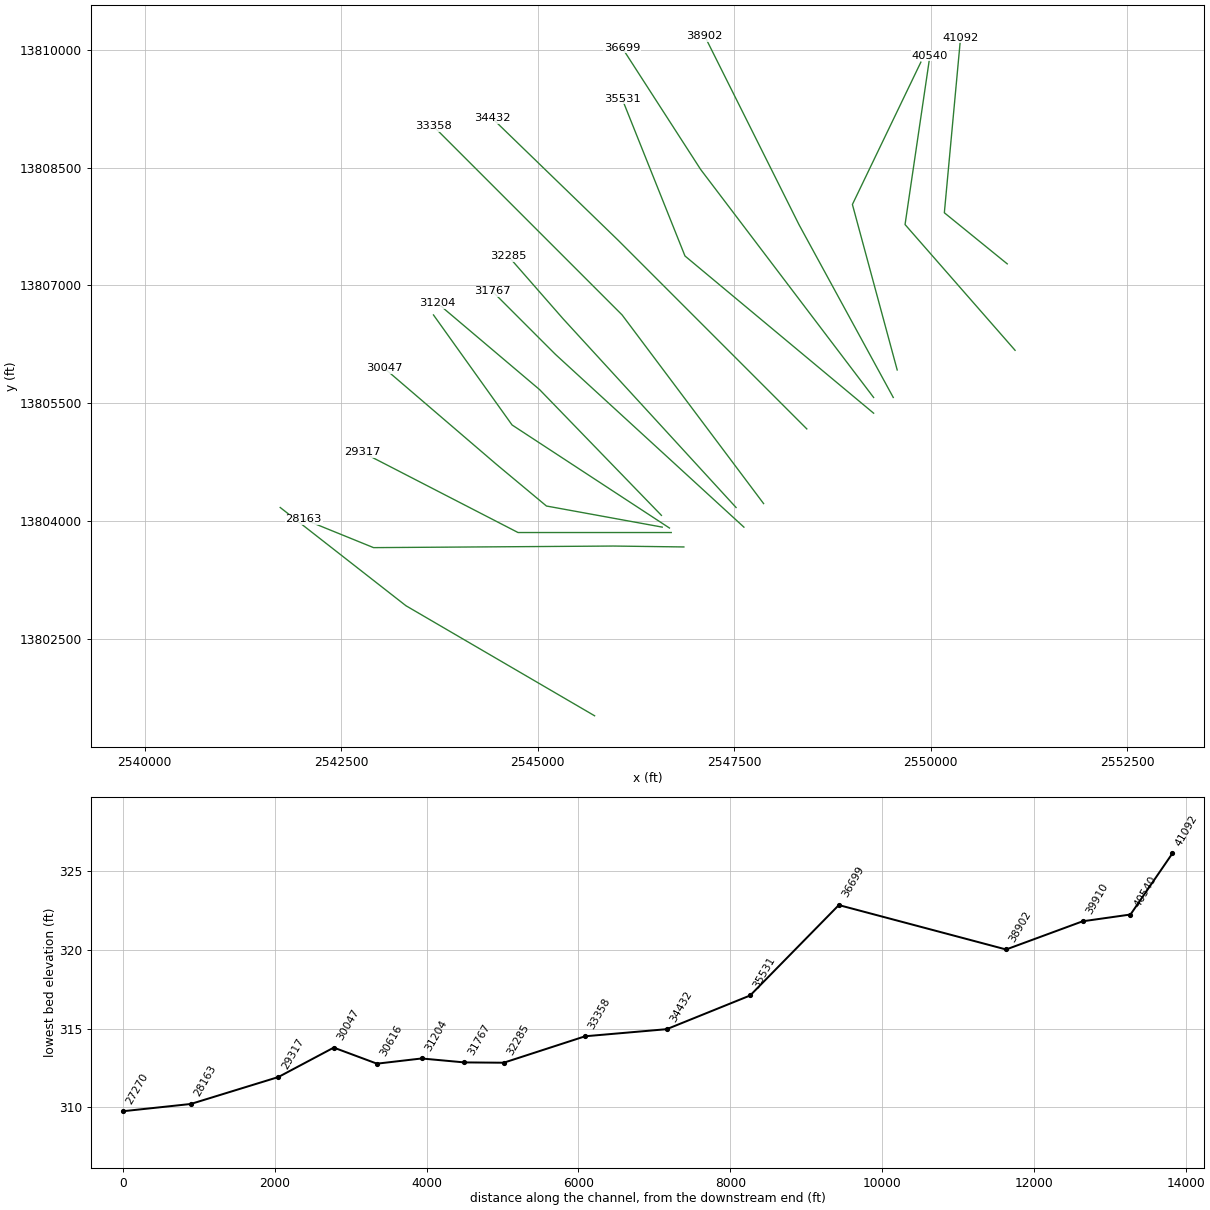
HEC-RAS study Big Fivemile Creek.prj: Big Fivemile Creek Base Level Engineering

--- Big Fivemile Creek.g01 (geometry) --- (continued)

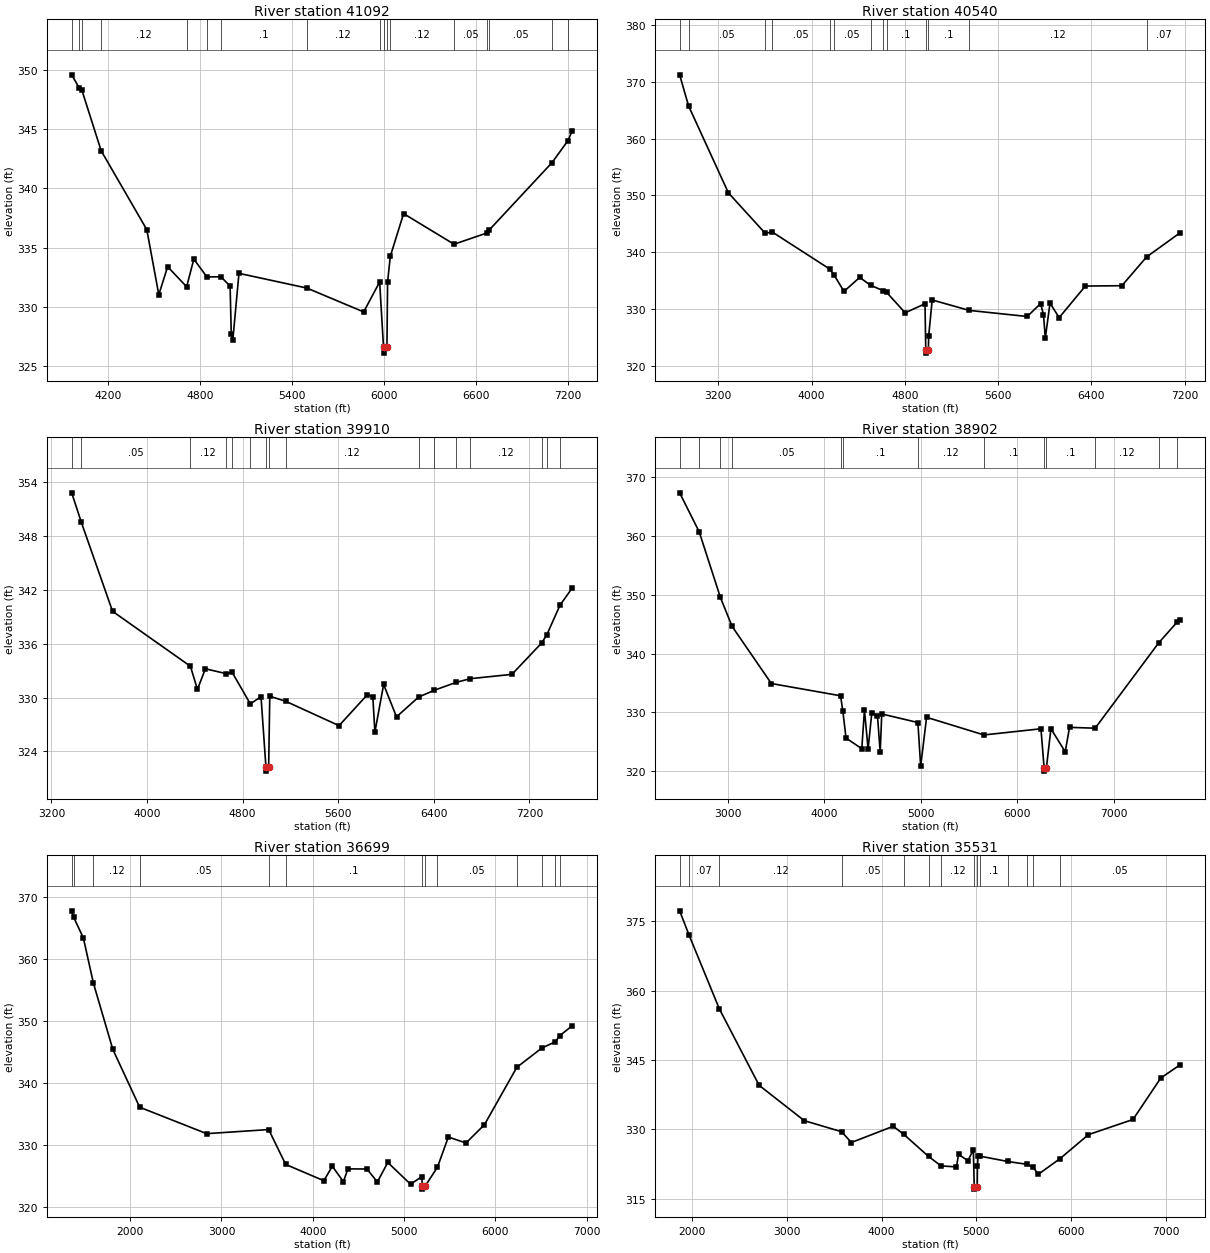
Type RM Length L Ch R = 1 ,41092   ,552,552,552
BEGIN DESCRIPTION:
Big Fivemile Creek 45.0
END DESCRIPTION:
XS GIS Cut Line= 3
      2550975.02     13807274.98        2550175.       13807925.
      2550381.16     13810151.07
#Sta/Elev= 30
  3964.7  349.56  4012.2  348.49  4030.1  348.31    4157  343.16  4454.6  336.52
  4532.9  331.04  4590.4   333.4  4714.5  331.71  4761.4  334.04  4846.4  332.54
  4938.1  332.55    4998  331.77  5005.5  327.77  5015.6  327.22  5055.8  332.84
  5498.8   331.6  5869.2  329.59  5973.5  332.11  5998.7  326.62  5999.2  326.12
    6021  326.62  6025.3  332.11  6042.9  334.27  6129.7  337.87    6459  335.29
    6673  336.24  6689.7  336.51  7098.2  342.17  7199.9  343.98  7231.1  344.87
#Mann= 17 ,-1 , 0
  3964.7     .07       0  4012.2     .12       0  4030.1     .07       0
    4157     .12       0  4714.5      .1       0  4846.4    .035       0
  4938.1      .1       0  5498.8     .12       0  5973.5    .035       0
  5998.7     .05       0    6021    .035       0  6042.9     .12       0
    6459     .05       0    6673     .12       0  6689.7     .05       0
  7098.2     .07       0  7199.9     .05       0
Bank Sta=5998.7,6021
XS Rating Curve= 0 ,0
Exp/Cntr=0.3,0.1

Type RM Length L Ch R = 1 ,40540   ,630,630,630
BEGIN DESCRIPTION:
Big Fivemile Creek 44.0
END DESCRIPTION:
XS GIS Cut Line= 3
      2551074.99     13806175.01        2549675.       13807775.
      2549991.17     13809921.42
#Sta/Elev= 30
  2868.5  371.24  2944.6  365.79  3286.6  350.46  3604.1  343.31    3661  343.59
  4154.6  337.06  4192.9     336  4278.4  333.11  4413.2  335.57  4505.9  334.19
  4611.8  333.26  4644.2  332.94  4803.3  329.34  4973.2  330.93  4979.9  322.74
  4980.4  322.24  5002.4  322.74  5004.6   325.2  5034.9   331.6  5353.4  329.76
  5850.5  328.69  5964.9  330.97  5989.8  328.98  6005.3   324.9  6045.7  331.04
  6124.2  328.49    6349  334.05  6662.3  334.11  6873.5  339.16  7164.1  343.47
#Mann= 13 ,-1 , 0
  2868.5     .07       0  2944.6     .05       0  3604.1     .12       0
    3661     .05       0  4154.6     .07       0  4192.9     .05       0
  4505.9    .035       0  4611.8     .05       0  4644.2      .1       0
  4979.9     .05       0  5002.4      .1       0  5353.4     .12       0
  6873.5     .07       0
Bank Sta=4979.9,5002.4
XS Rating Curve= 0 ,0
Exp/Cntr=0.3,0.1

Type RM Length L Ch R = 1 ,39910   ,1008,1008,1008
BEGIN DESCRIPTION:
Big Fivemile Creek 43.0
END DESCRIPTION:
XS GIS Cut Line= 3
        2549575.     13805924.99      2549005.18     13808030.68
      2549876.11     13809841.28
#Sta/Elev= 30
  3369.3  352.84  3450.2  349.54  3711.2  339.63    4363   333.5  4421.5  330.92
  4488.2  333.22  4661.7  332.68  4711.8  332.83  4864.1  329.31  4953.6  330.11
  4994.6  322.31  4995.1  321.81  5017.6  322.31  5026.9  330.16  5159.9   329.6
  5606.7  326.88  5844.1  330.34  5889.4   330.1  5906.5  326.15  5979.9  331.47
  6087.5  327.86  6272.6  330.07  6404.8  330.83  6589.4  331.72  6706.6  332.12
  7053.6   332.6  7301.1  336.08  7345.4  337.01  7456.1  340.32  7559.9  342.26
#Mann= 16 ,-1 , 0
  3369.3    .035       0  3450.2     .05       0    4363     .12       0
  4661.7     .05       0  4711.8     .12       0  4864.1      .1       0
  4994.6     .05       0  5017.6      .1       0  5159.9     .12       0
  6272.6     .07       0  6404.8     .12       0  6589.4     .07       0
  6706.6     .12       0  7301.1     .07       0  7345.4     .12       0
  7456.1     .07       0
Bank Sta=4994.6,5017.6
XS Rating Curve= 0 ,0
Exp/Cntr=0.3,0.1

Type RM Length L Ch R = 1 ,38902   ,2203,2203,2203
BEGIN DESCRIPTION:
Big Fivemile Creek 41.0
END DESCRIPTION:
XS GIS Cut Line= 3
      2549524.98     13805575.03        2548325.       13807775.
      2547125.02     13810174.97
#Sta/Elev= 30
  2499.2  367.33  2702.1  360.69  2921.7  349.54  3042.9  344.62  3449.8  334.91
  4166.8  332.83  4190.1  330.26  4223.5  325.64  4386.7  323.83  4414.3  330.38
  4452.2  323.78  4490.2  329.89  4549.5   329.4  4577.5  323.27  4593.7  329.74
  4968.1  328.28  4997.1  320.85  5058.3  329.17  5653.1  326.17  6243.4  327.22
  6276.6  320.52  6277.1  320.02  6299.6  320.52  6346.8  327.23  6494.9   323.3
  6539.7  327.46  6805.3  327.32  7463.8  341.83  7655.2  345.36  7688.4  345.66
#Mann= 13 ,-1 , 0
  2499.2     .05       0  2702.1     .07       0  2921.7     .12       0
  3042.9     .05       0  4166.8     .07       0  4190.1      .1       0
  4968.1     .12       0  5653.1      .1       0  6276.6     .05       0
  6299.6      .1       0  6805.3     .12       0  7463.8     .05       0
  7655.2     .12       0
Bank Sta=6276.6,6299.6
XS Rating Curve= 0 ,0
Exp/Cntr=0.3,0.1

Type RM Length L Ch R = 1 ,36699   ,1168,1168,1168
BEGIN DESCRIPTION:
Big Fivemile Creek 40.0
END DESCRIPTION:
XS GIS Cut Line= 3
        2549275.       13805575.        2547075.       13808475.
      2546075.02     13810024.96
#Sta/Elev= 30
  1359.7  367.79  1382.1  366.73  1487.6  363.39  1598.4  356.06    1810  345.41
  2104.3  336.07  2837.5   331.8  3517.4  332.46  3703.3  326.83  4121.1   324.2
  4214.5  326.53  4335.2  324.05  4385.1  326.11  4593.1  326.09  4707.5     324
  4821.9  327.15  5071.2  323.63  5194.8  324.86  5200.2  323.34  5200.7  322.84
  5231.7  323.34  5365.6  326.38  5485.2  331.26  5678.5  330.29  5881.1  333.26
  6235.3  342.52  6508.2  345.62  6656.9  346.64  6706.6  347.64  6844.3  349.25
#Mann= 13 ,-1 , 0
  1359.7     .05       0  1382.1     .07       0  1598.4     .12       0
  2104.3     .05       0  3517.4     .12       0  3703.3      .1       0
  5200.2     .05       0  5231.7      .1       0  5365.6     .05       0
  6235.3     .07       0  6508.2     .05       0  6656.9     .07       0
  6706.6     .05       0
Bank Sta=5200.2,5231.7
XS Rating Curve= 0 ,0
Exp/Cntr=0.3,0.1

Type RM Length L Ch R = 1 ,35531   ,1099,1099,1099
BEGIN DESCRIPTION:
Big Fivemile Creek 39.0
END DESCRIPTION:
XS GIS Cut Line= 3
      2549275.02     13805374.99        2546875.       13807375.
      2546074.99     13809375.01
#Sta/Elev= 30
  1872.2  377.23  1973.2   371.9  2290.1  356.07  2709.9  339.53  3186.3  331.89
  3579.9   329.5  3682.2  327.17  4123.5  330.68  4233.8  328.95  4496.4  324.15
  4627.7  322.12    4790   321.9  4812.1   324.6  4911.1  323.24  4968.3  325.62
  4977.3   317.6  4977.8   317.1  5008.8   317.6  5011.1  322.06  5017.9  324.24
  5037.2  324.23  5330.6  323.07  5532.2  322.46  5598.7  321.81    5652  320.29
  5881.8  323.69  6181.1  328.87  6650.9  332.15  6944.4  341.12  7150.4     344
#Mann= 14 ,-1 , 0
  1872.2     .05       0  1973.2     .07       0  2290.1     .12       0
  3579.9     .05       0  4233.8     .07       0  4496.4    .035       0
  4627.7     .12       0  4977.3     .05       0  5008.8     .12       0
  5037.2      .1       0  5330.6     .12       0  5532.2      .1       0
  5598.7     .12       0  5881.8     .05       0
Bank Sta=4977.3,5008.8
XS Rating Curve= 0 ,0
Exp/Cntr=0.3,0.1

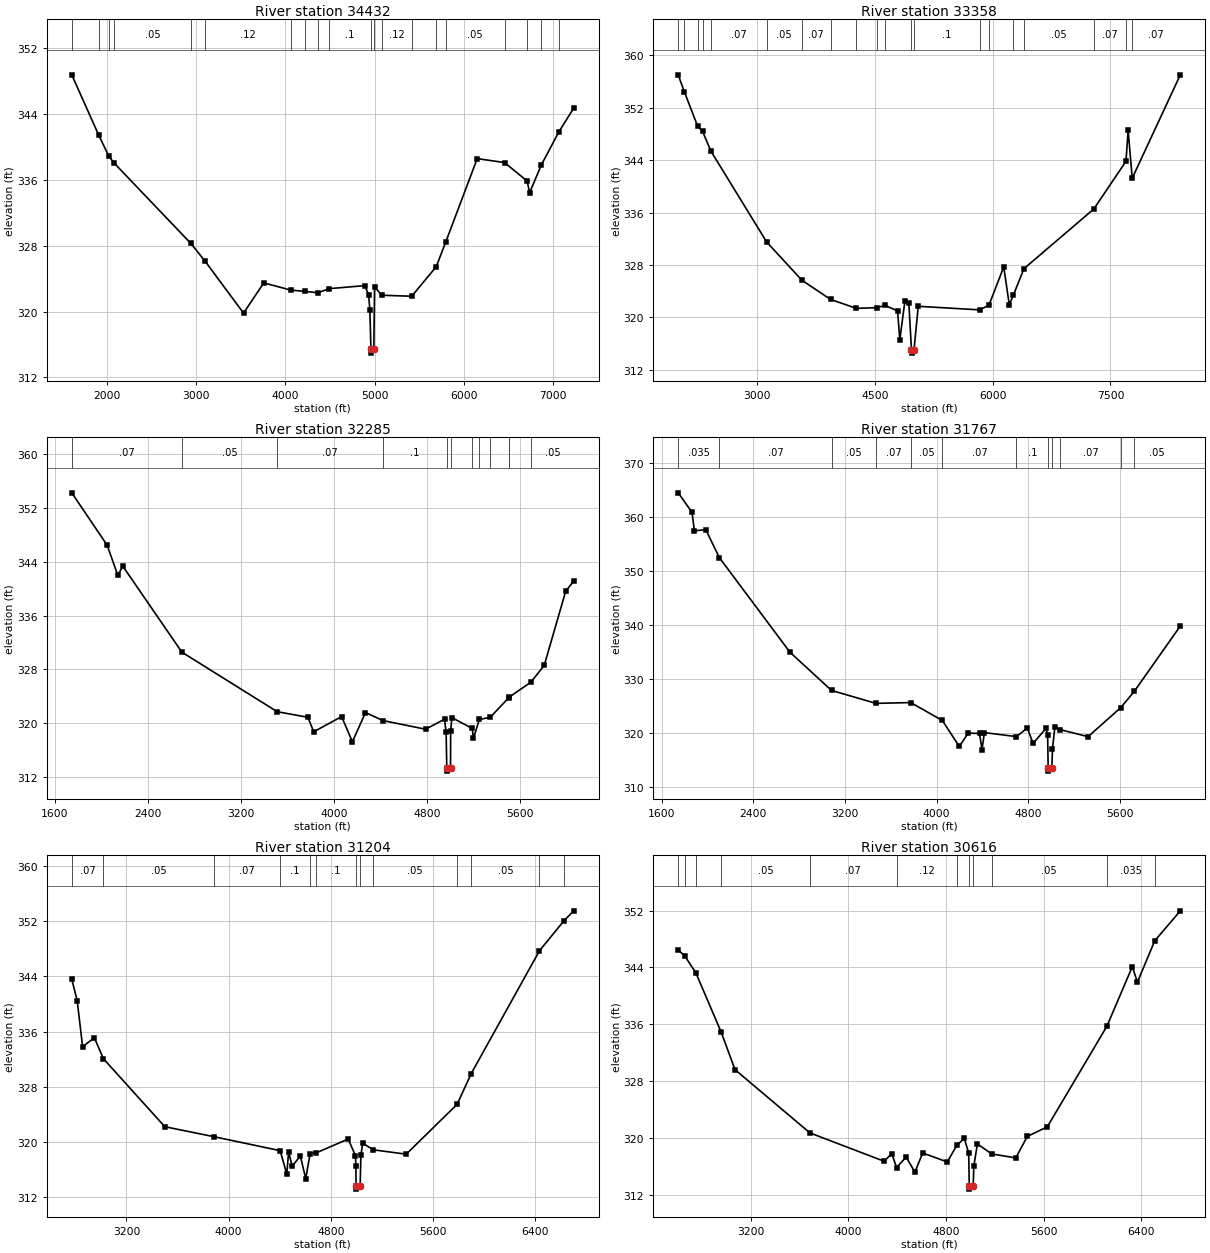
Type RM Length L Ch R = 1 ,34432   ,1074,1074,1074
BEGIN DESCRIPTION:
Big Fivemile Creek 38.0
END DESCRIPTION:
XS GIS Cut Line= 3
      2548425.01     13805174.99        2546025.       13807575.
      2544424.99     13809125.01
#Sta/Elev= 30
  1609.6  348.77  1909.8  341.48  2024.9  338.88    2083  338.06  2942.8  328.29
    3101  326.15  3532.9  319.82  3759.2  323.49  4062.2  322.62    4223  322.45
  4369.2   322.3  4490.2  322.79  4890.6  323.16    4933  322.05  4947.2  320.26
  4959.5  315.46    4960  314.96  4991.4  315.46  5000.2     323  5082.2  321.99
  5415.7  321.87  5690.6  325.46  5795.7  328.42  6149.3  338.59    6456  338.11
  6709.1  335.86  6736.3  334.44  6864.5  337.76  7064.4  341.86  7231.4  344.75
#Mann= 20 ,-1 , 0
  1609.6     .07       0  1909.8     .12       0  2024.9     .07       0
    2083     .05       0  2942.8    .035       0    3101     .12       0
  4062.2     .07       0    4223     .07       0  4369.2    .035       0
  4490.2      .1       0  4959.5     .05       0  4991.4      .1       0
  5082.2     .12       0  5415.7     .12       0  5690.6     .12       0
  5795.7     .05       0    6456     .07       0  6709.1     .12       0
  6864.5     .07       0  7064.4     .05       0
Bank Sta=4959.5,4991.4
XS Rating Curve= 0 ,0
Exp/Cntr=0.3,0.1

Type RM Length L Ch R = 1 ,33358   ,1073,1073,1073
BEGIN DESCRIPTION:
Big Fivemile Creek 37.0
END DESCRIPTION:
XS GIS Cut Line= 3
      2547875.01     13804224.98        2546075.       13806625.
      2543675.03     13809024.97
#Sta/Elev= 30
  1995.8  357.01  2072.5  354.49    2243  349.18  2304.8  348.42  2413.5  345.35
    3122  331.49  3570.8  325.65  3935.3  322.72  4264.7  321.35  4522.3  321.46
  4630.3  321.79  4788.5  320.97  4817.7  316.56  4882.3  322.45  4932.3  322.19
  4966.2  315.01  4966.7  314.51  4998.3  315.01  5052.4  321.67  5835.1  321.12
    5953  321.84  6141.3  327.69    6212  321.88    6265  323.41  6399.1  327.42
  7289.3  336.55  7698.1  343.83  7725.3  348.54  7777.8  341.25  8389.9  357.04
#Mann= 20 ,-1 , 0
  1995.8     .07       0  2072.5    .035       0    2243     .07       0
  2304.8    .035       0  2413.5     .07       0    3122     .05       0
  3570.8     .07       0  3935.3     .05       0  4264.7     .07       0
  4522.3      .1       0  4630.3      .1       0  4966.2     .05       0
  4998.3      .1       0  5835.1    .035       0    5953     .05       0
    6265    .035       0  6399.1     .05       0  7289.3     .07       0
  7698.1     .05       0  7777.8     .07       0
Bank Sta=4966.2,4998.3
XS Rating Curve= 0 ,0
Exp/Cntr=0.3,0.1

Type RM Length L Ch R = 1 ,32285   ,518,518,518
BEGIN DESCRIPTION:
Big Fivemile Creek 35.0
END DESCRIPTION:
XS GIS Cut Line= 3
      2547525.02     13804174.98        2545325.       13806575.
      2544625.01     13807374.99
#Sta/Elev= 30
  1744.2  354.28  2048.5  346.48  2140.4  341.98    2183  343.36  2691.3  330.55
  3511.4  321.68  3775.7  320.85    3825  318.69  4065.5  320.95    4158   317.2
  4270.8  321.55  4421.6  320.36  4787.6  319.07  4950.4  320.56  4964.5   318.6
  4969.9  313.33  4970.5  312.83  5002.3  313.33  5003.3   318.8  5013.8   320.8
  5189.7  319.18  5198.8  317.69  5250.1  320.52  5344.2  320.85  5501.2  323.73
    5506  323.84  5693.5  326.08  5808.2  328.58  5992.3  339.59    6063  341.19
#Mann= 12 ,-1 , 0
  1744.2     .07       0  2691.3     .05       0  3511.4     .07       0
  4421.6      .1       0  4969.9     .05       0  5002.3      .1       0
  5189.7     .12       0  5250.1     .07       0  5344.2    .035       0
  5501.2     .05       0    5506     .07       0  5693.5     .05       0
Bank Sta=4969.9,5002.3
XS Rating Curve= 0 ,0
Exp/Cntr=0.3,0.1

Type RM Length L Ch R = 1 ,31767   ,563,563,563
BEGIN DESCRIPTION:
Big Fivemile Creek 34.0
END DESCRIPTION:
XS GIS Cut Line= 3
      2547624.99     13803925.01        2545225.       13806125.
      2544425.02     13806924.98
#Sta/Elev= 30
  1743.1  364.44  1863.6  360.82  1884.6   357.4  1983.9  357.61  2102.3  352.43
  2719.8  334.88  3082.5  327.81  3470.6  325.41  3774.6  325.56  4050.5  322.24
  4198.8  317.43  4277.1   319.9  4375.8  319.83  4397.3  316.82  4418.3  319.99
  4698.5  319.25  4793.8  320.85  4843.2  317.99  4956.6  320.76  4970.8   319.6
  4975.6  313.35  4976.1  312.85    5008  313.35    5013  316.96  5034.2  321.04
  5082.7  320.53  5324.1  319.24  5608.6   324.6  5727.5  327.62  6130.2  339.75
#Mann= 12 ,-1 , 0
  1743.1    .035       0  2102.3     .07       0  3082.5     .05       0
  3470.6     .07       0  3774.6     .05       0  4050.5     .07       0
  4698.5      .1       0  4975.6     .05       0    5008      .1       0
  5082.7     .07       0  5608.6    .035       0  5727.5     .05       0
Bank Sta=4975.6,5008
XS Rating Curve= 0 ,0
Exp/Cntr=0.3,0.1

Type RM Length L Ch R = 1 ,31204   ,588,588,588
BEGIN DESCRIPTION:
Big Fivemile Creek 33.0
END DESCRIPTION:
XS GIS Cut Line= 3
      2546575.02     13804074.98        2545025.       13805675.
      2543725.03     13806774.98
#Sta/Elev= 30
  2772.3  343.61  2814.7  340.49  2857.1  333.81  2949.2  335.09  3020.4  332.04
  3500.7  322.17  3882.9  320.73  4403.8  318.69  4455.5  315.29  4469.7  318.48
    4498  316.44  4561.5  317.91    4604  314.64  4638.3  318.26  4684.6  318.36
  4936.3  320.38  4992.9  317.98  4996.5  316.53  4997.5   313.6    4998   313.1
  5029.9   313.6  5035.7  318.02    5050  319.77  5133.1  318.81  5390.6  318.18
  5788.8  325.42  5899.5  329.89  6433.9  347.74  6626.5  352.12  6702.9  353.54
#Mann= 13 ,-1 , 0
  2772.3     .07       0  3020.4     .05       0  3882.9     .07       0
  4403.8      .1       0  4638.3     .07       0  4684.6      .1       0
  4997.5     .05       0  5029.9      .1       0  5133.1     .05       0
  5788.8    .035       0  5899.5     .05       0  6433.9    .035       0
  6626.5     .05       0
Bank Sta=4997.5,5029.9
XS Rating Curve= 0 ,0
Exp/Cntr=0.3,0.1

Type RM Length L Ch R = 1 ,30616   ,569,569,569
BEGIN DESCRIPTION:
Big Fivemile Creek 32.0
END DESCRIPTION:
XS GIS Cut Line= 3
      2546677.37     13803913.91        2544675.       13805225.
      2543674.99     13806625.02
#Sta/Elev= 30
  2606.5  346.46  2659.4  345.64  2750.6  343.25  2958.4  334.89  3071.8   329.6
  3685.6  320.69  4292.9   316.7  4356.1  317.76  4395.7  315.81  4473.8  317.29
  4545.7  315.16  4609.4  317.86  4811.4   316.6  4888.5  318.93  4950.2  319.94
  4986.4  317.83  4991.1  313.27  4991.6  312.77  5023.5  313.27  5028.2  315.97
  5057.7  319.14  5174.9  317.73  5372.3  317.17  5466.9   320.2  5630.3  321.54
  6118.2   335.7  6327.1  344.11  6368.9  341.93    6511  347.76  6720.4  351.98
#Mann= 12 ,-1 , 0
  2606.5     .07       0  2659.4    .035       0  2750.6     .07       0
  2958.4     .05       0  3685.6     .07       0  4395.7     .12       0
  4888.5      .1       0  4991.1     .05       0  5023.5      .1       0
  5174.9     .05       0  6118.2    .035       0    6511     .05       0
Bank Sta=4991.1,5023.5
XS Rating Curve= 0 ,0
Exp/Cntr=0.3,0.1

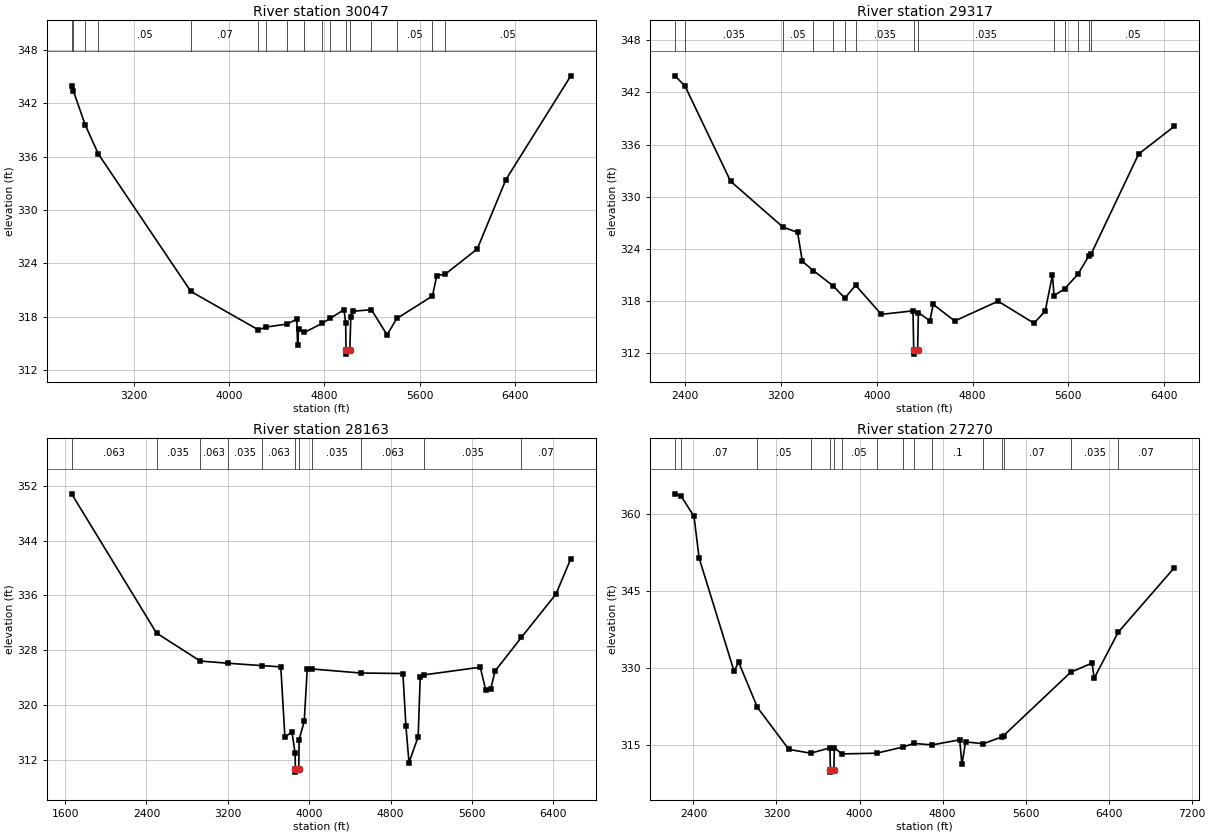
Type RM Length L Ch R = 1 ,30047   ,730,730,730
BEGIN DESCRIPTION:
Big Fivemile Creek 31.0
END DESCRIPTION:
XS GIS Cut Line= 4
      2546585.64     13803925.39      2545112.24     13804193.96
        2544475.       13804725.      2543053.68     13805943.63
#Sta/Elev= 30
  2672.8  343.98  2687.7   343.4  2788.1  339.55  2897.8  336.31  3675.6  320.85
  4243.9  316.52  4306.3  316.83    4482  317.17  4567.2  317.71  4573.7  314.82
  4581.5  316.57  4630.7  316.23  4779.4  317.25  4847.9  317.81  4964.2  318.79
  4978.5  317.24  4980.4  314.29    4981  313.79    5013  314.29  5021.4  317.92
  5035.7  318.61  5194.7  318.79  5326.5  315.96  5408.3   317.8  5708.2  320.33
  5744.7  322.63  5815.7  322.79  6084.9  325.62  6326.4  333.44  6872.2  345.11
#Mann= 17 ,-1 , 0
  2672.8     .07       0  2687.7    .035       0  2788.1     .07       0
  2897.8     .05       0  3675.6     .07       0  4243.9     .12       0
  4306.3     .07       0    4482      .1       0  4630.7    .035       0
  4779.4     .12       0  4847.9      .1       0  4980.4     .05       0
    5013      .1       0  5194.7     .07       0  5408.3     .05       0
  5708.2    .035       0  5815.7     .05       0
Bank Sta=4980.4,5013
XS Rating Curve= 0 ,0
Exp/Cntr=0.3,0.1

Type RM Length L Ch R = 1 ,29317   ,1154,1154,1154
BEGIN DESCRIPTION:
Big Fivemile Creek 29.0
END DESCRIPTION:
XS GIS Cut Line= 3
      2546700.22      13803856.6      2544750.83      13803856.6
      2542775.03     13804874.98
#Sta/Elev= 30
  2312.2  343.89  2396.3  342.72  2777.4  331.78  3214.4  326.52  3337.4   325.9
  3377.4  322.58  3468.4  321.52  3633.7  319.77  3732.2  318.35  3822.4  319.83
  4037.4  316.49  4301.9  316.89  4308.1  312.42  4308.7  311.92  4340.7  312.42
  4346.9   316.7  4443.1  315.74  4470.9  317.63  4650.7  315.73  5013.7     318
  5312.7  315.47    5407  316.86  5467.9  321.04  5480.7  318.64  5569.5  319.42
    5681  321.11  5773.3  323.24  5789.9  323.39    6188  334.91  6484.4  338.07
#Mann= 14 ,-1 , 0
  2312.2     .07       0  2396.3    .035       0  3214.4     .05       0
  3468.4    .035       0  3633.7     .05       0  3732.2     .07       0
  3822.4    .035       0  4308.1     .05       0  4340.7    .035       0
  5480.7     .12       0  5569.5    .035       0    5681     .05       0
  5773.3    .035       0  5789.9     .05       0
Bank Sta=4308.1,4340.7
XS Rating Curve= 0 ,0
Exp/Cntr=0.3,0.1

Type RM Length L Ch R = 1 ,28163   ,893,893,893
BEGIN DESCRIPTION:
Big Fivemile Creek 27.0
END DESCRIPTION:
XS GIS Cut Line= 4
      2546860.85     13803673.12      2545966.36     13803684.59
      2542912.54     13803664.43      2542025.03     13804024.99
#Sta/Elev= 30
  1664.4  350.82    2499   330.5  2928.3  326.42  3200.7   326.1  3535.6  325.75
  3720.3  325.57  3760.3  315.35  3830.3  316.04  3860.3  313.01  3863.7  310.71
  3864.3  310.21  3896.9  310.71  3900.4  314.94  3950.4  317.61  3980.4  325.32
    4028  325.26  4509.1  324.67  4920.4   324.6  4950.4  316.87  4980.4  311.59
  5070.4  315.38  5090.4  324.03  5127.3   324.4  5680.6  325.52  5734.1  322.21
  5782.3  322.29  5826.1  324.96  6084.4  329.86  6424.9  336.19  6570.8  341.35
#Mann= 11 ,-1 , 0
  1664.4    .063       0    2499    .035       0  2928.3    .063       0
  3200.7    .035       0  3535.6    .063       0  3863.7     .05       0
  3896.9    .063       0    4028    .035       0  4509.1    .063       0
  5127.3    .035       0  6084.4     .07       0
Bank Sta=3863.7,3896.9
XS Rating Curve= 0 ,0
Exp/Cntr=0.3,0.1

Type RM Length L Ch R = 1 ,27270   ,549,549,549
BEGIN DESCRIPTION:
Big Fivemile Creek 26.0
END DESCRIPTION:
XS GIS Cut Line= 3
      2545724.98     13801525.01        2543325.       13802925.
      2541724.97     13804175.03
#Sta/Elev= 30
  2221.5     364  2282.3  363.52  2405.5   359.6  2454.3  351.51  2790.8  329.45
  2835.1  331.19  3016.1  322.37  3319.2  314.18    3530  313.44  3714.5  314.48
  3719.4  310.25    3720  309.75  3752.6  310.25  3757.5  314.54  3827.3   313.3
  4164.1  313.44  4415.9  314.62  4522.8  315.35  4698.1  315.05  4964.8  316.05
  4986.3  311.25  5021.7  315.65  5191.9  315.28  5368.5   316.6  5388.5  316.88
    6035  329.23  6239.9     331  6260.7  328.07  6491.1     337  7030.4  349.55
#Mann= 16 ,-1 , 0
  2221.5     .05       0  2282.3     .07       0  3016.1     .05       0
    3530      .1       0  3719.4     .05       0  3752.6      .1       0
  3827.3     .05       0  4164.1     .07       0  4415.9     .05       0
  4522.8     .12       0  4698.1      .1       0  5191.9     .07       0
  5368.5     .05       0  5388.5     .07       0    6035    .035       0
  6491.1     .07       0
Bank Sta=3719.4,3752.6
XS Rating Curve= 0 ,0
Exp/Cntr=0.3,0.1