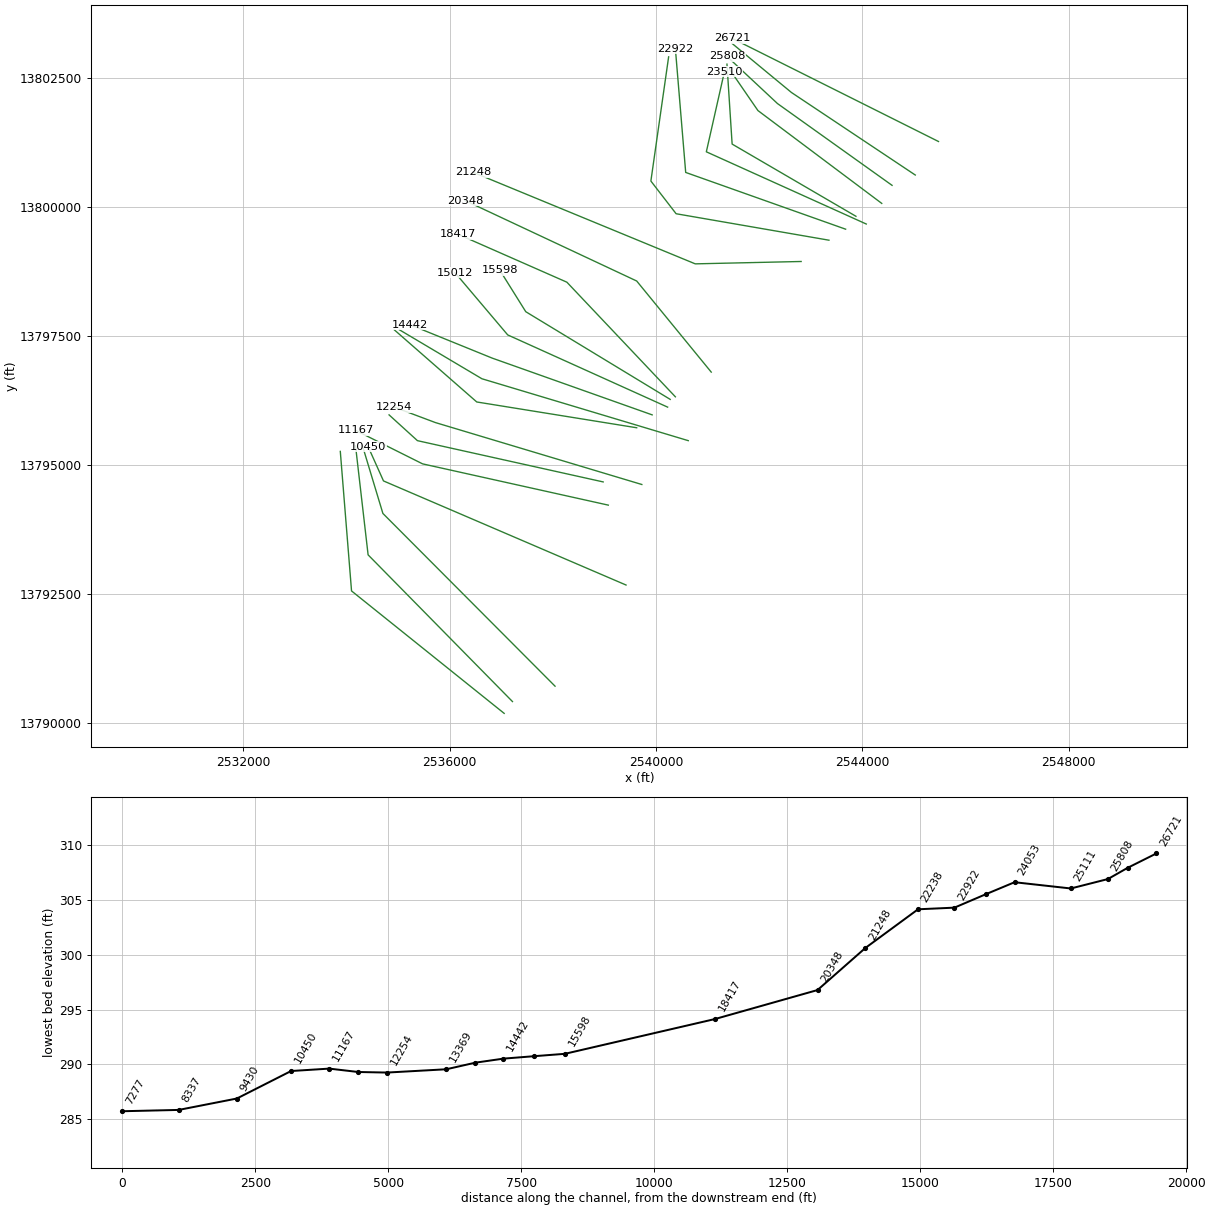
HEC-RAS study Big Fivemile Creek.prj: Big Fivemile Creek Base Level Engineering

--- Big Fivemile Creek.g01 (geometry) --- (continued)

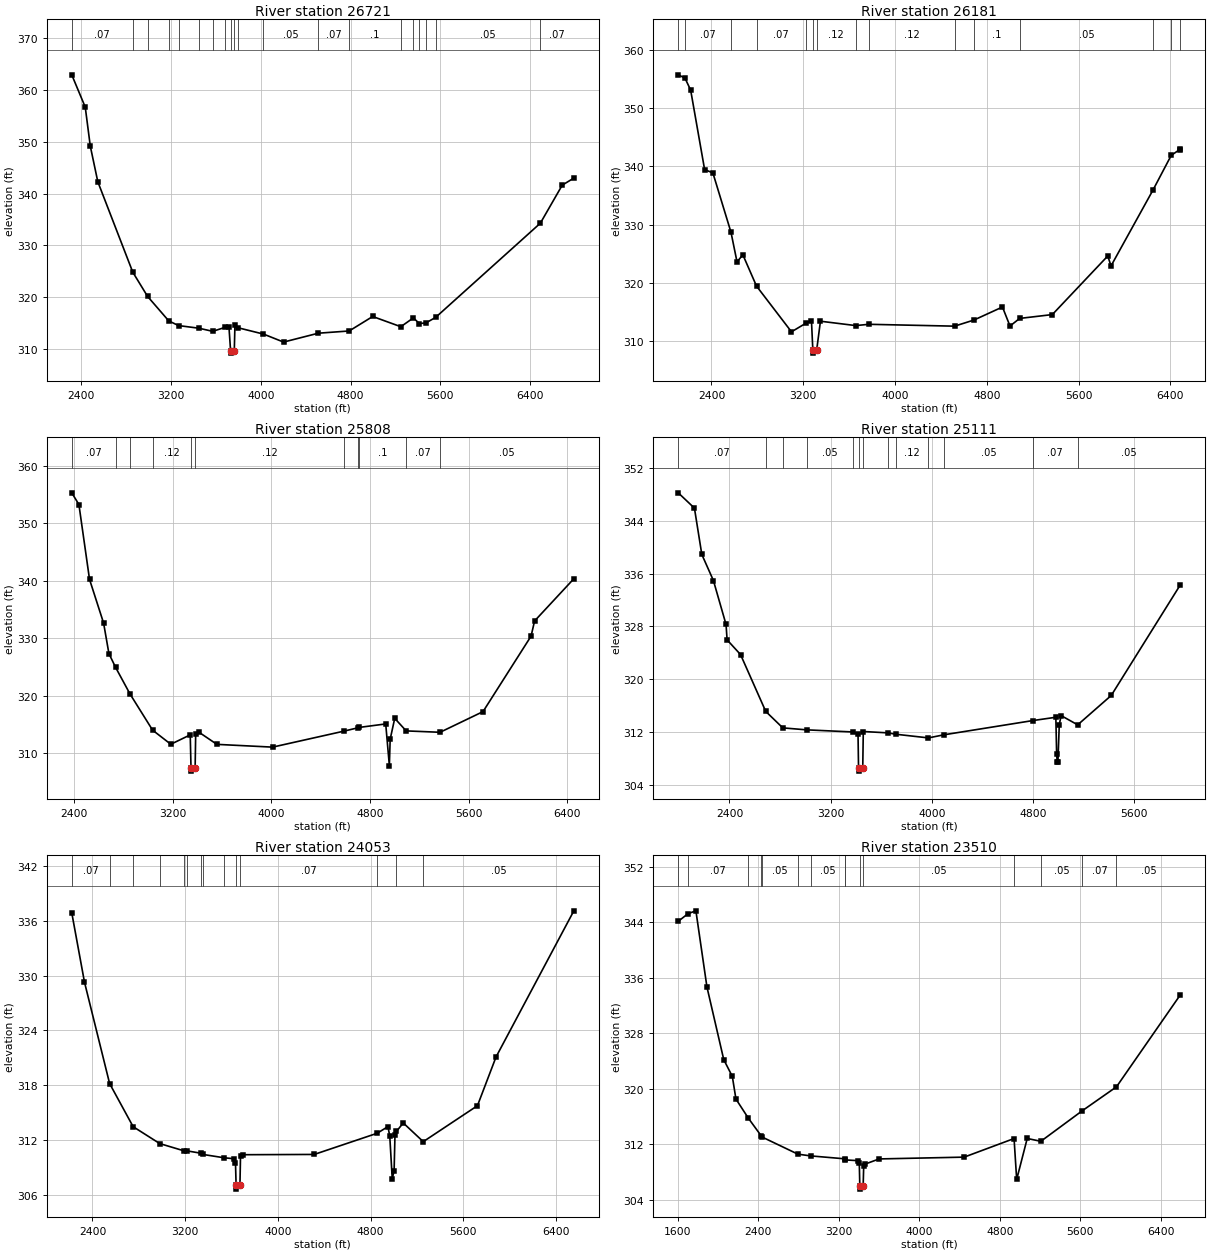
Type RM Length L Ch R = 1 ,26721   ,540,540,540
BEGIN DESCRIPTION:
Big Fivemile Creek 25.0
END DESCRIPTION:
XS GIS Cut Line= 3
      2545474.96     13801275.02        2543075.       13802475.
      2541474.99       13803275.
#Sta/Elev= 30
  2316.8  362.88  2436.9  356.65  2481.7  349.15  2548.7  342.28  2860.2  324.85
  2992.4  320.17  3180.8  315.46  3267.7  314.56  3449.3  314.05  3572.5  313.45
  3684.1  314.23  3717.1  314.24  3731.2  309.75  3731.8  309.25  3764.4  309.75
  3770.2  314.59  3795.8  314.15  4024.5  312.92  4203.4  311.38  4512.9  313.09
  4787.9  313.52  4997.2  316.31  5247.7  314.34  5359.4  316.04  5413.1  314.95
  5471.1  315.07  5558.1  316.14  6490.6  334.29  6685.5  341.62  6788.9  342.98
#Mann= 20 ,-1 , 0
  2316.8     .07       0  2860.2     .12       0  2992.4     .07       0
  3180.8     .05       0  3267.7     .07       0  3449.3     .05       0
  3572.5     .05       0  3684.1     .12       0  3731.2     .05       0
  3764.4     .12       0  3795.8     .07       0  4024.5     .05       0
  4512.9     .07       0  4787.9      .1       0  5247.7     .12       0
  5359.4     .07       0  5413.1     .12       0  5471.1     .07       0
  5558.1     .05       0  6490.6     .07       0
Bank Sta=3731.2,3764.4
XS Rating Curve= 0 ,0
Exp/Cntr=0.3,0.1

Type RM Length L Ch R = 1 ,26181   ,373,373,373
BEGIN DESCRIPTION:
Big Fivemile Creek 24.0
END DESCRIPTION:
XS GIS Cut Line= 3
      2545025.02     13800624.98        2542625.       13802225.
      2541475.01     13803174.99
#Sta/Elev= 30
  2110.2  355.73  2168.6  355.18  2218.4  353.11  2340.1  339.46  2412.2  338.89
    2570  328.69  2622.5  323.62  2673.6  324.82  2792.5  319.45  3097.2   311.6
  3223.4  313.08  3271.5  313.49  3283.4  308.44    3284  307.94  3316.7  308.44
  3349.6  313.42  3657.2  312.67  3771.9  312.89  4518.3  312.57  4687.3  313.62
  4936.1  315.86  5001.8  312.59    5086   313.9  5370.8  314.56  5853.8  324.62
  5882.5  322.92    6248  335.94  6406.8  341.89  6479.3  342.88  6486.3  343.02
#Mann= 15 ,-1 , 0
  2110.2     .05       0  2168.6     .07       0    2570     .12       0
  2792.5     .07       0  3223.4     .12       0  3283.4     .05       0
  3316.7     .12       0  3657.2     .07       0  3771.9     .12       0
  4518.3     .05       0  4687.3      .1       0    5086     .05       0
    6248     .07       0  6406.8     .05       0  6479.3     .07       0
Bank Sta=3283.4,3316.7
XS Rating Curve= 0 ,0
Exp/Cntr=0.3,0.1

Type RM Length L Ch R = 1 ,25808   ,697,697,697
BEGIN DESCRIPTION:
Big Fivemile Creek 23.0
END DESCRIPTION:
XS GIS Cut Line= 3
      2544575.02     13800424.98      2542354.18     13802010.37
      2541374.97     13802925.02
#Sta/Elev= 30
  2383.6  355.27  2441.4  353.24  2527.4  340.24  2641.6  332.63  2684.7  327.33
  2738.7  324.94  2855.4  320.32  3038.6  314.03  3186.2  311.58  3343.5  313.21
  3349.9  307.41  3350.5  306.91  3383.2  307.41  3387.7  313.36  3415.7  313.65
  3559.8  311.56  4010.9  311.08  4589.5  313.86  4704.5  314.45  4710.7   314.5
  4927.7  315.11  4957.2  307.87  4963.8  312.45  5000.7  316.08  5093.6   313.9
  5368.1  313.66  5716.2  317.25  6105.6  330.37  6133.9     333  6452.2  340.34
#Mann= 11 ,-1 , 0
  2383.6     .07       0  2738.7     .12       0  2855.4     .07       0
  3038.6     .12       0  3349.9     .05       0  3383.2     .12       0
  4589.5     .05       0  4704.5     .12       0  4710.7      .1       0
  5093.6     .07       0  5368.1     .05       0
Bank Sta=3349.9,3383.2
XS Rating Curve= 0 ,0
Exp/Cntr=0.3,0.1

Type RM Length L Ch R = 1 ,25111   ,1058,1058,1058
BEGIN DESCRIPTION:
Big Fivemile Creek 22.0
END DESCRIPTION:
XS GIS Cut Line= 3
      2544374.98     13800075.01        2541975.       13801875.
        2541425.       13802675.
#Sta/Elev= 30
  1994.6  348.26  2122.7  345.94    2181  338.92  2272.7  334.96  2372.7  328.29
    2381  325.96  2487.3  323.73  2686.6  315.11  2821.5  312.61  3010.1  312.31
  3376.4  311.99  3416.5  311.63  3420.6  306.55  3421.2  306.05  3453.9  306.55
  3458.1  312.06  3655.2  311.85  3713.1  311.65  3973.2  311.09    4099  311.57
  4799.5  313.72    4981  314.22  4987.3  308.61  4991.5  307.51  4997.6  307.51
  5008.1  313.11    5023  314.47  5153.8  313.07  5419.3  317.53  5965.4   334.3
#Mann= 13 ,-1 , 0
  1994.6     .07       0  2686.6     .12       0  2821.5     .07       0
  3010.1     .05       0  3376.4     .12       0  3420.6     .05       0
  3453.9     .12       0  3655.2     .07       0  3713.1     .12       0
  3973.2     .07       0    4099     .05       0  4799.5     .07       0
  5153.8     .05       0
Bank Sta=3420.6,3453.9
XS Rating Curve= 0 ,0
Exp/Cntr=0.3,0.1

Type RM Length L Ch R = 1 ,24053   ,543,543,543
BEGIN DESCRIPTION:
Big Fivemile Creek 21.0
END DESCRIPTION:
XS GIS Cut Line= 3
      2543875.03     13799824.98        2541475.       13801225.
        2541375.     13802774.96
#Sta/Elev= 30
  2221.4  336.89    2331   329.3  2547.8  318.19  2750.9  313.46  2980.5  311.61
  3193.5   310.8  3216.7  310.81  3332.7  310.56  3352.7  310.42  3538.1  310.05
  3624.3  309.95  3633.8  309.53  3639.1  307.12  3639.7  306.62  3672.4  307.12
  3677.2  310.23  3698.7  310.39  4313.2  310.42  4856.2  312.74  4949.1  313.47
  4964.8  312.45  4986.3  307.77  5002.4  308.63  5009.9  312.56  5022.4  312.94
  5081.3  313.87  5253.9  311.82  5721.4  315.76  5881.8   321.1  6553.1  337.11
#Mann= 14 ,-1 , 0
  2221.4     .07       0  2547.8     .12       0  2750.9     .07       0
  2980.5     .05       0  3193.5    .035       0  3216.7     .05       0
  3332.7    .035       0  3352.7     .05       0  3538.1     .07       0
  3639.1     .05       0  3672.4     .07       0  4856.2     .12       0
  5022.4     .07       0  5253.9     .05       0
Bank Sta=3639.1,3672.4
XS Rating Curve= 0 ,0
Exp/Cntr=0.3,0.1

Type RM Length L Ch R = 1 ,23510   ,588,588,588
BEGIN DESCRIPTION:
Big Fivemile Creek 20.0
END DESCRIPTION:
XS GIS Cut Line= 3
      2544074.99       13799675.        2540975.       13801075.
        2541325.     13802625.01
#Sta/Elev= 30
  1604.3  344.11  1701.6  345.21  1779.9  345.62  1889.6  334.65  2056.7  324.18
  2141.9  321.76  2177.8   318.5  2302.2  315.72  2428.4  313.21  2437.3  313.03
  2793.4  310.56    2919  310.31  3257.5  309.89  3265.9  309.73  3394.2  309.62
  3403.8  309.35    3409  306.02  3409.6  305.52  3442.4  306.02  3447.7  308.82
  3458.1  309.11  3601.3  309.87  4446.2  310.13  4942.3  312.81  4968.3  306.91
  5073.1  312.82  5208.4  312.41  5620.1  316.81  5960.3  320.26  6594.8  333.51
#Mann= 15 ,-1 , 0
  1604.3     .05       0  1701.6     .07       0  2302.2     .12       0
  2428.4     .07       0  2437.3     .05       0  2793.4    .035       0
    2919     .05       0  3257.5     .07       0  3265.9     .05       0
    3409     .05       0  3442.4     .05       0  4942.3     .07       0
  5208.4     .05       0  5620.1     .07       0  5960.3     .05       0
Bank Sta=3409,3442.4
XS Rating Curve= 0 ,0
Exp/Cntr=0.3,0.1

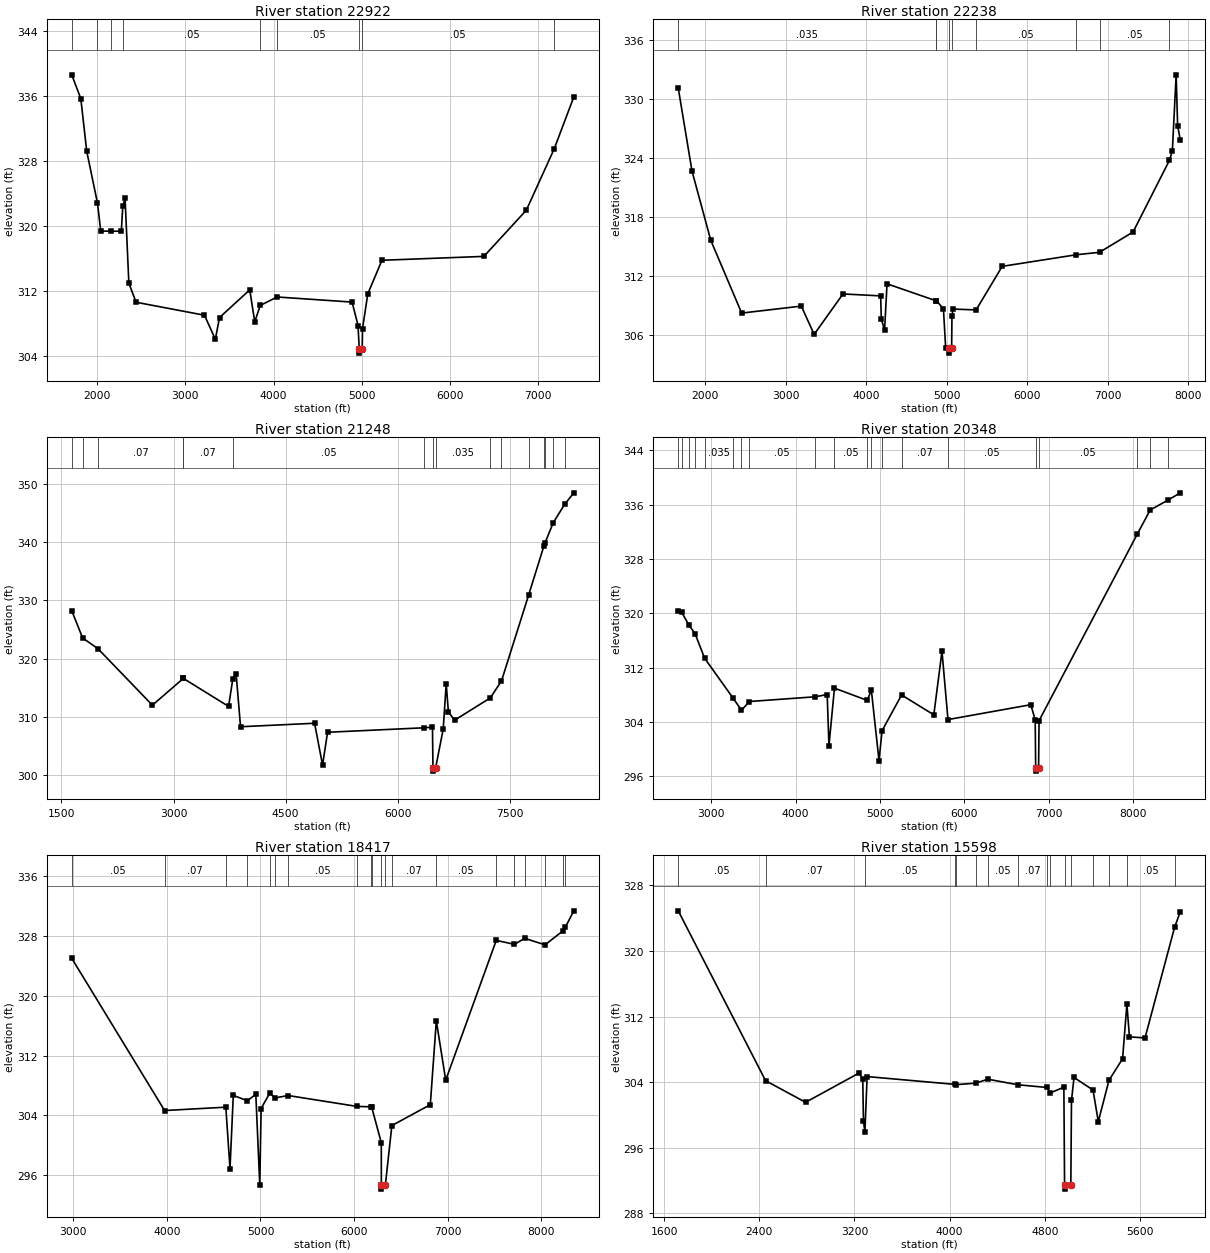
Type RM Length L Ch R = 1 ,22922   ,684,684,684
BEGIN DESCRIPTION:
Big Fivemile Creek 19.0
END DESCRIPTION:
XS GIS Cut Line= 3
      2543675.01       13799575.        2540575.       13800675.
        2540375.     13803074.99
#Sta/Elev= 30
  1710.6  338.65  1813.3   335.7  1880.4  329.22  2002.4  322.81  2039.6  319.37
  2157.1  319.35    2273  319.34  2289.5  322.44  2315.4  323.41  2358.4  312.93
  2440.4  310.58  3216.4  308.98  3339.9  306.01  3387.1  308.69  3730.5  312.11
    3787  308.16  3849.2  310.18  4040.4  311.23    4892   310.6    4959  307.71
  4973.2   304.8  4973.8   304.3  5006.6   304.8    5010  307.32  5070.2  311.63
  5230.8  315.76  6387.3  316.24  6868.9  321.94  7186.9  329.55  7408.3  335.94
#Mann= 9 ,-1 , 0
  1710.6     .07       0  2002.4    .033       0  2157.1     .07       0
  2289.5     .05       0  3849.2     .07       0  4040.4     .05       0
  4973.2     .05       0  5006.6     .05       0  7186.9     .07       0
Bank Sta=4973.2,5006.6
XS Rating Curve= 0 ,0
Exp/Cntr=0.3,0.1

Type RM Length L Ch R = 1 ,22238   ,990,990,990
BEGIN DESCRIPTION:
Big Fivemile Creek 18.0
END DESCRIPTION:
XS GIS Cut Line= 4
      2543351.86     13799361.43      2540389.26     13799874.36
      2539900.19     13800508.16       2540244.2     13802916.28
#Sta/Elev= 30
  1662.2  331.16  1833.1   322.7  2067.1  315.63  2450.6  308.23  3191.5  308.94
  3351.3  306.06  3709.8  310.18  4177.7  309.98  4186.1   307.6  4226.7  306.52
  4257.1  311.21  4867.6  309.48  4870.2   309.5  4958.1  308.66  4985.5  304.71
  5026.5  304.65  5027.1  304.15    5060  304.65    5064  307.94  5078.5  308.64
    5364  308.55  5688.5  312.99  6607.5  314.17  6897.7  314.42  7314.8  316.49
  7766.3  323.78  7803.2  324.76  7850.2   332.5  7868.8  327.32    7902  325.85
#Mann= 9 ,-1 , 0
  1662.2    .035       0  4867.6     .05       0  4870.2     .07       0
  5026.5     .05       0    5060     .07       0    5364     .05       0
  6607.5     .07       0  6897.7     .05       0  7766.3     .07       0
Bank Sta=5026.5,5060
XS Rating Curve= 0 ,0
Exp/Cntr=0.3,0.1

Type RM Length L Ch R = 1 ,21248   ,900,900,900
BEGIN DESCRIPTION:
Big Fivemile Creek 16.0
END DESCRIPTION:
XS GIS Cut Line= 3
      2542812.83     13798948.61      2540760.23     13798902.74
      2536449.46     13800679.79
#Sta/Elev= 30
  1639.1  328.23  1784.4  323.54  1988.9   321.7  2717.2  311.97  3131.8  316.58
  3131.9  316.58  3736.6  311.76  3793.4  316.51  3837.8  317.36  3896.4  308.26
  4887.1  308.86  4993.7  301.66  5060.7  307.31  6350.2  308.08  6463.9  308.19
  6470.4  301.12  6471.1  300.62  6505.2  301.12  6607.5  307.86  6647.6  315.65
    6677  310.81  6759.6  309.39  7238.2  313.23  7387.1  316.15  7748.8  330.87
    7953  339.32  7970.9  339.95  8078.6  343.37    8232  346.55  8354.9  348.53
#Mann= 16 ,-1 , 0
  1639.1     .07       0  1784.4    .035       0  1988.9     .07       0
  3131.8     .05       0  3131.9     .07       0  3793.4     .05       0
  6350.2    .035       0  6470.4     .05       0  6505.2    .035       0
  7238.2     .05       0  7387.1    .035       0  7748.8     .05       0
    7953     .07       0  7970.9     .05       0  8078.6    .035       0
    8232     .05       0
Bank Sta=6470.4,6505.2
XS Rating Curve= 0 ,0
Exp/Cntr=0.3,0.1

Type RM Length L Ch R = 1 ,20348   ,1931,1931,1931
BEGIN DESCRIPTION:
Big Fivemile Creek 15.0
END DESCRIPTION:
XS GIS Cut Line= 3
      2541069.84     13796804.24      2539624.97     13798570.19
       2536299.7     13800129.63
#Sta/Elev= 30
  2608.4  320.39  2647.9  320.19  2736.9  318.25  2808.9  316.99  2920.8  313.41
  3259.1  307.52  3358.4  305.75  3453.2  307.03  4228.6  307.72  4374.9  308.05
  4395.8  300.52  4461.1     309  4850.1  307.19  4898.7   308.7  4989.5  298.32
  5025.5  302.73  5257.2  307.99  5639.5  305.07  5736.3  314.43  5807.4  304.37
  6789.8  306.56    6842  304.32  6847.4  297.28  6848.1  296.78  6882.2  297.28
  6887.6  304.21  8054.6  331.72  8205.7  335.22  8412.2  336.65  8562.9  337.75
#Mann= 20 ,-1 , 0
  2608.4    .035       0  2647.9     .05       0  2736.9    .035       0
  2808.9     .05       0  2920.8    .035       0  3259.1     .05       0
  3358.4    .035       0  3453.2     .05       0  4228.6     .12       0
  4461.1     .05       0  4850.1     .07       0  4898.7     .05       0
  5025.5     .05       0  5257.2     .07       0  5807.4     .05       0
  6847.4     .05       0  6882.2     .05       0  8054.6    .035       0
  8205.7     .05       0  8412.2     .07       0
Bank Sta=6847.4,6882.2
XS Rating Curve= 0 ,0
Exp/Cntr=0.3,0.1

Type RM Length L Ch R = 1 ,18417   ,2819,2819,2819
BEGIN DESCRIPTION:
Big Fivemile Creek 13.0
END DESCRIPTION:
XS GIS Cut Line= 3
      2540375.02     13796324.98      2538271.84     13798547.26
      2536161.86     13799476.11
#Sta/Elev= 30
  2983.9  325.02  3975.9  304.65  4630.1   305.1  4674.7  296.88  4709.9  306.68
  4860.4  305.96  4950.6  306.82    4993  294.69  5007.2  304.92  5098.7  306.97
  5158.1  306.34  5295.3  306.66  6031.7   305.2    6177  305.15  6188.8   305.1
  6291.5  300.35    6292  294.63    6293  294.13  6334.6  294.63  6404.3  302.64
  6815.1  305.43  6879.5  316.65  6979.8  308.71  7520.1  327.43  7714.2  326.89
  7823.1   327.7  8041.1  326.83  8231.1  328.68    8259  329.22    8349  331.38
#Mann= 20 ,-1 , 0
  2983.9     .05       0  3975.9     .07       0  4630.1     .05       0
  4860.4      .1       0  5098.7     .05       0  5158.1      .1       0
  5295.3     .05       0  6031.7     .07       0    6177     .05       0
  6188.8     .07       0    6292     .05       0  6334.6     .07       0
  6404.3     .07       0  6879.5     .05       0  7520.1     .07       0
  7714.2    .035       0  7823.1     .05       0  8041.1     .07       0
  8231.1     .12       0    8259     .07       0
Bank Sta=6292,6334.6
XS Rating Curve= 0 ,0
Exp/Cntr=0.3,0.1

Type RM Length L Ch R = 1 ,15598   ,586,586,586
BEGIN DESCRIPTION:
Big Fivemile Creek 12.0
END DESCRIPTION:
XS GIS Cut Line= 3
      2540274.98     13796275.01        2537475.       13797975.
      2536975.02     13798774.97
#Sta/Elev= 30
  1719.3  324.91  2453.3  304.19  2789.2  301.55  3240.1  305.13  3269.9  304.34
  3275.7  299.25  3287.8  297.94  3306.7  304.69  4043.3  303.74  4052.2   303.7
  4219.8  303.89    4321  304.37  4573.5  303.69  4819.3  303.36  4843.5  302.68
  4959.8   303.4  4965.7  291.46  4966.8  290.96  5018.3  291.46  5023.8  301.78
  5045.1  304.58  5204.8  303.05  5249.1   299.2  5339.1  304.24  5453.1  306.86
  5489.4   313.5  5510.9  309.53  5641.8  309.41  5890.3   322.9  5938.3   324.8
#Mann= 16 ,-1 , 0
  1719.3     .05       0  2453.3     .07       0  3287.8     .05       0
  4043.3     .07       0  4052.2     .05       0  4219.8     .07       0
    4321     .05       0  4573.5     .07       0  4819.3     .05       0
  4843.5     .07       0  4965.7     .05       0  5018.3     .12       0
  5204.8     .05       0  5339.1     .07       0  5489.4     .05       0
  5890.3     .07       0
Bank Sta=4965.7,5018.3
XS Rating Curve= 0 ,0
Exp/Cntr=0.3,0.1

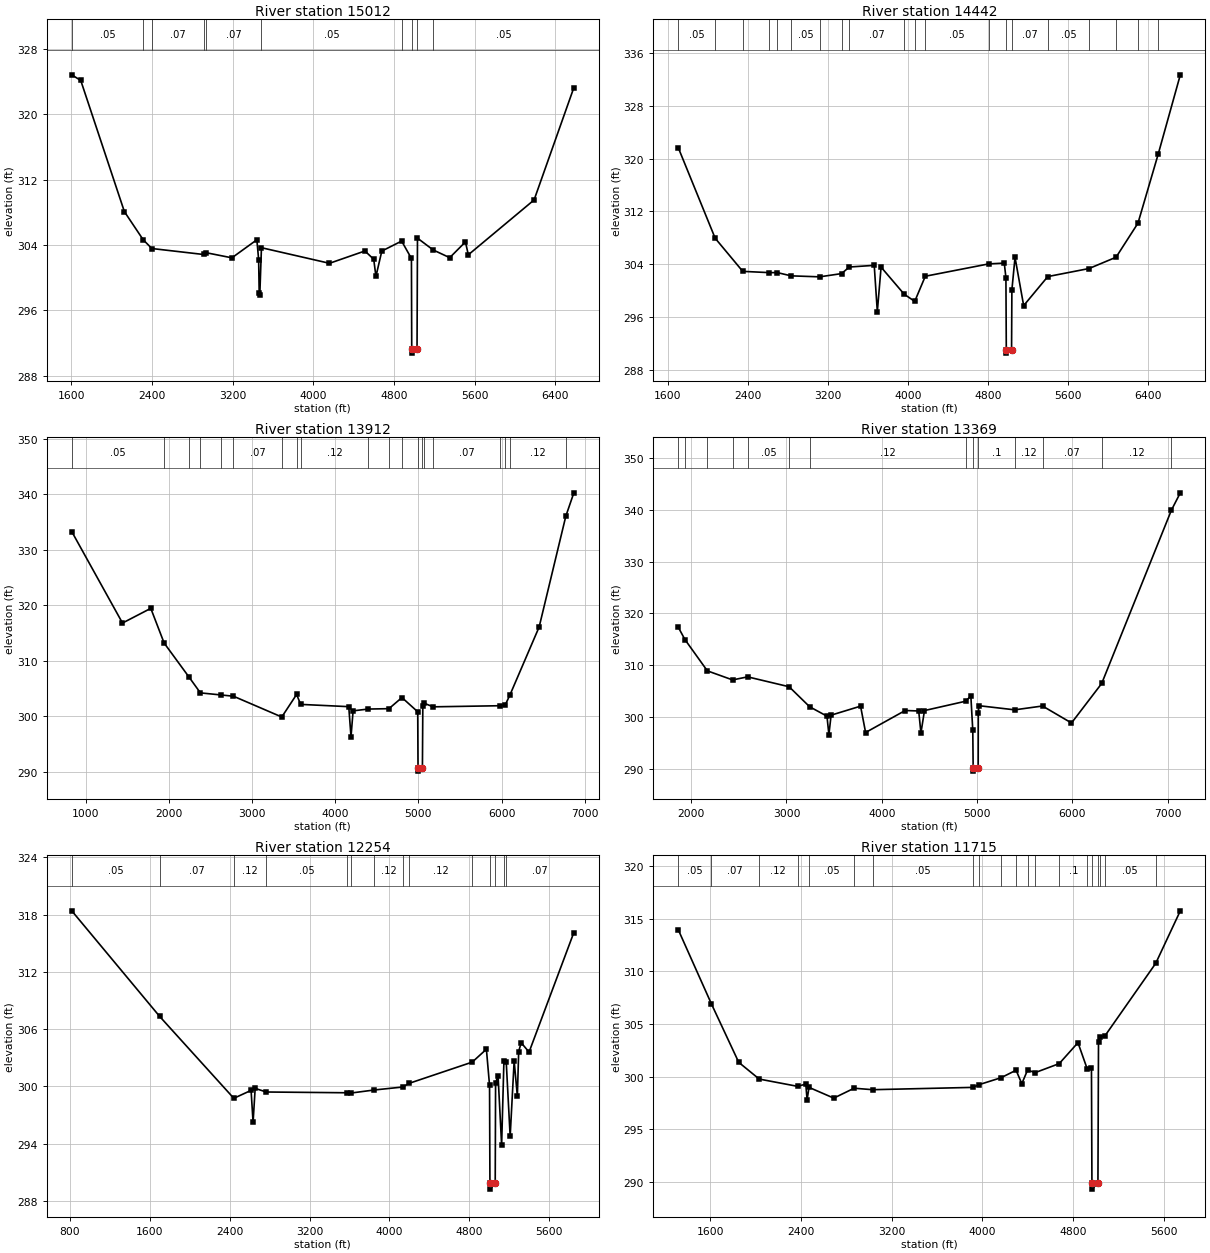
Type RM Length L Ch R = 1 ,15012   ,570,570,570
BEGIN DESCRIPTION:
Big Fivemile Creek 11.0
END DESCRIPTION:
XS GIS Cut Line= 3
      2540224.99     13796125.01        2537125.       13797525.
      2536104.83     13798730.38
#Sta/Elev= 30
  1602.7  324.82  1691.8  324.13  2124.5  308.07  2311.3  304.62    2397  303.55
  2909.9  302.82  2934.2  303.04  3191.1  302.41  3438.8  304.62  3456.4   302.2
  3461.9  298.16    3468  297.87  3484.3  303.65  4159.3  301.74    4511  303.25
    4598  302.23  4620.1  300.14  4678.3  303.24    4875  304.46  4972.2  302.33
  4975.1  291.24  4976.2  290.74  5027.7  291.24  5032.1  304.82  5188.4  303.37
  5351.9  302.43  5507.9  304.36  5536.5  302.78    6189   309.5  6583.3  323.25
#Mann= 10 ,-1 , 0
  1602.7     .05       0  2311.3    .035       0    2397     .07       0
  2909.9     .05       0  2934.2     .07       0  3484.3     .05       0
    4875     .07       0  4975.1     .05       0  5027.7     .07       0
  5188.4     .05       0
Bank Sta=4975.1,5027.7
XS Rating Curve= 0 ,0
Exp/Cntr=0.3,0.1

Type RM Length L Ch R = 1 ,14442   ,530,530,530
BEGIN DESCRIPTION:
Big Fivemile Creek 10.0
END DESCRIPTION:
XS GIS Cut Line= 3
      2539925.02     13795974.99        2536825.       13797075.
      2535224.99       13797725.
#Sta/Elev= 30
  1703.9  321.66  2072.8  307.93  2348.5  302.91  2610.1  302.72  2694.6  302.72
  2831.4  302.23  3116.8  302.08  3335.8  302.57  3413.1  303.57  3662.1  303.82
    3693  296.81  3730.6  303.55  3961.3  299.45  4066.8  298.36  4172.4  302.17
  4805.7  304.04  4961.5  304.16  4977.9  301.95  4981.7  291.02  4982.8  290.52
  5034.3  291.02  5037.5   300.1  5068.9  305.02  5155.2  297.72  5396.2  302.12
  5808.6  303.34  6078.3  305.05  6297.1  310.21  6499.9   320.7  6720.3  332.69
#Mann= 20 ,-1 , 0
  1703.9     .05       0  2072.8    .035       0  2348.5     .07       0
  2610.1     .05       0  2694.6    .035       0  2831.4     .05       0
  3116.8    .035       0  3335.8     .05       0  3413.1     .07       0
  3961.3     .07       0  4066.8     .12       0  4172.4     .05       0
  4805.7     .07       0  4981.7     .05       0  5034.3     .07       0
  5396.2     .05       0  5808.6     .05       0  6078.3     .07       0
  6297.1     .12       0  6499.9     .07       0
Bank Sta=4981.7,5034.3
XS Rating Curve= 0 ,0
Exp/Cntr=0.3,0.1

Type RM Length L Ch R = 1 ,13912   ,543,543,543
BEGIN DESCRIPTION:
Big Fivemile Creek 9.0
END DESCRIPTION:
XS GIS Cut Line= 3
      2540625.03     13795474.99        2536625.       13796675.
      2535025.03     13797624.98
#Sta/Elev= 30
   832.2  333.25  1442.1   316.8  1782.3  319.44  1942.7   313.2  2243.2  307.05
  2378.9  304.23  2631.4  303.85  2776.2  303.63  3357.3  299.89  3535.6  303.95
  3584.2  302.16  4162.7  301.75  4189.7  296.33  4214.9     301  4396.7  301.32
  4645.8  301.39  4802.1  303.39  4991.8  300.83  4995.5  290.75  4996.6  290.15
  5048.4  290.75  5053.2  301.81  5061.5  302.42    5176  301.72  5984.7  301.92
  6045.5  302.11  6100.2  303.84  6452.1   316.1  6772.8  336.04  6869.1  340.23
#Mann= 20 ,-1 , 0
   832.2     .05       0  1942.7     .07       0  2243.2     .05       0
  2378.9     .07       0  2631.4    .035       0  2776.2     .07       0
  3357.3     .05       0  3535.6     .07       0  3584.2     .12       0
  4396.7      .1       0  4645.8     .12       0  4802.1      .1       0
  4995.5     .05       0  5048.4      .1       0  5061.5     .12       0
    5176     .07       0  5984.7     .12       0  6045.5     .07       0
  6100.2     .12       0  6772.8     .07       0
Bank Sta=4995.5,5048.4
XS Rating Curve= 0 ,0
Exp/Cntr=0.3,0.1

Type RM Length L Ch R = 1 ,13369   ,1115,1115,1115
BEGIN DESCRIPTION:
Big Fivemile Creek 8.0
END DESCRIPTION:
XS GIS Cut Line= 3
      2539624.99       13795725.        2536525.       13796225.
      2534924.99     13797625.01
#Sta/Elev= 30
  1864.8  317.36  1934.9  314.97  2170.2  308.92  2434.8  307.17    2593  307.76
  3027.9  305.85  3243.4  301.98  3424.7  300.17    3445   296.6  3468.2  300.36
  3777.2   302.1  3829.9  297.01  4245.2  301.26    4387  301.17  4410.3  296.91
  4447.7  301.25  4878.5  303.05  4933.9  304.06  4954.2  297.43  4958.1  290.15
  4959.2  289.55    5011  290.15    5012  300.71  5018.6  302.19    5394  301.39
  5685.5  302.13  5989.6  298.85  6306.3  306.48  7037.7  339.97  7130.9  343.31
#Mann= 14 ,-1 , 0
  1864.8     .05       0  1934.9     .07       0  2170.2     .05       0
  2434.8     .07       0    2593     .05       0  3027.9     .07       0
  3243.4     .12       0  4878.5      .1       0  4958.1     .05       0
    5011      .1       0    5394     .12       0  5685.5     .07       0
  6306.3     .12       0  7037.7     .07       0
Bank Sta=4958.1,5011
XS Rating Curve= 0 ,0
Exp/Cntr=0.3,0.1

Type RM Length L Ch R = 1 ,12254   ,539,539,539
BEGIN DESCRIPTION:
Big Fivemile Creek 7.0
END DESCRIPTION:
XS GIS Cut Line= 3
      2539724.98     13794625.01        2535725.       13795825.
        2534925.       13796125.
#Sta/Elev= 30
   817.7  318.39  1698.6  307.33  2441.3  298.76  2614.3  299.59  2634.3  296.24
  2655.2   299.8  2766.1  299.42  3572.3  299.34  3614.4  299.31  3847.5  299.63
  4132.9  299.94  4198.8  300.33  4830.2  302.55  4972.1   303.9  5003.6  300.11
  5007.4  289.85  5008.4  289.25  5060.4  289.85  5064.1  300.39    5089   301.1
  5124.6  293.86  5147.5  302.63  5170.7  302.58  5210.1  294.77  5250.1  302.68
  5282.2  298.98  5295.5  303.66  5320.4  304.58  5399.6   303.6  5848.2  316.12
#Mann= 14 ,-1 , 0
   817.7     .05       0  1698.6     .07       0  2441.3     .12       0
  2766.1     .05       0  3572.3     .07       0  3614.4     .05       0
  3847.5     .12       0  4132.9    .035       0  4198.8     .12       0
  4830.2      .1       0  5007.4     .05       0  5060.4      .1       0
  5147.5     .12       0  5170.7     .07       0
Bank Sta=5007.4,5060.4
XS Rating Curve= 0 ,0
Exp/Cntr=0.3,0.1

Type RM Length L Ch R = 1 ,11715   ,548,548,548
BEGIN DESCRIPTION:
Big Fivemile Creek 6.0
END DESCRIPTION:
XS GIS Cut Line= 3
      2538975.02       13794675.        2535375.       13795475.
      2534825.03     13795974.97
#Sta/Elev= 30
  1315.8  313.96  1607.6  306.93  1849.8  301.35  2030.6  299.76  2368.5  299.07
  2441.4  299.28  2452.9   297.8  2470.1  298.97  2688.5  297.95    2868  298.89
  3031.2  298.75  3915.9  298.97  3974.1  299.24    4165  299.89  4297.5   300.6
    4348  299.32    4399  300.62  4465.3  300.37  4678.4  301.23  4843.6  303.22
  4925.8  300.71  4962.7  300.84  4966.9   289.9  4967.9   289.3  5019.9   289.9
  5024.9   303.3  5034.3  303.77  5078.7  303.82  5529.9  310.76  5746.9  315.75
#Mann= 20 ,-1 , 0
  1315.8     .05       0  1607.6     .07       0  2030.6     .12       0
  2368.5     .07       0  2470.1     .05       0    2868     .07       0
  3031.2     .05       0  3915.9    .035       0  3974.1     .05       0
    4165     .07       0  4297.5     .12       0    4399     .07       0
  4465.3     .12       0  4678.4      .1       0  4925.8     .12       0
  4966.9     .05       0  5019.9     .12       0  5034.3     .07       0
  5078.7     .05       0  5529.9     .07       0
Bank Sta=4966.9,5019.9
XS Rating Curve= 0 ,0
Exp/Cntr=0.3,0.1

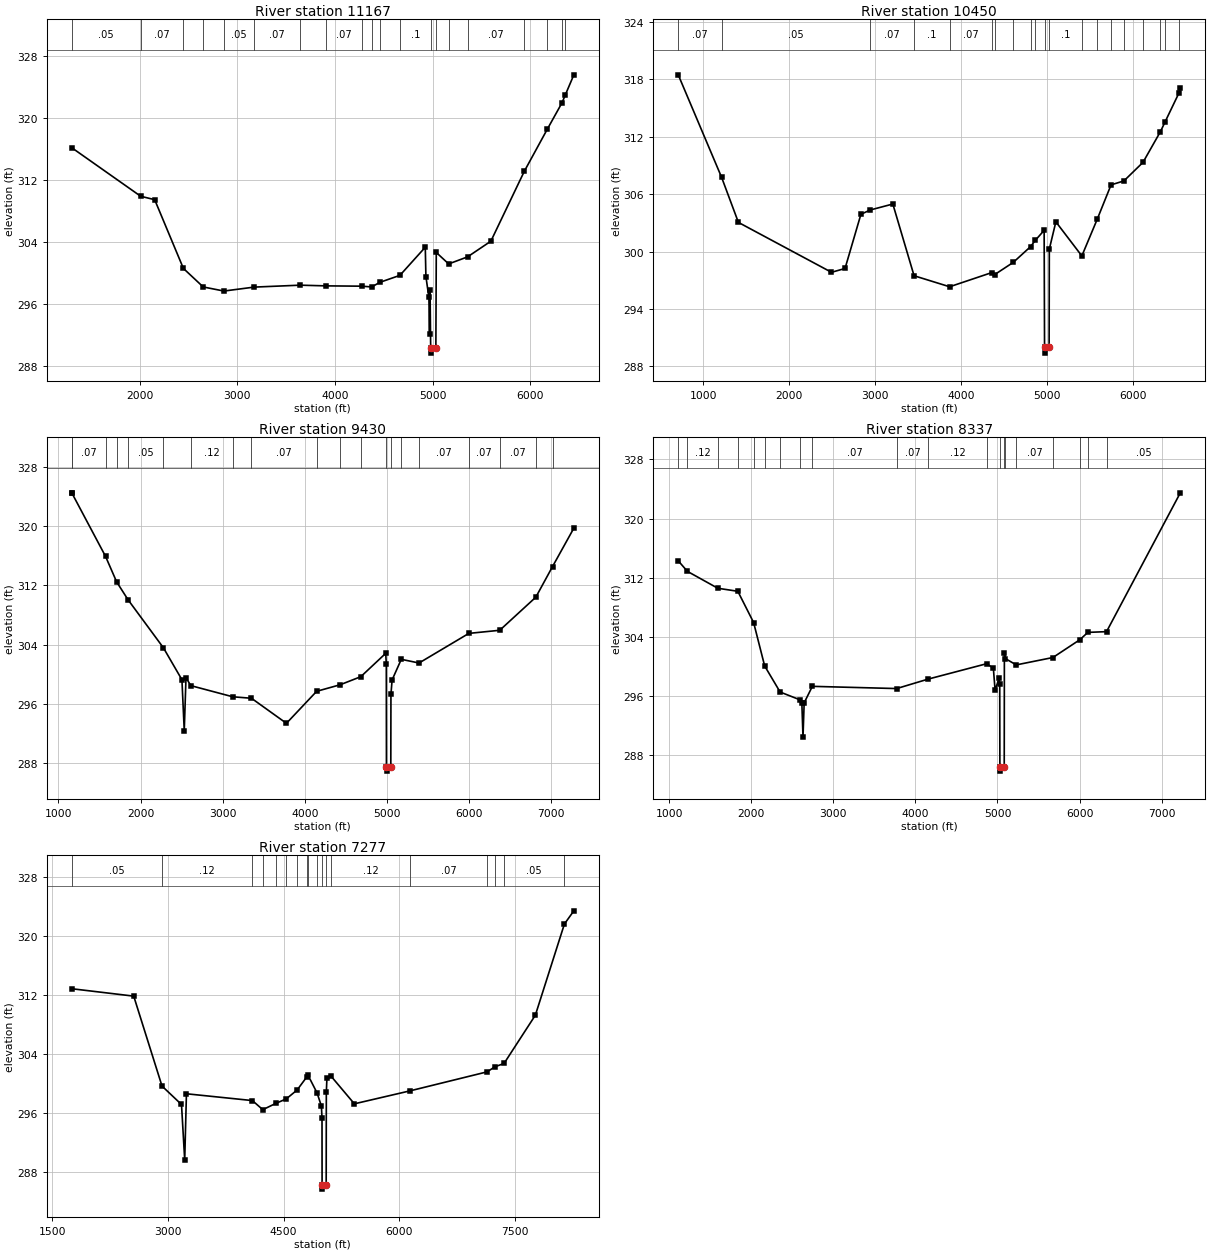
Type RM Length L Ch R = 1 ,11167   ,717,717,717
BEGIN DESCRIPTION:
Big Fivemile Creek 5.0
END DESCRIPTION:
XS GIS Cut Line= 3
      2539075.02       13794225.        2535475.       13795025.
      2534174.98     13795675.01
#Sta/Elev= 30
  1304.4  316.18  2010.4   309.9  2153.4  309.46  2447.2  300.57  2650.3  298.17
  2862.5  297.64  3171.8  298.15    3643   298.4  3907.4  298.31  4274.6  298.27
  4376.2  298.17  4457.6  298.76  4664.6  299.67  4924.4  303.31  4930.8  299.52
  4961.5  296.81  4967.9   292.1    4973   297.8  4979.7  290.21  4980.8  289.61
  5032.7  290.21    5037  302.63  5163.9  301.15  5357.2  302.06    5596  304.09
  5938.4  313.13  6173.1  318.56  6324.8     322  6358.7  323.02  6445.7  325.61
#Mann= 20 ,-1 , 0
  1304.4     .05       0  2010.4     .07       0  2447.2     .12       0
  2650.3     .07       0  2862.5     .05       0  3171.8     .07       0
    3643     .12       0  3907.4     .07       0  4274.6    .035       0
  4376.2     .07       0  4457.6     .12       0  4664.6      .1       0
  4979.7     .05       0  5032.7      .1       0  5163.9     .12       0
  5357.2     .07       0  5938.4     .07       0  6173.1    .035       0
  6324.8     .05       0  6358.7     .07       0
Bank Sta=4979.7,5032.7
XS Rating Curve= 0 ,0
Exp/Cntr=0.3,0.1

Type RM Length L Ch R = 1 ,10450   ,1020,1020,1020
BEGIN DESCRIPTION:
Big Fivemile Creek 4.0
END DESCRIPTION:
XS GIS Cut Line= 3
      2539418.54     13792676.04      2534716.99     13794694.26
      2534419.41     13795358.09
#Sta/Elev= 30
   708.5  318.45  1213.1  307.75  1408.8  303.04  2492.4  297.83    2650  298.23
  2834.4  303.88  2940.4  304.33  3206.4  304.96  3453.5  297.47  3867.4  296.32
  4358.2   297.8  4393.3   297.6  4608.7  298.87  4809.4  300.51  4863.8  301.16
  4967.4  302.21  4972.2  289.99  4973.3  289.39  5025.3  289.99  5027.7  300.25
  5103.8   303.1  5406.3  299.54  5586.2  303.39  5746.2  306.96  5895.6  307.37
    6118  309.31  6321.7  312.53  6374.8  313.53  6534.7  316.52  6552.4  317.05
#Mann= 20 ,-1 , 0
   708.5     .07       0  1213.1     .05       0  2940.4     .07       0
  3453.5      .1       0  3867.4     .07       0  4358.2     .12       0
  4393.3     .07       0  4608.7     .12       0  4809.4    .035       0
  4863.8      .1       0  4972.2     .05       0  5025.3      .1       0
  5406.3     .12       0  5586.2    .035       0  5746.2     .07       0
  5895.6     .07       0    6118     .05       0  6321.7     .07       0
  6374.8     .05       0  6534.7     .07       0
Bank Sta=4972.2,5025.3
XS Rating Curve= 0 ,0
Exp/Cntr=0.3,0.1

Type RM Length L Ch R = 1 ,9430    ,1093,1093,1093
BEGIN DESCRIPTION:
Big Fivemile Creek 3.0
END DESCRIPTION:
XS GIS Cut Line= 3
       2538042.5     13790715.12      2534705.52     13794063.56
      2534304.73      13795391.9
#Sta/Elev= 30
  1162.6  324.54  1163.1  324.53  1573.9  315.94  1709.1  312.49  1847.9  310.07
  2278.6  303.57  2504.2  299.25  2532.5  292.35  2553.8  299.53  2612.1  298.45
  3123.5  296.94  3351.3  296.74    3777  293.35  4144.9  297.68    4432  298.57
  4682.8  299.66  4986.2  302.82  4993.3  301.39    4995  287.48  4996.1  286.88
  5048.1  287.48  5049.8  297.28    5064  299.22  5175.8  302.01  5391.8  301.51
  5998.9  305.52  6374.9  305.94  6814.4  310.42  7018.2  314.57  7277.4  319.76
#Mann= 20 ,-1 , 0
  1162.6     .05       0  1163.1     .07       0  1573.9     .12       0
  1709.1     .12       0  1847.9     .05       0  2278.6      .1       0
  2612.1     .12       0  3123.5     .12       0  3351.3     .07       0
  4144.9     .12       0    4432     .12       0  4682.8     .07       0
    4995     .05       0  5048.1      .1       0  5175.8     .12       0
  5391.8     .07       0  5998.9     .07       0  6374.9     .07       0
  6814.4    .035       0  7018.2    .035       0
Bank Sta=4995,5048.1
XS Rating Curve= 0 ,0
Exp/Cntr=0.3,0.1

Type RM Length L Ch R = 1 ,8337    ,1060,1060,1060
BEGIN DESCRIPTION:
Big Fivemile Creek 2.0
END DESCRIPTION:
XS GIS Cut Line= 3
      2537216.85     13790416.98      2534418.84     13793260.86
        2534175.     13795374.99
#Sta/Elev= 30
  1110.4  314.29  1222.9  312.86  1592.6  310.58  1836.5  310.17    2029  305.94
  2163.4  300.07  2351.8  296.54    2600  295.46  2616.5  295.07  2630.6  290.43
  2644.8  295.08  2744.5  297.31    3772  297.01  4155.4  298.29    4868  300.37
  4950.1  299.77  4971.2  296.79  5020.8  298.43  5027.8  297.66  5029.5  286.44
  5030.6  285.84  5082.6  286.44  5084.4  301.78  5095.9  301.07  5228.7  300.21
  5675.7  301.21  6002.9  303.61  6101.6  304.61  6329.3  304.71  7228.1  323.49
#Mann= 20 ,-1 , 0
  1110.4     .12       0  1222.9     .12       0  1592.6    .035       0
  1836.5     .05       0    2029     .05       0  2163.4     .12       0
  2351.8    .035       0    2600     .12       0  2744.5     .07       0
    3772     .07       0  4155.4     .12       0    4868      .1       0
  5029.5     .05       0  5082.6      .1       0  5095.9     .12       0
  5228.7     .07       0  5675.7     .07       0  6002.9    .035       0
  6101.6     .07       0  6329.3     .05       0
Bank Sta=5029.5,5082.6
XS Rating Curve= 0 ,0
Exp/Cntr=0.3,0.1

Type RM Length L Ch R = 1 ,7277    ,0,0,0
BEGIN DESCRIPTION:
Big Fivemile Creek 1.0
END DESCRIPTION:
XS GIS Cut Line= 3
      2537056.31     13790187.63      2534097.76     13792561.35
      2533879.94      13795266.9
#Sta/Elev= 30
  1754.5  312.83  2557.4  311.83  2924.2  299.66  3176.7  297.17  3218.3  289.66
  3240.7  298.62  4095.5   297.7  4230.5  296.47  4401.7  297.33  4534.9  297.93
  4675.1  299.13  4804.3  300.95  4812.1  301.22  4933.4  298.74  4989.8  296.97
  4997.8  295.34  4998.9  286.32    5000  285.72    5052  286.32  5053.8  298.81
  5061.8  300.82  5117.6  300.97  5417.1  297.26  6140.6  299.02  7139.5  301.59
    7238  302.27  7357.3  302.72    7763  309.25  8139.7  321.59  8261.9  323.37
#Mann= 18 ,-1 , 0
  1754.5     .05       0  2924.2     .12       0  4095.5     .07       0
  4230.5     .12       0  4401.7     .07       0  4534.9     .12       0
  4675.1    .035       0  4804.3      .1       0  4812.1    .035       0
  4933.4      .1       0  4998.9     .05       0    5052      .1       0
  5117.6     .12       0  6140.6     .07       0  7139.5    .035       0
    7238     .07       0  7357.3     .05       0  8139.7    .035       0
Bank Sta=4998.9,5052
XS Rating Curve= 0 ,0
Exp/Cntr=0.3,0.1

Chan Stop Cuts=-1
Use User Specified Reach Order=0
Composite Channel Slope=5