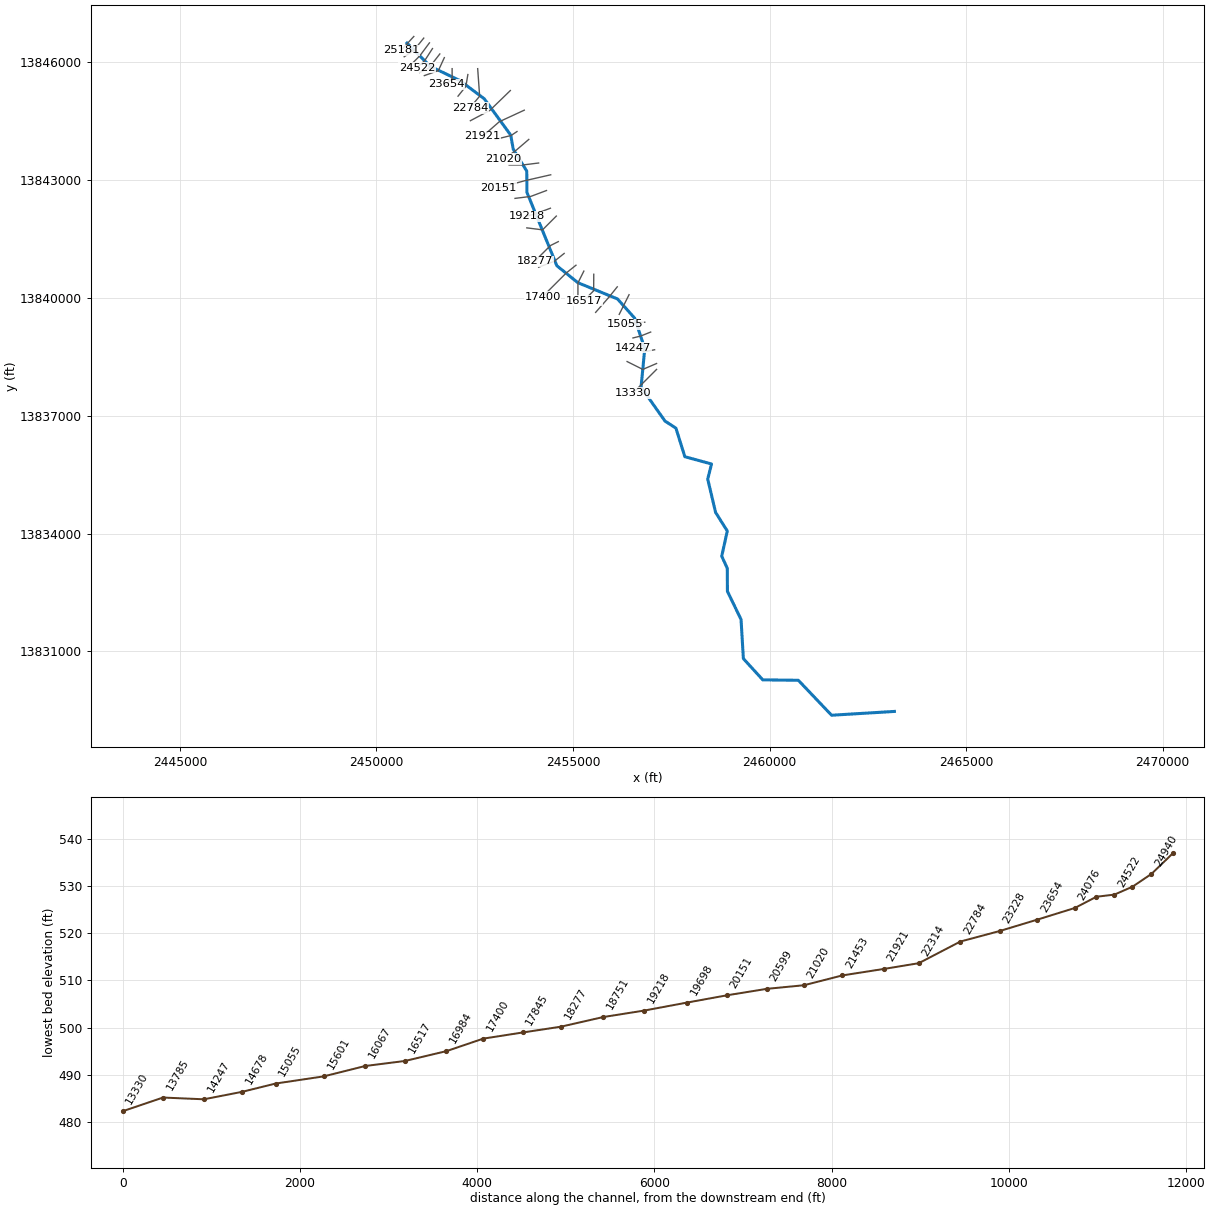
--- Big Sandy Branch.prj (project) ---

Proj Title=Big Sandy Branch Base Level Engineering
Current Plan=p01
Default Exp/Contr=0.3,0.1
English Units
Geom File=g01
Flow File=f01
Plan File=p01
Y Axis Title=Elevation
X Axis Title(PF)=Main Channel Distance
X Axis Title(XS)=Station
BEGIN DESCRIPTION:
Big Sandy Branch
END DESCRIPTION:
DSS Export Rating Curves= 0
DSS Export Rating Curve Sorted= 0
DSS Export Volume Flow Curves= 0
DXF OffsetX= 0
DXF OffsetY= 0
DXF ScaleX= 1
DXF ScaleY= 10

--- Big Sandy Branch.p01 (plan) ---

Plan Title=Multiple Run
Short Identifier=Multiple
Geom File=g01
Flow File=f01
Subcritical Flow
K Sum by GR= 0
Std Step Tol= 0.01
Critical Tol= 0.01
Num of Std Step Trials= 20
Max Error Tol= 0.3
Flow Tol Ratio= 0.001
Split Flow NTrial= 30
Split Flow Tol= 0.02
Split Flow Ratio= 0.02
Log Output Level= 0
Friction Slope Method= 1
Unsteady Friction Slope Method= 2
Unsteady Bridges Friction Slope Method= 1
Parabolic Critical Depth
Global Vel Dist=  1 , 1 , 1
Global Log Level= 0
CheckData=True
Encroach Param= -1, 0, 0, 0
BEGIN DESCRIPTION:
Multiple Run
END DESCRIPTION:

--- Big Sandy Branch.f01 (steady flow) ---

Flow Title=Multiple
Number of Profiles=7
Profile Names=10-year,25-year,50-year,1pct_min,100-year,1pct_plu,500-year
River Rch & RM= Big Sandy Branch,Reach-1,25181
     712    1165    1583    1043    2081    4153    3560
River Rch & RM= Big Sandy Branch,Reach-1,23654
     895    1481    2026    1343    2679    5346    4639
River Rch & RM= Big Sandy Branch,Reach-1,22314
    1450    2444    3381    2261    4511    9000    7956
River Rch & RM= Big Sandy Branch,Reach-1,18277
    1723    2921    4057    2721    5429   10832    9636
River Rch & RM= Big Sandy Branch,Reach-1,16067
    1776    2996    4146    2769    5525   11024    9726
River Rch & RM= Big Sandy Branch,Reach-1,11090
    2001    3387    4696    3141    6268   12506   11066
River Rch & RM= Big Sandy Branch,Reach-1,6951
    2089    3537    4906    3282    6548   13066   11563
Boundary for River Rch & Prof#=Big Sandy Branch,Reach-1,1
Up Type=0
Dn Type=3
Dn Slope=0.005
Boundary for River Rch & Prof#=Big Sandy Branch,Reach-1,2
Up Type=0
Dn Type=3
Dn Slope=0.005
Boundary for River Rch & Prof#=Big Sandy Branch,Reach-1,3
Up Type=0
Dn Type=3
Dn Slope=0.005
Boundary for River Rch & Prof#=Big Sandy Branch,Reach-1,4
Up Type=0
Dn Type=3
Dn Slope=0.005
Boundary for River Rch & Prof#=Big Sandy Branch,Reach-1,5
Up Type=0
Dn Type=3
Dn Slope=0.005
Boundary for River Rch & Prof#=Big Sandy Branch,Reach-1,6
Up Type=0
Dn Type=3
Dn Slope=0.005
Boundary for River Rch & Prof#=Big Sandy Branch,Reach-1,7
Up Type=0
Dn Type=3
Dn Slope=0.005

--- Big Sandy Branch.g01 (geometry) ---

Geom Title=Existing Conditions
Program Version=4.10

River Reach=Big Sandy Branch,Reach-1
Reach XY= 30
        2450775.       13846475.      2451368.94     13845883.14
       2452127.3     13845519.17      2452742.05     13845058.51
      2453417.19     13844131.19      2453478.83     13843776.58
      2453822.86     13843219.03      2453828.62      13842676.5
      2454588.63     13840811.79      2455122.69     13840380.82
      2456131.17     13839967.14      2456569.17      13839477.3
      2456824.93     13838704.97      2456730.83      13837722.7
      2457338.61     13836861.76      2457616.87     13836681.07
      2457844.58     13835954.42      2458523.39     13835768.98
      2458425.77     13835385.69      2458626.76     13834536.88
       2458923.8     13834064.49      2458782.56       13833425.
      2458924.25     13833114.32      2458927.24     13832530.93
      2459273.78      13831814.5      2459332.81     13830818.81
       2459826.5     13830278.62      2460731.19     13830267.19
      2461576.56     13829378.74        2463175.       13829475.

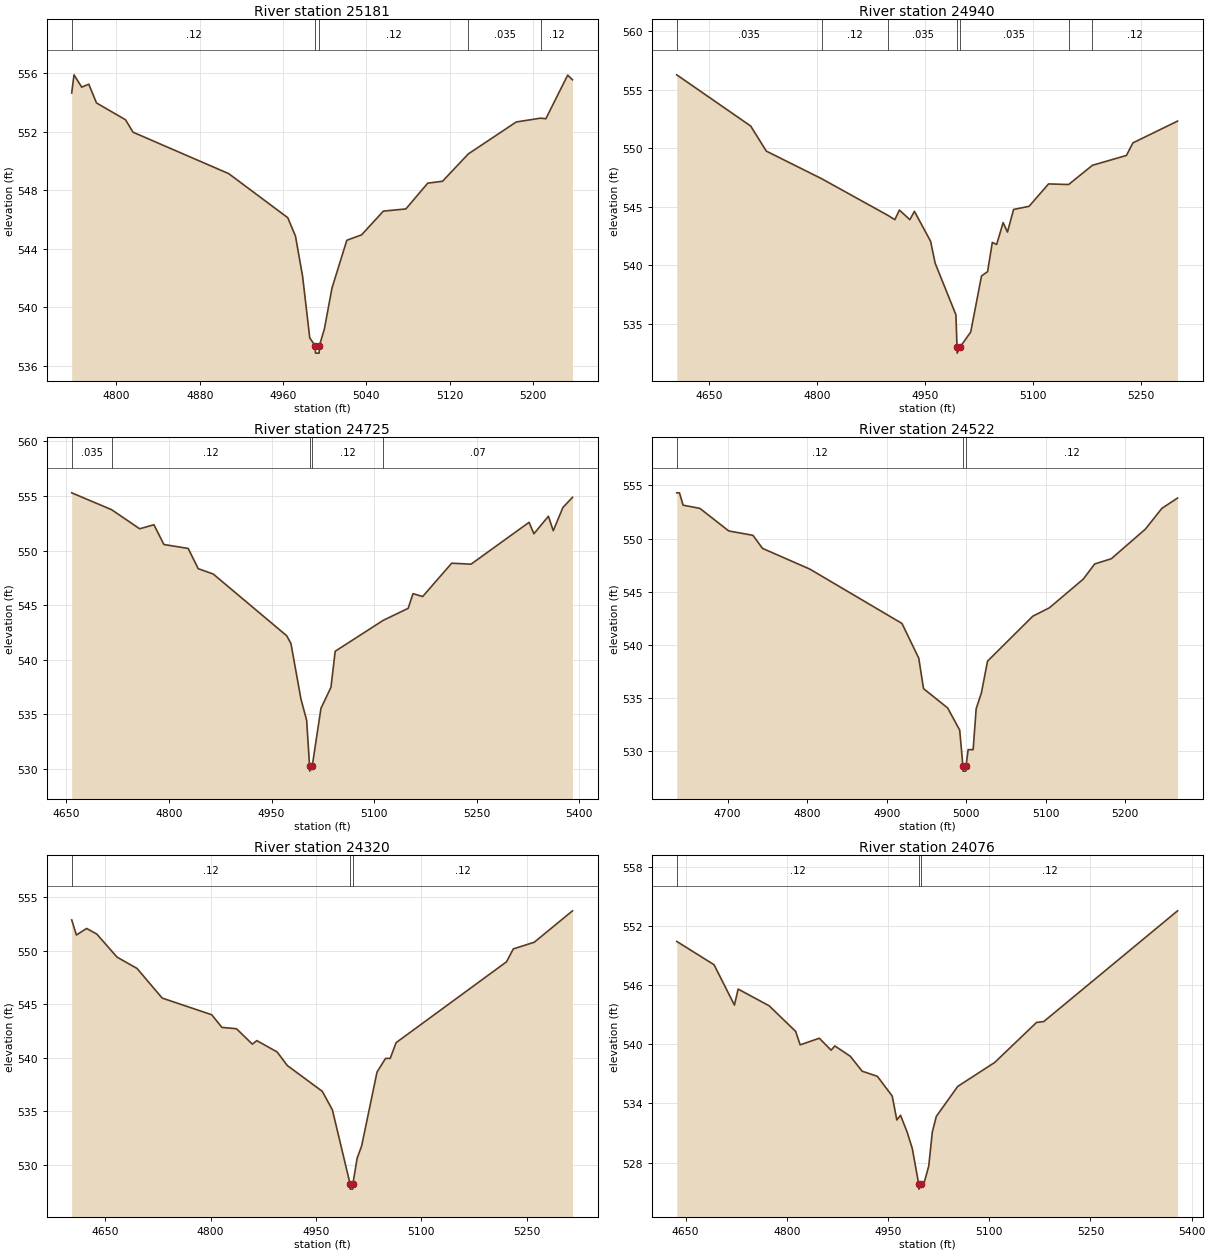
Type RM Length L Ch R = 1 ,25181   ,241,241,241
BEGIN DESCRIPTION:
X18232
END DESCRIPTION:
XS GIS Cut Line= 2
      2450950.22     13846643.01      2450624.15     13846289.54
#Sta/Elev= 30
  4757.1  554.65  4759.3  555.89  4766.7  555.05  4773.5  555.25  4780.9  553.97
  4808.8  552.82    4816  551.97  4907.9  549.14  4964.6  546.13    4972  544.87
  4978.8  542.14  4985.7  537.92  4990.9  537.38  4991.2  536.88  4994.7  536.88
  4994.9  537.38  4999.7  538.52  5007.1  541.34  5021.3  544.59  5035.5  544.96
  5056.4  546.58    5078  546.73    5099  548.49  5113.2  548.62    5138  550.49
    5184  552.67  5207.4  552.93  5212.4  552.89  5233.4  555.87    5238  555.55
#Mann= 5 ,-1 , 0
  4757.1     .12       0  4990.9     .05       0  4994.9     .12       0
    5138    .035       0  5207.4     .12       0
Bank Sta=4990.9,4994.9
XS Rating Curve= 0 ,0
Exp/Cntr=0.3,0.1

Type RM Length L Ch R = 1 ,24940   ,215,215,215
BEGIN DESCRIPTION:
Big Sandy Branch 53.0
END DESCRIPTION:
XS GIS Cut Line= 3
      2451202.72     13846601.91      2450955.74     13846294.55
      2450706.05     13846127.18
#Sta/Elev= 30
  4605.3  556.27  4707.9   551.9  4729.6  549.76  4806.8  547.39  4898.8  544.26
  4907.9  543.91  4914.3  544.73  4928.7  543.91  4935.1  544.62  4957.5  542.07
  4963.9  540.19  4992.7  535.79  4994.2  533.02  4994.4  532.52  4998.2  533.02
  5013.2  534.32  5028.2  539.11  5036.6  539.47  5043.2  541.97  5049.2  541.79
  5058.2  543.66  5064.2  542.85  5072.7  544.78  5094.2  545.05  5121.2  546.96
  5149.1  546.91  5182.1  548.55  5229.3  549.39  5238.2  550.46  5300.2  552.32
#Mann= 7 ,-1 , 0
  4605.3    .035       0  4806.8     .12       0  4898.8    .035       0
  4994.2    .035       0  4998.2    .035       0  5149.1     .07       0
  5182.1     .12       0
Bank Sta=4994.2,4998.2
XS Rating Curve= 0 ,0
Exp/Cntr=0.3,0.1

Type RM Length L Ch R = 1 ,24725   ,203,203,203
BEGIN DESCRIPTION:
X18233
END DESCRIPTION:
XS GIS Cut Line= 3
      2451348.15     13846481.17      2451103.91     13846151.86
      2450876.16      13845924.1
#Sta/Elev= 30
  4657.9  555.28  4716.2  553.74  4757.2  551.99  4778.1  552.36  4792.7  550.55
  4828.2  550.19  4842.8  548.34  4864.8  547.85  4972.2   542.2  4978.4  541.49
    4993  536.42  5001.4  534.45  5005.6  530.31  5005.9  529.81  5009.6  530.31
  5022.3  535.56  5036.9  537.48  5043.1  540.78  5113.3  543.61  5149.8  544.71
  5156.8  546.05    5171  545.79  5213.4  548.84  5241.7  548.75  5326.5  552.58
  5333.6  551.53  5354.8  553.14  5361.9  551.81    5376  553.94    5390  554.87
#Mann= 5 ,-1 , 0
  4657.9    .035       0  4716.2     .12       0  5005.6     .05       0
  5009.6     .12       0  5113.3     .07       0
Bank Sta=5005.6,5009.6
XS Rating Curve= 0 ,0
Exp/Cntr=0.3,0.1

Type RM Length L Ch R = 1 ,24522   ,202,202,202
BEGIN DESCRIPTION:
Big Sandy Branch 52.0
END DESCRIPTION:
XS GIS Cut Line= 3
      2451424.96      13846335.7        2451225.       13846025.
      2451028.55     13845854.04
#Sta/Elev= 30
    4636  554.29  4639.4  554.29    4644  553.13  4665.1  552.83  4701.4  550.71
  4731.8   550.3  4743.9  549.07  4803.3  547.13  4919.3  542.02  4940.4  538.76
  4946.4   535.9  4976.8  534.08  4991.9     532  4995.9  528.65  4996.1  528.15
  4999.6  528.15  4999.9  528.65  5002.5  530.17  5008.8  530.17  5012.6  534.01
  5019.2   535.5  5026.9  538.48  5083.8   542.7  5104.7  543.49  5147.4  546.19
  5161.7  547.61  5182.6   548.1  5225.3  550.87  5246.2  552.83  5265.9   553.8
#Mann= 3 ,-1 , 0
    4636     .12       0  4995.9     .05       0  4999.9     .12       0
Bank Sta=4995.9,4999.9
XS Rating Curve= 0 ,0
Exp/Cntr=0.3,0.1

Type RM Length L Ch R = 1 ,24320   ,244,244,244
BEGIN DESCRIPTION:
X18234
END DESCRIPTION:
XS GIS Cut Line= 3
      2451611.59     13846198.55      2451334.41     13845841.79
      2451099.24     13845726.93
#Sta/Elev= 30
    4602  552.88  4608.7  551.47  4623.2  552.08  4637.7  551.56  4666.6   549.4
  4695.1  548.34  4730.9  545.57  4801.5  544.01    4816  542.83  4836.8   542.7
  4859.4  541.26  4865.7  541.59  4894.7  540.53  4909.2  539.26    4959  536.85
  4973.4  535.12  4998.6   528.2  4998.8   527.7  5002.3   527.7  5002.6   528.2
  5008.7   530.6  5015.1  531.74    5037  538.65  5049.2  539.93  5055.8  539.93
  5064.2   541.4  5221.5  548.96  5231.2  550.17    5261  550.79  5315.5  553.73
#Mann= 3 ,-1 , 0
    4602     .12       0  4998.6     .05       0  5002.6     .12       0
Bank Sta=4998.6,5002.6
XS Rating Curve= 0 ,0
Exp/Cntr=0.3,0.1

Type RM Length L Ch R = 1 ,24076   ,422,422,422
BEGIN DESCRIPTION:
Big Sandy Branch 51.0
END DESCRIPTION:
XS GIS Cut Line= 3
      2451726.81     13846105.22        2451575.       13845775.
      2451218.21      13845647.6
#Sta/Elev= 30
  4636.8  550.42  4692.1  548.06  4722.3  543.97  4727.8  545.59  4773.7   543.9
  4813.1   541.3  4819.7  539.94  4848.1  540.61  4865.6   539.4  4871.1  539.83
  4894.1  538.78  4911.6  537.27  4934.2  536.75  4956.2  534.75    4963  532.33
  4968.5   532.8  4978.2  531.12    4986  529.42  4995.5  525.82  4995.7  525.32
  4999.5  525.82  5002.9  525.82  5010.3  527.65  5015.6  531.09  5021.5  532.69
  5053.3  535.73    5108  538.15  5170.1  542.21  5180.8   542.3  5379.1  553.52
#Mann= 3 ,-1 , 0
  4636.8     .12       0  4995.5     .05       0  4999.5     .12       0
Bank Sta=4995.5,4999.5
XS Rating Curve= 0 ,0
Exp/Cntr=0.3,0.1

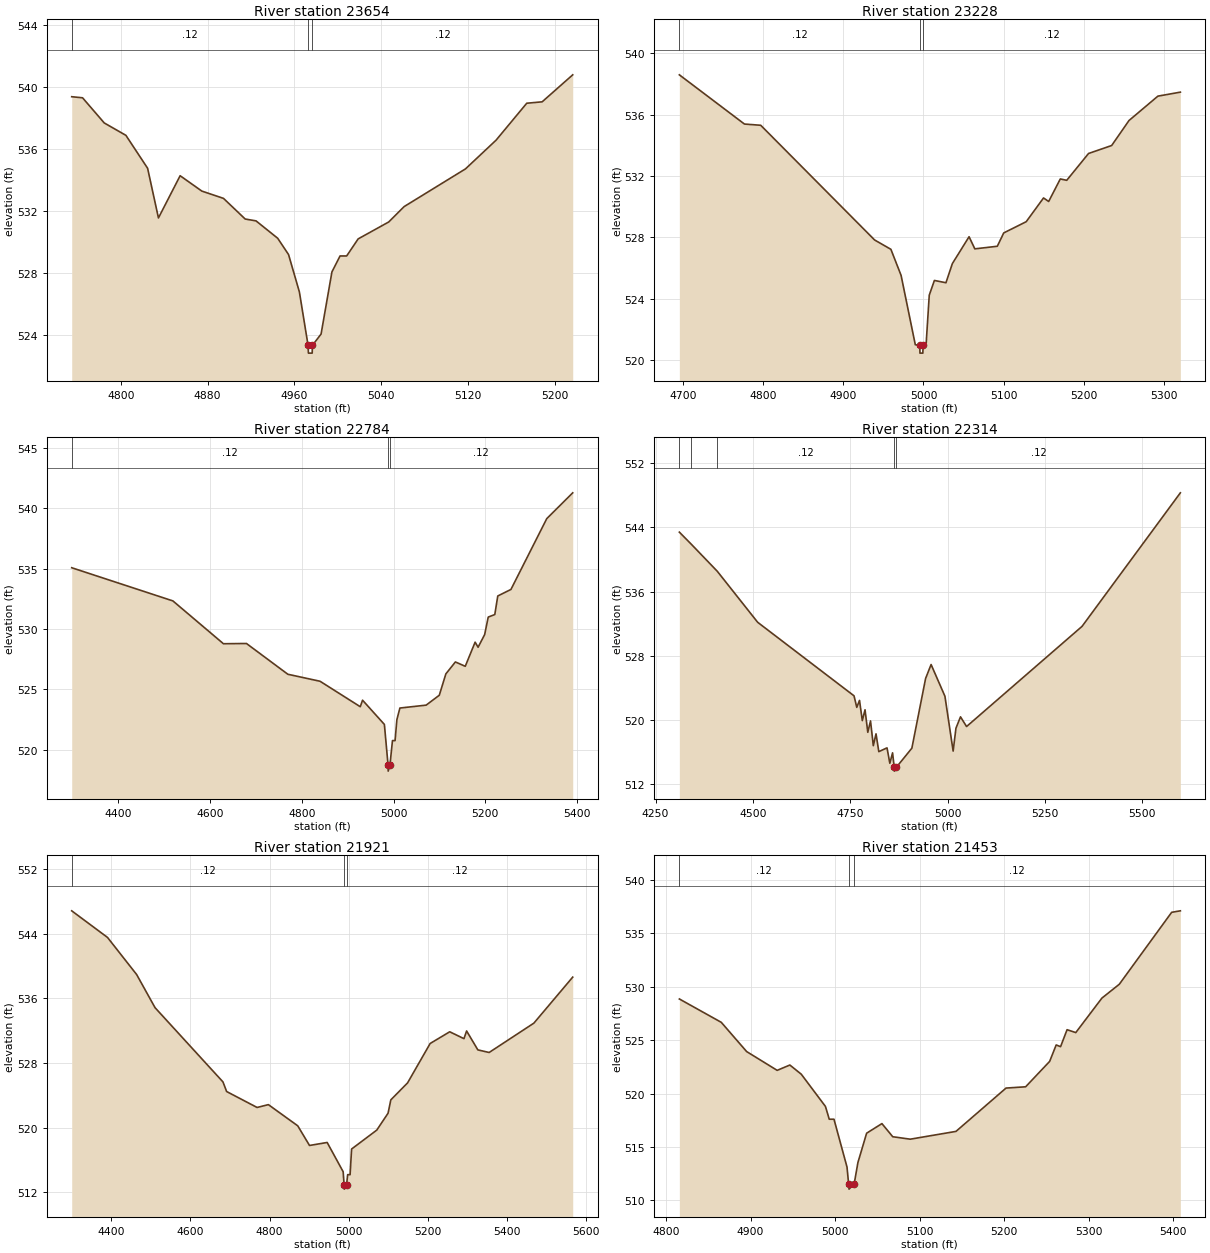
Type RM Length L Ch R = 1 ,23654   ,426,426,426
BEGIN DESCRIPTION:
Big Sandy Branch 50.0
END DESCRIPTION:
XS GIS Cut Line= 3
        2451925.     13845825.01        2451925.       13845575.
      2451775.03     13845425.03
#Sta/Elev= 30
  4754.6  539.38  4764.6  539.31  4784.6  537.69  4804.6  536.89  4824.6  534.77
  4834.6  531.57  4854.6  534.29  4874.6   533.3  4894.6  532.83  4914.6   531.5
  4924.6  531.38  4944.6  530.26  4954.6  529.21  4964.6   526.8  4972.6  523.36
  4972.9  522.86  4976.4  522.86  4976.6  523.36  4984.6  524.09  4994.6  528.09
  5002.1  529.12  5008.2  529.12  5018.8  530.22    5047  531.31  5061.2   532.3
  5117.8  534.73    5146  536.58  5174.3  538.96  5188.5  539.05  5216.7  540.79
#Mann= 3 ,-1 , 0
  4754.6     .12       0  4972.6     .05       0  4976.6     .12       0
Bank Sta=4972.6,4976.6
XS Rating Curve= 0 ,0
Exp/Cntr=0.3,0.1

Type RM Length L Ch R = 1 ,23228   ,444,444,444
BEGIN DESCRIPTION:
Big Sandy Branch 49.0
END DESCRIPTION:
XS GIS Cut Line= 3
      2452325.01     13845675.03        2452275.       13845375.
      2452075.02     13845125.02
#Sta/Elev= 30
  4695.8  538.59  4776.9  535.38  4797.2   535.3  4939.1  527.82  4959.4  527.21
  4972.1  525.51  4989.8  520.99  4995.4  520.94  4995.6  520.44  4999.2  520.44
  4999.5  520.94  5003.2  520.94  5007.2  524.22  5013.6  525.18    5028  525.03
    5036  526.28  5056.8  528.03    5064  527.24    5092  527.41    5100  528.28
    5128  529.01  5149.6  530.56    5156  530.33  5170.5   531.8  5178.5  531.71
  5205.7  533.46  5234.5  533.98  5256.1  535.61  5292.1   537.2  5320.1  537.46
#Mann= 3 ,-1 , 0
  4695.8     .12       0  4995.4     .05       0  4999.5     .12       0
Bank Sta=4995.4,4999.5
XS Rating Curve= 0 ,0
Exp/Cntr=0.3,0.1

Type RM Length L Ch R = 1 ,22784   ,470,470,470
BEGIN DESCRIPTION:
Big Sandy Branch 48.0
END DESCRIPTION:
XS GIS Cut Line= 3
        2452575.       13845825.        2452625.       13845125.
        2452375.       13844825.
#Sta/Elev= 30
  4298.2  535.07  4518.8  532.32    4629  528.77  4679.2  528.79  4769.4  526.24
  4839.6  525.66  4927.3  523.55  4932.3  524.09  4979.9  522.08  4987.9  518.71
  4988.2  518.21    4992  518.71  4997.5  520.74  5003.2  520.74  5007.1  522.47
  5013.7  523.44  5070.9  523.68  5099.6   524.5  5113.9  526.27  5134.7  527.26
  5156.2   526.9  5177.7   528.9  5184.2  528.48  5198.5  529.53  5206.3  530.98
  5220.6  531.19  5227.1  532.73  5255.8  533.27  5333.9  539.14  5390.5  541.28
#Mann= 3 ,-1 , 0
  4298.2     .12       0  4987.9     .05       0    4992     .12       0
Bank Sta=4987.9,4992
XS Rating Curve= 0 ,0
Exp/Cntr=0.3,0.1

Type RM Length L Ch R = 1 ,22314   ,393,393,393
BEGIN DESCRIPTION:
X18235
END DESCRIPTION:
XS GIS Cut Line= 3
      2453406.13     13845268.27      2452884.78     13844763.39
      2452389.13      13844500.5
#Sta/Elev= 30
    4311  543.42  4341.9   541.9  4408.4  538.54  4512.1  532.18  4759.6  523.01
  4766.7  521.57  4773.7  522.44  4780.9  519.92  4787.9  521.27    4795  518.46
    4802  519.88  4809.2  516.79  4816.1  518.27  4823.3  516.05  4844.4  516.52
  4851.6   514.6  4858.6   515.9  4862.8  514.12  4863.3  513.62  4868.7  514.12
  4908.2  516.48  4943.5  525.18  4957.6  526.91  4993.1  522.96  5014.2  516.12
  5021.4  518.97  5033.1  520.39  5048.7  519.18  5345.3  531.67  5597.8  548.32
#Mann= 5 ,-1 , 0
    4311     .12       0  4341.9    .035       0  4408.4     .12       0
  4862.8     .05       0  4868.7     .12       0
Bank Sta=4862.8,4868.7
XS Rating Curve= 0 ,0
Exp/Cntr=0.3,0.1

Type RM Length L Ch R = 1 ,21921   ,468,468,468
BEGIN DESCRIPTION:
Big Sandy Branch 47.0
END DESCRIPTION:
XS GIS Cut Line= 3
       2453760.1     13844768.87        2453125.       13844475.
      2452699.07     13844102.85
#Sta/Elev= 30
  4300.2  546.83  4390.6  543.54  4464.2  538.95  4510.7  534.85  4682.2  525.67
  4691.5  524.48  4768.4  522.51  4796.9  522.86  4871.1  520.24  4900.8  517.81
  4945.4  518.18  4985.8  514.56  4988.2  512.91  4988.7  512.41  4994.3  512.91
  4997.2   514.2  5003.3   514.2  5007.1  517.37  5070.7  519.71  5099.2   521.8
  5106.2  523.45  5148.5  525.55  5205.5  530.42  5254.9  531.87  5290.9  531.02
  5297.6  531.97    5326  529.63  5354.5  529.31  5467.5  532.94  5565.6  538.63
#Mann= 3 ,-1 , 0
  4300.2     .12       0  4988.2     .05       0  4994.3     .12       0
Bank Sta=4988.2,4994.3
XS Rating Curve= 0 ,0
Exp/Cntr=0.3,0.1

Type RM Length L Ch R = 1 ,21453   ,433,433,433
BEGIN DESCRIPTION:
Big Sandy Branch 46.0
END DESCRIPTION:
XS GIS Cut Line= 3
      2453575.01     13844225.01        2453425.       13844125.
        2453025.       13844025.
#Sta/Elev= 30
  4815.8  528.86  4865.4  526.67  4895.4  523.93  4931.5  522.17  4946.5  522.67
    4960  521.81  4988.6  518.79  4993.1  517.59  4998.7  517.59  5014.1  513.11
    5016  511.54  5016.5  511.04  5022.6  511.54    5027  513.53  5037.3  516.28
  5055.4  517.18  5068.2  515.95  5088.9  515.72    5143  516.45  5202.2  520.51
  5225.4  520.63  5253.8  523.01  5261.5  524.55  5266.7  524.39  5274.4  525.98
  5284.7  525.71  5315.6  528.94  5336.2  530.24  5398.1  536.98  5408.4  537.12
#Mann= 3 ,-1 , 0
  4815.8     .12       0    5016     .05       0  5022.6     .12       0
Bank Sta=5016,5022.6
XS Rating Curve= 0 ,0
Exp/Cntr=0.3,0.1

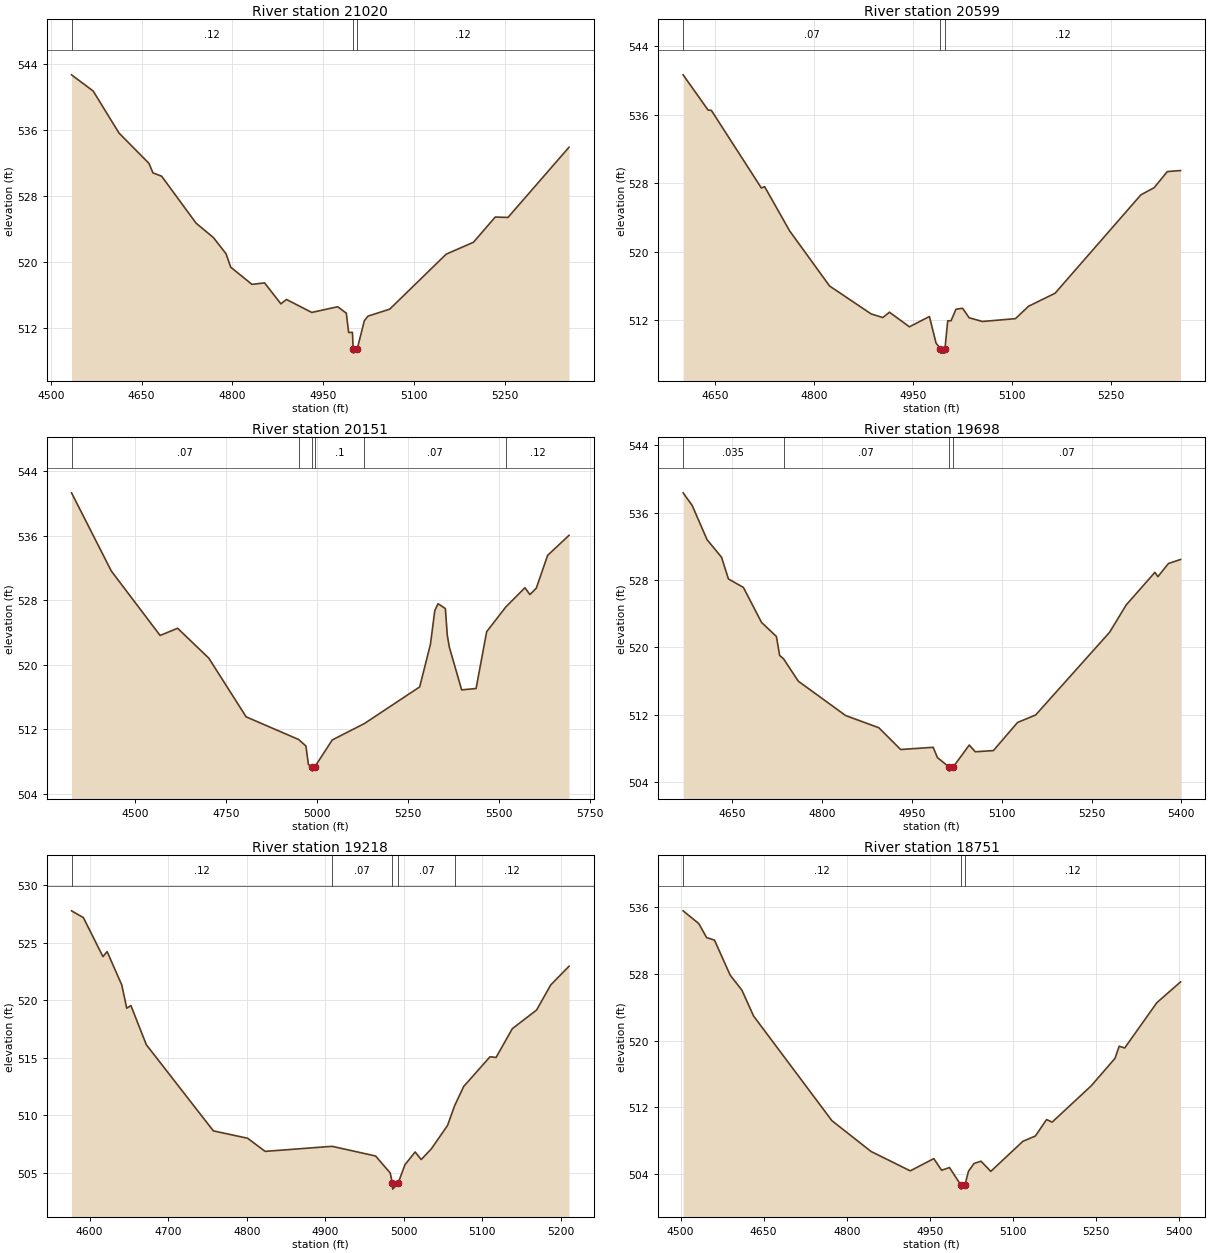
Type RM Length L Ch R = 1 ,21020   ,421,421,421
BEGIN DESCRIPTION:
Big Sandy Branch 45.0
END DESCRIPTION:
XS GIS Cut Line= 3
      2453875.03     13844025.03        2453525.       13843725.
      2453224.98     13843524.98
#Sta/Elev= 30
  4534.3  542.68    4570  540.72  4612.8  535.62  4662.2  531.95  4668.8   530.8
  4683.1   530.4  4740.1   524.7  4768.7  522.96  4789.5     521  4797.2  519.38
  4832.3  517.29  4853.2  517.47  4880.1  514.93  4889.4  515.46  4931.1  513.89
  4973.9  514.58  4988.2   513.8    4992  511.47  4998.3  511.47  4999.5  509.46
    5000  508.96  5006.2  509.46  5017.9  512.88  5023.9  513.44  5059.9  514.29
  5153.1  520.95  5198.1  522.39  5234.2  525.45  5255.2   525.4  5355.9   533.9
#Mann= 3 ,-1 , 0
  4534.3     .12       0  4999.5     .05       0  5006.2     .12       0
Bank Sta=4999.5,5006.2
XS Rating Curve= 0 ,0
Exp/Cntr=0.3,0.1

Type RM Length L Ch R = 1 ,20599   ,448,448,448
BEGIN DESCRIPTION:
Big Sandy Branch 44.0
END DESCRIPTION:
XS GIS Cut Line= 3
      2454124.97       13843425.        2453725.       13843375.
      2453374.98       13843375.
#Sta/Elev= 30
  4601.7  540.64  4639.5  536.53  4644.5  536.49  4720.1  527.45  4725.1   527.6
  4762.9  522.45  4823.4  516.02  4886.4  512.76    4904  512.34  4914.1  512.96
  4944.3  511.26  4974.6  512.46  4984.6  509.37  4991.3  508.69  4991.8  508.19
  4997.6  508.19  4998.1  508.69  5002.3  511.96  5007.3  511.96  5014.8  513.31
  5024.8  513.42  5034.8  512.31  5054.8  511.88  5104.8  512.21  5124.8  513.66
  5164.8  515.17  5294.8  526.65  5314.8  527.48  5334.8  529.36  5354.8  529.48
#Mann= 3 ,-1 , 0
  4601.7     .07       0  4991.3     .05       0  4998.1     .12       0
Bank Sta=4991.3,4998.1
XS Rating Curve= 0 ,0
Exp/Cntr=0.3,0.1

Type RM Length L Ch R = 1 ,20151   ,453,453,453
BEGIN DESCRIPTION:
Big Sandy Branch 43.0
END DESCRIPTION:
XS GIS Cut Line= 3
      2454432.45     13843125.22        2453775.       13842975.
      2453108.57     13842790.86
#Sta/Elev= 30
  4325.5  541.29  4434.7  531.61  4568.7  523.63  4616.8  524.52  4702.4  520.82
    4805  513.55  4948.9  510.75  4969.1  509.94  4975.9  507.65  4986.2  507.33
  4986.7  506.83    4993  507.33  5041.4  510.69  5129.6  512.72  5281.5  517.26
  5311.1  522.56  5322.9  526.71  5331.9  527.56    5352  526.96  5357.2  523.67
    5363  522.16  5396.7  516.89  5436.3  517.06  5465.4   524.1    5518  527.16
  5570.5  529.54    5584  528.69  5601.6  529.48  5632.8  533.55  5691.3  536.02
#Mann= 6 ,-1 , 0
  4325.5     .07       0  4948.9      .1       0  4986.2     .05       0
    4993      .1       0  5129.6     .07       0    5518     .12       0
Bank Sta=4986.2,4993
XS Rating Curve= 0 ,0
Exp/Cntr=0.3,0.1

Type RM Length L Ch R = 1 ,19698   ,480,480,480
BEGIN DESCRIPTION:
Big Sandy Branch 42.0
END DESCRIPTION:
XS GIS Cut Line= 3
      2454324.99       13842725.        2453925.       13842575.
        2453525.       13842525.
#Sta/Elev= 30
  4568.3  538.35  4583.4  536.85  4608.3  532.78  4632.4   530.7  4643.9  528.12
  4668.9  527.11  4699.1  522.96    4724  521.28  4729.4  519.03  4735.9  518.63
  4760.5  515.97  4839.7  511.88  4894.9  510.44  4931.4  507.85  4985.7  508.11
  4992.8  506.89    5012  505.78  5012.5  505.28  5019.2  505.78  5045.9  508.38
    5056  507.58  5086.2  507.72  5126.5  511.06  5156.7  511.95  5280.2  521.78
  5307.9  525.03  5355.8   528.9  5360.8  528.39  5378.4  529.95  5398.6  530.43
#Mann= 4 ,-1 , 0
  4568.3    .035       0  4735.9     .07       0    5012     .05       0
  5019.2     .07       0
Bank Sta=5012,5019.2
XS Rating Curve= 0 ,0
Exp/Cntr=0.3,0.1

Type RM Length L Ch R = 1 ,19218   ,467,467,467
BEGIN DESCRIPTION:
Big Sandy Branch 41.0
END DESCRIPTION:
XS GIS Cut Line= 3
      2454424.96     13842274.98        2454025.       13842125.
      2453825.01       13842075.
#Sta/Elev= 30
    4577  527.78  4592.1  527.19    4617   523.8  4622.3  524.24    4641  521.33
  4647.3  519.32  4652.6  519.55  4672.2  516.15  4757.6  508.66  4801.2  508.02
  4823.5  506.88  4908.7  507.32  4964.1  506.48  4982.8     505  4985.4   504.1
  4985.9   503.6  4992.7   504.1  5001.5  505.72  5014.5  506.83  5022.2  506.17
  5035.1   507.1  5055.7  509.13  5064.8  510.86  5076.3  512.52  5109.8   515.1
  5117.5  515.04  5138.2  517.54  5169.1  519.16  5187.1  521.34  5210.3  522.96
#Mann= 5 ,-1 , 0
    4577     .12       0  4908.7     .07       0  4985.4     .05       0
  4992.7     .07       0  5064.8     .12       0
Bank Sta=4985.4,4992.7
XS Rating Curve= 0 ,0
Exp/Cntr=0.3,0.1

Type RM Length L Ch R = 1 ,18751   ,474,474,474
BEGIN DESCRIPTION:
Big Sandy Branch 40.0
END DESCRIPTION:
XS GIS Cut Line= 3
      2454575.02     13842075.02        2454225.       13841725.
      2453825.01       13841775.
#Sta/Elev= 30
  4504.6  535.57  4532.9  534.04    4547  532.36  4561.2  532.06  4589.5  527.87
  4610.7  526.06  4631.9  522.95  4773.3  510.41    4844  506.72  4914.7   504.4
  4957.2  505.87  4971.3  504.47  4985.5   504.8    5006  502.71  5006.5  502.21
  5013.4  502.71  5019.8  504.35  5029.8  505.28  5042.4  505.56  5060.1  504.34
    5118  507.94  5140.7  508.58  5160.8  510.55  5170.9  510.24  5241.5   514.6
  5284.3  517.88  5291.9  519.34  5301.9  519.13  5359.9  524.56  5402.7  527.05
#Mann= 3 ,-1 , 0
  4504.6     .12       0    5006     .05       0  5013.4     .12       0
Bank Sta=5006,5013.4
XS Rating Curve= 0 ,0
Exp/Cntr=0.3,0.1

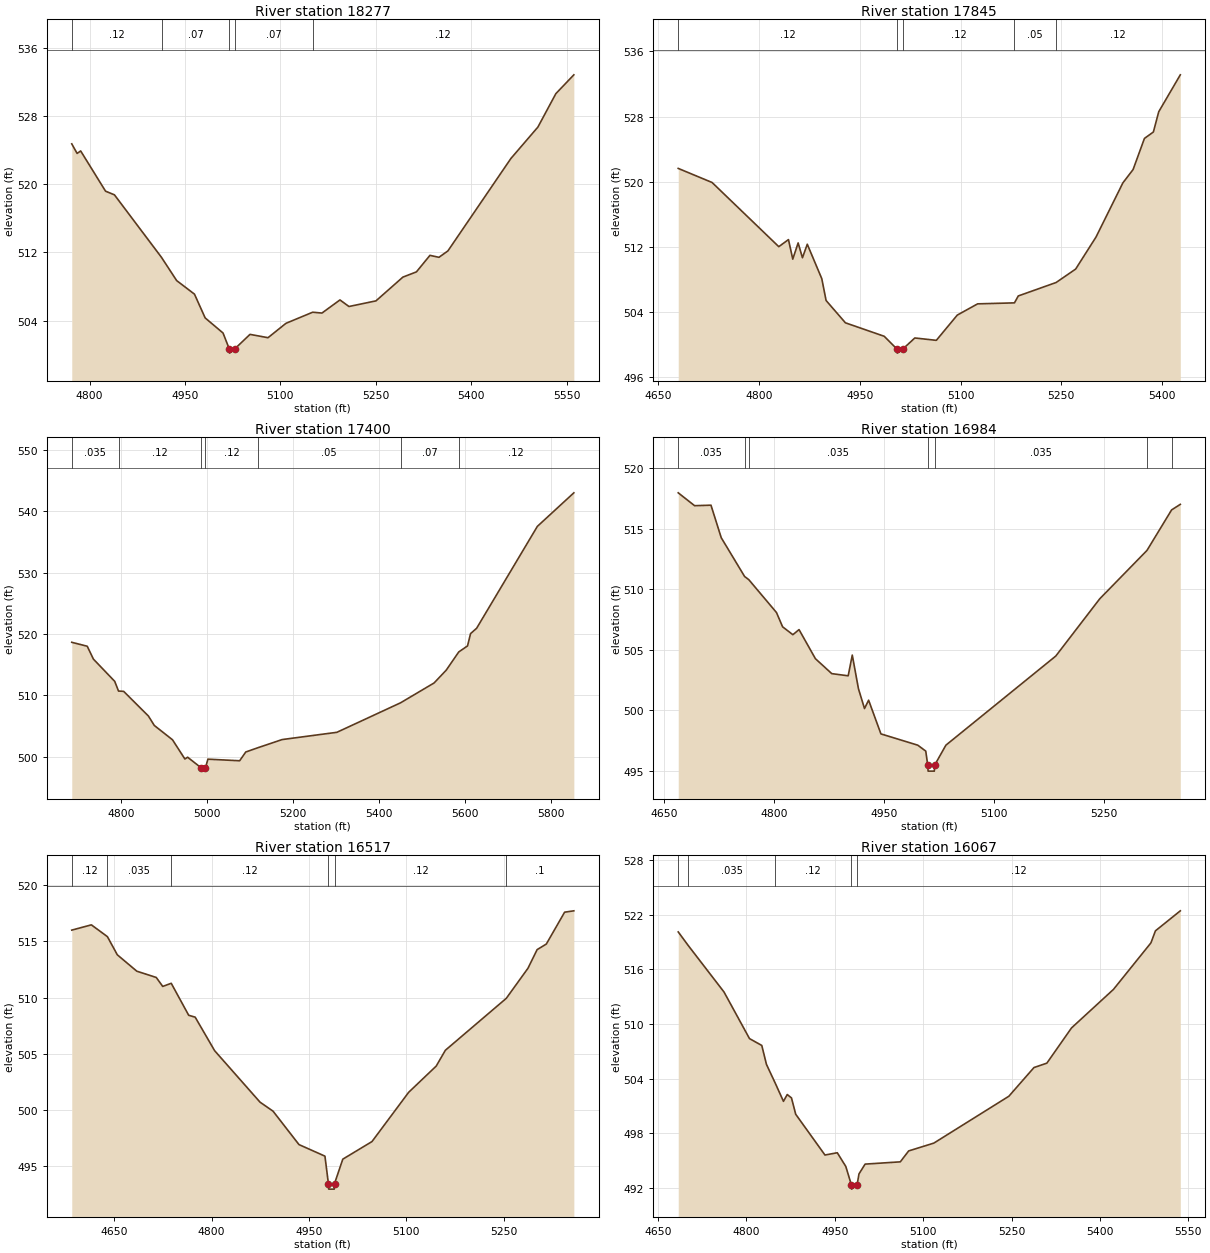
Type RM Length L Ch R = 1 ,18277   ,432,432,432
BEGIN DESCRIPTION:
Big Sandy Branch 39.0
END DESCRIPTION:
XS GIS Cut Line= 3
      2454625.03     13841425.02        2454425.       13841325.
      2454025.02     13840925.02
#Sta/Elev= 30
    4772  524.73  4780.4  523.61    4786   523.9  4825.1  519.18  4839.1  518.75
  4913.1  511.41  4936.9  508.69  4964.9   507.1  4981.7  504.31  5009.8  502.54
  5019.6  500.68  5020.1  500.18  5028.3  500.68  5052.2  502.38  5080.5  501.99
  5108.8  503.68  5150.8  504.98  5165.3  504.88  5193.6  506.42  5207.8  505.65
  5250.2  506.31  5292.6   509.1  5313.8  509.71  5335.1  511.65  5349.2  511.42
  5363.3  512.17  5462.3  523.01  5504.8   526.7    5533  530.62  5561.3  532.83
#Mann= 5 ,-1 , 0
    4772     .12       0  4913.1     .07       0  5019.6     .05       0
  5028.3     .07       0  5150.8     .12       0
Bank Sta=5019.6,5028.3
XS Rating Curve= 0 ,0
Exp/Cntr=0.3,0.1

Type RM Length L Ch R = 1 ,17845   ,445,445,445
BEGIN DESCRIPTION:
Big Sandy Branch 38.0
END DESCRIPTION:
XS GIS Cut Line= 3
      2454775.01     13841125.01        2454525.       13840925.
      2454124.97     13840774.99
#Sta/Elev= 30
  4679.8  521.63  4730.2   519.9  4829.5  512.02  4843.9  512.89  4850.3  510.49
  4858.3  512.48  4864.7  510.66  4871.9  512.32  4893.5  508.09  4899.9  505.41
  4928.7  502.67  4986.4  501.02  5005.4  499.45  5005.9  498.95  5014.1  499.45
    5032  500.81    5064  500.52  5095.2  503.62  5125.5     505  5180.3  505.12
    5186  505.97  5242.3  507.62  5271.4  509.27  5301.7   513.2  5341.7  519.85
  5356.9  521.49  5373.8  525.31  5387.1   526.1  5395.1  528.59  5427.2  533.12
#Mann= 5 ,-1 , 0
  4679.8     .12       0  5005.4     .05       0  5014.1     .12       0
  5180.3     .05       0  5242.3     .12       0
Bank Sta=5005.4,5014.1
XS Rating Curve= 0 ,0
Exp/Cntr=0.3,0.1

Type RM Length L Ch R = 1 ,17400   ,416,416,416
BEGIN DESCRIPTION:
Big Sandy Branch 37.0
END DESCRIPTION:
XS GIS Cut Line= 3
      2455074.99     13840824.99        2454825.       13840625.
      2454224.98     13840024.98
#Sta/Elev= 30
  4685.2  518.66  4721.2  518.02  4735.6  515.92  4785.2  512.29    4794  510.71
    4806  510.66  4863.7  506.63  4877.3   505.1  4919.7  502.76  4948.5  499.63
  4954.9  499.92  4987.1  498.15  4987.6  497.65  4995.8  497.65  4996.3  498.15
  5002.1   499.6    5076  499.34  5090.2  500.77  5118.2  501.46    5175   502.8
  5302.3  503.98  5450.5  508.79  5528.6  512.03  5556.9  514.12    5586  517.09
  5606.4  518.07  5613.5  520.08  5627.6  520.95    5769  537.57  5853.9  543.04
#Mann= 7 ,-1 , 0
  4685.2    .035       0    4794     .12       0  4987.1     .05       0
  4996.3     .12       0  5118.2     .05       0  5450.5     .07       0
    5586     .12       0
Bank Sta=4987.1,4996.3
XS Rating Curve= 0 ,0
Exp/Cntr=0.3,0.1

Type RM Length L Ch R = 1 ,16984   ,467,467,467
BEGIN DESCRIPTION:
Big Sandy Branch 36.0
END DESCRIPTION:
XS GIS Cut Line= 3
      2455274.99     13840674.99        2455125.       13840375.
        2455125.     13840024.99
#Sta/Elev= 30
  4668.9  517.95  4691.2  516.89  4713.6  516.93  4727.6  514.25  4759.5  511.05
  4765.2  510.79    4803  508.08  4811.4   506.9  4825.4  506.25  4833.8  506.67
  4856.2  504.27  4878.5  503.04  4900.9  502.86  4906.5  504.57  4914.9   501.8
  4923.2  500.16  4928.8  500.85  4945.6  498.07  4995.9  497.14  5006.8  496.65
  5009.5   495.5    5010     495  5018.5     495    5019   495.5  5034.3  497.14
  5184.3  504.49  5244.3  509.21  5308.8   513.2  5342.4  516.54  5354.3     517
#Mann= 7 ,-1 , 0
  4668.9    .035       0  4759.5     .12       0  4765.2    .035       0
  5009.5    .035       0    5019    .035       0  5308.8      .1       0
  5342.4     .07       0
Bank Sta=5009.5,5019
XS Rating Curve= 0 ,0
Exp/Cntr=0.3,0.1

Type RM Length L Ch R = 1 ,16517   ,450,450,450
BEGIN DESCRIPTION:
Big Sandy Branch 35.0
END DESCRIPTION:
XS GIS Cut Line= 3
      2455527.27     13840595.22        2455525.       13840175.
      2455274.99     13839924.99
#Sta/Elev= 30
  4584.5  516.01  4614.7  516.48  4639.4  515.43  4654.7  513.81  4684.7  512.35
  4714.7  511.79  4724.7  510.99  4737.8  511.27  4764.7  508.42  4774.7  508.25
  4804.7  505.26  4874.7  500.67  4894.7  499.87  4934.7  496.89  4974.7  495.86
    4980  493.42  4980.5  492.92    4989  492.92  4989.5  493.42  5002.2  495.59
  5047.2  497.16  5103.7  501.55  5146.2  503.89  5160.3   505.3  5254.2  509.93
  5287.6  512.61  5301.7  514.27  5315.9  514.77  5344.1  517.61  5358.3  517.73
#Mann= 6 ,-1 , 0
  4584.5     .12       0  4639.4    .035       0  4737.8     .12       0
    4980     .05       0  4989.5     .12       0  5254.2      .1       0
Bank Sta=4980,4989.5
XS Rating Curve= 0 ,0
Exp/Cntr=0.3,0.1

Type RM Length L Ch R = 1 ,16067   ,466,466,466
BEGIN DESCRIPTION:
Big Sandy Branch 34.0
END DESCRIPTION:
XS GIS Cut Line= 3
      2456125.01     13840275.02        2455925.       13840025.
      2455574.99     13839624.99
#Sta/Elev= 30
  4684.6  520.13  4701.4  518.65  4762.3  513.52  4805.5   508.4  4826.3  507.65
  4834.3  505.56  4849.4  503.47  4863.1   501.5  4869.5  502.25  4876.7  501.88
  4883.9  500.08  4933.5   495.6  4954.4  495.85  4968.8  494.35  4978.2  492.35
  4978.7  491.85  4988.1  492.35  4991.2  493.52  5001.6   494.6  5061.3  494.85
  5075.5  496.05  5118.2  496.91  5245.4  502.06  5288.1  505.22  5309.9   505.7
  5351.7  509.57  5422.9  513.81  5486.5  518.93  5494.1  520.25  5536.3  522.45
#Mann= 5 ,-1 , 0
  4684.6     .12       0  4701.4    .035       0  4849.4     .12       0
  4978.2     .05       0  4988.1     .12       0
Bank Sta=4978.2,4988.1
XS Rating Curve= 0 ,0
Exp/Cntr=0.3,0.1

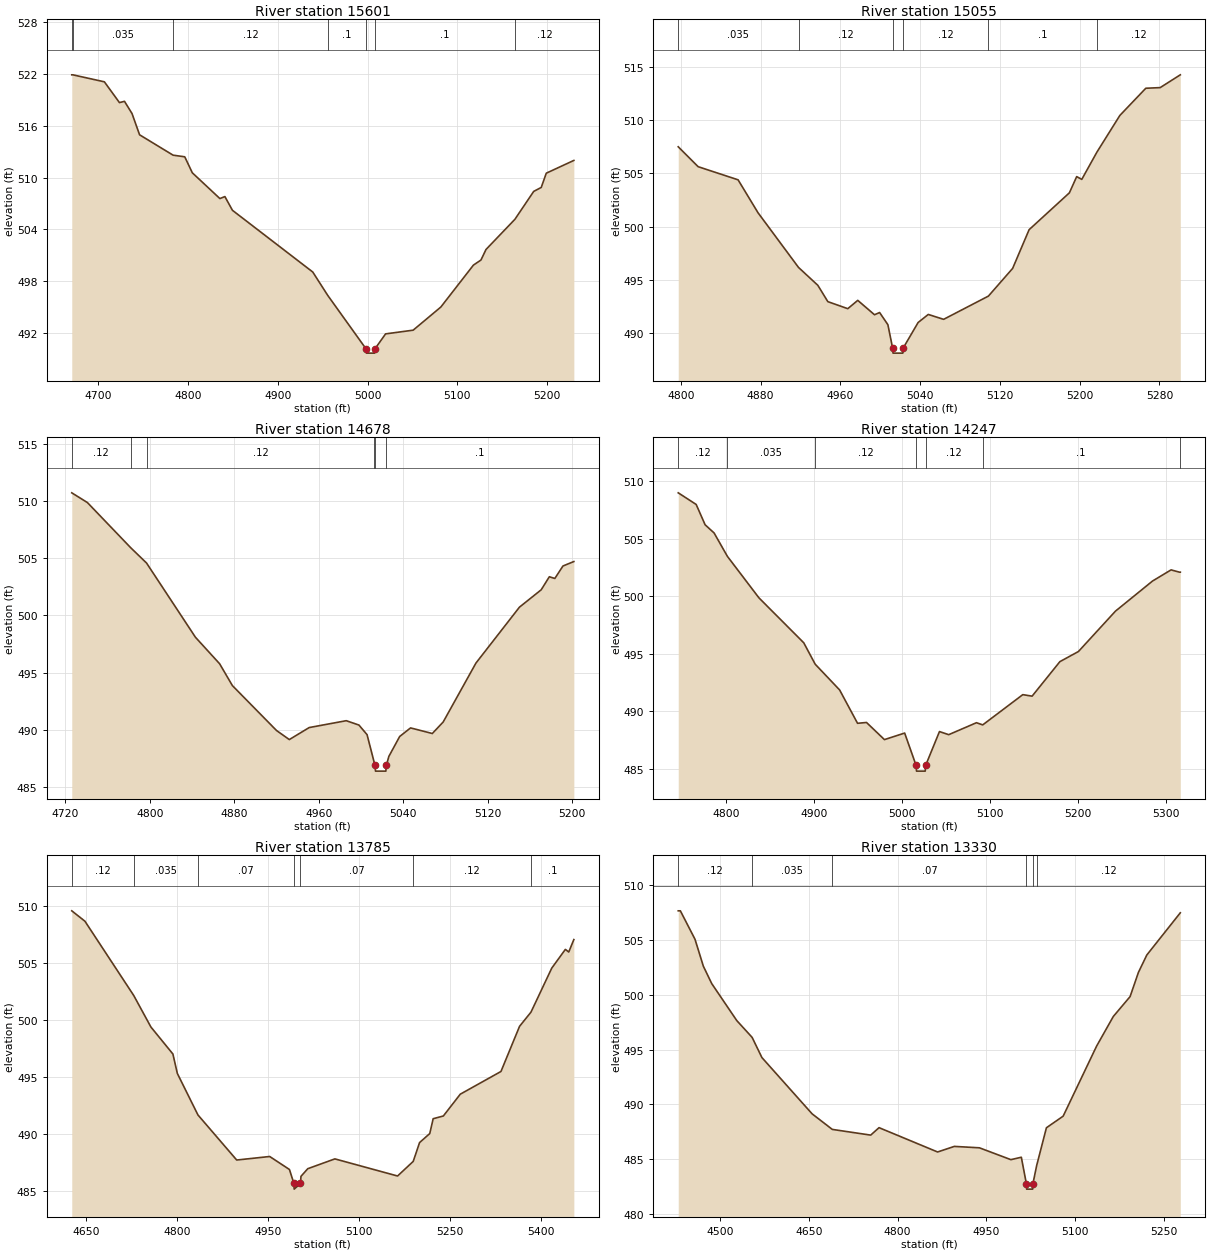
Type RM Length L Ch R = 1 ,15601   ,546,546,546
BEGIN DESCRIPTION:
Big Sandy Branch 33.0
END DESCRIPTION:
XS GIS Cut Line= 3
        2456425.     13840074.99        2456275.       13839775.
        2456175.     13839575.01
#Sta/Elev= 30
  4670.7  521.91  4671.9  521.91    4707   521.1  4723.8  518.69  4729.4  518.84
  4737.8  517.42  4746.2  514.96  4783.5   512.6  4796.5  512.41  4804.9  510.56
  4835.6  507.57  4841.2   507.8  4849.6  506.21    4939  499.06  4955.7  496.35
  4998.3  490.16  4998.8  489.66  5007.8  489.66  5008.3  490.16  5020.1  491.89
  5050.8  492.32  5081.6     495  5117.9  499.86  5126.3  500.45  5131.9  501.67
  5164.1  505.17    5185   508.4  5193.4  508.86    5199  510.51  5229.7  511.99
#Mann= 7 ,-1 , 0
  4670.7     .07       0  4671.9    .035       0  4783.5     .12       0
  4955.7      .1       0  4998.3     .05       0  5008.3      .1       0
  5164.1     .12       0
Bank Sta=4998.3,5008.3
XS Rating Curve= 0 ,0
Exp/Cntr=0.3,0.1

Type RM Length L Ch R = 1 ,15055   ,377,377,377
BEGIN DESCRIPTION:
Big Sandy Branch 32.0
END DESCRIPTION:
XS GIS Cut Line= 3
      2456824.95       13839375.      2456635.85      13839371.4
      2456325.03       13839325.
#Sta/Elev= 30
  4797.5  507.49  4817.5  505.62  4857.5  504.39  4877.5   501.3  4918.1  496.17
  4937.5  494.49  4947.5  492.96  4967.5   492.3  4977.5  493.08  4994.3  491.73
  4999.4  491.94  5007.7   490.8  5012.4  488.63  5012.9  488.13  5022.7  488.13
  5023.2  488.63    5038     491  5048.2  491.76  5063.6   491.3  5108.5  493.48
  5132.8  496.08  5149.3  499.71  5189.7  503.17    5197  504.69  5202.1  504.43
  5217.3  506.99  5240.3  510.43  5266.3  512.98  5280.7  513.04  5300.9  514.24
#Mann= 6 ,-1 , 0
  4797.5    .035       0  4918.1     .12       0  5012.4     .05       0
  5023.2     .12       0  5108.5      .1       0  5217.3     .12       0
Bank Sta=5012.4,5023.2
XS Rating Curve= 0 ,0
Exp/Cntr=0.3,0.1

Type RM Length L Ch R = 1 ,14678   ,431,431,431
BEGIN DESCRIPTION:
Big Sandy Branch 31.0
END DESCRIPTION:
XS GIS Cut Line= 3
      2456975.01     13839125.01        2456725.       13839025.
      2456525.03     13838975.01
#Sta/Elev= 30
  4726.1  510.72  4740.9  509.87    4782  505.91  4796.9  504.58  4843.2  498.09
  4866.1  495.77  4878.2  493.86    4920  489.93  4932.1  489.14  4950.9  490.19
    4986  490.79    4998  490.41  5005.7  489.57  5012.5  487.13  5013.2  486.88
  5013.7  486.38  5023.5  486.38    5024  486.88  5026.3  487.66  5036.6  489.41
  5046.9  490.16  5067.5  489.67  5077.8  490.68  5108.8  495.83    5150  500.72
  5170.6  502.24  5178.3  503.38  5183.5  503.23  5191.2  504.32  5201.5  504.71
#Mann= 6 ,-1 , 0
  4726.1     .12       0    4782    .035       0  4796.9     .12       0
  5012.5      .1       0  5013.2     .05       0    5024      .1       0
Bank Sta=5013.2,5024
XS Rating Curve= 0 ,0
Exp/Cntr=0.3,0.1

Type RM Length L Ch R = 1 ,14247   ,462,462,462
BEGIN DESCRIPTION:
Big Sandy Branch 30.0
END DESCRIPTION:
XS GIS Cut Line= 3
      2457075.04     13838675.01        2456825.       13838625.
      2456525.02     13838724.99
#Sta/Elev= 30
  4745.1     509  4765.5  507.99  4775.7  506.22  4785.9  505.51    4801  503.48
  4836.9  499.87  4887.9  495.96  4900.9   494.1  4928.7  491.86  4949.1  488.96
  4959.3  489.03  4979.7  487.54  5002.7  488.11  5015.7   485.3  5016.2   484.8
  5026.1   484.8  5026.6   485.3  5042.3  488.24  5052.8  487.97  5084.4  489.01
  5091.5  488.82  5137.1  491.45  5147.7  491.32  5179.3  494.32  5200.4   495.2
  5242.5  498.71  5284.7  501.33  5305.8   502.3  5315.4   502.1  5316.3   502.1
#Mann= 7 ,-1 , 0
  4745.1     .12       0    4801    .035       0  4900.9     .12       0
  5015.7     .05       0  5026.6     .12       0  5091.5      .1       0
  5315.4     .12       0
Bank Sta=5015.7,5026.6
XS Rating Curve= 0 ,0
Exp/Cntr=0.3,0.1

Type RM Length L Ch R = 1 ,13785   ,455,455,455
BEGIN DESCRIPTION:
Big Sandy Branch 29.0
END DESCRIPTION:
XS GIS Cut Line= 3
      2457124.98     13838324.99        2456775.       13838175.
      2456374.98     13838375.01
#Sta/Elev= 30
  4626.3  509.56    4648  508.65  4728.5  502.14  4756.8  499.38  4793.1  497.01
  4800.4  495.31  4834.4  491.67  4898.3  487.72  4952.7  488.03  4985.3  486.89
  4992.6  485.67  4993.1  485.17  5003.5  485.67  5004.3  486.29  5015.5  486.96
  5060.2  487.82  5163.6  486.32  5189.4   487.6  5199.9  489.25  5216.7  490.04
  5222.3  491.34  5239.1  491.58    5267  493.49  5334.1  495.48  5364.8  499.44
  5383.6  500.68  5417.9  504.54  5440.3  506.18  5445.9  505.95  5454.3  507.04
#Mann= 7 ,-1 , 0
  4626.3     .12       0  4728.5    .035       0  4834.4     .07       0
  4992.6     .05       0  5003.5     .07       0  5189.4     .12       0
  5383.6      .1       0
Bank Sta=4992.6,5003.5
XS Rating Curve= 0 ,0
Exp/Cntr=0.3,0.1

Type RM Length L Ch R = 1 ,13330   ,443,443,443
BEGIN DESCRIPTION:
Big Sandy Branch 28.0
END DESCRIPTION:
XS GIS Cut Line= 3
      2457125.02     13838175.02        2456725.       13837775.
      2456524.97     13837574.97
#Sta/Elev= 30
  4429.2  507.67  4432.8  507.67  4457.5  505.08  4471.7  502.61  4485.8  501.03
  4528.2  497.65  4554.1  496.12  4570.6  494.28  4655.5  489.14  4689.6  487.72
  4754.5   487.2  4768.6  487.88  4867.6  485.66  4895.9  486.17  4938.3  486.04
  4991.4  484.96  5009.1  485.18  5017.6  482.77  5018.1  482.27  5028.2  482.27
  5028.7  482.77  5035.1  484.44  5051.5  487.87  5079.8  488.93  5136.3  495.32
  5164.6  498.03  5192.9  499.84    5207  502.05  5221.2  503.64  5277.8  507.49
#Mann= 6 ,-1 , 0
  4429.2     .12       0  4554.1    .035       0  4689.6     .07       0
  5017.6     .05       0  5028.7     .07       0  5035.1     .12       0
Bank Sta=5017.6,5028.7
XS Rating Curve= 0 ,0
Exp/Cntr=0.3,0.1