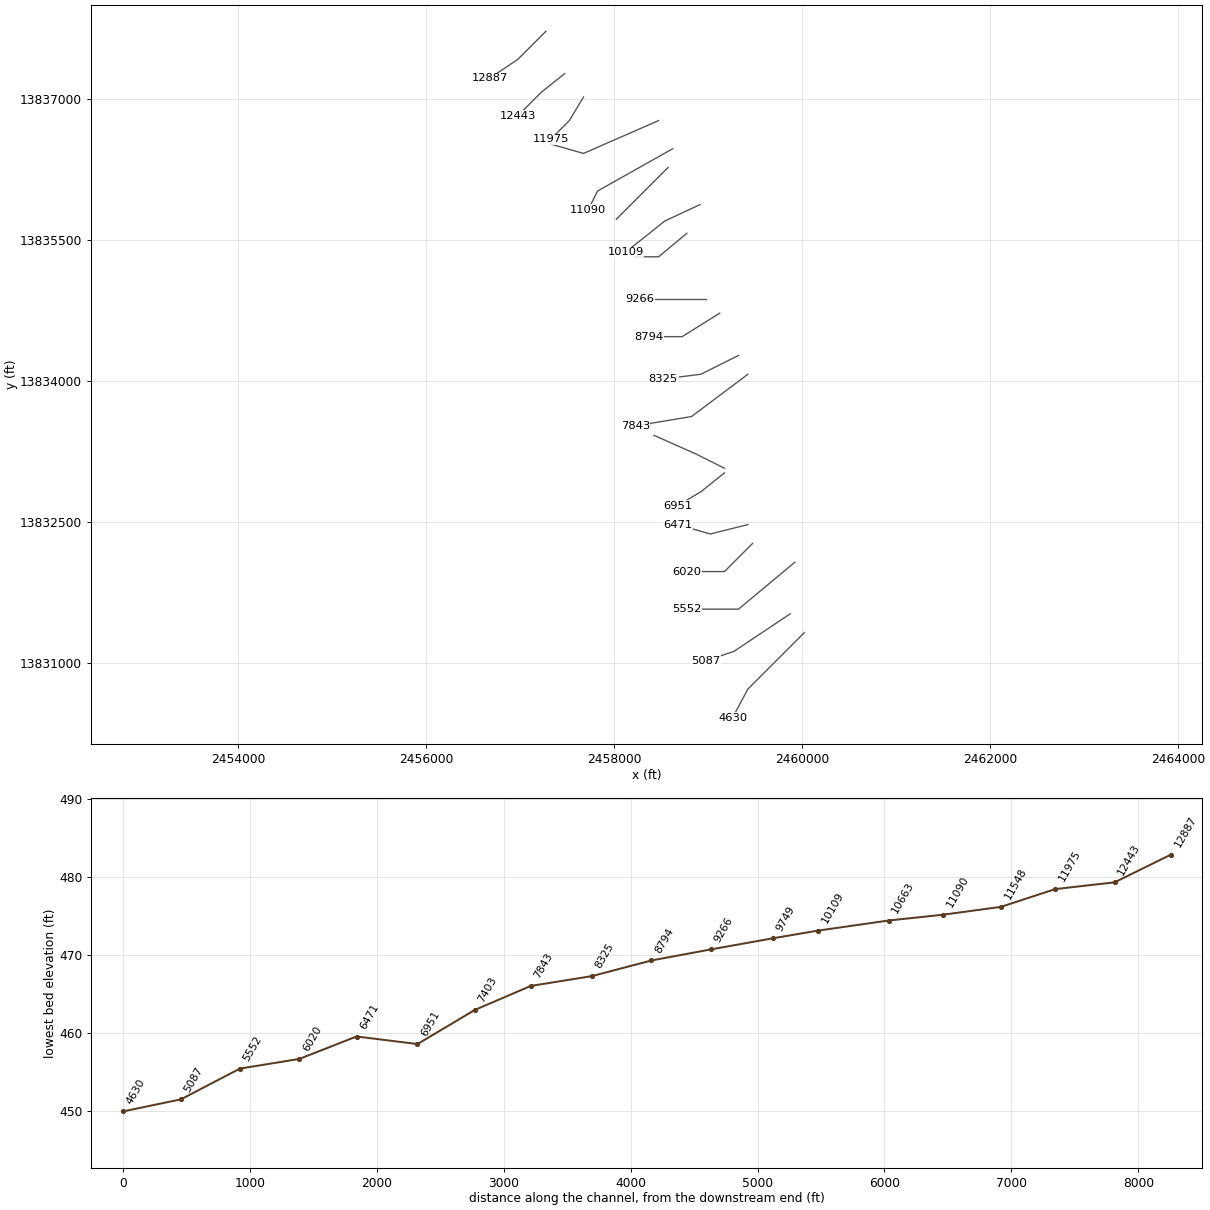
HEC-RAS study Big Sandy Branch.prj: Big Sandy Branch Base Level Engineering

--- Big Sandy Branch.g01 (geometry) --- (continued)

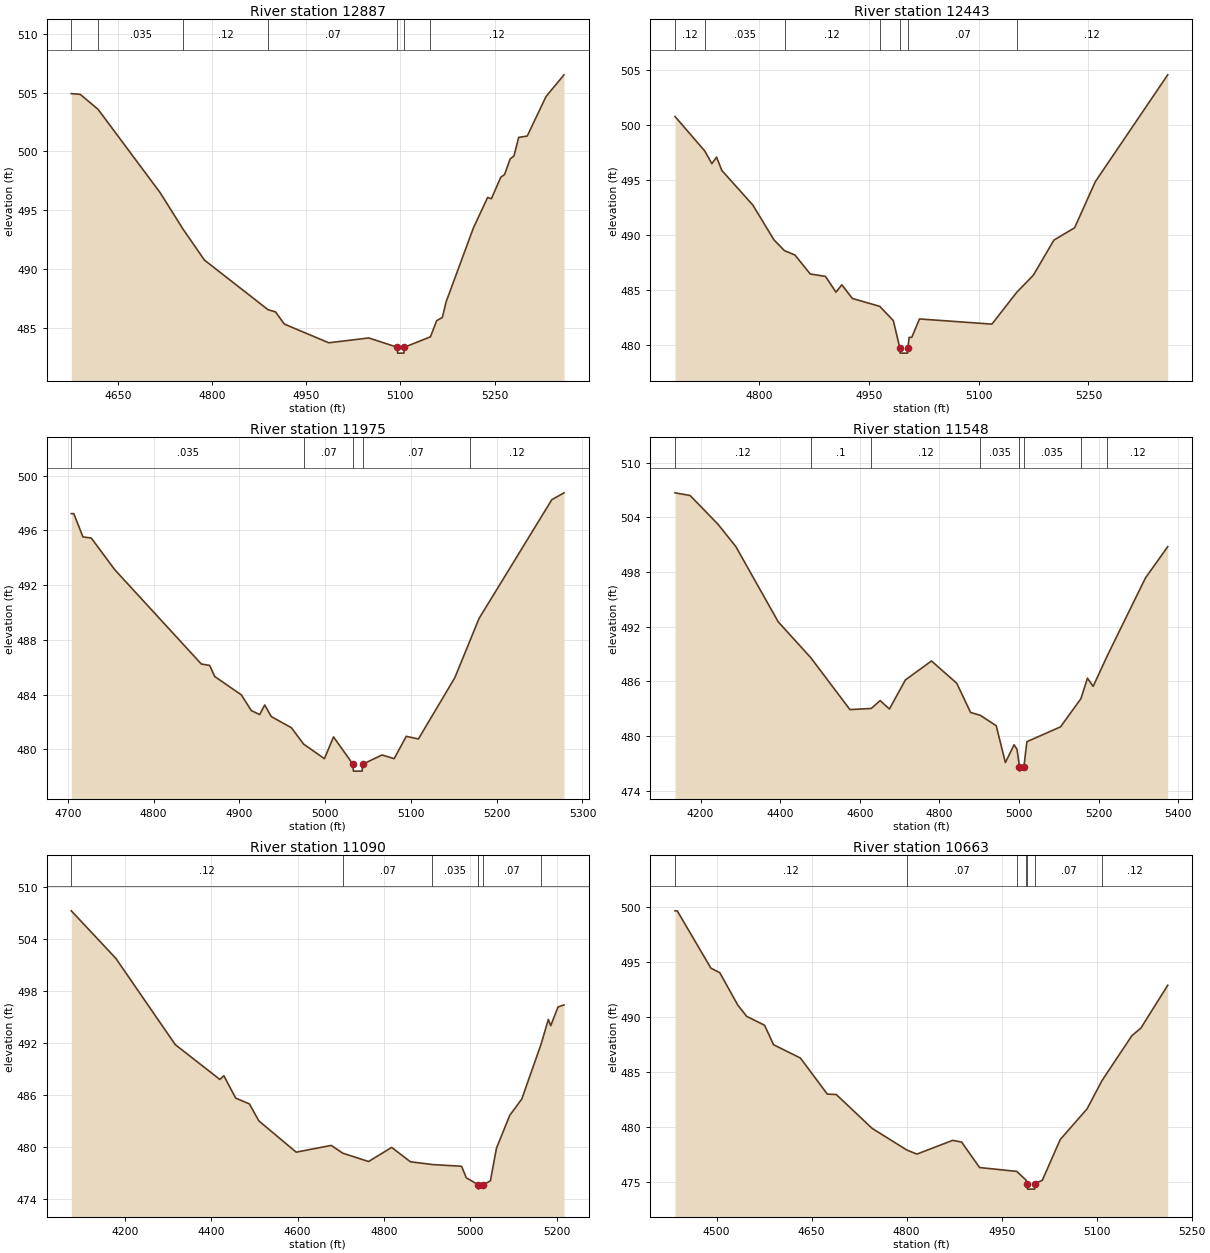
Type RM Length L Ch R = 1 ,12887   ,444,444,444
BEGIN DESCRIPTION:
Big Sandy Branch 27.0
END DESCRIPTION:
XS GIS Cut Line= 3
      2457275.03     13837725.03        2456975.       13837425.
      2456674.96     13837224.98
#Sta/Elev= 30
  4575.7  504.92  4589.9  504.86  4618.3  503.59  4717.2   496.5  4753.8  493.39
  4787.9  490.76  4889.2  486.54    4901  486.36  4915.1  485.32  4985.9  483.73
  5049.6  484.14  5095.1  483.35  5095.6  482.85  5105.7  482.85  5106.2  483.35
  5147.9  484.24  5157.7  485.61  5166.8  485.88  5172.8  487.21  5216.3   493.5
  5238.9  496.09  5244.9  495.98  5259.9  497.81  5265.9  498.04  5274.9  499.37
  5280.9  499.62  5288.4   501.2    5302  501.31    5332  504.68  5360.6  506.52
#Mann= 7 ,-1 , 0
  4575.7     .12       0  4618.3    .035       0  4753.8     .12       0
  4889.2     .07       0  5095.1     .05       0  5106.2     .07       0
  5147.9     .12       0
Bank Sta=5095.1,5106.2
XS Rating Curve= 0 ,0
Exp/Cntr=0.3,0.1

Type RM Length L Ch R = 1 ,12443   ,468,468,468
BEGIN DESCRIPTION:
Big Sandy Branch 26.0
END DESCRIPTION:
XS GIS Cut Line= 3
      2457474.97     13837274.98        2457225.       13837075.
      2456974.98     13836824.98
#Sta/Elev= 30
  4684.7  500.75  4725.3  497.63  4735.1  496.47  4741.5  497.07  4748.7  495.86
  4791.1  492.72  4819.9  489.57  4834.4  488.58  4848.7  488.19  4869.6  486.47
  4890.4  486.25  4904.8  484.82  4912.8  485.49  4927.2  484.25  4964.7  483.53
  4983.2  482.24    4992  479.79  4992.5  479.29  5002.7  479.29  5003.2  479.79
  5004.8  480.72  5008.4  480.72    5019  482.39    5118  481.92    5152  484.81
  5174.5  486.34  5202.8  489.54  5231.1  490.66  5259.4  494.84  5358.4  504.53
#Mann= 7 ,-1 , 0
  4684.7     .12       0  4725.3    .035       0  4834.4     .12       0
  4964.7     .07       0    4992     .05       0  5003.2     .07       0
    5152     .12       0
Bank Sta=4992,5003.2
XS Rating Curve= 0 ,0
Exp/Cntr=0.3,0.1

Type RM Length L Ch R = 1 ,11975   ,427,427,427
BEGIN DESCRIPTION:
Big Sandy Branch 25.0
END DESCRIPTION:
XS GIS Cut Line= 3
        2457675.       13837025.        2457525.       13836775.
      2457324.99     13836574.99
#Sta/Elev= 30
  4704.1  497.22    4707  497.22  4717.7  495.52  4727.4  495.44  4754.6  493.14
  4855.7  486.24  4865.4  486.14  4871.3  485.33  4902.3  483.99    4914  482.84
  4923.7  482.55  4929.6  483.25  4937.3   482.4  4960.7  481.59    4975  480.39
  4999.2  479.33  5009.8  480.92  5032.5  478.92    5033  478.42  5043.2  478.42
  5043.7  478.92  5066.4   479.6  5080.5  479.33  5094.6  480.96  5108.8  480.77
  5151.2  485.24  5168.8  487.93  5179.5  489.57  5264.3  498.24  5278.5  498.74
#Mann= 5 ,-1 , 0
  4704.1    .035       0    4975     .07       0  5032.5     .05       0
  5043.7     .07       0  5168.8     .12       0
Bank Sta=5032.5,5043.7
XS Rating Curve= 0 ,0
Exp/Cntr=0.3,0.1

Type RM Length L Ch R = 1 ,11548   ,458,458,458
BEGIN DESCRIPTION:
Big Sandy Branch 24.0
END DESCRIPTION:
XS GIS Cut Line= 3
        2458475.       13836775.        2457675.       13836425.
      2457325.02     13836524.99
#Sta/Elev= 30
    4136  506.68  4173.8  506.39    4244  503.23  4288.8  500.78  4395.2  492.52
  4477.1  488.58  4575.3  482.89  4628.9  483.02    4651  483.88  4674.4  482.96
  4714.5  486.15    4780  488.23  4843.5  485.78  4878.2  482.58  4902.8  482.26
  4942.6  481.12  4965.6  477.08  4987.4  479.03  4994.8  478.53  5000.9  476.64
  5001.4  476.14  5012.1  476.64  5019.6  479.37  5104.1     481  5155.2  484.09
  5171.7  486.34    5186  485.44  5220.9  488.75  5317.3  497.34  5373.2  500.77
#Mann= 8 ,-1 , 0
    4136     .12       0  4477.1      .1       0  4628.9     .12       0
  4902.8    .035       0  5000.9    .035       0  5012.1    .035       0
  5155.2     .07       0  5220.9     .12       0
Bank Sta=5000.9,5012.1
XS Rating Curve= 0 ,0
Exp/Cntr=0.3,0.1

Type RM Length L Ch R = 1 ,11090   ,427,427,427
BEGIN DESCRIPTION:
Big Sandy Branch 23.0
END DESCRIPTION:
XS GIS Cut Line= 3
      2458624.97     13836474.98        2457825.       13836025.
      2457725.02     13835825.04
#Sta/Elev= 30
  4075.7  507.28  4178.9  501.79  4316.6  491.82  4419.9   487.8  4429.1  488.23
  4456.5  485.65  4488.4  484.97  4510.1  483.02  4596.7   479.4  4677.7  480.18
  4704.8  479.28  4764.4  478.32  4817.9  479.95  4861.3  478.29  4912.3  477.97
  4979.8  477.77  4990.7  476.44  5018.2  475.64  5018.4  475.63  5018.9  475.13
  5030.2  475.63  5046.6  476.09  5060.6  479.85  5091.4  483.65  5119.3  485.54
  5164.1  491.89  5180.8  494.73  5186.4  494.01  5203.2  496.17  5217.1  496.41
#Mann= 7 ,-1 , 0
  4075.7     .12       0  4704.8     .07       0  4912.3    .035       0
  5018.2     .07       0  5018.4    .035       0  5030.2     .07       0
  5164.1     .12       0
Bank Sta=5018.4,5030.2
XS Rating Curve= 0 ,0
Exp/Cntr=0.3,0.1

Type RM Length L Ch R = 1 ,10663   ,554,554,554
BEGIN DESCRIPTION:
Big Sandy Branch 22.0
END DESCRIPTION:
XS GIS Cut Line= 3
      2458574.99     13836274.99        2458175.       13835875.
      2458025.01     13835725.01
#Sta/Elev= 30
  4434.3  499.66  4437.8  499.66  4490.9  494.46    4505  494.04  4533.3  491.11
  4547.4  490.08  4575.7  489.27  4589.9   487.5  4632.3  486.29  4674.7  483.02
  4688.9  482.98  4745.4  479.91  4800.3  477.94  4816.1  477.57  4872.7  478.82
  4886.8  478.66  4915.1  476.35  4973.8     476  4988.3  475.22  4990.3  474.89
  4990.8  474.39    5002  474.39  5002.5  474.89  5014.1  475.19  5042.4  478.89
  5084.8  481.68  5108.4  484.25  5155.5  488.32  5169.7  489.01  5212.1   492.9
#Mann= 7 ,-1 , 0
  4434.3     .12       0  4800.3     .07       0  4973.8    .035       0
  4988.3     .07       0  4990.3     .05       0  5002.5     .07       0
  5108.4     .12       0
Bank Sta=4990.3,5002.5
XS Rating Curve= 0 ,0
Exp/Cntr=0.3,0.1

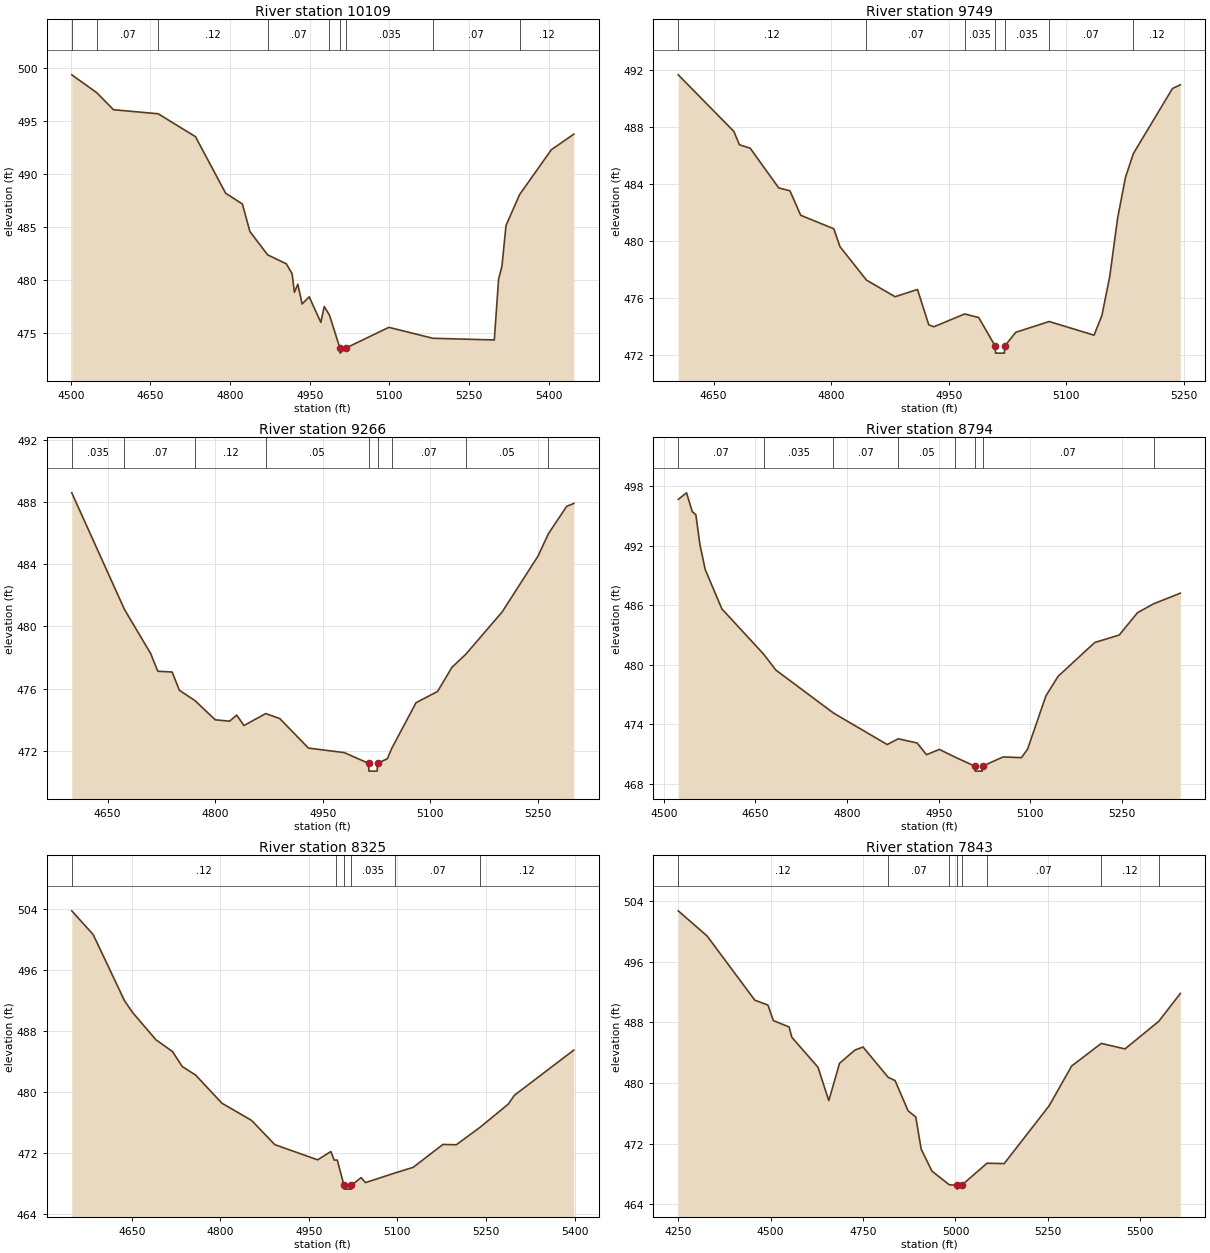
Type RM Length L Ch R = 1 ,10109   ,360,360,360
BEGIN DESCRIPTION:
Big Sandy Branch 21.0
END DESCRIPTION:
XS GIS Cut Line= 3
      2458916.09     13835880.99       2458540.2     13835705.39
      2458124.99       13835375.
#Sta/Elev= 30
  4501.8  499.33  4548.8  497.65  4580.4  496.04  4664.6  495.66  4734.8   493.5
  4791.6  488.17  4823.1  487.16  4837.3  484.56  4870.7  482.36  4905.8  481.52
  4916.7  480.59  4921.1  478.83  4927.5   479.6  4935.6  477.73  4948.9  478.41
  4970.8     476  4977.2  477.49    4987   476.7  5006.6   473.6  5007.1   473.1
  5018.9   473.6  5098.9  475.53  5181.8   474.5  5297.5  474.34  5305.6  480.08
  5311.9  481.29  5319.5  485.12    5345  488.03  5404.9  492.27  5447.3  493.74
#Mann= 9 ,-1 , 0
  4501.8    .035       0  4548.8     .07       0  4664.6     .12       0
  4870.7     .07       0    4987    .035       0  5006.6    .035       0
  5018.9    .035       0  5181.8     .07       0    5345     .12       0
Bank Sta=5006.6,5018.9
XS Rating Curve= 0 ,0
Exp/Cntr=0.3,0.1

Type RM Length L Ch R = 1 ,9749    ,483,483,483
BEGIN DESCRIPTION:
Big Sandy Branch 20.0
END DESCRIPTION:
XS GIS Cut Line= 3
      2458774.99     13835574.99        2458475.       13835325.
      2458224.99       13835325.
#Sta/Elev= 30
  4604.9  491.64  4675.8  487.67    4683  486.73  4696.7  486.49  4733.1   483.7
  4747.4   483.5  4761.1  481.78  4803.4  480.83  4811.2  479.58    4845  477.23
  4881.5  476.06  4910.1  476.57  4924.5  474.09    4931  473.95  4970.3  474.85
  4988.2   474.6  5009.2   472.6  5009.7   472.1    5021   472.1  5021.5   472.6
  5035.4  473.56  5078.1  474.32  5135.4  473.36  5145.4  474.75  5155.4  477.49
  5165.4  481.57  5175.4  484.43  5185.4   486.1  5235.4  490.68  5245.4  490.94
#Mann= 7 ,-1 , 0
  4604.9     .12       0    4845     .07       0  4970.3    .035       0
  5009.2    .035       0  5021.5    .035       0  5078.1     .07       0
  5185.4     .12       0
Bank Sta=5009.2,5021.5
XS Rating Curve= 0 ,0
Exp/Cntr=0.3,0.1

Type RM Length L Ch R = 1 ,9266    ,472,472,472
BEGIN DESCRIPTION:
Big Sandy Branch 19.0
END DESCRIPTION:
XS GIS Cut Line= 3
      2458975.03       13834875.        2458575.       13834875.
      2458275.03       13834875.
#Sta/Elev= 30
    4600  488.58  4673.4  481.09    4710  478.25    4720  477.11    4740  477.06
    4750  475.89  4771.9  475.22    4800  473.99    4820   473.9    4830  474.29
    4840  473.62  4870.4  474.39    4890  474.07    4930  472.17    4980  471.88
  5013.8  471.19  5014.3  470.69  5025.8  470.69  5026.3  471.19    5040  471.49
  5046.2  472.16    5080  475.09    5110  475.81    5130  477.36  5149.3   478.2
    5200  480.92    5250  484.51  5264.5  485.95    5290  487.71    5300   487.9
#Mann= 9 ,-1 , 0
    4600    .035       0  4673.4     .07       0  4771.9     .12       0
  4870.4     .05       0  5013.8     .05       0  5026.3     .05       0
  5046.2     .07       0  5149.3     .05       0  5264.5     .12       0
Bank Sta=5013.8,5026.3
XS Rating Curve= 0 ,0
Exp/Cntr=0.3,0.1

Type RM Length L Ch R = 1 ,8794    ,469,469,469
BEGIN DESCRIPTION:
Big Sandy Branch 18.0
END DESCRIPTION:
XS GIS Cut Line= 3
        2459125.       13834725.        2458725.       13834475.
        2458375.       13834475.
#Sta/Elev= 30
  4523.7  496.66  4537.3  497.32  4546.7  495.42  4552.6   495.1  4559.1  492.13
  4567.9  489.58    4595  485.63  4663.4  481.06  4683.5  479.45  4777.5  475.13
  4865.7  471.94  4883.8  472.52  4914.6   472.1    4930  470.92  4951.2  471.45
  4976.2  470.69  5009.1  469.76  5009.6  469.26  5021.2  469.26  5021.7  469.76
  5055.4  470.69  5085.4  470.62  5095.4  471.47  5125.4  476.84  5145.4  478.82
  5205.4  482.23  5245.4  482.98  5275.4  485.24  5301.7  486.13  5345.4   487.2
#Mann= 8 ,-1 , 0
  4523.7     .07       0  4663.4    .035       0  4777.5     .07       0
  4883.8     .05       0  4976.2     .07       0  5009.1     .05       0
  5021.7     .07       0  5301.7     .12       0
Bank Sta=5009.1,5021.7
XS Rating Curve= 0 ,0
Exp/Cntr=0.3,0.1

Type RM Length L Ch R = 1 ,8325    ,482,482,482
BEGIN DESCRIPTION:
Big Sandy Branch 17.0
END DESCRIPTION:
XS GIS Cut Line= 3
      2459324.97     13834274.98        2458925.       13834075.
      2458524.99       13834025.
#Sta/Elev= 30
  4548.5  503.75  4584.8  500.63  4637.9  491.95  4651.9  490.38    4691  486.84
    4719   485.3  4735.7  483.32  4758.1  482.22  4802.8  478.52  4853.1  476.26
  4892.3  473.09  4964.9  471.09  4987.3  472.18  4992.9  471.06  4996.2  471.06
  4998.2  471.06  5009.5  467.75    5010  467.25  5021.7  467.25  5022.2  467.75
  5038.5  468.76  5046.1  468.11  5095.1  469.35  5126.7  470.11  5177.1  473.11
  5199.8  473.07  5240.3  475.38  5287.9  478.41    5298  479.55  5398.8  485.49
#Mann= 6 ,-1 , 0
  4548.5     .12       0  4996.2    .035       0  5009.5    .035       0
  5022.2    .035       0  5095.1     .07       0  5240.3     .12       0
Bank Sta=5009.5,5022.2
XS Rating Curve= 0 ,0
Exp/Cntr=0.3,0.1

Type RM Length L Ch R = 1 ,7843    ,440,440,440
BEGIN DESCRIPTION:
Big Sandy Branch 16.0
END DESCRIPTION:
XS GIS Cut Line= 3
      2459424.99       13834075.        2458825.       13833625.
      2458224.97       13833525.
#Sta/Elev= 30
    4250  502.73  4328.1  499.41  4457.3  490.93  4492.7  490.29  4507.3  488.24
    4550   487.4  4557.3  486.04  4628.1  482.08  4657.3  477.68  4686.5  482.61
  4728.1  484.35    4750  484.75    4818  480.75  4836.5  480.33  4871.9  476.33
  4892.7  475.51  4907.3  471.26  4936.5  468.36  4983.1  466.57  5003.7  466.49
  5004.2  465.99  5016.5  466.49  5085.4  469.41  5131.8  469.36  5253.4  476.99
  5314.3  482.24  5394.5  485.23  5458.7   484.5    5550  488.14  5608.3  491.82
#Mann= 8 ,-1 , 0
    4250     .12       0    4818     .07       0  4983.1    .035       0
  5003.7    .035       0  5016.5    .035       0  5085.4     .07       0
  5394.5     .12       0    5550    .035       0
Bank Sta=5003.7,5016.5
XS Rating Curve= 0 ,0
Exp/Cntr=0.3,0.1

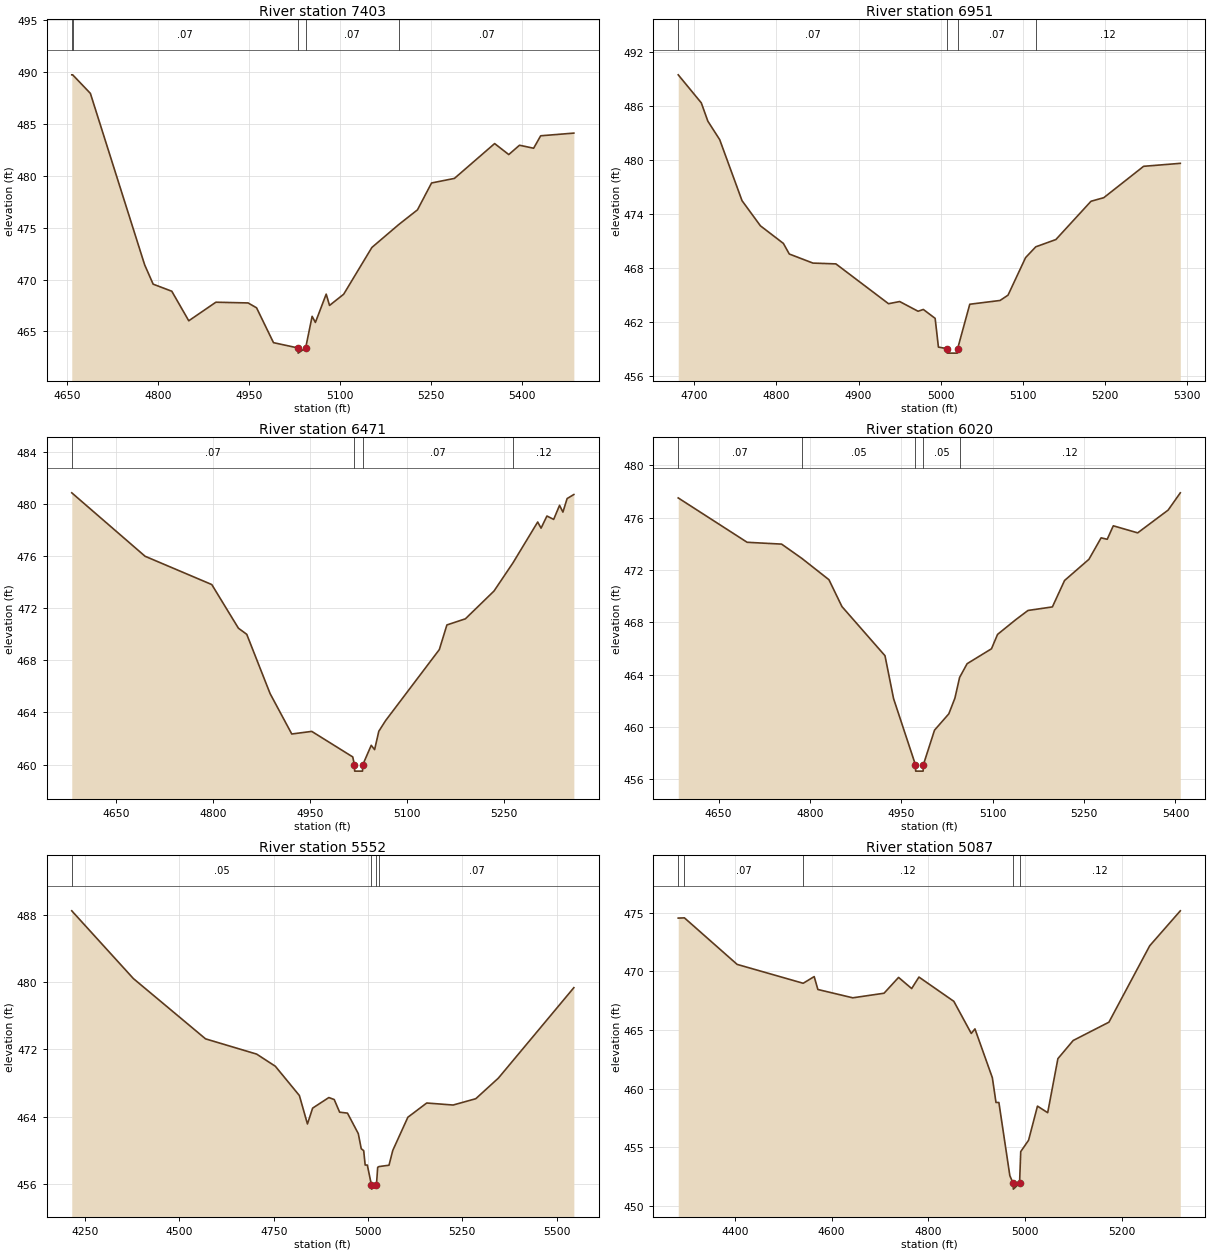
Type RM Length L Ch R = 1 ,7403    ,452,452,452
BEGIN DESCRIPTION:
Big Sandy Branch 15.0
END DESCRIPTION:
XS GIS Cut Line= 3
      2459174.99       13833075.        2458875.       13833225.
      2458425.04     13833424.98
#Sta/Elev= 30
  4657.4  489.75  4658.9  489.75  4688.1  487.96  4777.6  471.42  4791.6  469.56
  4822.3  468.88  4850.3  466.03    4895  467.82  4948.1  467.75  4962.1  467.28
    4990  463.92  5030.2  463.41  5030.7  462.91    5043  463.41  5053.7  466.46
  5059.1  465.87  5076.9   468.6  5082.4  467.51  5105.7  468.59  5152.2   473.1
  5196.7  475.32  5227.4  476.73  5250.6  479.32  5288.3  479.76  5354.6  483.12
  5377.9  482.06  5395.6  482.96  5418.9  482.67  5430.5  483.87  5485.2  484.13
#Mann= 5 ,-1 , 0
  4657.4     .12       0  4658.9     .07       0  5030.2     .05       0
    5043     .07       0  5196.7     .07       0
Bank Sta=5030.2,5043
XS Rating Curve= 0 ,0
Exp/Cntr=0.3,0.1

Type RM Length L Ch R = 1 ,6951    ,480,480,480
BEGIN DESCRIPTION:
Big Sandy Branch 14.0
END DESCRIPTION:
XS GIS Cut Line= 3
      2459175.03     13833025.03        2458925.       13832825.
      2458675.04     13832675.02
#Sta/Elev= 30
  4680.3   489.5  4708.4  486.38  4716.4  484.34  4730.8  482.29    4758   475.5
  4780.4   472.7  4808.4  470.74  4815.6  469.56  4844.4  468.55  4872.4  468.46
  4936.5  464.03  4950.1  464.27  4972.5  463.19  4978.9  463.39  4993.3   462.4
  4997.3   459.2  5007.6  459.03  5008.1  458.53  5020.2  458.53  5020.7  459.03
  5035.5  463.97  5072.4  464.39  5082.1  464.98  5103.5  469.16  5115.9  470.36
  5140.4  471.17  5183.2  475.43  5198.8  475.83  5247.3  479.32    5292  479.65
#Mann= 4 ,-1 , 0
  4680.3     .07       0  5007.6     .05       0  5020.7     .07       0
  5115.9     .12       0
Bank Sta=5007.6,5020.7
XS Rating Curve= 0 ,0
Exp/Cntr=0.3,0.1

Type RM Length L Ch R = 1 ,6471    ,451,451,451
BEGIN DESCRIPTION:
Big Sandy Branch 13.0
END DESCRIPTION:
XS GIS Cut Line= 3
      2459425.04     13832475.01        2459025.       13832375.
      2458674.96     13832475.01
#Sta/Elev= 30
  4581.6  480.86    4695  475.99  4798.1  473.82  4839.3  470.47  4852.2     470
  4888.3  465.45  4921.8  462.35  4952.7  462.55  5016.1  460.59  5018.6     460
  5019.1   459.5  5031.2   459.5  5031.7     460  5044.7  461.48  5049.9  461.15
  5056.4  462.56  5066.8  463.37    5150  468.83  5161.7  470.72  5190.3  471.19
  5234.5  473.32  5263.8  475.48  5302.1  478.62  5307.3  478.15  5316.4  479.08
  5326.8  478.82  5335.9   479.9  5341.1  479.38  5347.6  480.42    5358  480.73
#Mann= 4 ,-1 , 0
  4581.6     .07       0  5018.6     .05       0  5031.7     .07       0
  5263.8     .12       0
Bank Sta=5018.6,5031.7
XS Rating Curve= 0 ,0
Exp/Cntr=0.3,0.1

Type RM Length L Ch R = 1 ,6020    ,468,468,468
BEGIN DESCRIPTION:
Big Sandy Branch 12.0
END DESCRIPTION:
XS GIS Cut Line= 3
      2459474.97     13832274.97        2459175.       13831975.
      2458775.03       13831975.
#Sta/Elev= 30
  4583.8   477.5  4696.9  474.11  4753.5  473.97  4786.7  472.88  4831.2  471.25
  4852.5   469.2  4923.2  465.44  4937.3  462.16  4973.1  457.12  4973.6  456.62
  4985.8  456.62  4986.3  457.12  5004.5  459.75    5028     461    5038   462.2
  5045.7  463.78    5058  464.83    5098  465.97    5108  467.07    5138   468.2
    5158   468.9    5198  469.17    5218  471.19    5258  472.81    5278  474.45
    5288  474.34    5298  475.37    5338  474.83    5388  476.57    5408  477.89
#Mann= 5 ,-1 , 0
  4583.8     .07       0  4786.7     .05       0  4973.1     .05       0
  4986.3     .05       0  5045.7     .12       0
Bank Sta=4973.1,4986.3
XS Rating Curve= 0 ,0
Exp/Cntr=0.3,0.1

Type RM Length L Ch R = 1 ,5552    ,465,465,465
BEGIN DESCRIPTION:
Big Sandy Branch 11.0
END DESCRIPTION:
XS GIS Cut Line= 3
      2459925.01     13832075.01        2459325.       13831575.
      2458775.04       13831575.
#Sta/Elev= 30
  4214.7  488.44  4378.1  480.39  4569.4  473.23  4704.8  471.42  4754.3  469.98
  4818.1   466.5  4839.5  463.12  4853.2     465  4896.2  466.26  4910.5  466.02
  4924.8  464.52  4945.6  464.41  4974.3  461.97  4982.1  460.18  4988.6  459.95
  4992.5  458.24  4998.2  458.24  5009.1  455.88  5009.6  455.38  5022.4  455.88
  5025.7  457.97  5029.3  458.06  5055.7  458.22  5065.7  459.98  5105.7  463.92
  5155.7  465.61  5225.7  465.37  5285.7  466.12  5345.7  468.57  5545.7  479.31
#Mann= 4 ,-1 , 0
  4214.7     .05       0  5009.1     .05       0  5022.4     .05       0
  5029.3     .07       0
Bank Sta=5009.1,5022.4
XS Rating Curve= 0 ,0
Exp/Cntr=0.3,0.1

Type RM Length L Ch R = 1 ,5087    ,457,457,457
BEGIN DESCRIPTION:
Big Sandy Branch 10.0
END DESCRIPTION:
XS GIS Cut Line= 3
      2459875.01     13831525.01        2459275.       13831125.
      2458975.05     13831025.02
#Sta/Elev= 30
  4283.1  474.55  4295.9  474.57  4404.8   470.6  4541.2  468.99    4564  469.56
  4571.6  468.46  4643.7  467.75  4708.3  468.14  4738.3  469.49  4765.4  468.54
  4780.4  469.52  4852.5  467.45  4888.5  464.71  4896.1   465.1  4932.1  460.93
  4939.6  458.82  4945.6  458.82  4968.2  452.58    4975  451.93  4975.5  451.43
  4988.3  451.93  4990.7  454.63  5006.9   455.6  5025.3  458.51  5046.4  457.95
  5067.5  462.56  5099.1  464.11  5172.9  465.67  5257.2  472.19  5320.4  475.17
#Mann= 5 ,-1 , 0
  4283.1     .05       0  4295.9     .07       0  4541.2     .12       0
    4975     .05       0  4988.3     .12       0
Bank Sta=4975,4988.3
XS Rating Curve= 0 ,0
Exp/Cntr=0.3,0.1

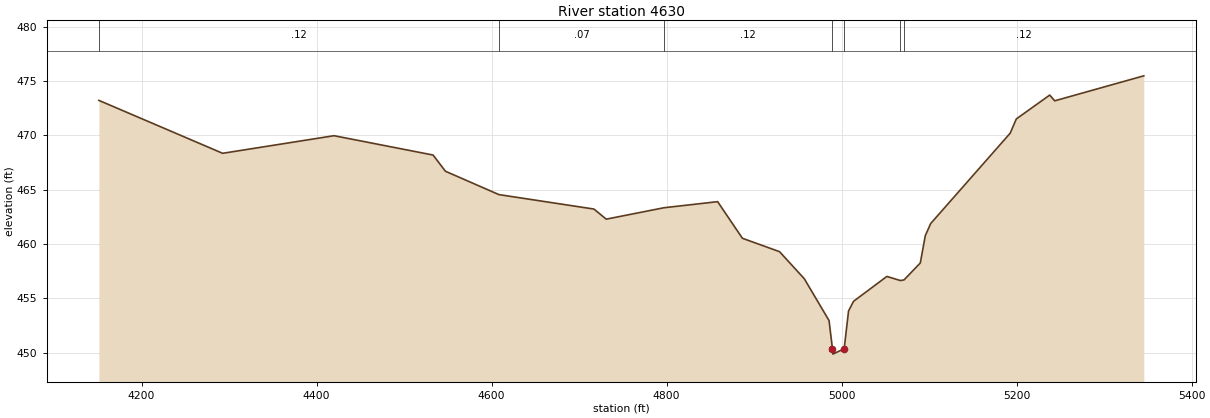
Type RM Length L Ch R = 1 ,4630    ,469,469,469
BEGIN DESCRIPTION:
Big Sandy Branch 9.0
END DESCRIPTION:
XS GIS Cut Line= 3
      2460025.01     13831325.01        2459425.       13830725.
      2459261.86     13830420.38
#Sta/Elev= 30
  4151.2  473.23  4292.6  468.36  4419.9  469.98  4533.1   468.2  4547.2  466.71
  4608.3  464.56  4716.9  463.23    4731   462.3  4796.9  463.35  4858.3  463.91
  4886.6  460.54    4929  459.31  4957.3  456.82  4985.6  452.97  4989.5  450.38
    4990  449.88  5002.9  450.38  5007.9  453.85  5013.6  454.74  5051.7  457.03
  5067.2  456.65  5071.3  456.71  5089.9  458.27  5095.6  460.78  5101.8   461.9
  5192.6  470.21  5199.6  471.52  5237.8  473.72  5243.5  473.19  5345.3  475.49
#Mann= 7 ,-1 , 0
  4151.2     .12       0  4608.3     .07       0  4796.9     .12       0
  4989.5     .05       0  5002.9     .12       0  5067.2     .07       0
  5071.3     .12       0
Bank Sta=4989.5,5002.9
XS Rating Curve= 0 ,0
Exp/Cntr=0.3,0.1