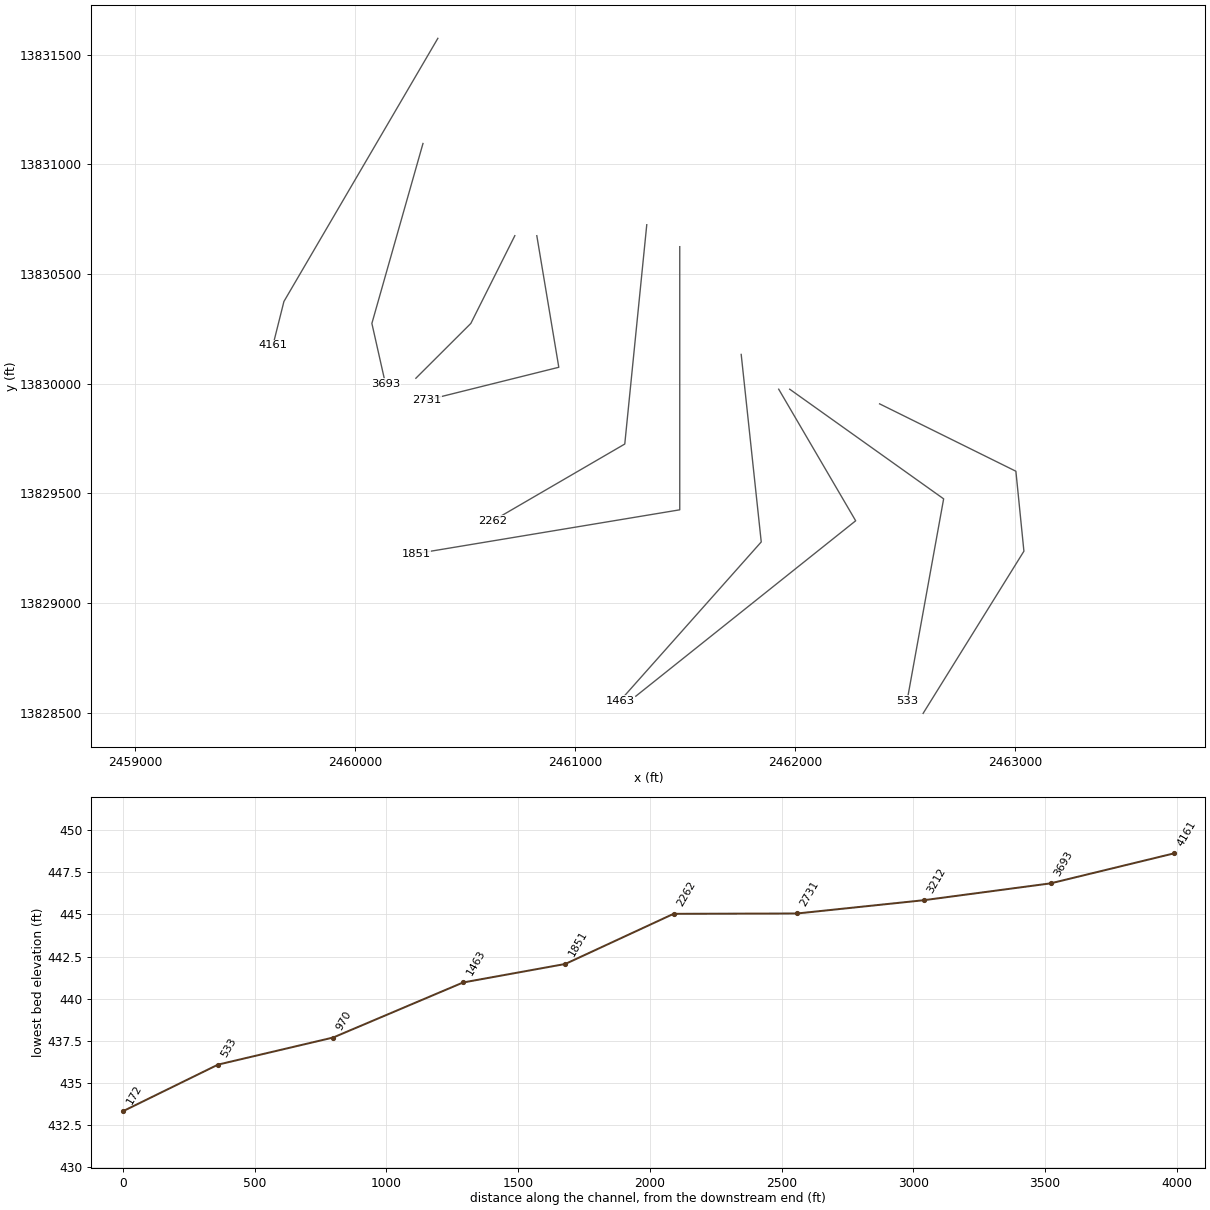
HEC-RAS study Big Sandy Branch.prj: Big Sandy Branch Base Level Engineering

--- Big Sandy Branch.g01 (geometry) --- (continued)

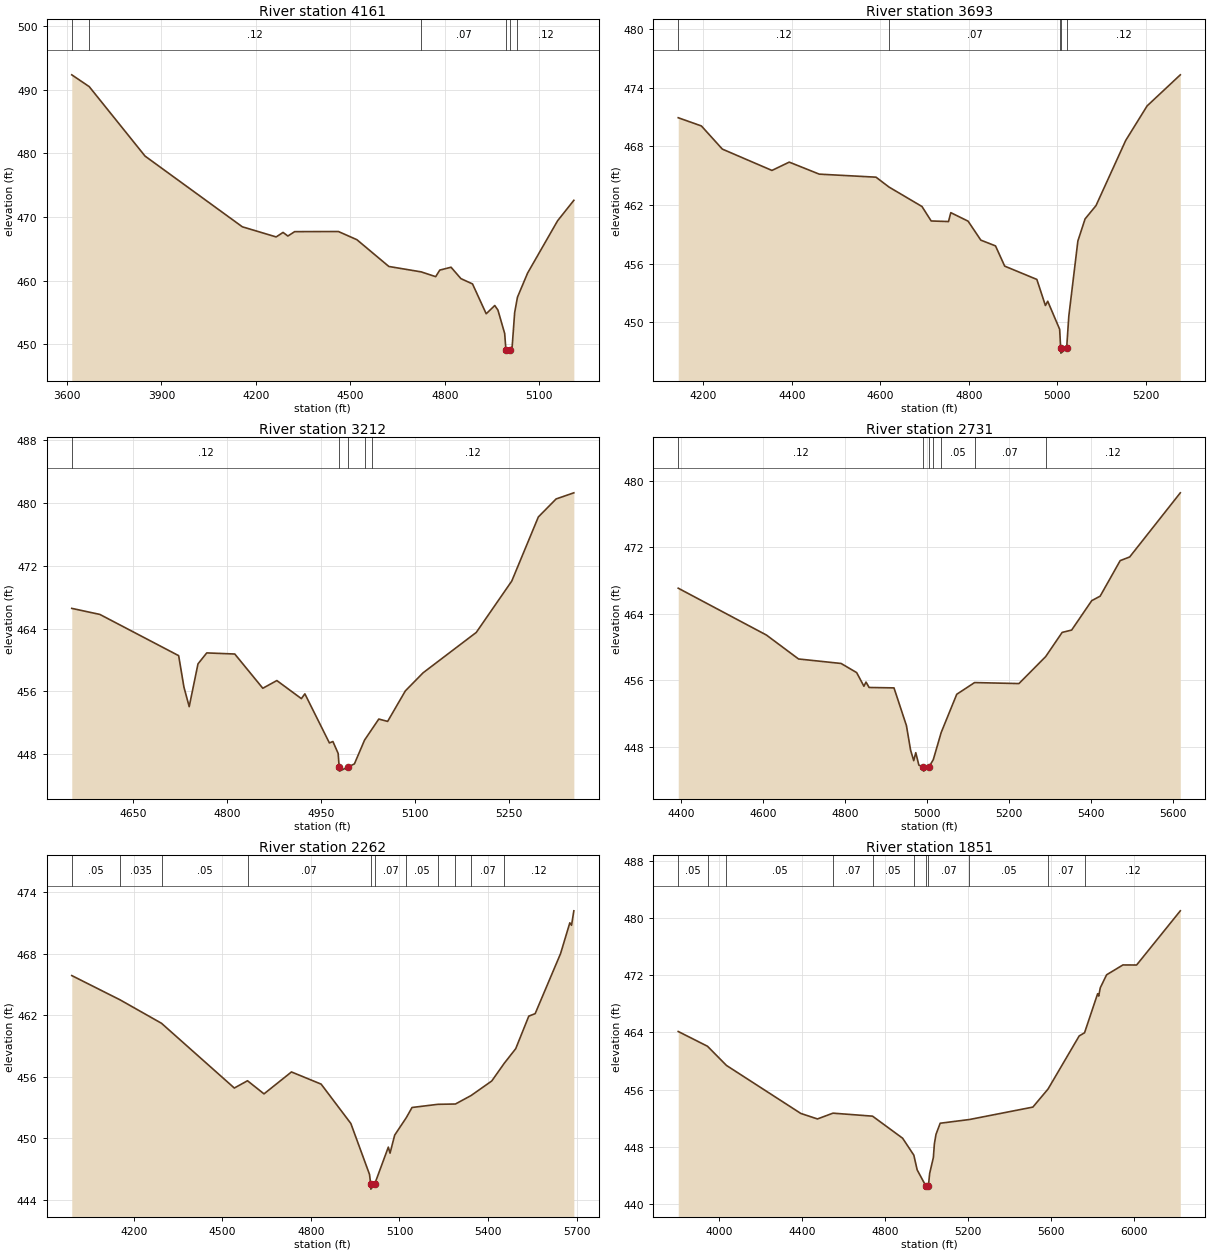
Type RM Length L Ch R = 1 ,4161    ,468,468,468
BEGIN DESCRIPTION:
Big Sandy Branch 8.0
END DESCRIPTION:
XS GIS Cut Line= 3
      2460374.99     13831574.98        2459675.       13830375.
      2459624.99     13830174.97
#Sta/Elev= 30
    3615  492.34  3670.4  490.49  3847.8  479.58    4157  468.47  4264.5  466.88
  4286.4  467.59  4301.7  467.02  4323.2  467.71  4462.2  467.73  4520.9  466.45
  4622.6  462.24  4725.4  461.39  4771.4  460.64  4784.3  461.67  4820.2  462.12
  4851.6  460.33  4888.4   459.5  4931.9  454.81  4959.1  456.11  4969.1   455.4
  4990.6  451.72  4994.6  449.13  4995.1  448.63    5008  449.13  5014.5  449.69
  5022.3  454.98  5031.2  457.41  5063.5  461.21  5158.8  469.42  5210.4  472.63
#Mann= 6 ,-1 , 0
    3615     .07       0  3670.4     .12       0  4725.4     .07       0
  4994.6     .05       0    5008     .07       0  5031.2     .12       0
Bank Sta=4994.6,5008
XS Rating Curve= 0 ,0
Exp/Cntr=0.3,0.1

Type RM Length L Ch R = 1 ,3693    ,481,481,481
BEGIN DESCRIPTION:
Big Sandy Branch 7.0
END DESCRIPTION:
XS GIS Cut Line= 3
      2460307.34     13831095.42        2460075.       13830275.
      2460136.97     13829998.96
#Sta/Elev= 30
    4143  470.93  4195.4  470.09  4242.8  467.72    4355  465.54  4394.1  466.39
    4462  465.16  4590.3  464.85  4619.7  463.84  4694.3  461.85  4715.1  460.37
  4754.3  460.31  4759.5  461.22  4798.6  460.35  4827.4  458.41  4860.6  457.82
  4881.4  455.75  4954.1  454.39  4973.5  451.72  4978.7  452.16  5005.7  449.29
    5008  447.35  5008.5  446.85  5021.5  447.35  5026.4  450.62  5046.9  458.32
  5063.2  460.58  5087.9  461.94    5155   468.6  5203.5  472.14  5278.6  475.32
#Mann= 5 ,-1 , 0
    4143     .12       0  4619.7     .07       0  5005.7     .12       0
    5008     .05       0  5021.5     .12       0
Bank Sta=5008,5021.5
XS Rating Curve= 0 ,0
Exp/Cntr=0.3,0.1

Type RM Length L Ch R = 1 ,3212    ,481,481,481
BEGIN DESCRIPTION:
Big Sandy Branch 6.0
END DESCRIPTION:
XS GIS Cut Line= 3
      2460725.02     13830675.04        2460525.       13830275.
      2460275.01     13830025.01
#Sta/Elev= 30
  4552.2  466.57    4597   465.8  4722.7  460.55  4731.1  456.55  4739.5  454.06
  4753.5   459.5  4767.5   460.9  4812.2  460.76  4856.9   456.4  4879.3  457.38
  4918.4  455.08    4924  455.69  4963.1  449.44  4968.7  449.62  4977.1   448.1
  4978.7  446.35  4979.2  445.85  4992.2  446.35    5003  446.77  5019.2   449.8
  5030.7  451.16  5041.9  452.48    5056  452.18  5084.3  456.07  5112.6  458.37
  5197.4  463.51    5254  470.05  5296.4  478.21  5324.7   480.5    5353  481.28
#Mann= 5 ,-1 , 0
  4552.2     .12       0  4978.7     .05       0  4992.2     .12       0
  5019.2     .07       0  5030.7     .12       0
Bank Sta=4978.7,4992.2
XS Rating Curve= 0 ,0
Exp/Cntr=0.3,0.1

Type RM Length L Ch R = 1 ,2731    ,469,469,469
BEGIN DESCRIPTION:
Big Sandy Branch 5.0
END DESCRIPTION:
XS GIS Cut Line= 3
        2460825.     13830675.02        2460925.       13830075.
      2460324.97     13829924.99
#Sta/Elev= 30
  4392.1  467.08  4607.6  461.44  4686.1  458.56    4790  458.02  4828.1  456.92
  4845.8  455.28  4850.9  455.78  4858.5  455.13  4919.3  455.08  4949.7  450.54
  4959.8   447.6  4967.5  446.32  4972.5  447.28  4980.1  445.78  4991.1  445.56
  4991.6  445.06  5004.7  445.56  5015.3  446.44  5034.6  449.71  5072.6  454.31
  5116.2  455.72  5224.6   455.6    5290  458.85  5330.2  461.76  5353.4  462.04
  5402.4  465.58    5423  466.12    5472   470.4  5495.2  470.84  5618.9  478.56
#Mann= 7 ,-1 , 0
  4392.1     .12       0  4991.1     .05       0  5004.7     .12       0
  5015.3     .07       0  5034.6     .05       0  5116.2     .07       0
    5290     .12       0
Bank Sta=4991.1,5004.7
XS Rating Curve= 0 ,0
Exp/Cntr=0.3,0.1

Type RM Length L Ch R = 1 ,2262    ,411,411,411
BEGIN DESCRIPTION:
Big Sandy Branch 4.0
END DESCRIPTION:
XS GIS Cut Line= 3
        2461325.     13830725.02        2461225.       13829725.
      2460625.03     13829375.02
#Sta/Elev= 30
  3990.6  465.89  4154.7  463.51  4294.4  461.23  4540.9  454.91  4585.5  455.62
  4641.4  454.34  4734.3  456.48  4834.8  455.29  4935.3  451.45  4998.5  446.48
  5002.5  445.54    5003  445.04  5016.1  445.54  5062.2  449.14    5068  448.55
  5083.7  450.31  5123.5  452.04  5142.4  453.01  5230.3  453.32  5289.4  453.35
  5342.5  454.18  5412.4   455.6  5454.7  457.33  5493.4  458.75  5537.7  461.93
  5559.2  462.17  5645.2  468.03  5676.6  471.04  5682.4   470.8  5690.2  472.21
#Mann= 11 ,-1 , 0
  3990.6     .05       0  4154.7    .035       0  4294.4     .05       0
  4585.5     .07       0  5002.5     .05       0  5016.1     .07       0
  5123.5     .05       0  5230.3     .07       0  5289.4     .05       0
  5342.5     .07       0  5454.7     .12       0
Bank Sta=5002.5,5016.1
XS Rating Curve= 0 ,0
Exp/Cntr=0.3,0.1

Type RM Length L Ch R = 1 ,1851    ,388,388,388
BEGIN DESCRIPTION:
Big Sandy Branch 3.0
END DESCRIPTION:
XS GIS Cut Line= 3
        2461475.     13830624.97        2461475.       13829425.
      2460275.02       13829225.
#Sta/Elev= 30
    3805  464.14  3945.9  462.07  4036.9  459.39    4395  452.66    4475  451.89
  4549.9   452.7  4740.2  452.28    4885  449.19  4938.9  446.82    4955  444.76
  4995.6  442.56  4996.1  442.06  5009.3  442.56  5015.1  444.26  5032.9  446.48
  5037.9  448.41  5045.5  449.72  5065.8  451.29  5206.6  451.81  5511.9  453.55
  5584.9  456.08  5734.9  463.52  5760.6  463.96  5823.6  469.43  5828.7   469.1
  5836.3  470.26  5866.7  472.08  5945.3  473.46  6011.2  473.45  6221.5  481.04
#Mann= 11 ,-1 , 0
    3805     .05       0  3945.9    .035       0  4036.9     .05       0
  4549.9     .07       0  4740.2     .05       0  4938.9     .07       0
  4995.6     .05       0  5009.3     .07       0  5206.6     .05       0
  5584.9     .07       0  5760.6     .12       0
Bank Sta=4995.6,5009.3
XS Rating Curve= 0 ,0
Exp/Cntr=0.3,0.1

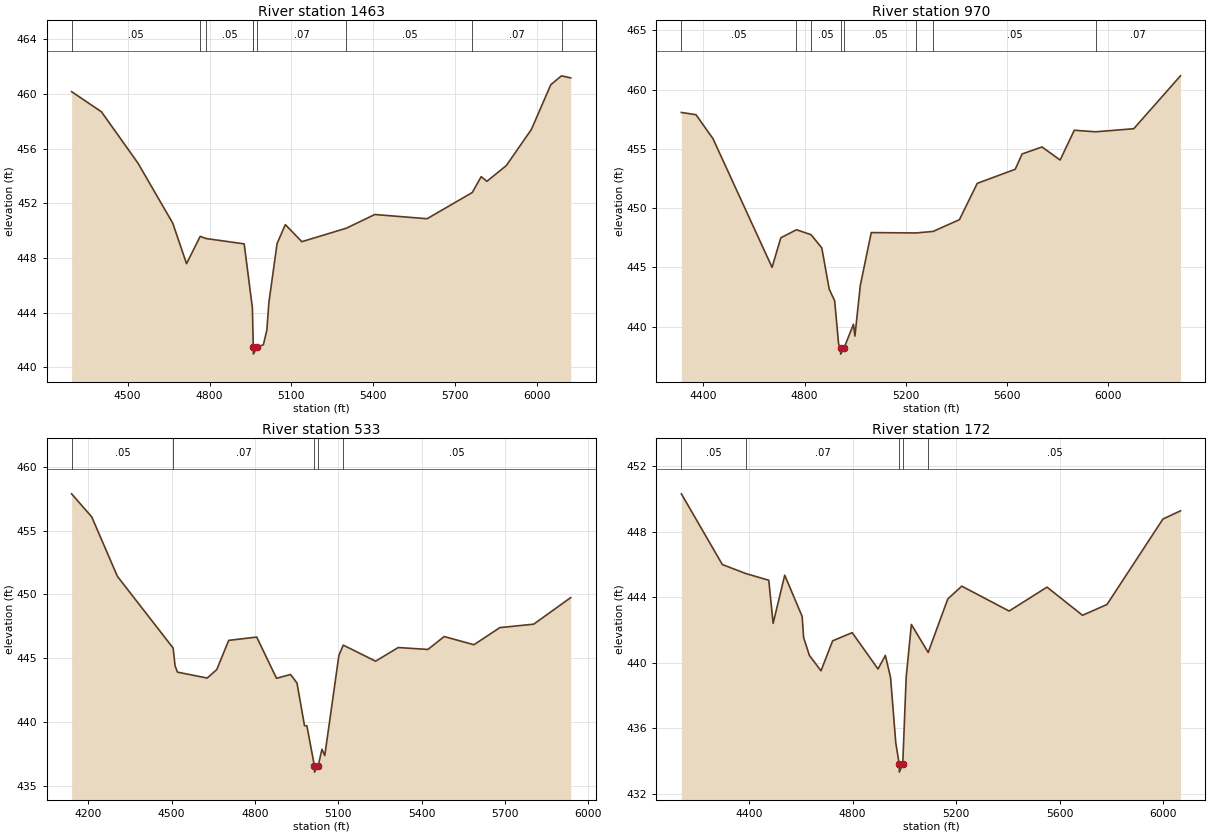
Type RM Length L Ch R = 1 ,1463    ,493,493,493
BEGIN DESCRIPTION:
X18236
END DESCRIPTION:
XS GIS Cut Line= 3
      2461754.43      13830133.6      2461845.58     13829278.52
      2461203.24     13828553.72
#Sta/Elev= 30
  4294.8  460.17    4404   458.7  4537.9  454.94  4665.5  450.54  4715.8  447.58
  4765.9  449.58  4787.7  449.42    4927  449.03  4957.1  444.35  4959.8  441.91
  4960.3  441.46  4960.8  440.96    4974  441.46  4997.4  441.65  5010.1  442.73
  5017.5  444.74  5047.6  449.06  5077.8  450.44  5138.2  449.19  5301.7  450.18
  5405.5  451.18    5597  450.87  5762.7  452.79  5795.3  453.95  5816.2  453.61
  5887.3  454.76  5979.3  457.41  6050.3  460.68  6089.5  461.33  6123.2  461.18
#Mann= 9 ,-1 , 0
  4294.8     .05       0  4765.9     .07       0  4787.7     .05       0
  4959.8     .07       0  4960.3     .05       0    4974     .07       0
  5301.7     .05       0  5762.7     .07       0  6089.5     .05       0
Bank Sta=4960.3,4974
XS Rating Curve= 0 ,0
Exp/Cntr=0.3,0.1

Type RM Length L Ch R = 1 ,970     ,437,437,437
BEGIN DESCRIPTION:
Big Sandy Branch 2.0
END DESCRIPTION:
XS GIS Cut Line= 3
        2461925.       13829975.        2462275.       13829375.
      2461275.04     13828575.03
#Sta/Elev= 30
  4312.5  458.07  4370.4  457.88  4437.8  455.85  4671.4  445.01  4706.1   447.5
    4768  448.18  4825.7  447.76  4868.2  446.65  4897.6  443.17  4919.1  442.19
  4934.8  438.55  4942.4  438.19  4942.9  437.69  4956.1  438.19  4993.5  440.21
  4999.3  439.21  5020.7  443.49  5063.9  447.94  5242.1  447.91  5309.1  448.04
  5412.9  449.03  5483.4  452.09  5633.8  453.28    5661  454.57  5739.5  455.16
  5811.5  454.06  5867.5  456.57  5952.3  456.44  6102.9   456.7  6287.7  461.16
#Mann= 8 ,-1 , 0
  4312.5     .05       0    4768     .07       0  4825.7     .05       0
  4942.4     .05       0  4956.1     .05       0  5242.1    .035       0
  5309.1     .05       0  5952.3     .07       0
Bank Sta=4942.4,4956.1
XS Rating Curve= 0 ,0
Exp/Cntr=0.3,0.1

Type RM Length L Ch R = 1 ,533     ,361,361,361
BEGIN DESCRIPTION:
Big Sandy Branch 1.0
END DESCRIPTION:
XS GIS Cut Line= 3
      2461974.98     13829975.01        2462675.       13829475.
      2462508.78     13828554.04
#Sta/Elev= 30
  4139.9  457.88  4212.4  456.07  4304.6  451.42  4505.2   445.8  4512.3   444.4
  4520.9  443.91  4627.8  443.45  4662.2  444.11  4705.2   446.4    4806  446.66
  4877.3  443.43  4927.7  443.73    4951  443.06    4978  439.72  4986.6  439.71
  5013.6  436.58  5014.1  436.08  5027.3  436.58  5040.8  437.87    5051  437.38
  5101.8  445.22  5117.4  446.03  5233.9  444.77  5315.2  445.84  5422.1  445.69
  5480.8   446.7  5587.9  446.06    5681   447.4  5802.9  447.67    5936  449.75
#Mann= 5 ,-1 , 0
  4139.9     .05       0  4505.2     .07       0  5013.6     .05       0
  5027.3     .07       0  5117.4     .05       0
Bank Sta=5013.6,5027.3
XS Rating Curve= 0 ,0
Exp/Cntr=0.3,0.1

Type RM Length L Ch R = 1 ,172     ,0,0,0
BEGIN DESCRIPTION:
X18237
END DESCRIPTION:
XS GIS Cut Line= 4
      2462383.82     13829908.19      2463003.57     13829600.91
      2463040.03     13829236.33      2462581.71     13828496.77
#Sta/Elev= 30
  4138.4  450.31  4296.7  445.99  4387.6  445.44  4476.1  445.03  4492.9   442.4
  4537.7  445.34    4605  442.82  4610.6  441.54    4633  440.44  4677.8   439.5
  4722.7  441.33  4798.3  441.83  4898.1  439.61  4926.5  440.44  4946.6  439.09
  4966.7   435.1    4980  433.81  4980.5  433.31  4993.7  433.81  5006.9  439.11
    5027  442.33  5091.9  440.62  5167.7  443.89  5221.6  444.67  5404.7  443.15
    5551  444.61  5688.3  442.89  5782.8  443.55  5998.9  448.77  6066.6  449.27
#Mann= 5 ,-1 , 0
  4138.4     .05       0  4387.6     .07       0    4980     .05       0
  4993.7     .07       0  5091.9     .05       0
Bank Sta=4980,4993.7
XS Rating Curve= 0 ,0
Exp/Cntr=0.3,0.1

Chan Stop Cuts=-1
Use User Specified Reach Order=0
Composite Channel Slope=5