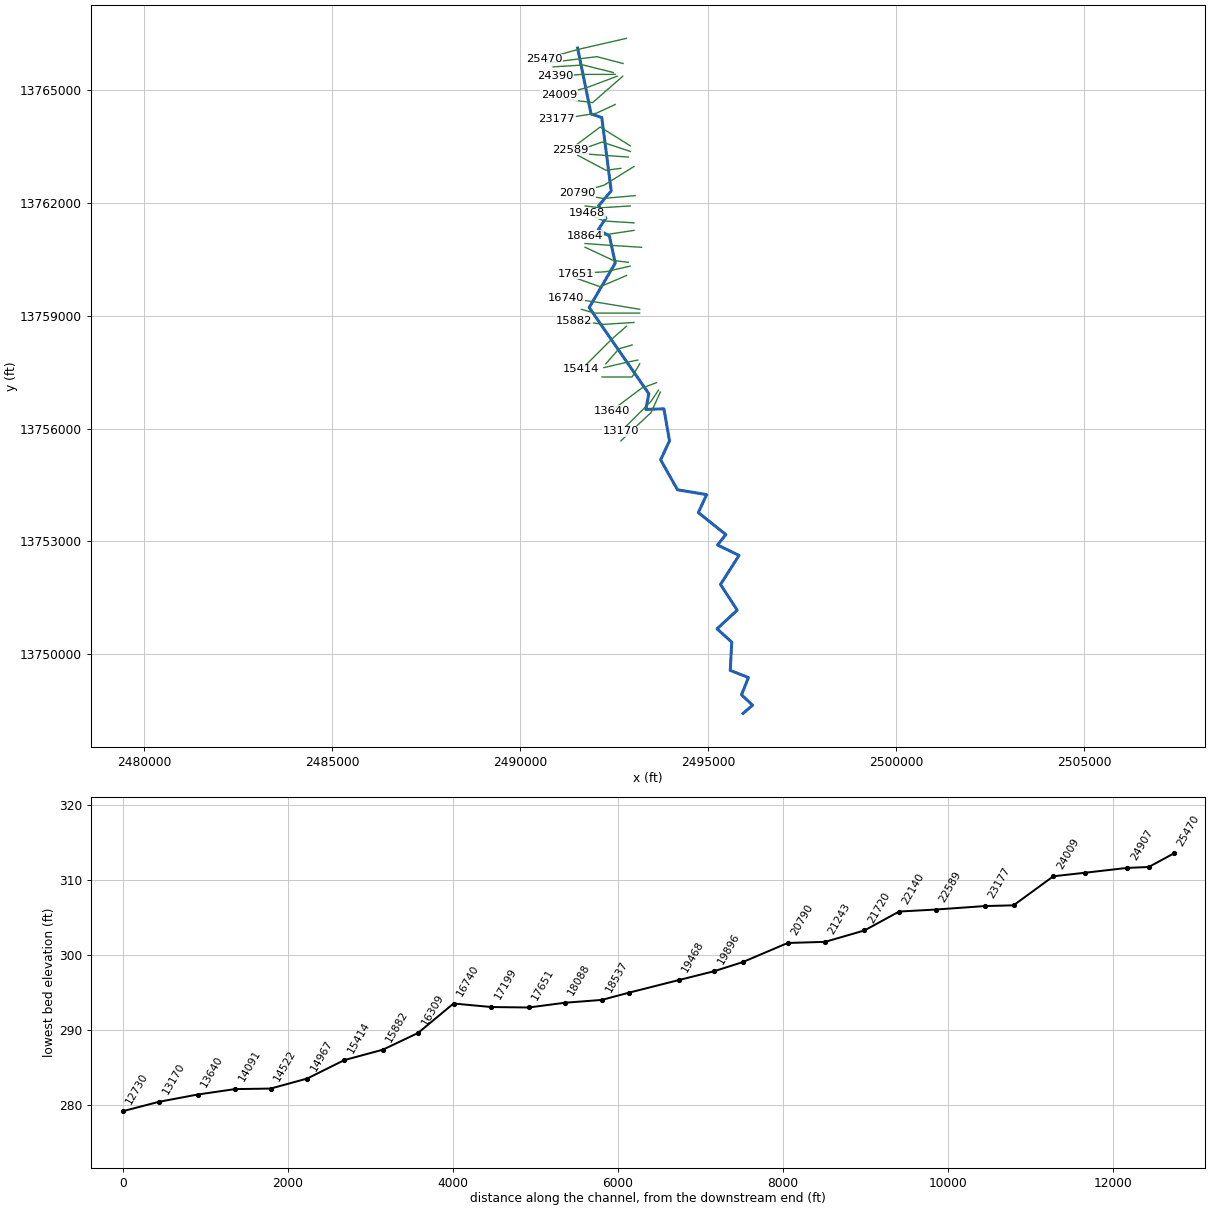
--- CLEAR FORK CREEK.prj (project) ---

Proj Title=CLEAR FORK CREEK Base Level Engineering
Current Plan=p01
Default Exp/Contr=0.3,0.1
English Units
Geom File=g01
Flow File=f01
Plan File=p01
Y Axis Title=Elevation
X Axis Title(PF)=Main Channel Distance
X Axis Title(XS)=Station
BEGIN DESCRIPTION:
CLEAR FORK CREEK
END DESCRIPTION:
DSS Export Rating Curves= 0
DSS Export Rating Curve Sorted= 0
DSS Export Volume Flow Curves= 0
DXF OffsetX= 0
DXF OffsetY= 0
DXF ScaleX= 1
DXF ScaleY= 10

--- CLEAR FORK CREEK.p01 (plan) ---

Plan Title=Multiple Run
Short Identifier=Multiple
Geom File=g01
Flow File=f01
Subcritical Flow
K Sum by GR= 0
Std Step Tol= 0.01
Critical Tol= 0.01
Num of Std Step Trials= 20
Max Error Tol= 0.3
Flow Tol Ratio= 0.001
Split Flow NTrial= 30
Split Flow Tol= 0.02
Split Flow Ratio= 0.02
Log Output Level= 0
Friction Slope Method= 1
Unsteady Friction Slope Method= 2
Unsteady Bridges Friction Slope Method= 1
Parabolic Critical Depth
Global Vel Dist=  1 , 1 , 1
Global Log Level= 0
CheckData=True
Encroach Param= -1, 0, 0, 0
BEGIN DESCRIPTION:
Multiple Run
END DESCRIPTION:

--- CLEAR FORK CREEK.f01 (steady flow) ---

Flow Title=Multiple
Number of Profiles=7
Profile Names=10-year,25-year,50-year,1pct_min,100-year,1pct_plu,500-year
River Rch & RM= CLEAR FORK CREEK,Reach-1,25470
     927    1517    2058    1350    2694    5375    4571
River Rch & RM= CLEAR FORK CREEK,Reach-1,24009
     946    1540    2081    1359    2712    5412    4564
River Rch & RM= CLEAR FORK CREEK,Reach-1,19896
    1138    1864    2528    1656    3304    6593    5593
River Rch & RM= CLEAR FORK CREEK,Reach-1,15882
    1383    2284    3116    2051    4092    8164    6994
River Rch & RM= CLEAR FORK CREEK,Reach-1,13640
    1508    2487    3388    2226    4441    8861    7562
River Rch & RM= CLEAR FORK CREEK,Reach-1,5973
    1553    2558    3480    2283    4555    9089    7735
Boundary for River Rch & Prof#=CLEAR FORK CREEK,Reach-1,1
Up Type=0
Dn Type=3
Dn Slope=0.005
Boundary for River Rch & Prof#=CLEAR FORK CREEK,Reach-1,2
Up Type=0
Dn Type=3
Dn Slope=0.005
Boundary for River Rch & Prof#=CLEAR FORK CREEK,Reach-1,3
Up Type=0
Dn Type=3
Dn Slope=0.005
Boundary for River Rch & Prof#=CLEAR FORK CREEK,Reach-1,4
Up Type=0
Dn Type=3
Dn Slope=0.005
Boundary for River Rch & Prof#=CLEAR FORK CREEK,Reach-1,5
Up Type=0
Dn Type=3
Dn Slope=0.005
Boundary for River Rch & Prof#=CLEAR FORK CREEK,Reach-1,6
Up Type=0
Dn Type=3
Dn Slope=0.005
Boundary for River Rch & Prof#=CLEAR FORK CREEK,Reach-1,7
Up Type=0
Dn Type=3
Dn Slope=0.005

--- CLEAR FORK CREEK.g01 (geometry) ---

Geom Title=Existing Conditions
Program Version=4.10

River Reach=CLEAR FORK CREEK,Reach-1
Reach XY= 30
        2491525.       13766125.      2491882.68     13764371.29
      2492167.32     13764278.71      2492417.93     13762325.01
      2492082.69     13761928.67      2492275.59       13761600.
      2492074.73     13761294.94      2492369.54     13761127.47
       2492525.4     13760404.73      2491832.52     13759221.43
      2493419.18     13756927.31      2493338.26     13756511.32
      2493819.64      13756527.7      2493967.44       13755675.
      2493732.81     13755171.59      2494180.82     13754372.69
      2494955.74     13754245.08      2494733.97     13753767.94
      2495466.13     13753181.51      2495244.38     13752904.35
      2495817.41     13752628.33      2495324.53     13751854.84
      2495767.35     13751171.31       2495232.2      13750674.7
      2495623.12     13750319.31       2495582.8     13749568.79
      2496067.21     13749378.43      2495882.79     13748921.58
      2496174.85     13748641.09        2495925.       13748425.

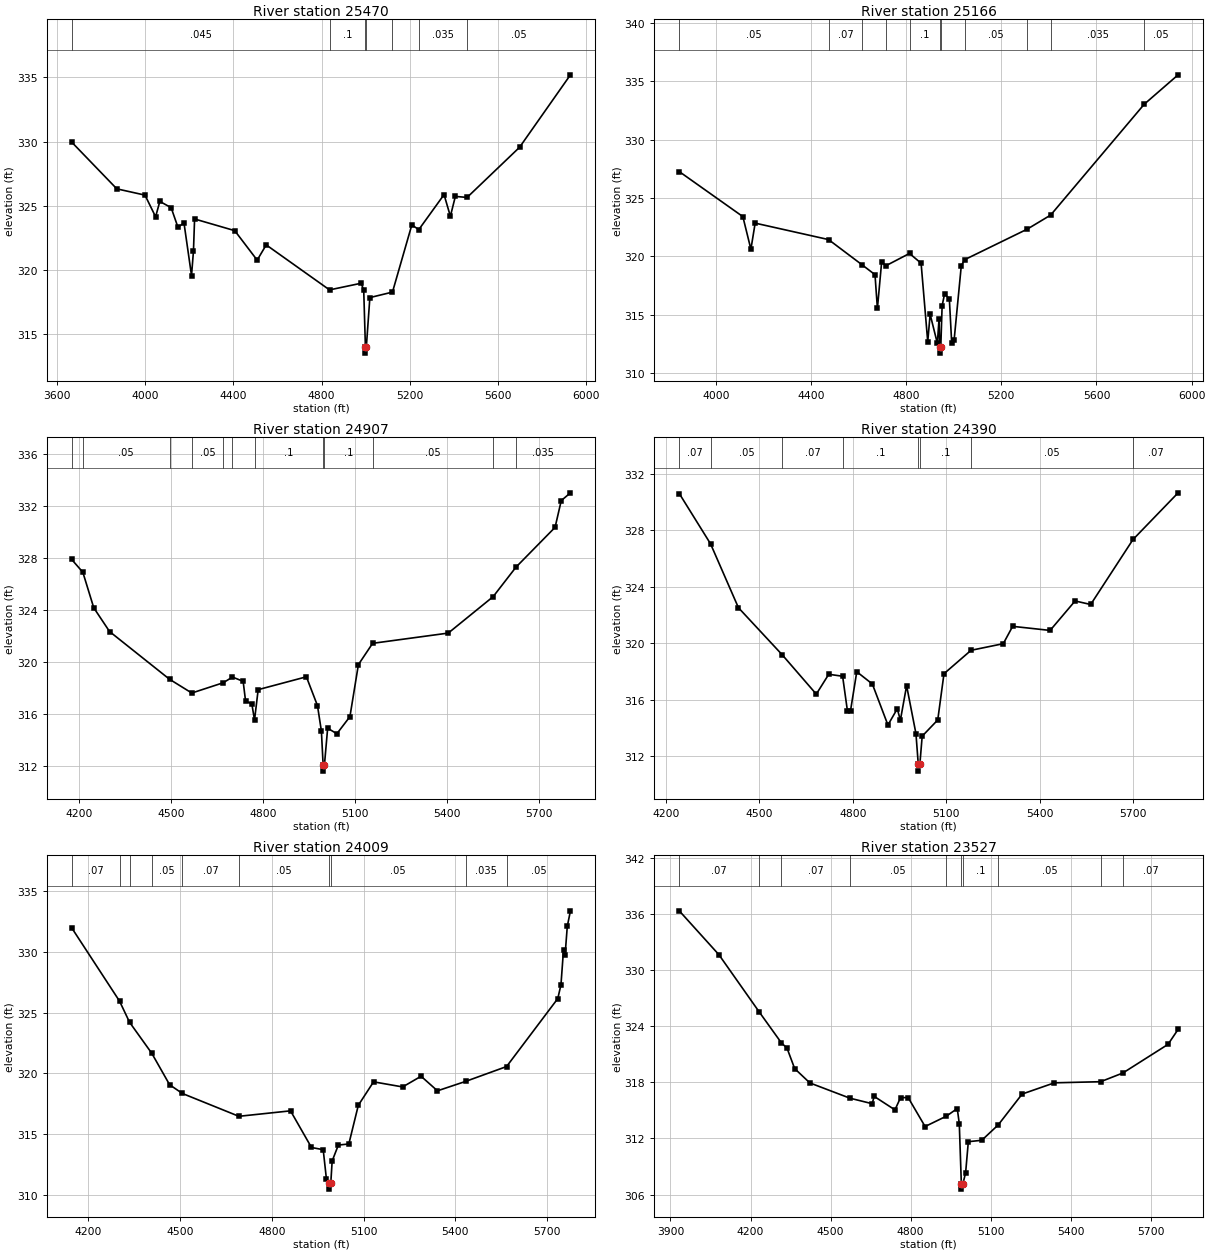
Type RM Length L Ch R = 1 ,25470   ,304,304,304
BEGIN DESCRIPTION:
CLEAR FORK CREEK 47.0
END DESCRIPTION:
XS GIS Cut Line= 3
      2492824.66     13766384.18      2491538.76     13766089.49
      2490633.21     13765832.29
#Sta/Elev= 30
  3667.3  329.96  3872.1  326.31  3999.9  325.82  4047.9  324.13  4067.1  325.33
  4118.4  324.84  4149.1  323.32  4176.6  323.65  4210.7  319.55  4219.5  321.45
  4224.6  323.96  4406.5  323.05  4508.2  320.75  4549.2  321.94  4836.2  318.43
  4979.6  318.95  4991.1   318.4  4998.7     314    4999   313.5    5003     314
  5018.9  317.83  5121.4  318.26  5209.1   323.5  5240.6  323.13  5355.1  325.86
  5383.8  324.17  5406.3  325.72  5459.6  325.64  5697.3  329.55  5927.9   335.2
#Mann= 7 ,-1 , 0
  3667.3    .045       0  4836.2      .1       0  4998.7     .05       0
    5003      .1       0  5121.4     .05       0  5240.6    .035       0
  5459.6     .05       0
Bank Sta=4998.7,5003
XS Rating Curve= 0 ,0
Exp/Cntr=0.3,0.1

Type RM Length L Ch R = 1 ,25166   ,259,259,259
BEGIN DESCRIPTION:
X18478
END DESCRIPTION:
XS GIS Cut Line= 3
      2492733.59     13765714.43      2492037.05      13765896.6
      2490670.74     13765725.14
#Sta/Elev= 30
  3846.2  327.26  4113.5   323.4  4147.3   320.6  4165.2  322.84  4473.6  321.43
  4616.3  319.24    4669  318.42  4679.1  315.52  4696.9   319.5  4715.2  319.19
  4814.1  320.24  4862.8   319.4  4890.7  312.67  4900.8  315.02  4931.1  312.53
  4938.3  314.65  4941.1  312.19  4941.4  311.69  4945.5  312.19  4951.2  315.76
  4961.3  316.75  4981.5  316.37  4991.5  312.52  5001.6  312.81  5031.8   319.2
  5046.3  319.71  5308.5  322.32  5407.4  323.53  5800.9  333.04  5943.2  335.56
#Mann= 11 ,-1 , 0
  3846.2     .05       0  4473.6     .07       0  4616.3      .1       0
  4715.2     .07       0  4814.1      .1       0  4941.1     .05       0
  4945.5      .1       0  5046.3     .05       0  5308.5     .07       0
  5407.4    .035       0  5800.9     .05       0
Bank Sta=4941.1,4945.5
XS Rating Curve= 0 ,0
Exp/Cntr=0.3,0.1

Type RM Length L Ch R = 1 ,24907   ,517,517,517
BEGIN DESCRIPTION:
CLEAR FORK CREEK 46.0
END DESCRIPTION:
XS GIS Cut Line= 3
      2492475.03     13765474.99        2491675.       13765675.
      2490875.01       13765625.
#Sta/Elev= 30
  4175.9  327.89  4212.5   326.9  4248.1  324.16  4299.6  322.33  4495.2  318.65
  4567.7  317.59    4670  318.38  4700.3  318.82  4735.1  318.49  4742.9  316.99
  4763.5  316.74  4772.2  315.51  4784.1  317.85  4941.3  318.84  4977.4  316.62
  4990.2  314.66  4995.8  312.07  4996.1  311.57  5000.2  312.07  5010.6  314.88
  5040.6  314.45  5083.2  315.77  5110.8  319.78  5157.2  321.42  5403.8  322.21
  5550.2  325.02  5624.5  327.29    5752  330.36  5772.1  332.42  5802.1  333.02
#Mann= 12 ,-1 , 0
  4175.9     .07       0  4212.5     .05       0  4495.2     .07       0
  4567.7     .05       0    4670      .1       0  4700.3     .07       0
  4772.2      .1       0  4995.8     .05       0  5000.2      .1       0
  5157.2     .05       0  5550.2     .07       0  5624.5    .035       0
Bank Sta=4995.8,5000.2
XS Rating Curve= 0 ,0
Exp/Cntr=0.3,0.1

Type RM Length L Ch R = 1 ,24390   ,381,381,381
BEGIN DESCRIPTION:
CLEAR FORK CREEK 45.0
END DESCRIPTION:
XS GIS Cut Line= 3
      2492525.01       13765425.      2491640.56      13765425.1
      2490924.96       13765375.
#Sta/Elev= 30
  4242.7  330.61  4343.2  327.04  4432.7  322.51  4572.9  319.18  4682.7  316.38
  4722.7  317.79  4767.2  317.65  4782.7  315.19  4792.7  315.22  4812.7  317.97
  4862.7   317.1  4912.7  314.19  4942.7  315.34  4952.7  314.53  4972.7  316.98
  5002.7  313.58  5010.1  311.42  5010.5  310.92  5015.3  311.42  5022.7   313.4
  5072.7  314.55  5092.7  317.83  5179.6  319.49  5283.1  319.96  5313.2  321.19
  5433.5   320.9  5513.7  322.99  5563.8  322.74  5699.7  327.35  5844.5  330.66
#Mann= 8 ,-1 , 0
  4242.7     .07       0  4343.2     .05       0  4572.9     .07       0
  4767.2      .1       0  5010.1     .05       0  5015.3      .1       0
  5179.6     .05       0  5699.7     .07       0
Bank Sta=5010.1,5015.3
XS Rating Curve= 0 ,0
Exp/Cntr=0.3,0.1

Type RM Length L Ch R = 1 ,24009   ,482,482,482
BEGIN DESCRIPTION:
CLEAR FORK CREEK 44.0
END DESCRIPTION:
XS GIS Cut Line= 3
      2492575.01       13765375.        2491775.       13765075.
      2491025.02       13764875.
#Sta/Elev= 30
  4145.6  331.99  4302.3  325.94    4335   324.2  4407.7  321.64    4466  319.05
  4507.8  318.33  4692.4  316.45  4861.2   316.9  4929.7  313.88    4968   313.7
  4978.6  311.27  4987.6  310.95    4988  310.45  4992.8  310.95  4997.3  312.77
  5017.5  314.08  5051.8  314.17  5082.8  317.36  5132.6  319.29  5227.7  318.87
  5287.9  319.75  5341.5  318.55    5434  319.33  5567.4  320.55  5734.8  326.15
  5745.2  327.29  5753.6  330.19  5758.8  329.78  5765.9  332.11  5776.2  333.38
#Mann= 10 ,-1 , 0
  4145.6     .07       0  4302.3     .05       0    4335     .07       0
  4407.7     .05       0  4507.8     .07       0  4692.4     .05       0
  4987.6     .05       0  4992.8     .05       0    5434    .035       0
  5567.4     .05       0
Bank Sta=4987.6,4992.8
XS Rating Curve= 0 ,0
Exp/Cntr=0.3,0.1

Type RM Length L Ch R = 1 ,23527   ,350,350,350
BEGIN DESCRIPTION:
CLEAR FORK CREEK 43.0
END DESCRIPTION:
XS GIS Cut Line= 3
      2492725.03     13765375.02        2491925.       13764675.
      2491124.98       13764775.
#Sta/Elev= 30
  3932.9  336.32  4081.5  331.63  4232.1  325.53  4315.1  322.23  4336.8  321.64
  4365.3  319.46  4422.2  317.93  4572.2   316.3  4655.7  315.71  4663.3  316.49
  4741.1  315.05    4762  316.35  4790.5  316.37  4854.1  313.27    4934  314.38
  4974.6  315.19  4982.2  313.59    4990  307.08  4990.4  306.58  4995.3  307.08
    5006  308.35  5016.1  311.65  5066.5   311.8    5128  313.44  5217.7  316.74
  5338.6  317.94  5511.9  318.06  5595.2  318.99  5764.4  322.05  5802.2  323.65
#Mann= 10 ,-1 , 0
  3932.9     .07       0  4232.1     .05       0  4315.1     .07       0
  4572.2     .05       0    4934      .1       0    4990     .05       0
  4995.3      .1       0    5128     .05       0  5511.9    .035       0
  5595.2     .07       0
Bank Sta=4990,4995.3
XS Rating Curve= 0 ,0
Exp/Cntr=0.3,0.1

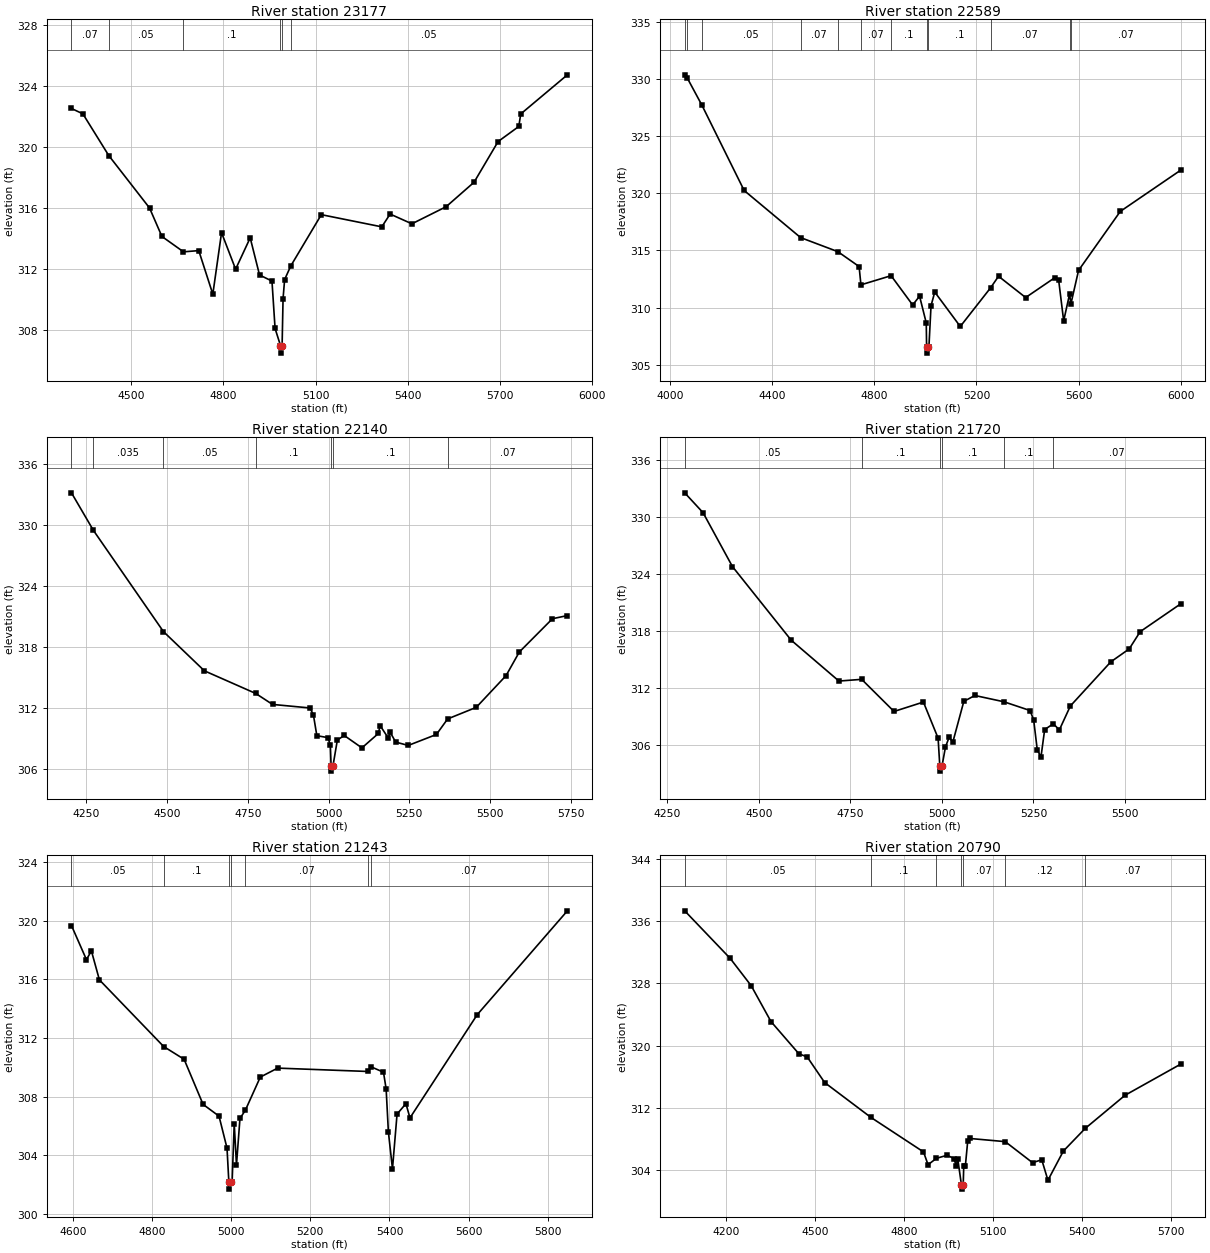
Type RM Length L Ch R = 1 ,23177   ,588,588,588
BEGIN DESCRIPTION:
CLEAR FORK CREEK 42.0
END DESCRIPTION:
XS GIS Cut Line= 3
      2492525.01     13764625.01      2492020.98       13764391.
      2490974.97       13764225.
#Sta/Elev= 30
  4305.1  322.54  4342.2  322.19  4426.6  319.45  4559.3  316.01  4599.6  314.14
  4669.9  313.13  4719.6  313.21  4765.4  310.35  4793.8  314.39  4839.6  311.99
  4887.1  314.05  4917.5  311.61    4958  311.21  4968.1   308.1  4985.7  306.98
  4986.1  306.48    4991  306.98  4994.1  310.06  4999.2  311.31  5019.4  312.21
  5118.7  315.57  5315.6  314.77  5342.7  315.61  5413.6  314.97    5525  316.09
  5616.1   317.7  5694.3  320.37  5761.7  321.36    5768  322.18  5919.9  324.75
#Mann= 6 ,-1 , 0
  4305.1     .07       0  4426.6     .05       0  4669.9      .1       0
  4985.7     .05       0    4991      .1       0  5019.4     .05       0
Bank Sta=4985.7,4991
XS Rating Curve= 0 ,0
Exp/Cntr=0.3,0.1

Type RM Length L Ch R = 1 ,22589   ,449,449,449
BEGIN DESCRIPTION:
CLEAR FORK CREEK 41.0
END DESCRIPTION:
XS GIS Cut Line= 3
      2492925.03     13763524.98        2492125.       13764025.
      2491325.03     13763425.02
#Sta/Elev= 30
  4056.6  330.35  4065.7  330.11  4124.4  327.68  4289.5  320.24  4510.8  316.12
  4656.9  314.89    4740  313.59  4747.2  311.99  4865.4  312.79  4949.9  310.23
    4977     311  5003.2  308.66  5004.6  306.52    5005  306.02  5010.1  306.52
  5013.6  306.55  5021.9  310.16  5036.5  311.36  5136.5  308.35  5255.3  311.73
  5286.5  312.74  5392.7  310.88  5507.3  312.62  5521.9  312.43  5541.7  308.84
  5565.1  311.21  5569.8   310.3    5600  313.25  5763.6  318.41    6000  322.01
#Mann= 12 ,-1 , 0
  4056.6     .05       0  4065.7    .035       0  4124.4     .05       0
  4510.8     .07       0  4656.9      .1       0  4747.2     .07       0
  4865.4      .1       0  5004.6     .05       0  5010.1      .1       0
  5255.3     .07       0  5565.1      .1       0  5569.8     .07       0
Bank Sta=5004.6,5010.1
XS Rating Curve= 0 ,0
Exp/Cntr=0.3,0.1

Type RM Length L Ch R = 1 ,22140   ,420,420,420
BEGIN DESCRIPTION:
CLEAR FORK CREEK 40.0
END DESCRIPTION:
XS GIS Cut Line= 3
      2492925.01       13763375.        2492175.       13763625.
      2491474.98     13763374.99
#Sta/Elev= 30
  4204.9  333.16  4272.6  329.47  4489.2   319.5    4616  315.63  4774.8   313.4
  4826.8  312.32  4942.8  311.97  4953.3  311.28  4963.9  309.24  4998.1  309.05
  5005.6  308.32    5008  306.25  5008.5  305.75  5013.7  306.25  5027.3  308.81
  5048.6  309.26  5103.3  308.04  5154.2  309.46  5159.5  310.24    5185     309
  5190.3   309.6  5207.8  308.61  5246.6  308.28  5333.7  309.36  5368.4  310.89
  5456.9  312.03  5549.2  315.16  5590.1  317.48  5692.6  320.76  5738.8  321.07
#Mann= 7 ,-1 , 0
  4204.9     .05       0  4272.6    .035       0  4489.2     .05       0
  4774.8      .1       0    5008     .05       0  5013.7      .1       0
  5368.4     .07       0
Bank Sta=5008,5013.7
XS Rating Curve= 0 ,0
Exp/Cntr=0.3,0.1

Type RM Length L Ch R = 1 ,21720   ,477,477,477
BEGIN DESCRIPTION:
CLEAR FORK CREEK 39.0
END DESCRIPTION:
XS GIS Cut Line= 3
      2492874.98       13763225.        2492175.       13763275.
      2491524.98       13763325.
#Sta/Elev= 30
  4297.9  332.52    4348  330.43  4428.2  324.76  4588.6  317.01  4718.9  312.71
    4781  312.89  4869.3  309.51  4949.5   310.5  4989.6   306.7  4994.3  303.73
  4994.8  303.23  5000.1  303.73  5009.7  305.77  5019.7   306.8  5029.7  306.27
  5059.8  310.57  5089.9  311.19  5169.2  310.53  5240.4  309.61  5250.4  308.64
  5260.4  305.44  5270.5  304.74  5280.5  307.61  5304.2  308.21  5320.6  307.57
  5350.7  310.09    5461  314.73  5511.2  316.09  5541.3  317.91  5651.6  320.83
#Mann= 6 ,-1 , 0
  4297.9     .05       0    4781      .1       0  4994.3     .05       0
  5000.1      .1       0  5169.2      .1       0  5304.2     .07       0
Bank Sta=4994.3,5000.1
XS Rating Curve= 0 ,0
Exp/Cntr=0.3,0.1

Type RM Length L Ch R = 1 ,21243   ,453,453,453
BEGIN DESCRIPTION:
CLEAR FORK CREEK 38.0
END DESCRIPTION:
XS GIS Cut Line= 3
      2492675.04       13762925.        2492275.       13762875.
      2491524.96     13763275.02
#Sta/Elev= 30
  4596.4  319.66  4634.2  317.34  4646.8  317.93    4667  315.96  4829.4  311.42
  4881.1  310.55    4929  307.48  4969.3  306.68  4989.5   304.5  4994.1  302.21
  4994.6  301.71  4999.9  302.21  5002.4  302.21  5007.7  306.17  5013.4  303.36
  5022.2  306.52  5035.8  307.08  5073.6  309.34  5117.5  309.95    5347  309.72
  5352.6  310.05  5384.9  309.67  5391.6  308.53  5397.3   305.6  5407.6  303.09
  5419.2  306.82  5441.6  307.53  5451.8  306.56  5621.8  313.59  5849.6  320.66
#Mann= 7 ,-1 , 0
  4596.4     .05       0  4829.4      .1       0  4994.1     .05       0
  4999.9      .1       0  5035.8     .07       0    5347      .1       0
  5352.6     .07       0
Bank Sta=4994.1,4999.9
XS Rating Curve= 0 ,0
Exp/Cntr=0.3,0.1

Type RM Length L Ch R = 1 ,20790   ,548,548,548
BEGIN DESCRIPTION:
CLEAR FORK CREEK 37.0
END DESCRIPTION:
XS GIS Cut Line= 3
        2493025.       13762975.        2492225.       13762475.
      2491525.01       13762275.
#Sta/Elev= 30
    4060  337.31  4213.3   331.2  4284.1  327.69  4350.7  323.09    4445  318.94
  4472.7  318.55  4531.7  315.25  4687.4  310.78  4864.8  306.34  4880.2   304.7
  4908.6  305.52  4944.4  305.91    4968  305.48  4974.5  304.56  4980.4  305.41
  4992.8  302.06  4993.3  301.56  4998.6  302.06  5000.5  304.57    5006  304.57
  5013.8  307.72  5020.3  308.07  5140.3  307.66  5232.2  304.96  5263.4  305.33
  5284.2   302.7  5336.2  306.45  5409.6  309.35  5544.2  313.62  5731.4  317.61
#Mann= 7 ,-1 , 0
    4060     .05       0  4687.4      .1       0  4908.6     .07       0
  4992.8     .05       0  4998.6     .07       0  5140.3     .12       0
  5409.6     .07       0
Bank Sta=4992.8,4998.6
XS Rating Curve= 0 ,0
Exp/Cntr=0.3,0.1

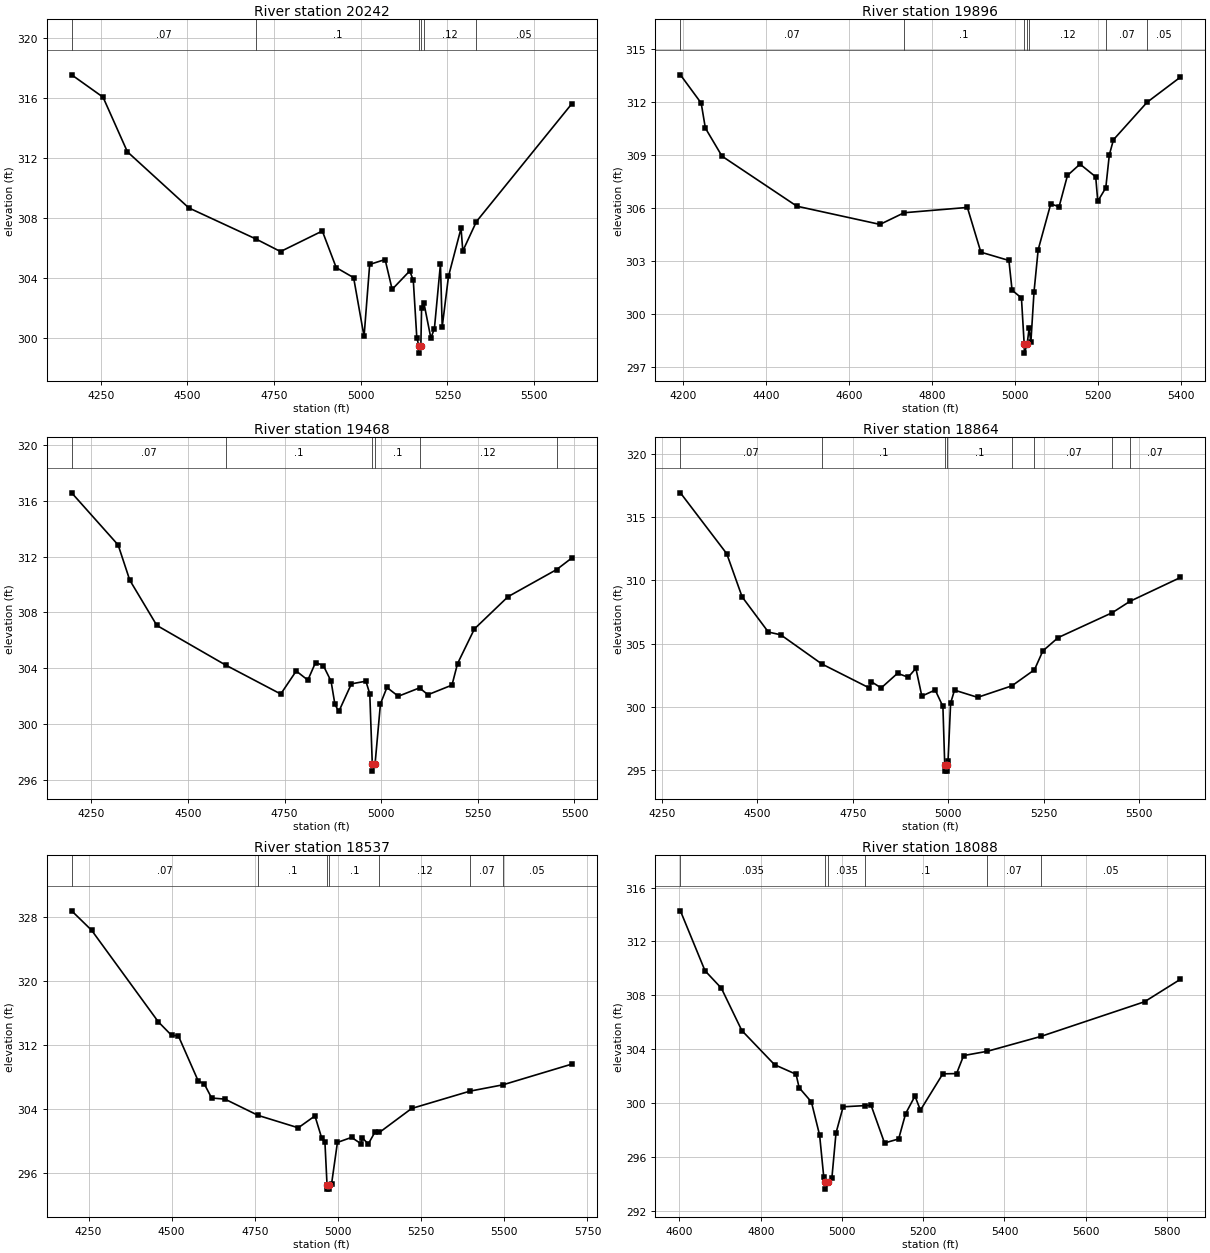
Type RM Length L Ch R = 1 ,20242   ,346,346,346
BEGIN DESCRIPTION:
CLEAR FORK CREEK 36.0
END DESCRIPTION:
XS GIS Cut Line= 3
      2493055.11     13762199.58      2492197.79     13762124.57
      2491625.03       13762225.
#Sta/Elev= 30
  4166.2  317.55  4256.7  316.06  4326.9  312.42  4504.1  308.68  4697.5  306.61
  4768.6  305.77  4889.1  307.14  4929.2   304.7  4979.4  304.03  5009.5  300.11
  5025.7  304.91  5070.2  305.24  5090.5  303.25  5141.3  304.48  5151.5  303.85
  5161.6  300.04  5167.4   299.5  5167.9     299  5173.3   299.5  5175.4  302.02
  5181.9  302.36  5202.2     300  5212.4  300.64  5229.8  304.93  5234.9  300.75
    5253  304.12  5289.2  307.32  5294.3  305.81  5333.6  307.77  5608.3  315.61
#Mann= 6 ,-1 , 0
  4166.2     .07       0  4697.5      .1       0  5167.4     .05       0
  5173.3      .1       0  5181.9     .12       0  5333.6     .05       0
Bank Sta=5167.4,5173.3
XS Rating Curve= 0 ,0
Exp/Cntr=0.3,0.1

Type RM Length L Ch R = 1 ,19896   ,428,428,428
BEGIN DESCRIPTION:
CLEAR FORK CREEK 35.0
END DESCRIPTION:
XS GIS Cut Line= 3
        2492925.       13761925.        2492125.       13761875.
      2491724.98       13761925.
#Sta/Elev= 30
  4193.2  313.53  4243.3  311.93  4253.3  310.52  4293.4  308.93  4473.8   306.1
  4674.1  305.07  4732.2  305.73  4884.6  306.03  4917.1   303.5  4984.7  303.03
  4992.3  301.35  5014.9  300.91  5021.5  298.29    5022  297.79  5028.5  298.29
  5033.4  299.19  5037.6   298.4  5045.2  301.26  5055.2  303.64  5085.5  306.23
  5105.6  306.07  5125.8  307.84    5156  308.48  5193.8  307.76  5198.8  306.38
  5218.1  307.14  5226.6     309  5236.6  309.86  5317.7  311.98  5397.9   313.4
#Mann= 7 ,-1 , 0
  4193.2     .07       0  4732.2      .1       0  5021.5     .05       0
  5028.5      .1       0  5033.4     .12       0  5218.1     .07       0
  5317.7     .05       0
Bank Sta=5021.5,5028.5
XS Rating Curve= 0 ,0
Exp/Cntr=0.3,0.1

Type RM Length L Ch R = 1 ,19468   ,604,604,604
BEGIN DESCRIPTION:
CLEAR FORK CREEK 34.0
END DESCRIPTION:
XS GIS Cut Line= 3
      2493025.02       13761475.        2492225.       13761525.
      2491775.02     13761724.99
#Sta/Elev= 30
  4198.8  316.57  4319.1  312.83  4349.1  310.31  4419.2  307.06  4597.1  304.22
  4739.9  302.14  4779.9  303.79    4810  303.14    4830   304.4  4850.1  304.18
  4870.1  303.06  4880.1  301.39  4890.2  300.89  4922.7  302.87  4960.3  303.06
  4970.3  302.15  4976.8  297.11  4977.3  296.61  4983.9  297.11  4997.9  301.44
  5014.7  302.61  5044.1  301.98    5099  302.58  5120.8  302.09    5183  302.78
  5197.4  304.32  5241.1  306.81    5328  309.12  5454.1  311.07  5492.8  311.89
#Mann= 6 ,-1 , 0
  4198.8     .07       0  4597.1      .1       0  4976.8     .05       0
  4983.9      .1       0    5099     .12       0  5454.1     .07       0
Bank Sta=4976.8,4983.9
XS Rating Curve= 0 ,0
Exp/Cntr=0.3,0.1

Type RM Length L Ch R = 1 ,18864   ,327,327,327
BEGIN DESCRIPTION:
CLEAR FORK CREEK 33.0
END DESCRIPTION:
XS GIS Cut Line= 3
      2493025.02       13761275.      2492197.79     13761149.41
      2491725.03       13761125.
#Sta/Elev= 30
  4298.1  316.92  4419.5  312.11  4459.8   308.7  4528.5  305.92  4561.1   305.7
  4668.5   303.4  4793.2   301.5  4798.3     302  4824.1   301.5    4867  302.66
  4894.9  302.35  4915.1  303.05  4930.7  300.86  4965.7  301.34  4985.9  300.04
  4990.7  295.43  4991.2  294.93  4997.4  294.93  4997.9  295.43  4999.4  295.76
  5006.1   300.3  5016.3  301.33  5076.9  300.76  5166.7  301.67  5225.8  302.94
  5247.8  304.43  5287.8  305.48  5429.7  307.45  5476.2  308.35  5608.2  310.23
#Mann= 8 ,-1 , 0
  4298.1     .07       0  4668.5      .1       0  4990.7     .05       0
  4997.9      .1       0  5166.7     .12       0  5225.8     .07       0
  5429.7     .12       0  5476.2     .07       0
Bank Sta=4990.7,4997.9
XS Rating Curve= 0 ,0
Exp/Cntr=0.3,0.1

Type RM Length L Ch R = 1 ,18537   ,449,449,449
BEGIN DESCRIPTION:
CLEAR FORK CREEK 32.0
END DESCRIPTION:
XS GIS Cut Line= 3
      2493224.96       13760825.        2492425.       13760875.
        2491725.       13760925.
#Sta/Elev= 30
  4199.3  328.82  4259.4  326.38  4459.8  314.92  4499.8  313.22  4519.9  313.18
    4580  307.49  4597.5  307.18  4620.1  305.38  4660.2  305.24    4760   303.2
  4880.6  301.65  4930.7  303.14  4950.7  300.41  4960.7  299.87  4967.1  294.47
  4967.6  293.97  4973.9  293.97  4974.4  294.47  4980.8  294.65  4998.3  299.82
  5040.9  300.45  5068.5  299.67  5073.5  300.38    5091  299.62  5111.1  301.11
  5124.5  301.07  5221.4  304.07  5396.7  306.24  5495.6  307.03  5702.6  309.62
#Mann= 7 ,-1 , 0
  4199.3     .07       0    4760      .1       0  4967.1     .05       0
  4974.4      .1       0  5124.5     .12       0  5396.7     .07       0
  5495.6     .05       0
Bank Sta=4967.1,4974.4
XS Rating Curve= 0 ,0
Exp/Cntr=0.3,0.1

Type RM Length L Ch R = 1 ,18088   ,437,437,437
BEGIN DESCRIPTION:
CLEAR FORK CREEK 31.0
END DESCRIPTION:
XS GIS Cut Line= 3
      2492875.04       13760425.        2492475.       13760475.
        2491725.       13760825.
#Sta/Elev= 30
  4602.3  314.28  4662.8  309.83  4703.1  308.53  4753.5  305.38  4834.1  302.84
    4887  302.13  4894.6  301.13  4924.8  300.07    4945   297.6  4955.1  294.51
  4958.9  294.09  4959.4  293.59  4966.3  294.09  4975.2  294.42  4985.3  297.76
  5002.9  299.71  5056.8   299.8  5071.7  299.82  5104.8  297.02  5139.5  297.32
  5156.8  299.21  5179.7  300.51  5193.1  299.46  5248.2  302.16  5282.1  302.18
  5299.5  303.52  5358.1  303.84  5489.4  304.94  5744.8  307.52  5833.1  309.19
#Mann= 6 ,-1 , 0
  4602.3    .035       0  4958.9    .035       0  4966.3    .035       0
  5056.8      .1       0  5358.1     .07       0  5489.4     .05       0
Bank Sta=4958.9,4966.3
XS Rating Curve= 0 ,0
Exp/Cntr=0.3,0.1

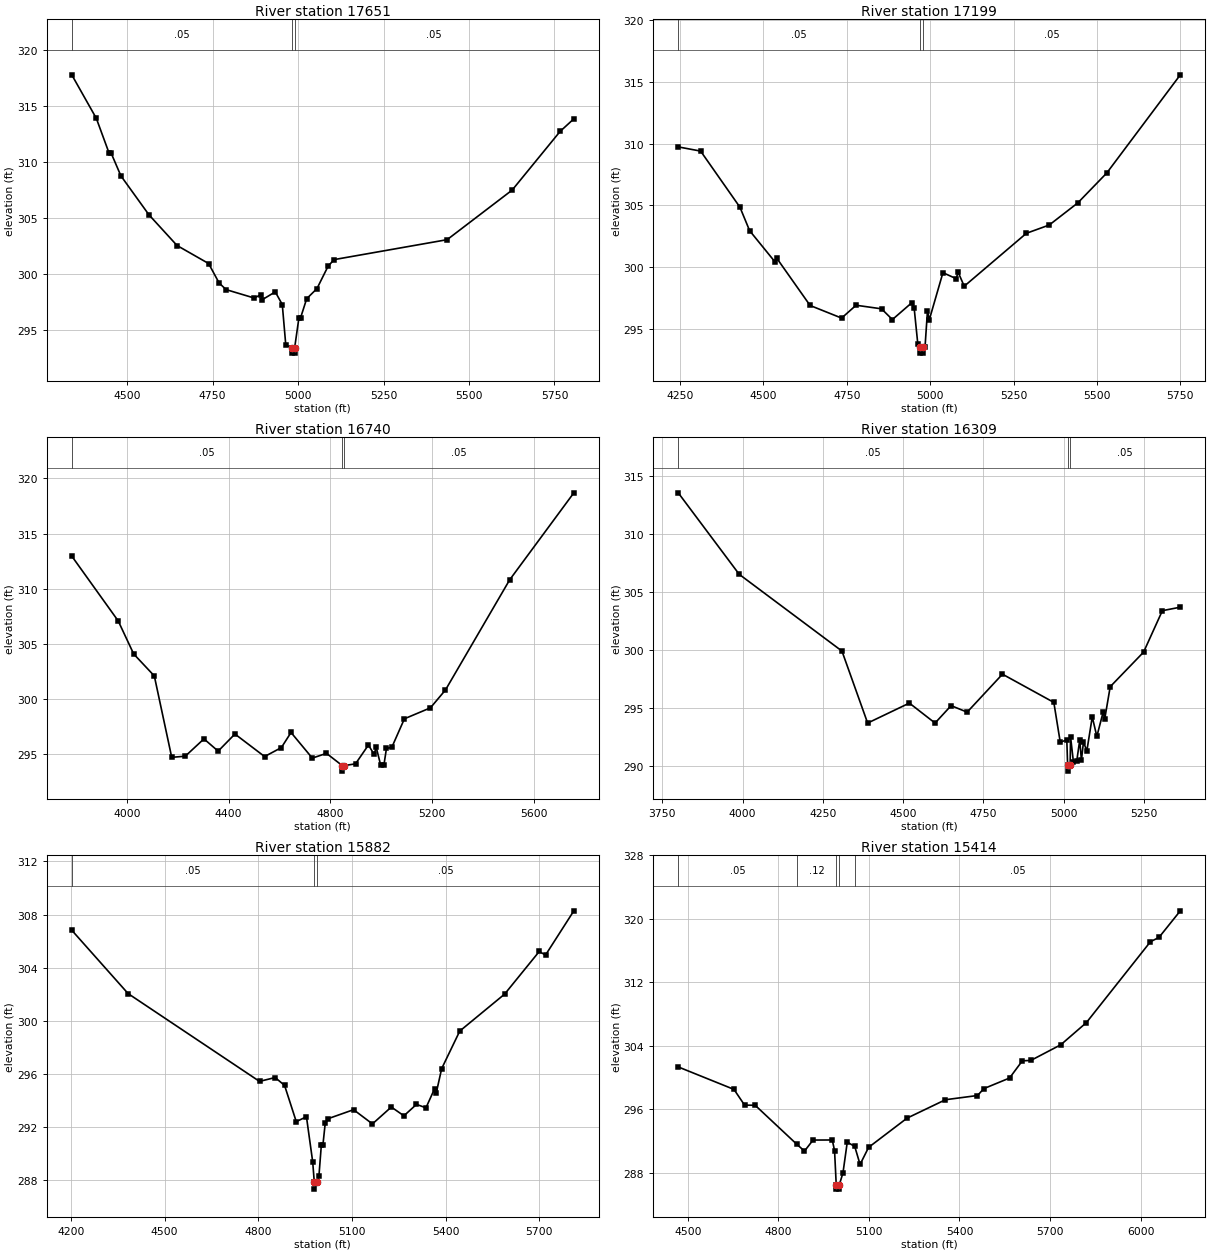
Type RM Length L Ch R = 1 ,17651   ,452,452,452
BEGIN DESCRIPTION:
CLEAR FORK CREEK 30.0
END DESCRIPTION:
XS GIS Cut Line= 3
      2492925.04     13760325.01        2492275.       13760175.
      2491474.98       13760125.
#Sta/Elev= 30
  4337.9  317.81  4409.8  313.92  4447.4  310.79  4452.5  310.86  4481.6  308.79
  4563.7  305.31  4645.8  302.57  4738.2  300.96    4769  299.22  4789.5  298.63
  4871.6  297.88  4890.4  298.17  4895.6  297.74  4933.2  298.43  4953.7   297.3
    4964  293.66  4982.5  293.46    4983  292.96  4989.5  292.96    4990  293.46
  5002.5  296.14  5007.5  296.14  5025.1  297.82  5055.1  298.72  5087.7  300.72
  5105.2  301.31  5435.9  303.09  5626.2  307.52  5766.5  312.76  5806.6  313.88
#Mann= 3 ,-1 , 0
  4337.9     .05       0  4982.5     .05       0    4990     .05       0
Bank Sta=4982.5,4990
XS Rating Curve= 0 ,0
Exp/Cntr=0.3,0.1

Type RM Length L Ch R = 1 ,17199   ,459,459,459
BEGIN DESCRIPTION:
CLEAR FORK CREEK 29.0
END DESCRIPTION:
XS GIS Cut Line= 3
      2492825.01       13760075.        2492125.       13759775.
      2491424.99       13760025.
#Sta/Elev= 30
  4244.8  309.73  4311.9  309.39  4429.8  304.84  4458.8  302.94  4534.9  300.41
  4540.4   300.7  4640.1  296.88  4734.4  295.86  4777.9   296.9  4854.1  296.61
  4886.7  295.74  4944.7   297.1    4952  296.66  4962.9  293.75    4970  293.52
  4970.5  293.02    4977  293.02  4977.5  293.52  4984.6  293.54  4991.9  296.47
  4997.3  295.72  5038.2  299.54  5078.1  299.05  5083.4   299.6    5102  298.44
  5288.3  302.73  5356.8   303.4  5442.3  305.19  5529.4  307.62  5749.7  315.57
#Mann= 3 ,-1 , 0
  4244.8     .05       0    4970     .05       0  4977.5     .05       0
Bank Sta=4970,4977.5
XS Rating Curve= 0 ,0
Exp/Cntr=0.3,0.1

Type RM Length L Ch R = 1 ,16740   ,431,431,431
BEGIN DESCRIPTION:
CLEAR FORK CREEK 28.0
END DESCRIPTION:
XS GIS Cut Line= 3
      2493174.97       13759175.        2491975.       13759375.
      2491224.96     13759475.01
#Sta/Elev= 30
  3783.5  312.96    3966  307.09  4026.8   304.1  4107.9  302.11  4176.3  294.74
  4229.5  294.84    4303  296.41  4358.8   295.3  4424.7  296.85  4541.3  294.81
  4607.2  295.62  4645.2  296.99  4728.8  294.67  4784.6   295.1  4846.6  293.99
  4847.1  293.49  4854.3  293.99  4898.6  294.15  4949.3  295.85  4972.1     295
  4979.7  295.67  4997.5  294.04  5010.1  294.02  5020.2  295.54  5041.6  295.66
  5090.8  298.23    5193  299.22  5252.2  300.84  5504.4  310.81  5756.7  318.69
#Mann= 3 ,-1 , 0
  3783.5     .05       0  4846.6     .05       0  4854.3     .05       0
Bank Sta=4846.6,4854.3
XS Rating Curve= 0 ,0
Exp/Cntr=0.3,0.1

Type RM Length L Ch R = 1 ,16309   ,427,427,427
BEGIN DESCRIPTION:
CLEAR FORK CREEK 27.0
END DESCRIPTION:
XS GIS Cut Line= 3
      2493174.96       13759075.        2491975.       13759075.
      2491624.97     13759175.01
#Sta/Elev= 30
  3799.6  313.53  3989.6  306.51  4309.6   299.9  4389.6   293.7  4519.6  295.42
  4599.6   293.7  4649.6   295.2  4699.6  294.64  4809.6  297.91  4969.6  295.48
  4989.6  292.05    5010  292.25  5012.6  290.06  5013.1  289.56  5020.4  290.06
  5021.7  292.52  5030.8  290.31  5041.2  290.47  5050.3  292.23  5055.5   290.5
    5062  292.08  5072.4  291.29  5089.3  294.23  5103.6  292.55  5123.1  294.63
  5128.3  294.08  5145.2  296.83  5249.2  299.81  5307.7  303.38  5363.6  303.68
#Mann= 3 ,-1 , 0
  3799.6     .05       0  5012.6     .05       0  5020.4     .05       0
Bank Sta=5012.6,5020.4
XS Rating Curve= 0 ,0
Exp/Cntr=0.3,0.1

Type RM Length L Ch R = 1 ,15882   ,468,468,468
BEGIN DESCRIPTION:
CLEAR FORK CREEK 26.0
END DESCRIPTION:
XS GIS Cut Line= 3
      2493025.03       13758825.        2492225.       13758775.
      2491425.01       13758875.
#Sta/Elev= 30
  4202.9  306.82  4383.3  302.05  4804.1  295.44  4854.2  295.73  4884.3  295.14
  4921.8  292.41  4954.4  292.78  4974.4  289.39  4979.6  287.83  4980.1  287.33
  4989.2  287.83  4994.5  288.35    5002  290.62    5007  290.62  5014.6  292.31
  5024.6  292.64  5105.3  293.31  5165.7  292.24  5226.2  293.51  5266.5  292.85
  5306.8  293.71  5337.1  293.45  5364.8  294.89  5369.8  294.54  5387.4   296.4
  5445.4  299.23    5589  302.01  5699.9  305.22    5720  304.95  5810.7  308.28
#Mann= 3 ,-1 , 0
  4202.9     .05       0  4979.6     .05       0  4989.2     .05       0
Bank Sta=4979.6,4989.2
XS Rating Curve= 0 ,0
Exp/Cntr=0.3,0.1

Type RM Length L Ch R = 1 ,15414   ,447,447,447
BEGIN DESCRIPTION:
CLEAR FORK CREEK 25.0
END DESCRIPTION:
XS GIS Cut Line= 3
      2492824.98     13758724.98        2492425.       13758375.
      2491625.03     13757575.03
#Sta/Elev= 30
  4468.5  301.33  4653.1   298.5  4688.2  296.52  4723.3   296.5  4860.3  291.62
  4886.6  290.73    4915  292.12  4978.6  292.13  4986.2   290.8  4991.8  286.44
  4992.3  285.94  5001.1  285.94  5001.6  286.44  5014.1  287.99  5028.3  291.86
  5053.1  291.31  5070.7  289.05    5099   291.2  5226.3  294.88  5353.5   297.2
  5459.6  297.73  5480.8   298.6  5565.7  299.93  5608.1   302.1  5636.4  302.15
  5735.4  304.12  5820.2  306.91  6032.4   317.1  6060.6  317.64  6131.3  320.99
#Mann= 5 ,-1 , 0
  4468.5     .05       0  4860.3     .12       0  4991.8     .05       0
  5001.6     .12       0  5053.1     .05       0
Bank Sta=4991.8,5001.6
XS Rating Curve= 0 ,0
Exp/Cntr=0.3,0.1

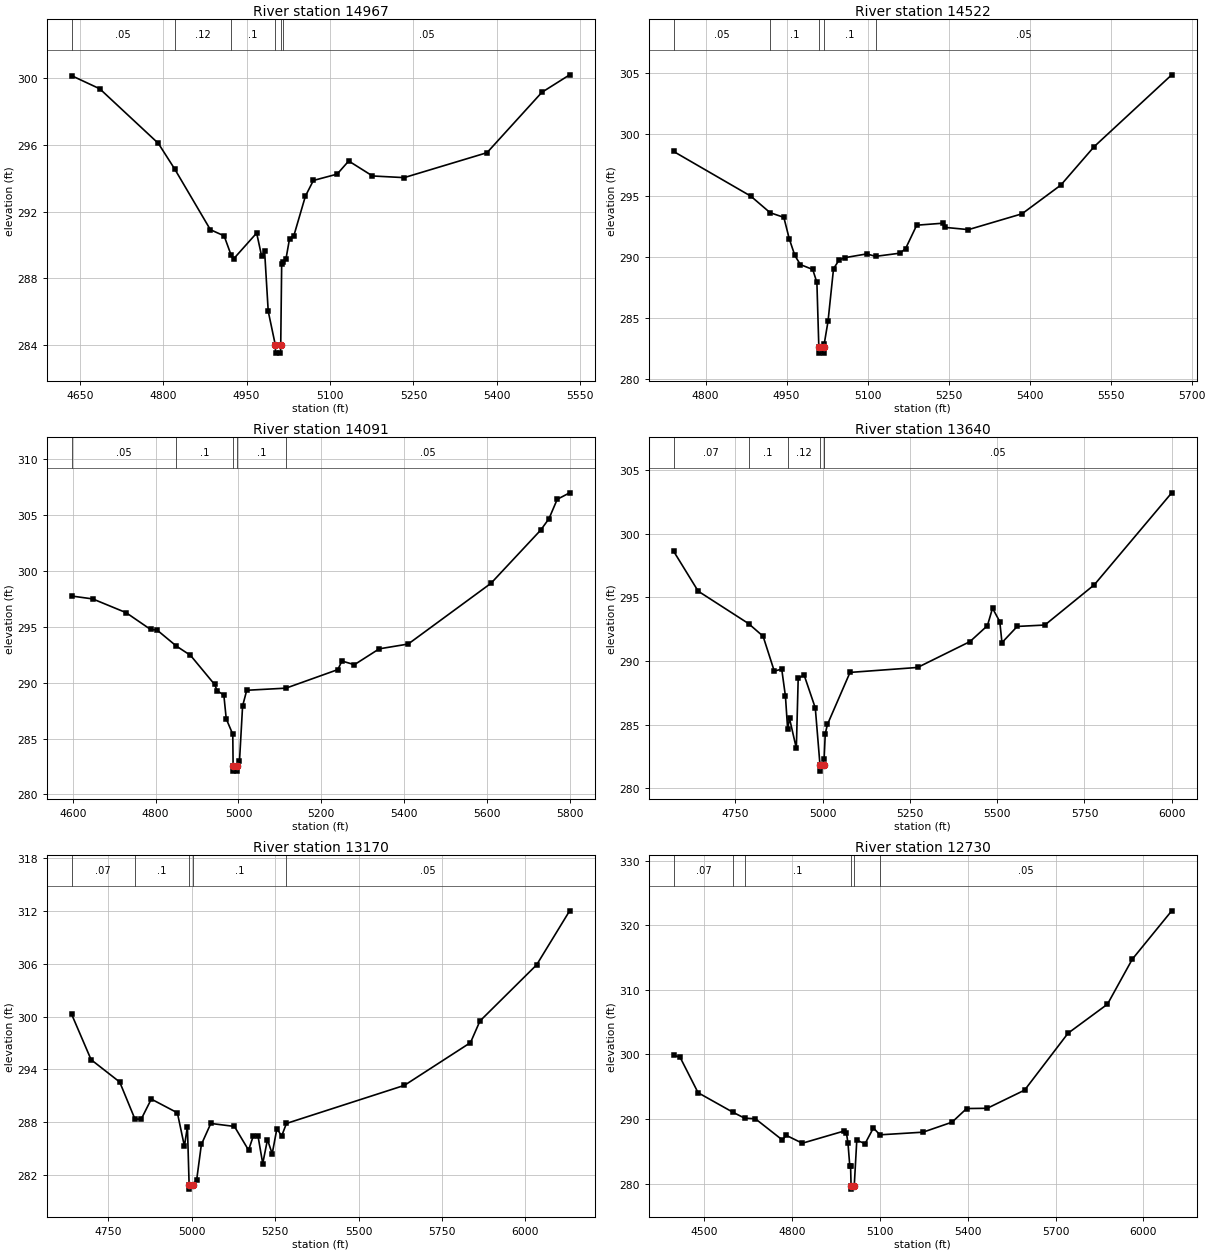
Type RM Length L Ch R = 1 ,14967   ,445,445,445
BEGIN DESCRIPTION:
CLEAR FORK CREEK 24.0
END DESCRIPTION:
XS GIS Cut Line= 3
      2492975.04     13758225.01        2492625.       13758125.
      2492274.97     13757724.96
#Sta/Elev= 30
  4635.3  300.17    4686  299.38  4791.3   296.1  4820.7  294.56  4884.9  290.91
  4909.6  290.54  4922.3  289.37  4926.5  289.15  4968.1  290.71  4977.2   289.3
  4982.4  289.62  4988.9  286.01  5001.6  283.99  5002.1  283.49  5010.9  283.49
  5011.4  283.99  5013.1  288.87  5015.9  288.97  5020.7  289.13  5027.3  290.38
  5034.9  290.54  5055.8  292.93  5070.1  293.87  5112.8  294.25  5133.6  295.04
  5176.4  294.14  5233.3  294.04  5382.3  295.54    5481  299.17  5530.9  300.22
#Mann= 6 ,-1 , 0
  4635.3     .05       0  4820.7     .12       0  4922.3      .1       0
  5001.6     .05       0  5011.4      .1       0  5015.9     .05       0
Bank Sta=5001.6,5011.4
XS Rating Curve= 0 ,0
Exp/Cntr=0.3,0.1

Type RM Length L Ch R = 1 ,14522   ,431,431,431
BEGIN DESCRIPTION:
CLEAR FORK CREEK 23.0
END DESCRIPTION:
XS GIS Cut Line= 3
      2493125.03     13757825.01        2492875.       13757775.
      2492224.97     13757624.99
#Sta/Elev= 30
    4741  298.59  4883.8  294.95  4919.6   293.6    4945  293.22  4955.2  291.45
  4965.4  290.11  4975.6  289.37  4998.5  288.97  5006.2  287.91  5009.8  282.65
  5010.3  282.15  5019.2  282.15  5019.7  282.65  5019.9  282.93  5026.8  284.74
    5037  289.03  5047.3  289.74  5057.6  289.93  5098.6  290.24  5114.8  290.04
  5160.2   290.3  5170.5  290.68    5191  292.58  5238.9  292.74    5244   292.4
  5286.8  292.22    5386  293.51  5457.8  295.85  5519.4  298.98  5663.1  304.84
#Mann= 5 ,-1 , 0
    4741     .05       0  4919.6      .1       0  5009.8     .05       0
  5019.7      .1       0  5114.8     .05       0
Bank Sta=5009.8,5019.7
XS Rating Curve= 0 ,0
Exp/Cntr=0.3,0.1

Type RM Length L Ch R = 1 ,14091   ,451,451,451
BEGIN DESCRIPTION:
CLEAR FORK CREEK 22.0
END DESCRIPTION:
XS GIS Cut Line= 3
        2493175.     13757724.99        2492975.       13757375.
        2492175.       13757375.
#Sta/Elev= 30
  4596.9  297.76    4648   297.5  4728.6  296.27  4787.6  294.77  4803.5  294.71
  4850.3  293.27  4884.1  292.45  4942.4  289.84  4948.9  289.26  4964.7   288.9
  4970.5  286.76  4986.3  285.38  4987.1  282.58  4987.6  282.08  4996.6  282.08
  4997.1  282.58  5002.5  282.97    5010  287.91    5020  289.32  5114.8  289.51
    5240  291.17    5250  291.94    5280  291.61    5340  293.03    5410  293.46
    5610   298.9    5730  303.66    5750  304.68    5770  306.42    5800     307
#Mann= 5 ,-1 , 0
  4596.9     .05       0  4850.3      .1       0  4987.1     .05       0
  4997.1      .1       0  5114.8     .05       0
Bank Sta=4987.1,4997.1
XS Rating Curve= 0 ,0
Exp/Cntr=0.3,0.1

Type RM Length L Ch R = 1 ,13640   ,470,470,470
BEGIN DESCRIPTION:
CLEAR FORK CREEK 21.0
END DESCRIPTION:
XS GIS Cut Line= 3
      2493625.02     13757225.01        2493225.       13757075.
      2492425.02     13756475.02
#Sta/Elev= 30
  4572.8  298.62  4643.1  295.49  4787.6  292.94  4829.1  291.95  4861.2  289.21
  4882.5  289.37  4893.2  287.23  4899.4  284.68  4904.8   285.5  4924.4  283.15
  4929.7  288.64  4946.6  288.91  4978.7  286.32  4992.1  281.86  4992.6  281.36
  5002.6  281.86    5004  282.34  5007.3  284.31  5013.6  285.03  5078.2  289.11
  5271.9   289.5  5421.9  291.53  5471.9  292.78  5486.5  294.15  5507.3   293.1
  5513.6  291.45  5557.3  292.72  5636.5  292.83  5778.2  295.99    6000  303.21
#Mann= 6 ,-1 , 0
  4572.8     .07       0  4787.6      .1       0  4899.4     .12       0
  4992.1     .05       0  5002.6     .12       0    5004     .05       0
Bank Sta=4992.1,5002.6
XS Rating Curve= 0 ,0
Exp/Cntr=0.3,0.1

Type RM Length L Ch R = 1 ,13170   ,440,440,440
BEGIN DESCRIPTION:
CLEAR FORK CREEK 20.0
END DESCRIPTION:
XS GIS Cut Line= 3
      2493674.98     13757024.97        2493475.       13756725.
      2492674.99     13755924.99
#Sta/Elev= 30
  4640.4  300.29  4698.9  295.11  4784.6  292.57  4830.3  288.35  4849.2  288.36
  4879.2  290.63  4957.3  289.07  4978.4  285.27  4987.4   287.5  4992.5  280.89
    4993  280.39  5003.3  280.89  5015.1  281.44  5029.2  285.47  5057.5  287.86
  5128.2  287.52  5170.6  284.82  5184.8  286.45  5198.9  286.41    5213   283.3
  5227.2  286.02  5241.3  284.41  5255.5  287.28  5269.6  286.42    5284  287.86
  5637.3  292.19  5835.3  297.05  5863.6  299.51  6033.3  305.89  6132.3  312.04
#Mann= 5 ,-1 , 0
  4640.4     .07       0  4830.3      .1       0  4992.5     .05       0
  5003.3      .1       0    5284     .05       0
Bank Sta=4992.5,5003.3
XS Rating Curve= 0 ,0
Exp/Cntr=0.3,0.1

Type RM Length L Ch R = 1 ,12730   ,469,469,469
BEGIN DESCRIPTION:
CLEAR FORK CREEK 19.0
END DESCRIPTION:
XS GIS Cut Line= 3
      2493725.01     13756975.02        2493475.       13756425.
      2492674.97     13755674.97
#Sta/Elev= 30
  4395.7  299.87  4417.7  299.55  4479.2  294.06  4598.4  291.03  4638.1  290.12
  4674.7  290.03    4767  286.74  4780.2  287.46  4835.1  286.24  4977.9  288.13
  4985.6  287.86  4991.1  286.22  4997.1  282.75  4999.9  282.75  5001.6  279.63
  5002.1  279.13  5012.4  279.63  5021.1   286.7  5049.4  286.17  5077.8   288.6
  5100.1  287.54  5247.3  287.95  5346.4   289.5  5396.2  291.61  5466.6  291.65
  5594.1  294.46  5742.6  303.28  5877.1  307.77  5961.9  314.74  6096.5  322.23
#Mann= 6 ,-1 , 0
  4395.7     .07       0  4598.4     .12       0  4638.1      .1       0
  5001.6     .05       0  5012.4      .1       0  5100.1     .05       0
Bank Sta=5001.6,5012.4
XS Rating Curve= 0 ,0
Exp/Cntr=0.3,0.1