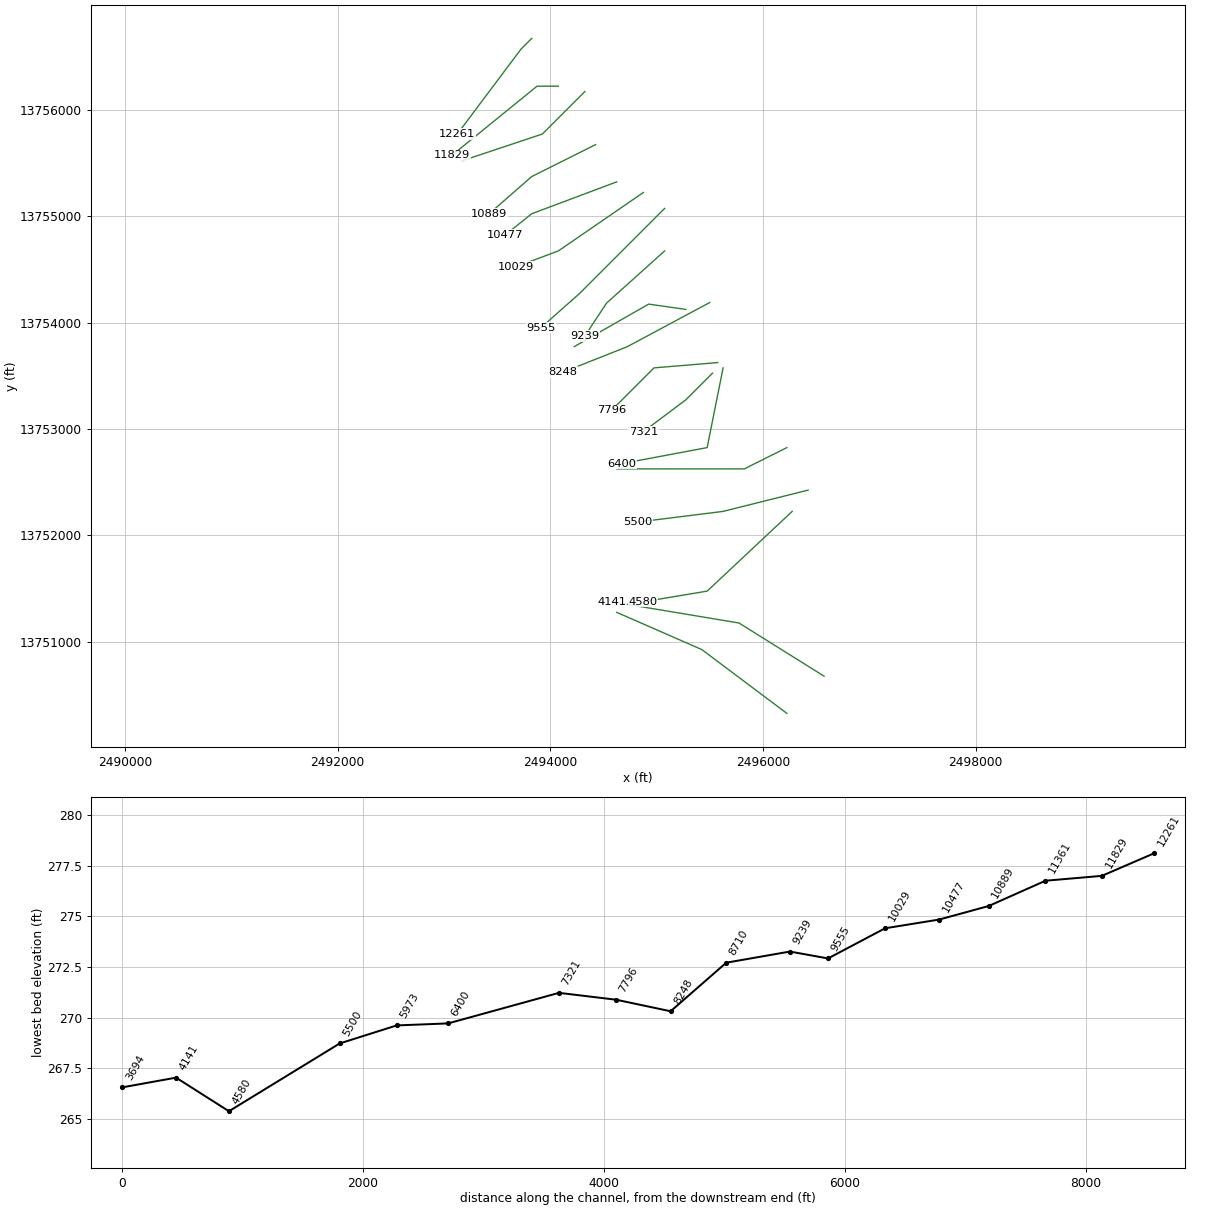
HEC-RAS study CLEAR FORK CREEK.prj: CLEAR FORK CREEK Base Level Engineering

--- CLEAR FORK CREEK.g01 (geometry) --- (continued)

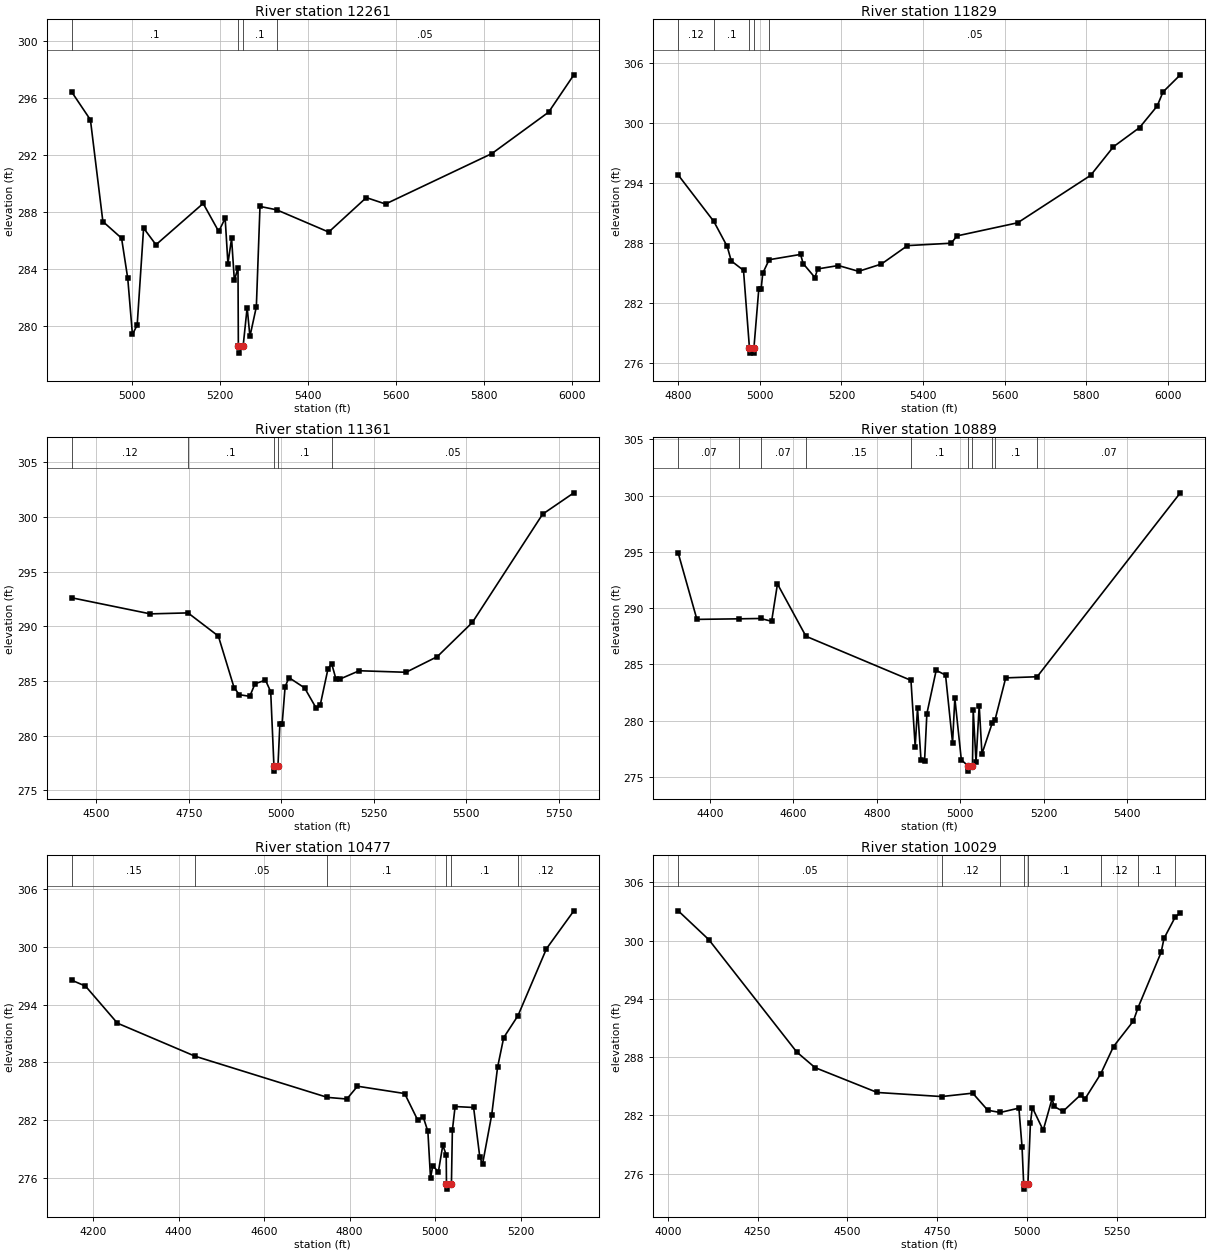
Type RM Length L Ch R = 1 ,12261   ,432,432,432
BEGIN DESCRIPTION:
CLEAR FORK CREEK 18.0
END DESCRIPTION:
XS GIS Cut Line= 3
      2493825.01     13756675.01        2493725.       13756575.
      2493125.02     13755775.03
#Sta/Elev= 30
  4863.7  296.44  4906.1  294.49  4934.4  287.35  4976.9  286.18    4991  283.35
  5001.6  279.42  5012.4  280.08    5027  286.89  5055.1  285.72  5162.4  288.62
  5197.8  286.65  5212.4  287.58  5218.7   284.4    5227  286.16  5233.3  283.23
  5241.6  284.09  5242.4  278.61  5242.9  278.11  5253.3  278.61  5262.4  281.31
  5268.7  279.28  5283.3  281.36  5291.6  288.41  5329.7  288.17  5447.8  286.61
  5533.3  289.03    5577  288.58  5818.7  292.12  5947.8  295.03  6005.1  297.65
#Mann= 4 ,-1 , 0
  4863.7      .1       0  5242.4     .05       0  5253.3      .1       0
  5329.7     .05       0
Bank Sta=5242.4,5253.3
XS Rating Curve= 0 ,0
Exp/Cntr=0.3,0.1

Type RM Length L Ch R = 1 ,11829   ,468,468,468
BEGIN DESCRIPTION:
CLEAR FORK CREEK 17.0
END DESCRIPTION:
XS GIS Cut Line= 3
      2494075.02       13756225.        2493875.       13756225.
        2493075.       13755575.
#Sta/Elev= 30
    4800  294.79  4887.3  290.15    4920  287.66    4930  286.21    4960  285.27
  4974.6   277.5  4975.1     277    4985     277  4985.5   277.5  4997.5  283.41
  5003.2  283.41  5007.2  284.98  5022.8  286.33  5099.9  286.86  5106.3  285.94
  5135.1  284.55  5141.8  285.41  5192.6  285.75  5242.1  285.17  5298.1   285.9
    5362  287.74  5469.1  287.98  5483.4  288.71  5632.1  290.02    5811  294.76
    5867  297.62  5930.9  299.53  5974.1  301.68  5988.4  303.09  6030.8   304.8
#Mann= 5 ,-1 , 0
    4800     .12       0  4887.3      .1       0  4974.6     .05       0
  4985.5      .1       0  5022.8     .05       0
Bank Sta=4974.6,4985.5
XS Rating Curve= 0 ,0
Exp/Cntr=0.3,0.1

Type RM Length L Ch R = 1 ,11361   ,472,472,472
BEGIN DESCRIPTION:
CLEAR FORK CREEK 16.0
END DESCRIPTION:
XS GIS Cut Line= 3
      2494325.02     13756175.02        2493925.       13755775.
      2493174.98     13755524.99
#Sta/Elev= 30
  4433.9  292.61  4646.1  291.14  4747.9  291.23  4829.9  289.11  4872.3   284.4
  4886.5  283.75  4914.8   283.6  4928.9  284.75  4957.2  285.08  4971.3  284.02
    4980  277.26  4980.5  276.76  4990.9  277.26  4996.1  281.07  5002.2  281.07
  5010.2  284.48  5020.7  285.31  5062.9  284.37  5094.5   282.5    5105  282.79
  5126.1  286.12  5135.9  286.59  5147.2  285.23  5157.7  285.17  5210.4  285.94
  5336.9   285.8  5421.3  287.23  5516.1  290.36  5705.9  300.26  5790.2  302.21
#Mann= 5 ,-1 , 0
  4433.9     .12       0  4747.9      .1       0    4980     .05       0
  4990.9      .1       0  5135.9     .05       0
Bank Sta=4980,4990.9
XS Rating Curve= 0 ,0
Exp/Cntr=0.3,0.1

Type RM Length L Ch R = 1 ,10889   ,412,412,412
BEGIN DESCRIPTION:
CLEAR FORK CREEK 15.0
END DESCRIPTION:
XS GIS Cut Line= 3
      2494425.01       13755675.        2493825.       13755375.
      2493425.03     13755025.02
#Sta/Elev= 30
  4324.6  294.89  4369.3     289  4470.8  289.05  4521.9  289.08  4548.2  288.83
  4562.2  292.15  4630.4   287.5  4881.9  283.58    4892  277.69  4897.6  281.11
    4906  276.48  4914.4  276.37    4920  280.62  4942.3  284.47  4964.7  284.05
  4981.5  278.03    4987  281.99  5002.5  276.51  5017.6  276.01  5018.1  275.51
  5029.2  276.01    5031  280.94  5037.7  276.33  5045.3  281.33  5051.9  277.05
  5076.8  279.82  5083.2  280.07  5108.8   283.8    5184   283.9  5526.9  300.25
#Mann= 10 ,-1 , 0
  4324.6     .07       0  4470.8      .1       0  4521.9     .07       0
  4630.4     .15       0  4881.9      .1       0  5017.6     .05       0
  5029.2      .1       0  5076.8     .07       0  5083.2      .1       0
    5184     .07       0
Bank Sta=5017.6,5029.2
XS Rating Curve= 0 ,0
Exp/Cntr=0.3,0.1

Type RM Length L Ch R = 1 ,10477   ,448,448,448
BEGIN DESCRIPTION:
CLEAR FORK CREEK 14.0
END DESCRIPTION:
XS GIS Cut Line= 3
      2494625.01       13755325.        2493825.       13755025.
      2493574.97     13754824.98
#Sta/Elev= 30
  4149.9  296.54    4182  295.93  4256.7  292.08  4438.8  288.64    4748  284.37
  4793.4   284.2  4818.3  285.53  4928.7  284.77  4958.9  282.04  4972.3  282.31
    4983  280.84  4989.2  275.99  4994.5  277.29  5007.5  276.62  5017.9   279.4
  5025.9   278.4  5026.5  275.34    5027  274.84  5038.1  275.34  5040.3  280.95
  5046.7  283.42    5090  283.32  5104.4   278.2  5110.8  277.42  5132.4  282.57
    5146  287.48  5160.4  290.58  5193.8  292.86  5260.4  299.81  5324.5  303.75
#Mann= 6 ,-1 , 0
  4149.9     .15       0  4438.8     .05       0    4748      .1       0
  5026.5     .05       0  5038.1      .1       0  5193.8     .12       0
Bank Sta=5026.5,5038.1
XS Rating Curve= 0 ,0
Exp/Cntr=0.3,0.1

Type RM Length L Ch R = 1 ,10029   ,474,474,474
BEGIN DESCRIPTION:
CLEAR FORK CREEK 13.0
END DESCRIPTION:
XS GIS Cut Line= 3
      2494874.97     13755224.98        2494075.       13754675.
      2493674.99       13754525.
#Sta/Elev= 30
  4029.2  303.06  4114.4  300.09  4359.3  288.52  4410.1  286.92  4583.3  284.36
  4762.7  283.94  4849.1  284.29  4891.1  282.53  4925.7   282.3  4977.7  282.75
  4986.5  278.76  4991.1  274.91  4991.6  274.41  5002.8  274.91  5009.8  281.17
  5015.1  282.81  5045.4  280.47  5070.3  283.74  5075.6  282.92  5100.6  282.42
  5149.5  284.11  5161.1  283.66  5205.5  286.27  5241.2  289.09  5296.4  291.71
  5309.6   293.1  5373.8  298.79  5381.8  300.22  5413.6  302.46  5427.2  302.82
#Mann= 8 ,-1 , 0
  4029.2     .05       0  4762.7     .12       0  4925.7      .1       0
  4991.1     .05       0  5002.8      .1       0  5205.5     .12       0
  5309.6      .1       0  5413.6     .07       0
Bank Sta=4991.1,5002.8
XS Rating Curve= 0 ,0
Exp/Cntr=0.3,0.1

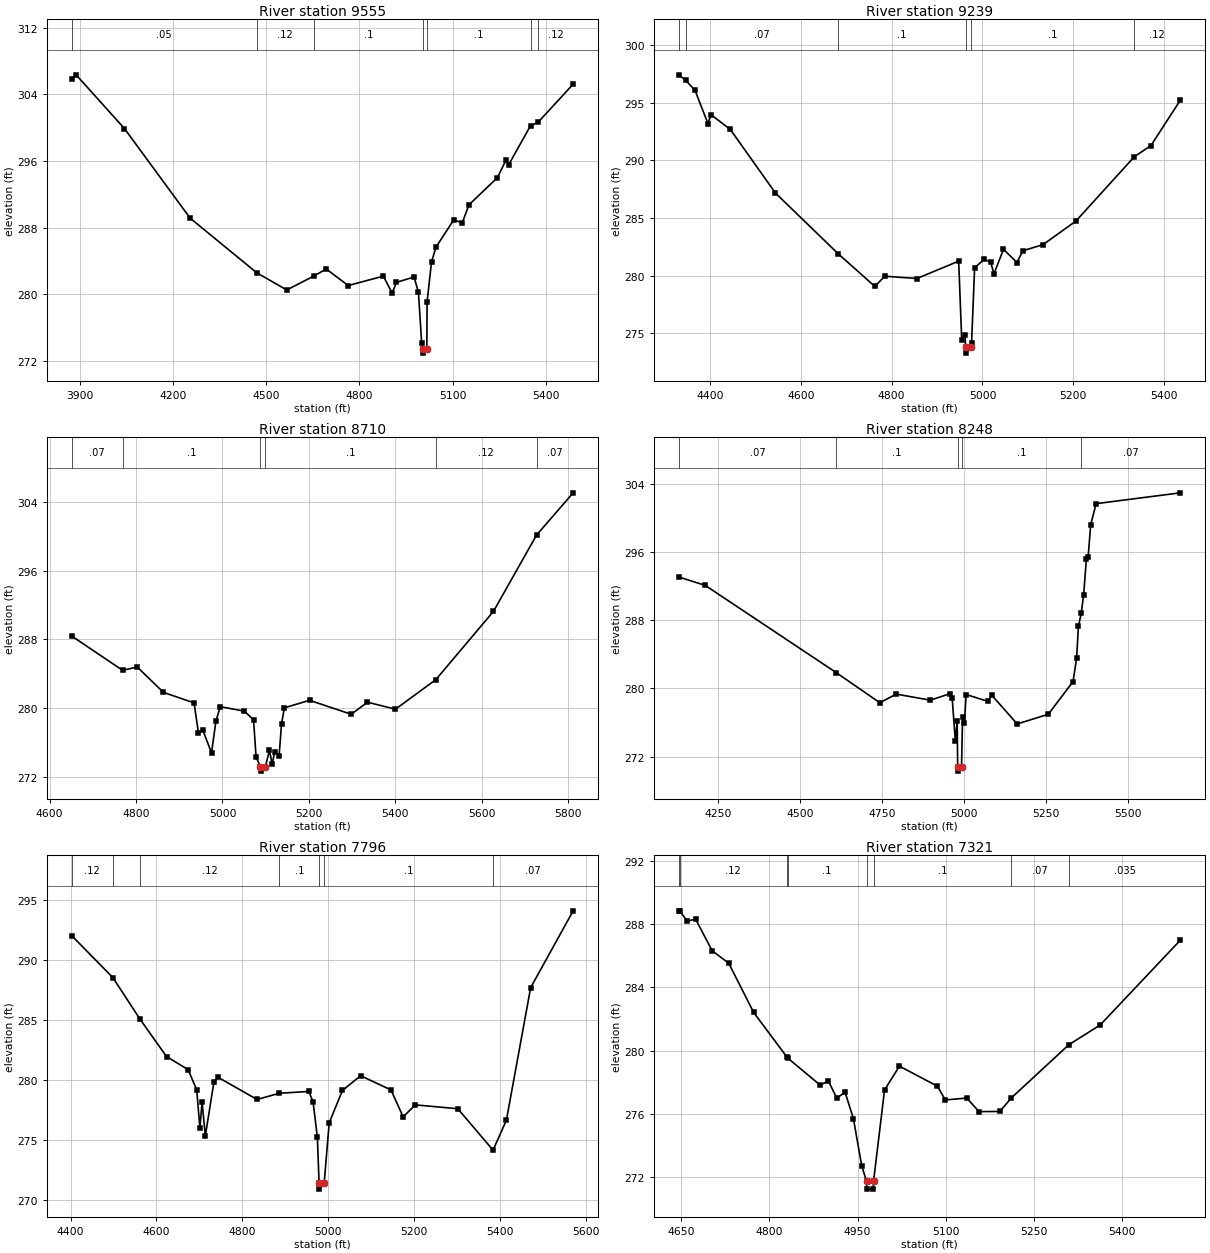
Type RM Length L Ch R = 1 ,9555    ,316,316,316
BEGIN DESCRIPTION:
CLEAR FORK CREEK 12.0
END DESCRIPTION:
XS GIS Cut Line= 3
      2495074.99     13755074.99        2494275.       13754275.
      2493912.37     13753953.63
#Sta/Elev= 30
  3872.9  305.81    3887  306.36  4042.6  299.91  4254.7  289.13    4469  282.58
  4565.8  280.51    4653  282.18  4693.1  283.03  4763.8  281.04    4877  282.17
  4905.3  280.15  4919.4  281.42    4976  282.07  4990.1  280.25  5000.7  274.09
  5005.5  273.42    5006  272.92  5017.2  273.42    5018  279.08  5032.3  283.86
  5046.5  285.64  5103.4   288.9  5131.8  288.61  5152.7  290.73  5244.8  294.01
  5273.1  296.18  5280.7  295.54  5351.4  300.25  5375.3  300.64  5488.8  305.24
#Mann= 7 ,-1 , 0
  3872.9     .05       0    4469     .12       0    4653      .1       0
  5005.5     .05       0  5017.2      .1       0  5351.4     .07       0
  5375.3     .12       0
Bank Sta=5005.5,5017.2
XS Rating Curve= 0 ,0
Exp/Cntr=0.3,0.1

Type RM Length L Ch R = 1 ,9239    ,529,529,529
BEGIN DESCRIPTION:
CLEAR FORK CREEK 11.0
END DESCRIPTION:
XS GIS Cut Line= 3
      2495074.99     13754674.99      2494528.53     13754184.01
      2494325.03     13753875.04
#Sta/Elev= 30
  4331.3  297.43  4346.1  296.96  4366.8  296.08  4395.2   293.2  4401.9  293.97
  4444.5  292.69    4544  287.16  4681.9   281.9    4763  279.05  4784.6  279.94
  4855.6  279.74  4947.6  281.25  4954.3  274.39  4961.8   274.8  4962.7  273.76
  4963.2  273.26  4974.4  273.76    4976  274.16  4982.7  280.67  5003.6   281.4
  5017.9  281.18  5025.3  280.15  5046.3  282.27  5076.1  281.13  5088.7  282.15
  5133.3  282.68  5205.6  284.72  5334.4  290.31  5371.2  291.29  5435.9  295.23
#Mann= 6 ,-1 , 0
  4331.3     .05       0  4346.1     .07       0  4681.9      .1       0
  4962.7     .05       0  4974.4      .1       0  5334.4     .12       0
Bank Sta=4962.7,4974.4
XS Rating Curve= 0 ,0
Exp/Cntr=0.3,0.1

Type RM Length L Ch R = 1 ,8710    ,462,462,462
BEGIN DESCRIPTION:
CLEAR FORK CREEK 10.0
END DESCRIPTION:
XS GIS Cut Line= 3
      2495275.03       13754125.        2494925.       13754175.
      2494225.01     13753775.01
#Sta/Elev= 30
  4651.4  288.39  4768.9  284.42    4803  284.79  4863.6  281.85  4934.3  280.63
  4944.4  277.17  4954.5  277.48  4974.7  274.83  4984.8  278.48  4994.9  280.19
  5050.3  279.68  5071.9  278.68  5077.7   274.4  5087.6  273.21  5088.1  272.71
  5099.4  273.21  5108.6  275.12  5115.1  273.52  5120.9  274.98    5131   274.5
  5136.7  278.19  5143.2  280.06  5201.5  280.93    5298  279.31  5335.4  280.71
  5400.2   279.9  5493.5  283.33  5626.9  291.26  5726.4  300.11  5811.2  305.02
#Mann= 6 ,-1 , 0
  4651.4     .07       0  4768.9      .1       0  5087.6     .05       0
  5099.4      .1       0  5493.5     .12       0  5726.4     .07       0
Bank Sta=5087.6,5099.4
XS Rating Curve= 0 ,0
Exp/Cntr=0.3,0.1

Type RM Length L Ch R = 1 ,8248    ,452,452,452
BEGIN DESCRIPTION:
CLEAR FORK CREEK 9.0
END DESCRIPTION:
XS GIS Cut Line= 3
      2495498.37     13754189.39        2494725.       13753775.
       2494121.3     13753535.68
#Sta/Elev= 30
  4132.1  293.07  4212.6  292.08  4611.5  281.85  4743.9  278.33  4793.9  279.34
  4897.4  278.63  4956.6  279.38  4964.1   278.9  4973.8  273.84  4979.4  276.17
  4980.9  270.81  4981.4  270.31  4992.7  270.81  4995.7  276.63  5001.4     276
  5006.7  279.29    5073  278.49  5084.8  279.21  5162.1  275.84  5256.9  276.98
  5332.2  280.81    5343  283.54  5348.5  287.28    5357   288.8  5364.5  291.01
  5372.8  295.17  5378.2  295.45    5386  299.22  5402.5  301.67  5658.9  302.94
#Mann= 5 ,-1 , 0
  4132.1     .07       0  4611.5      .1       0  4980.9     .05       0
  4992.7      .1       0    5357     .07       0
Bank Sta=4980.9,4992.7
XS Rating Curve= 0 ,0
Exp/Cntr=0.3,0.1

Type RM Length L Ch R = 1 ,7796    ,475,475,475
BEGIN DESCRIPTION:
CLEAR FORK CREEK 8.0
END DESCRIPTION:
XS GIS Cut Line= 3
      2495574.98       13753625.        2494975.       13753575.
      2494575.03     13753175.03
#Sta/Elev= 30
  4402.7     292  4498.6   288.5  4561.9  285.03  4623.4  281.93  4673.6  280.84
  4693.7  279.16  4701.2  275.97  4706.2  278.13  4713.8  275.32  4733.8   279.8
  4743.9  280.19  4834.2  278.35  4886.4  278.87  4954.6  279.02  4964.6  278.18
  4974.7  275.21  4978.7  271.38  4979.2  270.88  4990.6  271.38  5002.2  276.39
    5033   279.1  5075.5  280.33  5146.2  279.14  5174.5   276.9  5202.7   277.9
  5301.7  277.58  5383.8  274.13  5414.9  276.62  5471.4  287.67  5570.4  294.07
#Mann= 7 ,-1 , 0
  4402.7     .12       0  4498.6     .07       0  4561.9     .12       0
  4886.4      .1       0  4978.7     .05       0  4990.6      .1       0
  5383.8     .07       0
Bank Sta=4978.7,4990.6
XS Rating Curve= 0 ,0
Exp/Cntr=0.3,0.1

Type RM Length L Ch R = 1 ,7321    ,921,921,921
BEGIN DESCRIPTION:
CLEAR FORK CREEK 7.0
END DESCRIPTION:
XS GIS Cut Line= 3
      2495524.99     13753524.99        2495275.       13753275.
      2494875.03     13752975.03
#Sta/Elev= 30
  4645.9  288.85  4647.3  288.85    4660  288.19  4674.2  288.33  4702.5  286.32
  4730.7  285.53  4773.2  282.41  4829.7  279.59  4830.9  279.53  4886.3  277.81
  4900.4  278.07  4914.6  276.98  4928.7  277.36  4942.9  275.69    4957  272.71
  4965.2  271.72  4965.7  271.22  4976.7  271.22  4977.2  271.72  4995.9   277.5
  5021.3  279.01  5085.9  277.74  5099.4  276.87  5135.9  276.99  5156.7  276.13
  5192.2  276.14  5211.5  276.99  5309.4  280.36    5363  281.62  5499.4  286.99
#Mann= 8 ,-1 , 0
  4645.9     .07       0  4647.3     .12       0  4829.7     .07       0
  4830.9      .1       0  4965.2     .05       0  4977.2      .1       0
  5211.5     .07       0  5309.4    .035       0
Bank Sta=4965.2,4977.2
XS Rating Curve= 0 ,0
Exp/Cntr=0.3,0.1

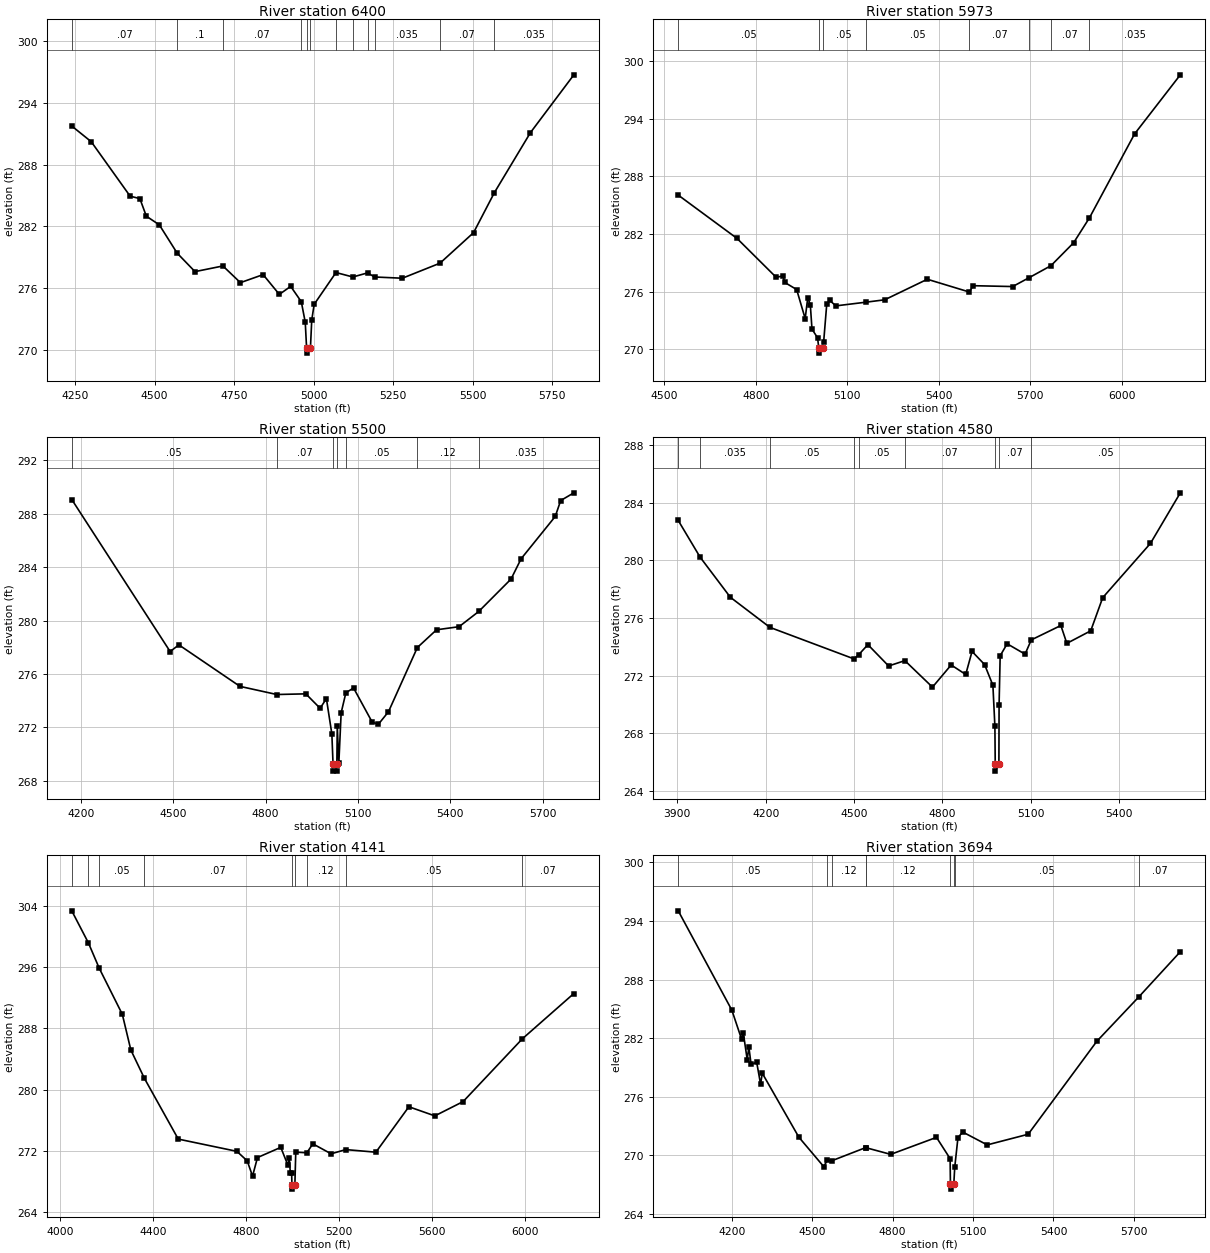
Type RM Length L Ch R = 1 ,6400    ,427,427,427
BEGIN DESCRIPTION:
CLEAR FORK CREEK 6.0
END DESCRIPTION:
XS GIS Cut Line= 3
        2495625.     13753574.99        2495475.       13752825.
      2494674.98       13752675.
#Sta/Elev= 30
  4239.4  291.75  4300.6  290.23    4423  284.94  4453.5  284.71  4473.9     283
  4514.7  282.16  4570.9  279.41  4626.9  277.62  4714.7  278.17  4769.7  276.55
  4841.1  277.33  4892.1  275.41  4927.8  276.19  4961.2   274.7  4973.6   272.7
  4977.8  270.21  4978.3  269.71  4989.9  270.21    4994  272.92  5001.7  274.45
  5070.2  277.53  5123.3   277.1  5169.8   277.5  5191.4   277.1  5278.9  276.98
  5397.3  278.44  5502.8   281.4  5568.4  285.29  5681.7  291.11  5818.2  296.72
#Mann= 12 ,-1 , 0
  4239.4     .07       0  4570.9      .1       0  4714.7     .07       0
  4961.2    .035       0  4977.8    .035       0  4989.9    .035       0
  5070.2     .07       0  5123.3    .035       0  5169.8     .07       0
  5191.4    .035       0  5397.3     .07       0  5568.4    .035       0
Bank Sta=4977.8,4989.9
XS Rating Curve= 0 ,0
Exp/Cntr=0.3,0.1

Type RM Length L Ch R = 1 ,5973    ,473,473,473
BEGIN DESCRIPTION:
CLEAR FORK CREEK 5.0
END DESCRIPTION:
XS GIS Cut Line= 3
      2496225.01     13752825.01        2495825.       13752625.
      2494625.03       13752625.
#Sta/Elev= 30
  4545.7  286.06  4738.6  281.55  4867.1   277.5  4889.5  277.65  4895.1  276.97
  4934.2  276.23  4962.2   273.2  4970.6  275.39    4979  274.65  4984.5  272.11
  5002.9   271.2  5006.8  270.11  5007.3  269.61  5019.1  270.11  5022.9  270.82
  5032.9   274.7  5042.9  275.09  5062.9  274.53  5160.9  274.91  5222.9  275.16
  5362.9   277.3  5500.9  275.97  5512.9  276.63  5642.9  276.54  5697.8  277.48
  5768.4  278.71  5842.9   281.1  5894.7  283.69  6042.9  292.43  6192.9  298.58
#Mann= 8 ,-1 , 0
  4545.7     .05       0  5006.8     .05       0  5019.1     .05       0
  5160.9     .05       0  5500.9     .07       0  5697.8    .035       0
  5768.4     .07       0  5894.7    .035       0
Bank Sta=5006.8,5019.1
XS Rating Curve= 0 ,0
Exp/Cntr=0.3,0.1

Type RM Length L Ch R = 1 ,5500    ,920,920,920
BEGIN DESCRIPTION:
CLEAR FORK CREEK 4.0
END DESCRIPTION:
XS GIS Cut Line= 3
      2496424.99       13752425.        2495625.       13752225.
      2494825.04     13752125.01
#Sta/Elev= 30
  4170.3  289.07  4489.8  277.68  4518.2  278.18  4716.6  275.07  4836.2  274.46
  4930.5  274.51  4976.9  273.43  4997.4  274.15  5015.1   271.5    5019  269.22
  5019.5  268.72  5030.8  268.72  5031.3  269.22  5032.7  272.09  5037.7   269.3
  5045.3  273.09  5060.6  274.59  5085.6  274.95  5146.1  272.39  5166.2  272.23
    5199  273.17  5292.8  277.98  5355.2  279.31  5428.3  279.54  5492.1  280.68
  5597.1  283.11  5629.8  284.63  5740.7   287.8  5758.3  288.99  5801.1  289.57
#Mann= 7 ,-1 , 0
  4170.3     .05       0  4836.2     .07       0    5019     .05       0
  5031.3     .07       0  5060.6     .05       0  5292.8     .12       0
  5492.1    .035       0
Bank Sta=5019,5031.3
XS Rating Curve= 0 ,0
Exp/Cntr=0.3,0.1

Type RM Length L Ch R = 1 ,4580    ,439,439,439
BEGIN DESCRIPTION:
CLEAR FORK CREEK 3.0
END DESCRIPTION:
XS GIS Cut Line= 3
        2496275.       13752225.        2495475.       13751475.
      2494874.96     13751374.99
#Sta/Elev= 30
  3903.1  282.77  3977.5  280.22  4080.1  277.44  4214.4  275.35  4500.1  273.16
  4515.3  273.44  4547.1  274.15  4617.5  272.67  4672.7  273.04  4766.4   271.2
  4829.9  272.74  4879.3  272.08  4900.8  273.68  4943.3  272.77  4971.6  271.33
  4978.4  268.47  4979.5  265.87    4980  265.37    4992  265.87  4992.6  269.98
  4996.3  273.38    5020  274.21  5080.8  273.49  5101.9  274.48  5202.4  275.48
  5222.7  274.24  5303.8  275.11  5344.4  277.41  5506.6  281.18    5608  284.69
#Mann= 9 ,-1 , 0
  3903.1     .05       0  3977.5    .035       0  4214.4     .05       0
  4500.1     .07       0  4515.3     .05       0  4672.7     .07       0
  4979.5     .05       0    4992     .07       0  5101.9     .05       0
Bank Sta=4979.5,4992
XS Rating Curve= 0 ,0
Exp/Cntr=0.3,0.1

Type RM Length L Ch R = 1 ,4141    ,447,447,447
BEGIN DESCRIPTION:
CLEAR FORK CREEK 2.0
END DESCRIPTION:
XS GIS Cut Line= 3
      2496574.96     13750675.03        2495775.       13751175.
        2494575.       13751375.
#Sta/Elev= 30
  4049.1  303.35  4120.6  299.17  4166.9  295.88  4266.6  289.84  4303.2  285.19
  4361.9  281.47  4507.2  273.56  4759.5  271.96  4803.8  270.72  4826.8  268.73
    4848  271.15  4948.2  272.48  4978.9  270.15  4984.8  271.07  4989.5  269.11
    4995  269.11  4996.3  267.53  4996.8  267.03  5008.8  267.53  5012.7  271.86
  5060.2  271.77  5086.2  272.94  5164.8  271.64  5227.8  272.19  5357.4  271.85
  5499.3  277.78  5610.9  276.59  5732.5  278.45  5987.2  286.64    6209  292.56
#Mann= 9 ,-1 , 0
  4049.1     .05       0  4120.6     .07       0  4166.9     .05       0
  4361.9     .07       0  4996.3     .05       0  5008.8     .07       0
  5060.2     .12       0  5227.8     .05       0  5987.2     .07       0
Bank Sta=4996.3,5008.8
XS Rating Curve= 0 ,0
Exp/Cntr=0.3,0.1

Type RM Length L Ch R = 1 ,3694    ,942,942,942
BEGIN DESCRIPTION:
CLEAR FORK CREEK 1.0
END DESCRIPTION:
XS GIS Cut Line= 3
      2496224.99     13750325.01        2495425.       13750925.
        2494625.       13751275.
#Sta/Elev= 30
    4000  295.05    4200  284.88  4236.4   281.9  4242.7  282.55  4257.3  279.82
  4263.5   281.1  4271.9  279.32  4292.7  279.54  4307.3  277.29  4313.5  278.42
    4450  271.87  4542.7  268.86  4556.4  269.51  4573.4  269.46  4699.1   270.8
  4699.2   270.8  4792.7  270.11  4963.5  271.85  5014.4  269.67  5015.5  267.05
    5016  266.55  5028.1  267.05  5031.6  268.79  5043.6  271.82  5061.2   272.4
  5152.8  271.08  5305.6  272.17  5561.7  281.69  5718.5  286.24  5873.2  290.86
#Mann= 9 ,-1 , 0
    4000     .05       0  4556.4     .07       0  4573.4     .12       0
  4699.1     .07       0  4699.2     .12       0  5015.5     .05       0
  5028.1     .12       0  5031.6     .05       0  5718.5     .07       0
Bank Sta=5015.5,5028.1
XS Rating Curve= 0 ,0
Exp/Cntr=0.3,0.1