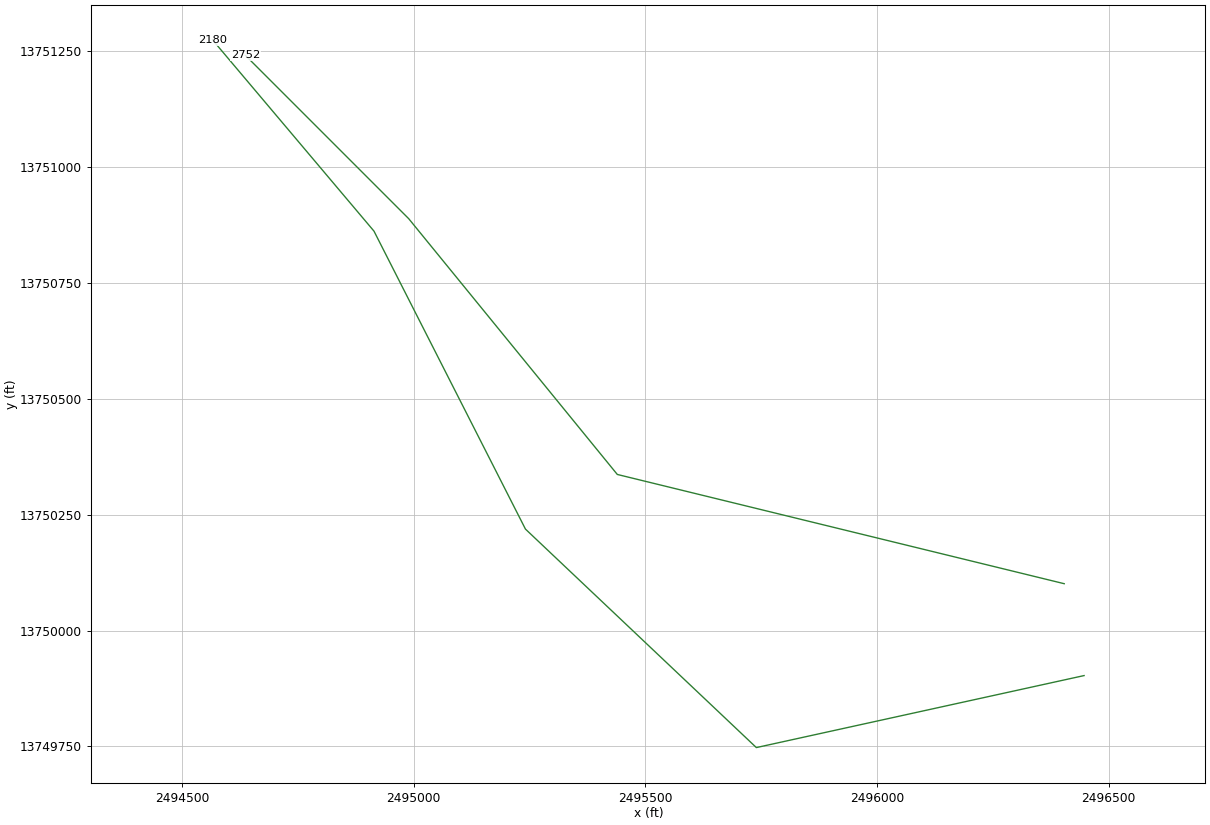
HEC-RAS study CLEAR FORK CREEK.prj: CLEAR FORK CREEK Base Level Engineering

--- CLEAR FORK CREEK.g01 (geometry) --- (continued)

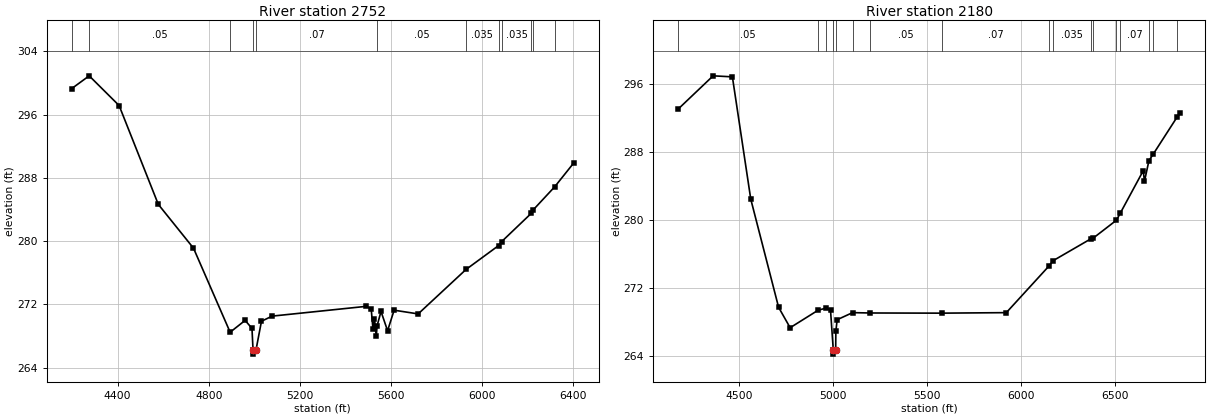
Type RM Length L Ch R = 1 ,2752    ,572,572,572
BEGIN DESCRIPTION:
X18477
END DESCRIPTION:
XS GIS Cut Line= 4
      2496403.84     13750101.21      2495439.39     13750336.97
      2494989.31     13750888.84      2494636.95      13751241.2
#Sta/Elev= 30
    4199  299.31  4275.4  300.92  4406.7  297.16  4578.7  284.65  4733.1  279.11
  4893.9  268.47  4959.6  269.97  4989.7  268.96  4994.4   266.2  4994.9   265.7
  5007.2   266.2  5031.3  269.86  5078.1  270.51    5492  271.75  5512.9  271.41
  5520.8  268.82  5527.2  270.15  5535.1  267.96  5538.8   269.3  5555.9   271.1
  5584.7  268.66  5613.4  271.26  5718.9  270.79  5928.7  276.41    6072  279.44
  6085.3  279.94  6215.3  283.52  6223.9  283.96  6318.1  286.88  6402.3  289.92
#Mann= 12 ,-1 , 0
    4199    .035       0  4275.4     .05       0  4893.9     .07       0
  4994.4     .05       0  5007.2     .07       0  5538.8     .05       0
  5928.7    .035       0    6072     .07       0  6085.3    .035       0
  6215.3     .07       0  6223.9    .035       0  6318.1     .07       0
Bank Sta=4994.4,5007.2
XS Rating Curve= 0 ,0
Exp/Cntr=0.3,0.1

Type RM Length L Ch R = 1 ,2180    ,0,0,0
BEGIN DESCRIPTION:
X18476
END DESCRIPTION:
XS GIS Cut Line= 5
      2496446.71     13749902.97      2495739.43     13749747.59
      2495241.14     13750219.09       2494914.3     13750862.05
      2494566.05     13751274.59
#Sta/Elev= 30
  4175.7  293.01  4361.7  296.91  4464.1  296.79  4561.9  282.43  4709.9  269.74
  4771.3  267.34  4920.5   269.4  4964.3  269.65  4986.2  269.39  5000.8  264.74
  5001.3  264.24  5013.6  264.74  5014.5  266.91  5021.4  268.28  5103.5  269.11
  5198.6  269.07  5577.7  269.05  5921.4  269.11  6148.6  274.59  6169.7   275.2
  6370.7  277.77  6381.4  277.82  6507.2  279.96  6528.7  280.83  6649.8  285.77
  6656.3  284.53  6680.1  286.95  6704.2  287.76  6828.8  292.03    6847  292.56
#Mann= 17 ,-1 , 0
  4175.7     .05       0  4920.5     .07       0  4964.3     .05       0
  5000.8     .05       0  5013.6     .05       0  5103.5     .07       0
  5198.6     .05       0  5577.7     .07       0  6148.6     .05       0
  6169.7    .035       0  6370.7     .12       0  6381.4     .07       0
  6507.2    .035       0  6528.7     .07       0  6680.1    .035       0
  6704.2     .07       0  6828.8    .035       0
Bank Sta=5000.8,5013.6
XS Rating Curve= 0 ,0
Exp/Cntr=0.3,0.1

Chan Stop Cuts=-1
Use User Specified Reach Order=0
Composite Channel Slope=5