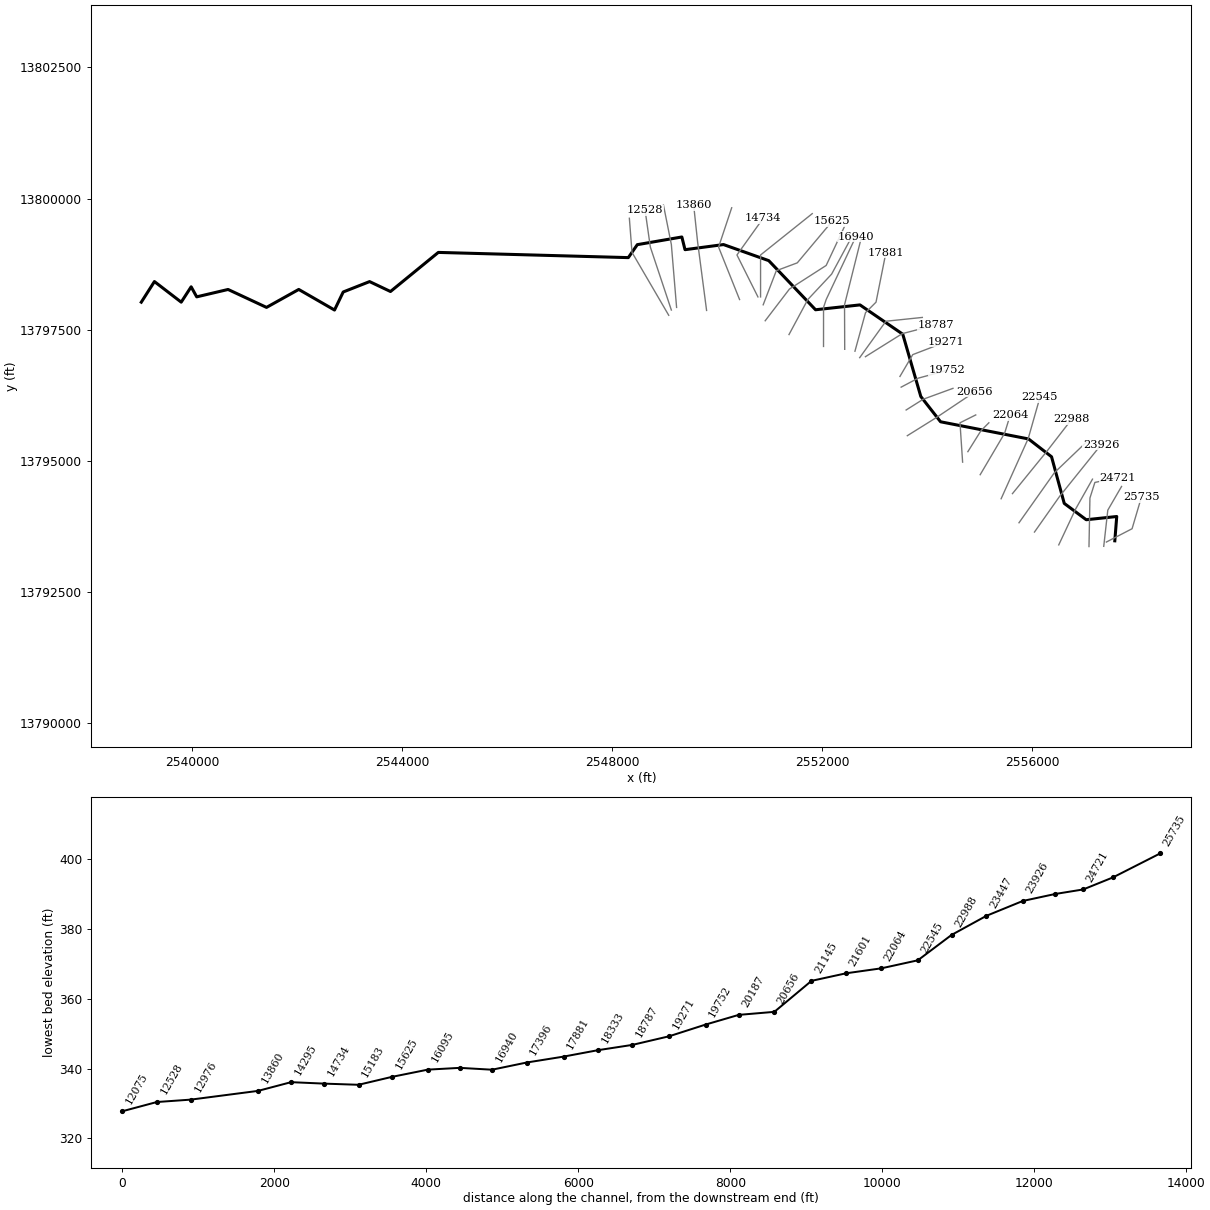
--- Cedar Creek.prj (project) ---

Proj Title=Cedar Creek Base Level Engineering
Current Plan=p01
Default Exp/Contr=0.3,0.1
English Units
Geom File=g01
Flow File=f01
Plan File=p01
Y Axis Title=Elevation
X Axis Title(PF)=Main Channel Distance
X Axis Title(XS)=Station
BEGIN DESCRIPTION:
Cedar Creek
END DESCRIPTION:
DSS Export Rating Curves= 0
DSS Export Rating Curve Sorted= 0
DSS Export Volume Flow Curves= 0
DXF OffsetX= 0
DXF OffsetY= 0
DXF ScaleX= 1
DXF ScaleY= 10

--- Cedar Creek.p01 (plan) ---

Plan Title=Multiple Run
Short Identifier=Multiple
Geom File=g01
Flow File=f01
Subcritical Flow
K Sum by GR= 0
Std Step Tol= 0.01
Critical Tol= 0.01
Num of Std Step Trials= 20
Max Error Tol= 0.3
Flow Tol Ratio= 0.001
Split Flow NTrial= 30
Split Flow Tol= 0.02
Split Flow Ratio= 0.02
Log Output Level= 0
Friction Slope Method= 1
Unsteady Friction Slope Method= 2
Unsteady Bridges Friction Slope Method= 1
Parabolic Critical Depth
Global Vel Dist=  1 , 1 , 1
Global Log Level= 0
CheckData=True
Encroach Param= -1, 0, 0, 0
BEGIN DESCRIPTION:
Multiple Run
END DESCRIPTION:

--- Cedar Creek.f01 (steady flow) ---

Flow Title=Multiple
Number of Profiles=7
Profile Names=10-year,25-year,50-year,1pct_min,100-year,1pct_plu,500-year
River Rch & RM= Cedar Creek,Reach-1,25735
     928    1523    2070    1363    2720    5427    4645
River Rch & RM= Cedar Creek,Reach-1,22064
    1158    1921    2631    1744    3480    6943    6023
River Rch & RM= Cedar Creek,Reach-1,17881
    1933    3271    4538    3040    6065   12102   10732
River Rch & RM= Cedar Creek,Reach-1,8271
    2899    4981    6984    4721    9420   18796   16976
River Rch & RM= Cedar Creek,Reach-1,4566
    2855    4887    6834    4607    9192   18340   16470
Boundary for River Rch & Prof#=Cedar Creek,Reach-1,1
Up Type=0
Dn Type=3
Dn Slope=0.005
Boundary for River Rch & Prof#=Cedar Creek,Reach-1,2
Up Type=0
Dn Type=3
Dn Slope=0.005
Boundary for River Rch & Prof#=Cedar Creek,Reach-1,3
Up Type=0
Dn Type=3
Dn Slope=0.005
Boundary for River Rch & Prof#=Cedar Creek,Reach-1,4
Up Type=0
Dn Type=3
Dn Slope=0.005
Boundary for River Rch & Prof#=Cedar Creek,Reach-1,5
Up Type=0
Dn Type=3
Dn Slope=0.005
Boundary for River Rch & Prof#=Cedar Creek,Reach-1,6
Up Type=0
Dn Type=3
Dn Slope=0.005
Boundary for River Rch & Prof#=Cedar Creek,Reach-1,7
Up Type=0
Dn Type=3
Dn Slope=0.005

--- Cedar Creek.g01 (geometry) ---

Geom Title=Existing Conditions

River Reach=Cedar Creek,Reach-1
Reach XY= 30
      2557575.00     13793475.00      2557611.61     13793938.33
      2557030.30     13793877.00      2556611.67     13794188.39
      2556369.55     13795077.47      2555931.17     13795417.14
      2554254.80     13795744.59      2553878.61     13796226.48
      2553534.68     13797414.22      2552719.33     13797973.02
      2551872.56     13797880.39      2550981.05     13798816.84
      2550118.97     13799123.38      2549385.30     13799025.86
      2549325.28     13799268.01      2548476.46     13799121.48
      2548304.98     13798874.55      2544684.59     13798973.81
      2543773.26     13798228.31      2543375.00     13798417.44
      2542872.41     13798219.29      2542706.78     13797875.07
      2542025.09     13798267.71      2541411.08     13797925.41
      2540678.40     13798267.22      2540080.85     13798126.49
      2539975.00     13798318.13      2539785.69     13798025.54
      2539275.20     13798418.02      2539025.00     13798025.00

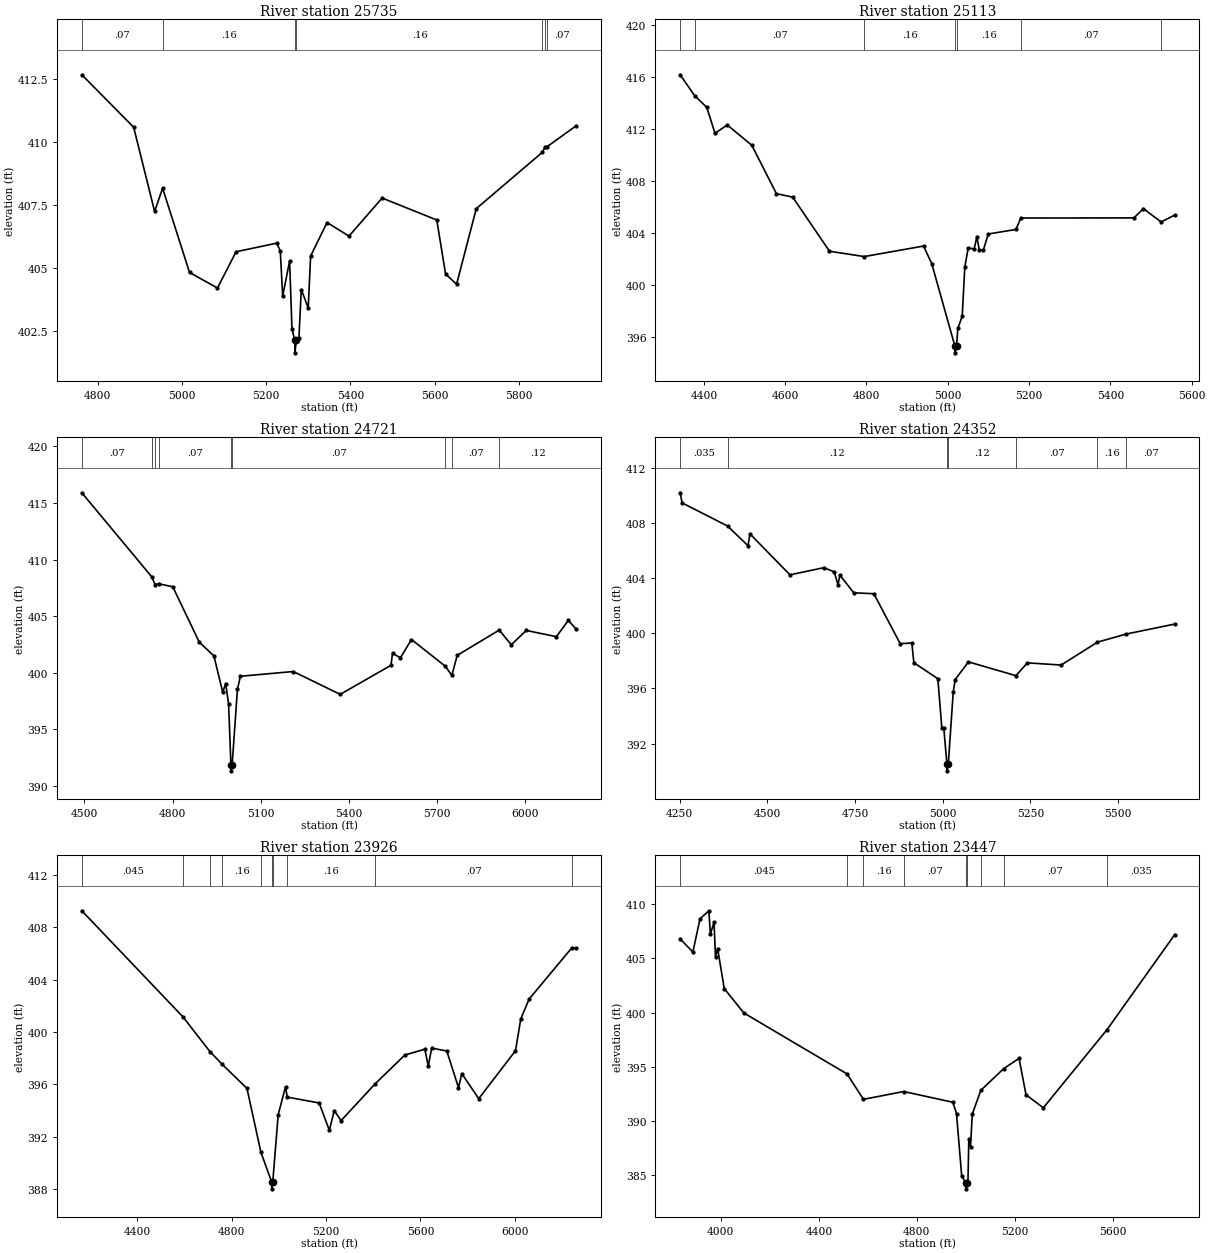
Type RM Length L Ch R = 1,25735,622,622,622
BEGIN DESCRIPTION:
Cedar Creek 45.0
END DESCRIPTION:
XS GIS Cut Line= 3
      2557414.15     13793451.60      2557904.08     13793705.63
      2558080.50     13794302.74
#Sta/Elev= 30
  4762.1  412.68  4885.2  410.60  4935.0  407.26  4954.0  408.18  5017.9  404.84
  5084.3  404.22  5128.5  405.66  5224.9  406.00  5233.5  405.70  5239.2  403.90
  5255.7  405.29  5261.3  402.60  5267.9  402.15  5268.2  401.65  5271.9  402.15
  5277.8  402.23  5283.4  404.16  5299.9  403.43  5305.6  405.49  5344.6  406.82
  5396.7  406.28  5475.5  407.79  5605.3  406.92  5626.1  404.78  5652.3  404.37
  5699.1  407.37  5856.4  409.61  5862.5  409.82  5867.5  409.83  5936.6  410.66
#Mann=7,-1,0
  4762.1    0.07       0  4954.0    0.16       0  5267.9    0.07       0
  5271.9    0.16       0  5856.4    0.07       0  5862.5    0.16       0
  5867.5    0.07       0
Bank Sta=5267.9,5271.9
Exp/Cntr=0.3,0.1

Type RM Length L Ch R = 1,25113,392,392,392
BEGIN DESCRIPTION:
Cedar Creek 44.0
END DESCRIPTION:
XS GIS Cut Line= 3
      2557364.23     13793369.96      2557441.35     13794059.48
      2557703.54     13794511.53
#Sta/Elev= 30
  4341.7  416.20  4377.4  414.58  4407.1  413.69  4427.3  411.69  4457.5  412.33
  4517.8  410.77  4578.4  407.04  4618.5  406.77  4709.0  402.60  4794.5  402.19
  4940.4  403.00  4960.6  401.64  5017.7  395.27  5017.9  394.77  5021.7  395.27
  5024.7  396.66  5035.5  397.58  5041.9  401.38  5050.2  402.84  5065.0  402.79
  5071.7  403.73  5077.5  402.67  5087.5  402.69  5099.7  403.93  5167.8  404.28
  5179.6  405.16  5458.1  405.17  5481.2  405.89  5524.7  404.86  5558.1  405.38
#Mann=7,-1,0
  4341.7    0.16       0  4377.4    0.07       0  4794.5    0.16       0
  5017.7    0.07       0  5021.7    0.16       0  5179.6    0.07       0
  5524.7    0.16       0
Bank Sta=5017.7,5021.7
Exp/Cntr=0.3,0.1

Type RM Length L Ch R = 1,24721,369,369,369
BEGIN DESCRIPTION:
Cedar Creek 43.0
END DESCRIPTION:
XS GIS Cut Line= 4
      2557082.96     13793365.35      2557101.10     13794290.85
      2557195.18     13794588.02      2557631.30     13794681.48
#Sta/Elev= 30
  4490.9  415.90  4729.3  408.46  4740.2  407.79  4752.2  407.86  4800.6  407.59
  4890.6  402.70  4940.6  401.48  4970.6  398.27  4980.6  399.04  4990.6  397.23
  4998.6  391.82  4998.9  391.32  5002.6  391.82  5020.7  398.52  5030.7  399.68
  5210.7  400.10  5370.7  398.08  5543.5  400.65  5548.7  401.70  5575.8  401.32
  5613.3  402.93  5728.7  400.56  5750.7  399.75  5769.0  401.53  5911.9  403.76
  5953.1  402.47  6004.2  403.73  6106.5  403.18  6147.4  404.62  6174.3  403.83
#Mann=9,-1,0
  4490.9    0.07       0  4729.3    0.12       0  4740.2     0.1       0
  4752.2    0.07       0  4998.6    0.05       0  5002.6    0.07       0
  5728.7   0.063       0  5750.7    0.07       0  5911.9    0.12       0
Bank Sta=4998.6,5002.6
Exp/Cntr=0.3,0.1

Type RM Length L Ch R = 1,24352,426,426,426
BEGIN DESCRIPTION:
Cedar Creek 42.0
END DESCRIPTION:
XS GIS Cut Line= 3
      2556506.80     13793397.13      2556825.00     13794075.00
      2557149.59     13794650.77
#Sta/Elev= 30
  4251.4  410.18  4256.7  409.45  4386.4  407.77  4444.8  406.34  4450.3  407.20
  4564.4  404.23  4661.2  404.75  4690.9  404.44  4701.3  403.50  4706.8  404.21
  4746.2  402.93  4803.6  402.86  4878.7  399.24  4911.9  399.29  4917.6  397.86
  4986.1  396.70  4997.5  393.10  5003.1  393.10  5011.9  390.52  5012.2  390.02
  5015.9  390.52  5029.9  395.73  5035.6  396.64  5073.2  397.92  5208.7  396.92
  5241.3  397.85  5337.6  397.69  5441.1  399.35  5523.5  399.94  5661.2  400.66
#Mann=7,-1,0
  4251.4   0.035       0  4386.4    0.12       0  5011.9    0.07       0
  5015.9    0.12       0  5208.7    0.07       0  5441.1    0.16       0
  5523.5    0.07       0
Bank Sta=5011.9,5015.9
Exp/Cntr=0.3,0.1

Type RM Length L Ch R = 1,23926,479,479,479
BEGIN DESCRIPTION:
Cedar Creek 41.0
END DESCRIPTION:
XS GIS Cut Line= 3
      2556044.05     13793642.08      2556525.00     13794325.00
      2557314.32     13795307.03
#Sta/Elev= 30
  4165.3  409.26  4595.1  401.13  4707.9  398.51  4759.6  397.54  4865.1  395.69
  4924.1  390.82  4970.3  388.52  4970.5  388.02  4974.3  388.52  4997.5  393.69
  5028.6  395.82  5035.6  395.03  5171.0  394.58  5214.2  392.49  5235.0  394.00
  5263.8  393.23  5408.0  396.04  5534.2  398.24  5619.0  398.69  5633.4  397.39
  5647.8  398.77  5711.8  398.55  5761.4  395.76  5775.8  396.81  5847.3  394.91
  6003.0  398.57  6025.3  400.99  6060.5  402.51  6242.7  406.45  6260.5  406.38
#Mann=10,-1,0
  4165.3   0.045       0  4595.1    0.16       0  4707.9    0.07       0
  4759.6    0.16       0  4924.1    0.12       0  4970.3    0.07       0
  4974.3    0.12       0  5035.6    0.16       0  5408.0    0.07       0
  6242.7    0.16       0
Bank Sta=4970.3,4974.3
Exp/Cntr=0.3,0.1

Type RM Length L Ch R = 1,23447,459,459,459
BEGIN DESCRIPTION:
Cedar Creek 40.0
END DESCRIPTION:
XS GIS Cut Line= 3
      2555749.19     13793819.02      2556425.00     13794775.00
      2557036.79     13795360.71
#Sta/Elev= 30
  3834.3  406.79  3886.1  405.59  3915.1  408.65  3951.3  409.39  3957.5  407.24
  3972.3  408.32  3978.4  405.14  3987.0  405.91  4014.1  402.22  4094.1  399.97
  4515.2  394.35  4582.1  392.01  4746.2  392.73  4947.2  391.74  4961.9  390.70
  4982.9  384.98  5000.0  384.26  5000.2  383.76  5004.0  384.26  5008.5  384.26
  5012.1  388.33  5019.0  387.66  5026.3  390.65  5061.2  392.84  5153.9  394.83
  5217.2  395.79  5245.5  392.43  5316.2  391.23  5575.7  398.42  5852.0  407.18
#Mann=9,-1,0
  3834.3   0.045       0  4515.2    0.07       0  4582.1    0.16       0
  4746.2    0.07       0  5000.0    0.07       0  5004.0    0.07       0
  5061.2    0.16       0  5153.9    0.07       0  5575.7   0.035       0
Bank Sta=5000,5004
Exp/Cntr=0.3,0.1

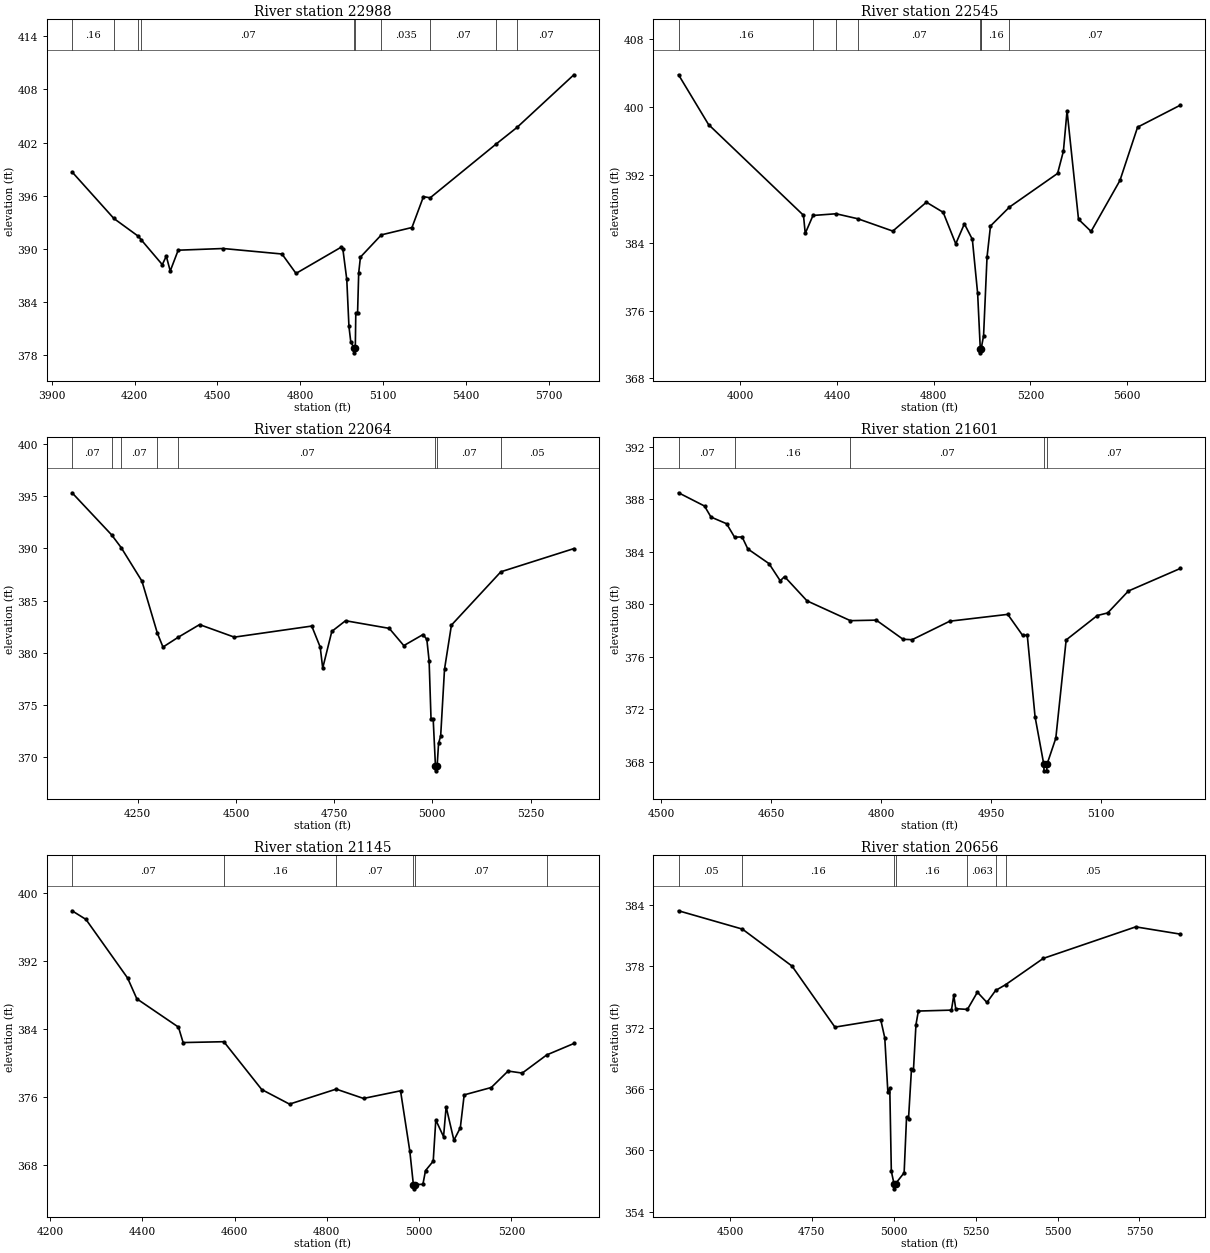
Type RM Length L Ch R = 1,22988,443,443,443
BEGIN DESCRIPTION:
Cedar Creek 39.0
END DESCRIPTION:
XS GIS Cut Line= 3
      2555625.02     13794375.03      2556275.00     13795175.00
      2556756.31     13795796.98
#Sta/Elev= 30
  3973.8  398.69  4125.1  393.44  4214.2  391.42  4224.3  391.03  4300.6  388.23
  4315.0  389.19  4329.3  387.51  4358.1  389.86  4521.1  390.05  4734.0  389.43
  4784.8  387.24  4947.8  390.19  4954.2  390.05  4968.6  386.57  4976.5  381.26
  4983.0  379.55  4995.2  378.78  4995.5  378.28  4999.5  378.78  5001.3  382.75
  5007.7  382.75  5011.8  387.29  5018.1  389.08  5093.9  391.59  5204.7  392.42
  5246.3  395.90  5270.7  395.77  5508.4  401.81  5585.5  403.72  5791.0  409.65
#Mann=10,-1,0
  3973.8    0.16       0  4125.1    0.07       0  4214.2    0.16       0
  4224.3    0.07       0  4995.2    0.07       0  4999.5    0.07       0
  5093.9   0.035       0  5270.7    0.07       0  5508.4    0.16       0
  5585.5    0.07       0
Bank Sta=4995.2,4999.5
Exp/Cntr=0.3,0.1

Type RM Length L Ch R = 1,22545,481,481,481
BEGIN DESCRIPTION:
Cedar Creek 38.0
END DESCRIPTION:
XS GIS Cut Line= 3
      2555408.97     13794277.25      2555925.00     13795425.00
      2556148.42     13796209.80
#Sta/Elev= 30
  3745.5  403.77  3869.5  397.91  4262.0  387.22  4269.3  385.09  4301.4  387.20
  4396.8  387.40  4487.0  386.81  4631.3  385.36  4770.2  388.76  4839.5  387.57
  4891.5  383.86  4927.2  386.21  4960.1  384.39  4982.0  378.02  4992.9  371.52
  4993.2  371.02  4997.2  371.52  4997.6  371.67  5006.5  373.02  5020.8  382.29
  5035.1  385.96  5113.6  388.19  5312.5  392.15  5336.6  394.78  5351.6  399.53
  5399.0  386.75  5451.0  385.32  5570.3  391.32  5643.2  397.60  5819.9  400.19
#Mann=8,-1,0
  3745.5    0.16       0  4301.4    0.07       0  4396.8    0.16       0
  4487.0    0.07       0  4992.9    0.07       0  4997.2    0.07       0
  4997.6    0.16       0  5113.6    0.07       0
Bank Sta=4992.9,4997.2
Exp/Cntr=0.3,0.1

Type RM Length L Ch R = 1,22064,463,463,463
BEGIN DESCRIPTION:
Cedar Creek 37.0
END DESCRIPTION:
XS GIS Cut Line= 3
      2555009.72     13794735.40      2555475.00     13795525.00
      2555581.35     13795869.57
#Sta/Elev= 30
  4083.1  395.32  4183.6  391.30  4208.0  390.08  4260.9  386.87  4300.1  381.90
  4314.5  380.56  4353.3  381.50  4407.6  382.71  4496.0  381.51  4693.1  382.57
  4714.6  380.56  4721.0  378.55  4744.2  382.06  4779.1  383.08  4890.3  382.35
  4927.4  380.70  4976.4  381.76  4986.0  381.29  4991.8  379.25  4996.7  373.66
  5002.2  373.66  5007.9  369.22  5008.2  368.72  5012.3  369.22  5015.9  371.37
  5021.2  372.04  5031.0  378.44  5048.6  382.66  5174.4  387.76  5360.2  389.98
#Mann=8,-1,0
  4083.1    0.07       0  4183.6    0.16       0  4208.0    0.07       0
  4300.1    0.16       0  4353.3    0.07       0  5007.9    0.07       0
  5012.3    0.07       0  5174.4    0.05       0
Bank Sta=5007.9,5012.3
Exp/Cntr=0.3,0.1

Type RM Length L Ch R = 1,21601,456,456,456
BEGIN DESCRIPTION:
Cedar Creek 36.0
END DESCRIPTION:
XS GIS Cut Line= 3
      2554774.99     13795174.98      2555025.00     13795575.00
      2555175.03     13795725.03
#Sta/Elev= 30
  4523.9  388.50  4559.3  387.49  4568.1  386.65  4589.4  386.14  4600.2  385.12
  4610.6  385.13  4618.3  384.22  4647.2  383.10  4662.5  381.79  4668.4  382.11
  4699.0  380.26  4758.1  378.75  4793.4  378.79  4829.9  377.33  4842.3  377.30
  4893.6  378.71  4972.6  379.23  4992.7  377.64  4999.2  377.64  5009.8  371.43
  5021.7  367.80  5022.0  367.30  5025.8  367.30  5026.1  367.80  5038.1  369.79
  5052.2  377.28  5094.6  379.14  5108.8  379.34  5137.0  381.01  5207.8  382.73
#Mann=5,-1,0
  4523.9    0.07       0  4600.2    0.16       0  4758.1    0.07       0
  5021.7    0.07       0  5026.1    0.07       0
Bank Sta=5021.7,5026.1
Exp/Cntr=0.3,0.1

Type RM Length L Ch R = 1,21145,489,489,489
BEGIN DESCRIPTION:
Cedar Creek 35.0
END DESCRIPTION:
XS GIS Cut Line= 3
      2554675.00     13794974.96      2554625.00     13795725.00
      2554924.99     13795874.99
#Sta/Elev= 30
  4248.1  397.92  4278.2  396.90  4368.4  389.99  4388.4  387.54  4478.6  384.20
  4488.7  382.38  4576.9  382.48  4659.0  376.84  4719.2  375.12  4820.3  376.89
  4879.5  375.79  4959.7  376.69  4979.8  369.58  4987.5  365.63  4987.8  365.13
  4992.1  365.63  5008.2  365.67  5013.8  367.28  5030.5  368.39  5036.1  373.25
  5052.9  371.28  5058.5  374.80  5075.3  370.86  5089.2  372.33  5097.6  376.21
  5156.3  377.08  5192.7  379.02  5223.4  378.78  5276.4  380.92  5335.2  382.27
#Mann=6,-1,0
  4248.1    0.07       0  4576.9    0.16       0  4820.3    0.07       0
  4987.5    0.07       0  4992.1    0.07       0  5276.4    0.05       0
Bank Sta=4987.5,4992.1
Exp/Cntr=0.3,0.1

Type RM Length L Ch R = 1,20656,469,469,469
BEGIN DESCRIPTION:
Cedar Creek 34.0
END DESCRIPTION:
XS GIS Cut Line= 3
      2553621.53     13795479.42      2554175.00     13795825.00
      2554905.43     13796314.18
#Sta/Elev= 30
  4343.1  383.40  4538.0  381.61  4689.5  378.00  4820.4  372.04  4960.2  372.77
  4972.6  370.99  4982.0  365.71  4987.9  366.06  4992.6  357.97  5000.7  356.75
  5001.1  356.25  5005.4  356.75  5031.7  357.82  5039.1  363.27  5045.1  363.11
  5054.1  367.94  5060.1  367.83  5067.8  372.28  5075.1  373.61  5176.1  373.70
  5183.2  375.14  5189.2  373.84  5224.9  373.77  5255.3  375.45  5284.4  374.45
  5310.9  375.62  5341.2  376.18  5456.4  378.75  5738.6  381.83  5874.7  381.12
#Mann=7,-1,0
  4343.1    0.05       0  4538.0    0.16       0  5000.7    0.07       0
  5005.4    0.16       0  5224.9   0.063       0  5310.9   0.035       0
  5341.2    0.05       0
Bank Sta=5000.7,5005.4
Exp/Cntr=0.3,0.1

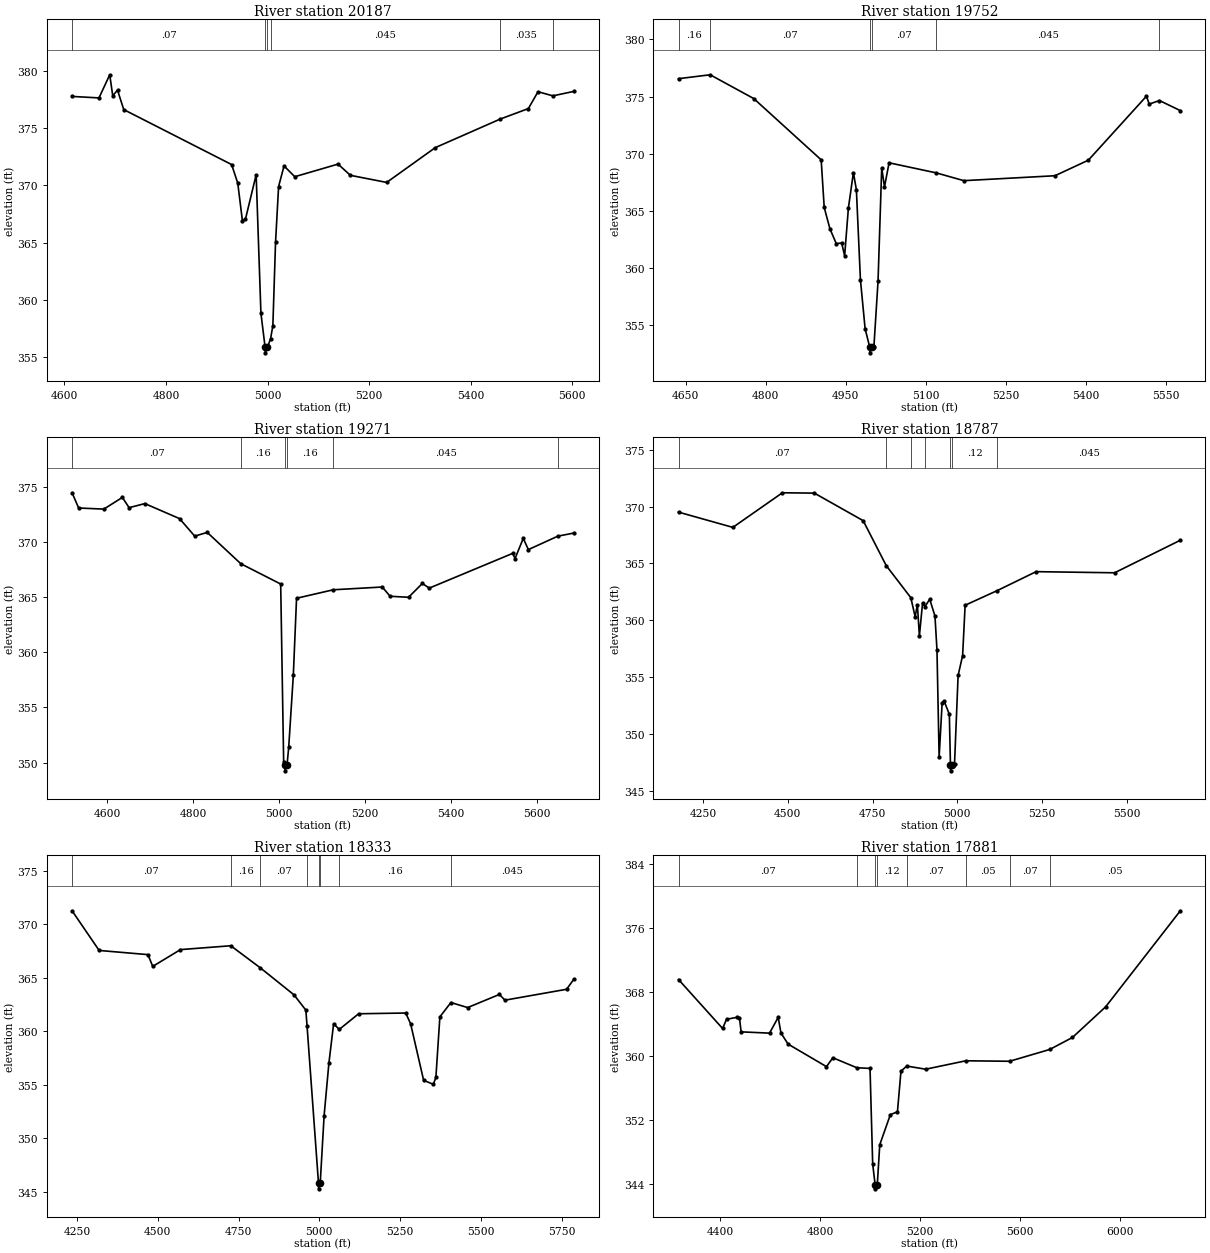
Type RM Length L Ch R = 1,20187,435,435,435
BEGIN DESCRIPTION:
Cedar Creek 33.0
END DESCRIPTION:
XS GIS Cut Line= 3
      2553598.89     13795969.40      2553925.00     13796175.00
      2554491.32     13796381.76
#Sta/Elev= 30
  4615.0  377.77  4668.0  377.64  4689.2  379.66  4695.1  377.83  4704.5  378.32
  4716.8  376.62  4929.3  371.82  4941.4  370.19  4950.5  366.92  4956.4  367.03
  4977.6  370.93  4987.0  358.83  4995.2  355.88  4995.6  355.38  4999.9  355.88
  5006.0  356.60  5010.5  357.75  5015.8  365.03  5021.8  369.90  5032.5  371.70
  5053.7  370.76  5138.9  371.86  5163.2  370.88  5234.7  370.26  5330.5  373.30
  5458.2  375.79  5513.8  376.71  5532.8  378.18  5562.0  377.82  5603.4  378.21
#Mann=6,-1,0
  4615.0    0.07       0  4995.2    0.07       0  4999.9    0.07       0
  5006.0   0.045       0  5458.2   0.035       0  5562.0    0.05       0
Bank Sta=4995.2,4999.9
Exp/Cntr=0.3,0.1

Type RM Length L Ch R = 1,19752,481,481,481
BEGIN DESCRIPTION:
Cedar Creek 32.0
END DESCRIPTION:
XS GIS Cut Line= 3
      2553503.62     13796404.91      2553825.00     13796575.00
      2554381.85     13796726.49
#Sta/Elev= 30
  4636.3  376.56  4695.6  376.90  4777.4  374.82  4903.7  369.47  4909.4  365.31
  4920.1  363.45  4932.0  362.15  4942.1  362.21  4947.7  361.09  4954.7  365.25
  4964.1  368.35  4969.7  366.86  4977.3  358.99  4986.1  354.71  4994.7  353.11
  4995.0  352.61  4999.4  353.11  5002.5  353.11  5010.3  358.86  5017.2  368.76
  5022.4  367.11  5031.0  369.21  5119.5  368.33  5171.1  367.65  5341.9  368.08
  5404.6  369.44  5513.5  375.03  5518.7  374.34  5537.9  374.65  5577.0  373.77
#Mann=6,-1,0
  4636.3    0.16       0  4695.6    0.07       0  4994.7    0.07       0
  4999.4    0.07       0  5119.5   0.045       0  5537.9   0.035       0
Bank Sta=4994.7,4999.4
Exp/Cntr=0.3,0.1

Type RM Length L Ch R = 1,19271,484,484,484
BEGIN DESCRIPTION:
Cedar Creek 31.0
END DESCRIPTION:
XS GIS Cut Line= 3
      2553480.92     13796609.05      2553725.00     13797025.00
      2554363.71     13797270.67
#Sta/Elev= 30
  4518.5  374.45  4533.8  373.07  4592.4  372.97  4635.4  374.03  4651.1  373.10
  4687.7  373.47  4768.3  372.11  4803.7  370.52  4832.7  370.86  4910.8  368.02
  5003.5  366.18  5010.4  350.09  5013.3  349.75  5013.7  349.25  5018.2  349.75
  5022.2  351.40  5032.9  357.92  5040.4  364.89  5125.9  365.66  5239.7  365.91
  5257.9  365.07  5300.8  364.98  5332.9  366.23  5349.0  365.81  5542.9  368.96
  5548.3  368.49  5567.5  370.32  5579.3  369.30  5648.0  370.52  5685.1  370.80
#Mann=6,-1,0
  4518.5    0.07       0  4910.8    0.16       0  5013.3    0.07       0
  5018.2    0.16       0  5125.9   0.045       0  5648.0   0.035       0
Bank Sta=5013.3,5018.2
Exp/Cntr=0.3,0.1

Type RM Length L Ch R = 1,18787,454,454,454
BEGIN DESCRIPTION:
Cedar Creek 30.0
END DESCRIPTION:
XS GIS Cut Line= 3
      2552823.12     13796985.58      2553525.00     13797425.00
      2554156.89     13797588.95
#Sta/Elev= 30
  4177.5  369.51  4337.8  368.17  4484.0  371.21  4578.3  371.18  4722.4  368.76
  4790.5  364.81  4863.1  361.99  4875.8  360.32  4882.4  361.38  4888.3  358.63
  4897.7  361.53  4904.7  361.21  4918.9  361.86  4934.3  360.37  4940.2  357.42
  4946.6  347.99  4955.5  352.78  4961.4  352.90  4976.7  351.75  4980.0  347.28
  4980.4  346.78  4985.2  347.28  4992.0  347.38  5002.6  355.16  5015.9  356.91
  5023.3  361.33  5118.3  362.62  5232.9  364.28  5464.4  364.18  5658.4  367.04
#Mann=7,-1,0
  4177.5    0.07       0  4790.5    0.12       0  4863.1    0.16       0
  4904.7    0.12       0  4980.0    0.07       0  4985.2    0.12       0
  5118.3   0.045       0
Bank Sta=4980,4985.2
Exp/Cntr=0.3,0.1

Type RM Length L Ch R = 1,18333,452,452,452
BEGIN DESCRIPTION:
Cedar Creek 29.0
END DESCRIPTION:
XS GIS Cut Line= 3
      2552714.26     13796967.47      2553213.26     13797661.53
      2553907.35     13797734.11
#Sta/Elev= 30
  4234.8  371.26  4318.6  367.55  4469.6  367.16  4484.4  366.06  4570.3  367.63
  4725.9  367.99  4817.5  365.92  4921.5  363.40  4958.2  361.97  4962.0  360.46
  4997.4  345.76  4997.8  345.26  5002.6  345.76  5014.7  352.10  5029.4  356.98
  5044.1  360.69  5061.7  360.17  5121.5  361.63  5267.3  361.70  5282.4  360.69
  5322.6  355.41  5352.8  355.03  5360.6  355.69  5372.9  361.34  5407.0  362.68
  5458.9  362.21  5557.3  363.44  5574.0  362.90  5765.0  363.92  5787.5  364.86
#Mann=8,-1,0
  4234.8    0.07       0  4725.9    0.16       0  4817.5    0.07       0
  4962.0    0.12       0  4997.4    0.07       0  5002.6    0.12       0
  5061.7    0.16       0  5407.0   0.045       0
Bank Sta=4997.4,5002.6
Exp/Cntr=0.3,0.1

Type RM Length L Ch R = 1,17881,485,485,485
BEGIN DESCRIPTION:
Cedar Creek 28.0
END DESCRIPTION:
XS GIS Cut Line= 4
      2552623.49     13797089.89      2552825.00     13797825.00
      2553025.00     13798025.00      2553213.25     13798968.02
#Sta/Elev= 30
  4233.9  369.54  4410.1  363.43  4425.8  364.58  4467.3  364.82  4477.7  364.73
  4484.2  363.01  4597.9  362.85  4632.4  364.82  4643.6  362.86  4672.1  361.48
  4825.5  358.67  4851.0  359.78  4947.1  358.53  4999.7  358.45  5010.3  346.54
  5020.1  343.92  5020.6  343.42  5028.7  343.92  5038.6  348.92  5081.0  352.68
  5109.3  353.03  5123.4  358.10  5146.5  358.74  5222.4  358.35  5382.7  359.40
  5557.8  359.34  5718.1  360.81  5809.2  362.31  5941.8  366.13  6240.6  378.12
#Mann=8,-1,0
  4233.9    0.07       0  4947.1    0.12       0  5020.1    0.07       0
  5028.7    0.12       0  5146.5    0.07       0  5382.7    0.05       0
  5557.8    0.07       0  5718.1    0.05       0
Bank Sta=5020.1,5028.7
Exp/Cntr=0.3,0.1

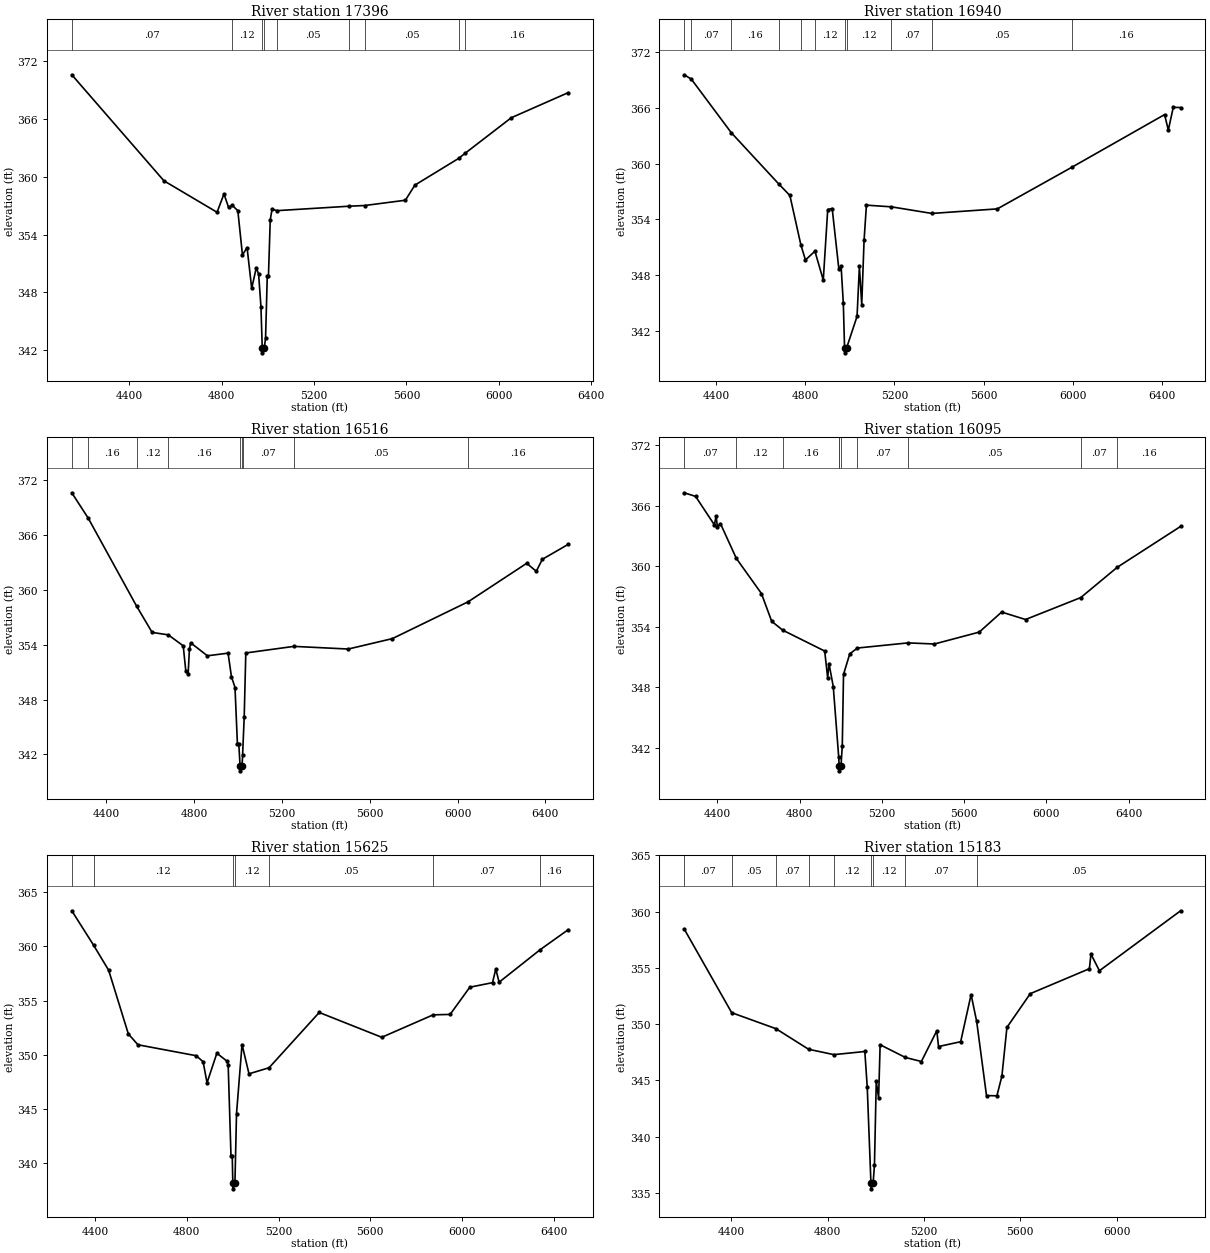
Type RM Length L Ch R = 1,17396,456,456,456
BEGIN DESCRIPTION:
Cedar Creek 27.0
END DESCRIPTION:
XS GIS Cut Line= 4
      2552428.43     13797126.18      2552425.00     13797975.00
      2552475.00     13798175.00      2552740.27     13799236.07
#Sta/Elev= 30
  4151.2  370.61  4550.0  359.60  4780.0  356.33  4810.0  358.23  4830.0  356.83
  4846.0  357.05  4870.0  356.49  4890.0  351.90  4910.0  352.66  4930.0  348.43
  4950.0  350.58  4960.0  349.89  4970.0  346.54  4975.7  342.23  4976.2  341.73
  4984.4  342.23  4990.0  343.26  4997.5  349.75  5002.6  349.75  5010.3  355.54
  5018.1  356.63  5040.8  356.50  5352.0  356.96  5418.8  357.03  5595.3  357.58
  5636.5  359.15  5827.0  361.94  5854.6  362.47  6054.0  366.15  6299.9  368.75
#Mann=9,-1,0
  4151.2    0.07       0  4846.0    0.12       0  4975.7    0.07       0
  4984.4    0.12       0  5040.8    0.05       0  5352.0    0.07       0
  5418.8    0.05       0  5827.0    0.07       0  5854.6    0.16       0
Bank Sta=4975.7,4984.4
Exp/Cntr=0.3,0.1

Type RM Length L Ch R = 1,16940,424,424,424
BEGIN DESCRIPTION:
Cedar Creek 26.0
END DESCRIPTION:
XS GIS Cut Line= 4
      2552024.67     13797180.66      2552025.00     13797925.00
      2552075.00     13798075.00      2552640.83     13799274.81
#Sta/Elev= 30
  4256.0  369.55  4287.8  369.08  4467.0  363.33  4681.4  357.79  4730.3  356.58
  4779.9  351.25  4800.3  349.65  4842.8  350.59  4880.3  347.49  4900.3  355.07
  4920.3  355.18  4950.3  348.67  4960.3  349.00  4970.3  345.02  4975.9  340.17
  4976.4  339.67  4984.7  340.17  5032.0  343.59  5042.5  348.95  5053.0  344.84
  5063.6  351.80  5074.1  355.54  5186.0  355.36  5367.9  354.65  5662.0  355.14
  5997.9  359.63  6413.0  365.27  6429.9  363.61  6452.0  366.05  6485.0  366.03
#Mann=11,-1,0
  4256.0    0.16       0  4287.8    0.07       0  4467.0    0.16       0
  4681.4    0.12       0  4779.9    0.07       0  4842.8    0.12       0
  4975.9    0.07       0  4984.7    0.12       0  5186.0    0.07       0
  5367.9    0.05       0  5997.9    0.16       0
Bank Sta=4975.9,4984.7
Exp/Cntr=0.3,0.1

Type RM Length L Ch R = 1,16516,421,421,421
BEGIN DESCRIPTION:
Cedar Creek 25.0
END DESCRIPTION:
XS GIS Cut Line= 4
      2551366.85     13797407.44      2551725.00     13798075.00
      2552178.92     13798559.77      2552578.13     13799299.21
#Sta/Elev= 30
  4242.0  370.63  4316.9  367.85  4537.2  358.23  4608.1  355.35  4681.9  355.08
  4749.9  353.88  4761.6  351.11  4772.2  350.76  4777.9  353.49  4783.9  354.21
  4859.9  352.79  4954.2  353.08  4969.5  350.52  4985.8  349.32  4996.7  343.19
  5003.0  343.19  5009.0  340.70  5009.5  340.20  5017.9  340.70  5020.4  341.94
  5027.7  346.07  5035.0  353.10  5254.2  353.82  5502.0  353.53  5703.0  354.67
  6048.2  358.70  6315.1  362.91  6358.9  362.04  6386.4  363.35  6504.0  364.98
#Mann=9,-1,0
  4242.0    0.07       0  4316.9    0.16       0  4537.2    0.12       0
  4681.9    0.16       0  5009.0    0.07       0  5017.9    0.16       0
  5020.4    0.07       0  5254.2    0.05       0  6048.2    0.16       0
Bank Sta=5009,5017.9
Exp/Cntr=0.3,0.1

Type RM Length L Ch R = 1,16095,470,470,470
BEGIN DESCRIPTION:
Cedar Creek 24.0
END DESCRIPTION:
XS GIS Cut Line= 4
      2550913.21     13797670.60      2551375.00     13798275.00
      2552075.00     13798725.00      2552423.89     13799467.09
#Sta/Elev= 30
  4239.4  367.29  4294.5  366.93  4386.0  364.10  4394.2  364.99  4400.5  363.90
  4415.1  364.24  4492.7  360.77  4614.6  357.29  4664.4  354.53  4718.2  353.65
  4922.1  351.58  4936.6  348.91  4942.9  350.34  4963.7  348.06  4990.1  341.09
  4992.4  340.19  4992.9  339.69  5001.4  340.19  5007.6  342.20  5013.6  349.26
  5043.9  351.30  5081.1  351.88  5327.2  352.39  5455.4  352.28  5673.3  353.46
  5782.3  355.45  5898.5  354.71  6167.0  356.89  6344.0  359.89  6652.2  363.95
#Mann=10,-1,0
  4239.4    0.07       0  4492.7    0.12       0  4718.2    0.16       0
  4990.1    0.12       0  4992.4    0.07       0  5001.4    0.12       0
  5081.1    0.07       0  5327.2    0.05       0  6167.0    0.07       0
  6344.0    0.16       0
Bank Sta=4992.4,5001.4
Exp/Cntr=0.3,0.1

Type RM Length L Ch R = 1,15625,442,442,442
BEGIN DESCRIPTION:
Cedar Creek 23.0
END DESCRIPTION:
XS GIS Cut Line= 4
      2550875.00     13797975.00      2551125.00     13798625.00
      2551525.00     13798775.00      2552192.53     13799571.43
#Sta/Elev= 30
  4299.0  363.28  4394.7  360.08  4459.7  357.79  4545.4  351.92  4587.2  350.92
  4841.1  349.91  4871.1  349.36  4888.3  347.41  4931.1  350.14  4974.0  349.43
  4980.4  349.05  4992.7  340.66  4998.1  340.66  5000.7  338.13  5001.2  337.63
  5009.8  338.13  5016.8  344.57  5040.8  350.94  5071.1  348.24  5158.6  348.80
  5377.2  353.90  5649.7  351.61  5873.6  353.68  5947.6  353.72  6033.4  356.23
  6132.3  356.65  6146.6  357.91  6161.0  356.69  6340.5  359.70  6461.8  361.53
#Mann=7,-1,0
  4299.0    0.07       0  4394.7    0.12       0  5000.7    0.07       0
  5009.8    0.12       0  5158.6    0.05       0  5873.6    0.07       0
  6340.5    0.16       0
Bank Sta=5000.7,5009.8
Exp/Cntr=0.3,0.1

Type RM Length L Ch R = 1,15183,449,449,449
BEGIN DESCRIPTION:
Cedar Creek 22.0
END DESCRIPTION:
XS GIS Cut Line= 4
      2550825.00     13798125.03      2550825.00     13798925.00
      2551325.00     13799325.00      2551810.17     13799713.13
#Sta/Elev= 30
  4204.3  358.44  4401.3  351.01  4584.8  349.59  4720.6  347.76  4825.8  347.28
  4954.3  347.56  4964.3  344.41  4979.7  335.85  4980.2  335.35  4988.8  335.85
  4994.3  337.47  5001.8  344.90  5011.5  343.44  5017.9  348.16  5122.7  347.03
  5189.2  346.67  5253.2  349.40  5260.4  348.00  5352.4  348.43  5395.7  352.62
  5418.8  350.24  5459.7  343.64  5502.9  343.62  5523.7  345.38  5544.5  349.70
  5641.4  352.70  5887.1  354.92  5893.5  356.22  5928.7  354.74  6265.9  360.07
#Mann=9,-1,0
  4204.3    0.07       0  4401.3    0.05       0  4584.8    0.07       0
  4720.6    0.05       0  4825.8    0.12       0  4979.7    0.07       0
  4988.8    0.12       0  5122.7    0.07       0  5418.8    0.05       0
Bank Sta=4979.7,4988.8
Exp/Cntr=0.3,0.1

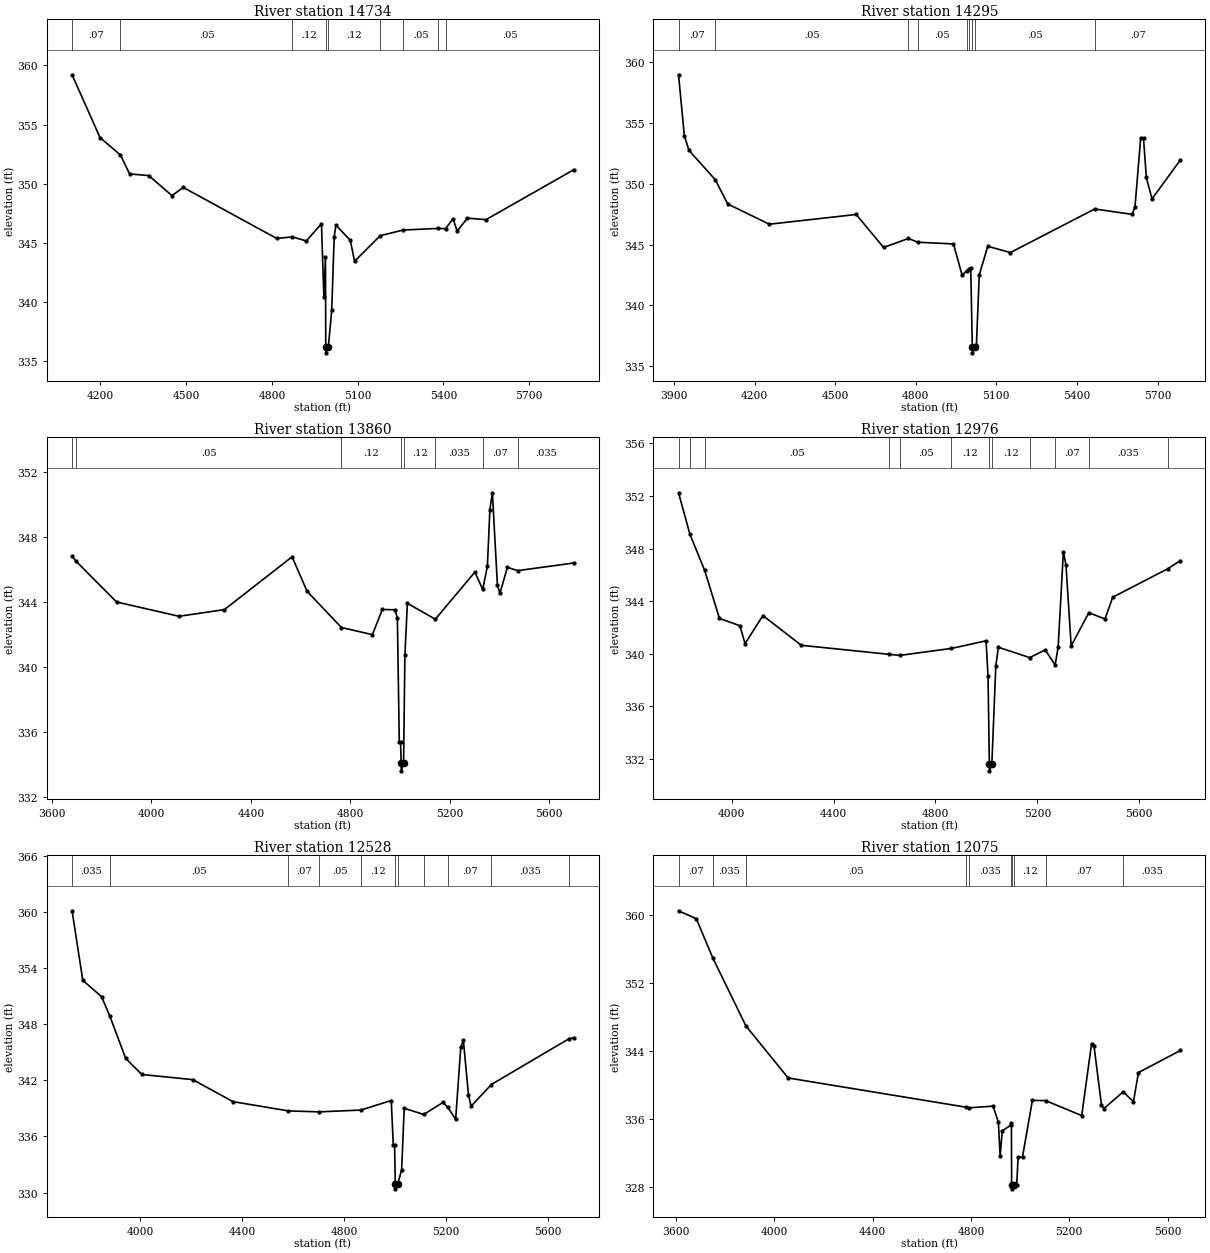
Type RM Length L Ch R = 1,14734,439,439,439
BEGIN DESCRIPTION:
Cedar Creek 21.0
END DESCRIPTION:
XS GIS Cut Line= 3
      2550775.02     13798124.96      2550375.00     13798925.00
      2550874.99     13799624.99
#Sta/Elev= 30
  4101.3  359.21  4199.2  353.89  4270.6  352.42  4302.6  350.82  4369.7  350.68
  4450.7  348.98  4489.9  349.68  4816.9  345.36  4871.8  345.49  4920.3  345.15
  4973.4  346.60  4981.8  340.43  4987.4  343.76  4988.4  336.18  4988.9  335.68
  4997.5  336.18  5009.3  339.30  5017.9  345.48  5024.0  346.50  5074.4  345.19
  5089.2  343.43  5178.6  345.59  5258.6  346.07  5382.0  346.21  5407.5  346.18
  5433.3  347.03  5448.0  345.98  5483.7  347.08  5548.8  346.95  5856.0  351.18
#Mann=9,-1,0
  4101.3    0.07       0  4270.6    0.05       0  4871.8    0.12       0
  4988.4    0.07       0  4997.5    0.12       0  5178.6    0.07       0
  5258.6    0.05       0  5382.0    0.07       0  5407.5    0.05       0
Bank Sta=4988.4,4997.5
Exp/Cntr=0.3,0.1

Type RM Length L Ch R = 1,14295,435,435,435
BEGIN DESCRIPTION:
Cedar Creek 20.0
END DESCRIPTION:
XS GIS Cut Line= 3
      2550425.00     13798075.00      2550025.00     13799075.00
      2550275.00     13799825.00
#Sta/Elev= 30
  3917.2  358.95  3938.7  353.95  3956.2  352.73  4053.8  350.33  4100.3  348.33
  4255.1  346.67  4578.2  347.47  4680.5  344.76  4772.9  345.50  4807.5  345.19
  4940.4  345.05  4972.7  342.48  4990.4  342.86  4999.6  343.03  5004.8  343.06
  5010.6  336.60  5011.1  336.10  5020.1  336.60  5025.9  336.72  5036.4  342.49
  5068.0  344.86  5152.3  344.34  5466.1  347.92  5605.6  347.48  5616.2  348.12
  5637.2  353.76  5647.8  353.72  5658.3  350.51  5679.4  348.75  5784.8  351.94
#Mann=9,-1,0
  3917.2    0.07       0  4053.8    0.05       0  4772.9    0.12       0
  4807.5    0.05       0  4990.4    0.12       0  4999.6    0.05       0
  5010.6    0.05       0  5020.1    0.05       0  5466.1    0.07       0
Bank Sta=5010.6,5020.1
Exp/Cntr=0.3,0.1

Type RM Length L Ch R = 1,13860,884,884,884
BEGIN DESCRIPTION:
Cedar Creek 19.0
END DESCRIPTION:
XS GIS Cut Line= 3
      2549796.48     13797867.42      2549625.00     13799175.00
      2549550.79     13799870.88
#Sta/Elev= 30
  3680.7  346.81  3694.6  346.53  3859.8  343.99  4111.0  343.11  4293.5  343.52
  4565.8  346.77  4626.3  344.64  4764.4  342.42  4888.8  341.98  4928.9  343.53
  4979.3  343.51  4989.4  343.01  4997.0  335.36  5002.0  335.36  5004.7  334.10
  5005.2  333.60  5014.3  334.10  5019.6  340.72  5029.6  343.91  5141.9  342.93
  5301.2  345.83  5332.7  344.76  5351.5  346.20  5361.5  349.68  5371.6  350.71
  5391.7  345.04  5401.7  344.52  5431.9  346.12  5473.6  345.92  5699.3  346.39
#Mann=8,-1,0
  3680.7   0.035       0  3694.6    0.05       0  4764.4    0.12       0
  5004.7    0.07       0  5014.3    0.12       0  5141.9   0.035       0
  5332.7    0.07       0  5473.6   0.035       0
Bank Sta=5004.7,5014.3
Exp/Cntr=0.3,0.1

Type RM Length L Ch R = 1,12976,448,448,448
BEGIN DESCRIPTION:
Cedar Creek 18.0
END DESCRIPTION:
XS GIS Cut Line= 3
      2549225.00     13797925.00      2549125.00     13799125.00
      2548975.00     13799874.99
#Sta/Elev= 30
  3791.7  352.25  3836.3  349.10  3894.2  346.35  3952.3  342.69  4032.5  342.14
  4052.6  340.78  4122.8  342.91  4273.4  340.65  4619.5  339.96  4659.3  339.88
  4862.5  340.41  4998.4  340.99  5006.1  338.29  5011.4  331.60  5011.9  331.10
  5021.1  331.60  5036.6  339.06  5046.8  340.50  5169.8  339.71  5230.4  340.30
  5269.6  339.15  5281.4  340.54  5301.8  347.77  5312.0  346.75  5332.4  340.60
  5401.7  343.13  5465.0  342.65  5495.6  344.31  5710.6  346.46  5760.7  347.09
#Mann=12,-1,0
  3791.7   0.035       0  3836.3    0.07       0  3894.2    0.05       0
  4619.5    0.07       0  4659.3    0.05       0  4862.5    0.12       0
  5011.4    0.07       0  5021.1    0.12       0  5169.8   0.035       0
  5269.6    0.07       0  5401.7   0.035       0  5710.6    0.05       0
Bank Sta=5011.4,5021.1
Exp/Cntr=0.3,0.1

Type RM Length L Ch R = 1,12528,453,453,453
BEGIN DESCRIPTION:
Cedar Creek 17.0
END DESCRIPTION:
XS GIS Cut Line= 3
      2549125.01     13797874.98      2548725.00     13799075.00
      2548625.00     13799774.97
#Sta/Elev= 30
  3731.1  360.10  3773.3  352.67  3847.1  350.93  3879.5  348.85  3941.9  344.33
  4005.2  342.62  4205.5  342.07  4363.6  339.72  4581.3  338.73  4701.8  338.63
  4865.6  338.82  4985.5  339.84  4993.4  335.10  4998.6  335.10  5001.3  330.91
  5001.8  330.41  5011.0  330.91  5026.3  332.45  5036.4  339.01  5113.1  338.35
  5188.0  339.63  5207.6  339.12  5238.5  337.83  5258.7  345.53  5268.8  346.27
  5289.0  340.44  5299.1  339.23  5378.8  341.55  5683.5  346.43  5703.1  346.55
#Mann=11,-1,0
  3731.1   0.035       0  3879.5    0.05       0  4581.3    0.07       0
  4701.8    0.05       0  4865.6    0.12       0  5001.3    0.07       0
  5011.0    0.12       0  5113.1   0.035       0  5207.6    0.07       0
  5378.8   0.035       0  5683.5    0.05       0
Bank Sta=5001.3,5011
Exp/Cntr=0.3,0.1

Type RM Length L Ch R = 1,12075,484,484,484
BEGIN DESCRIPTION:
Cedar Creek 16.0
END DESCRIPTION:
XS GIS Cut Line= 3
      2549075.01     13797774.99      2548375.00     13798975.00
      2548325.00     13799625.02
#Sta/Elev= 30
  3610.8  360.45  3683.2  359.51  3750.9  354.86  3885.0  346.91  4056.9  340.80
  4781.9  337.36  4790.9  337.29  4890.5  337.49  4912.0  335.57  4919.0  331.63
  4927.7  334.59  4962.9  335.26  4964.9  335.48  4965.8  328.27  4966.3  327.77
  4975.7  328.27  4986.4  328.28  4992.2  331.46  5010.1  331.53  5050.2  338.16
  5103.8  338.14  5250.8  336.38  5290.9  344.82  5300.9  344.55  5331.0  337.67
  5341.1  337.21  5419.7  339.17  5461.4  338.02  5481.5  341.43  5652.0  344.03
#Mann=10,-1,0
  3610.8    0.07       0  3750.9   0.035       0  3885.0    0.05       0
  4781.9    0.12       0  4790.9   0.035       0  4962.9    0.12       0
  4965.8    0.07       0  4975.7    0.12       0  5103.8    0.07       0
  5419.7   0.035       0
Bank Sta=4965.8,4975.7
Exp/Cntr=0.3,0.1