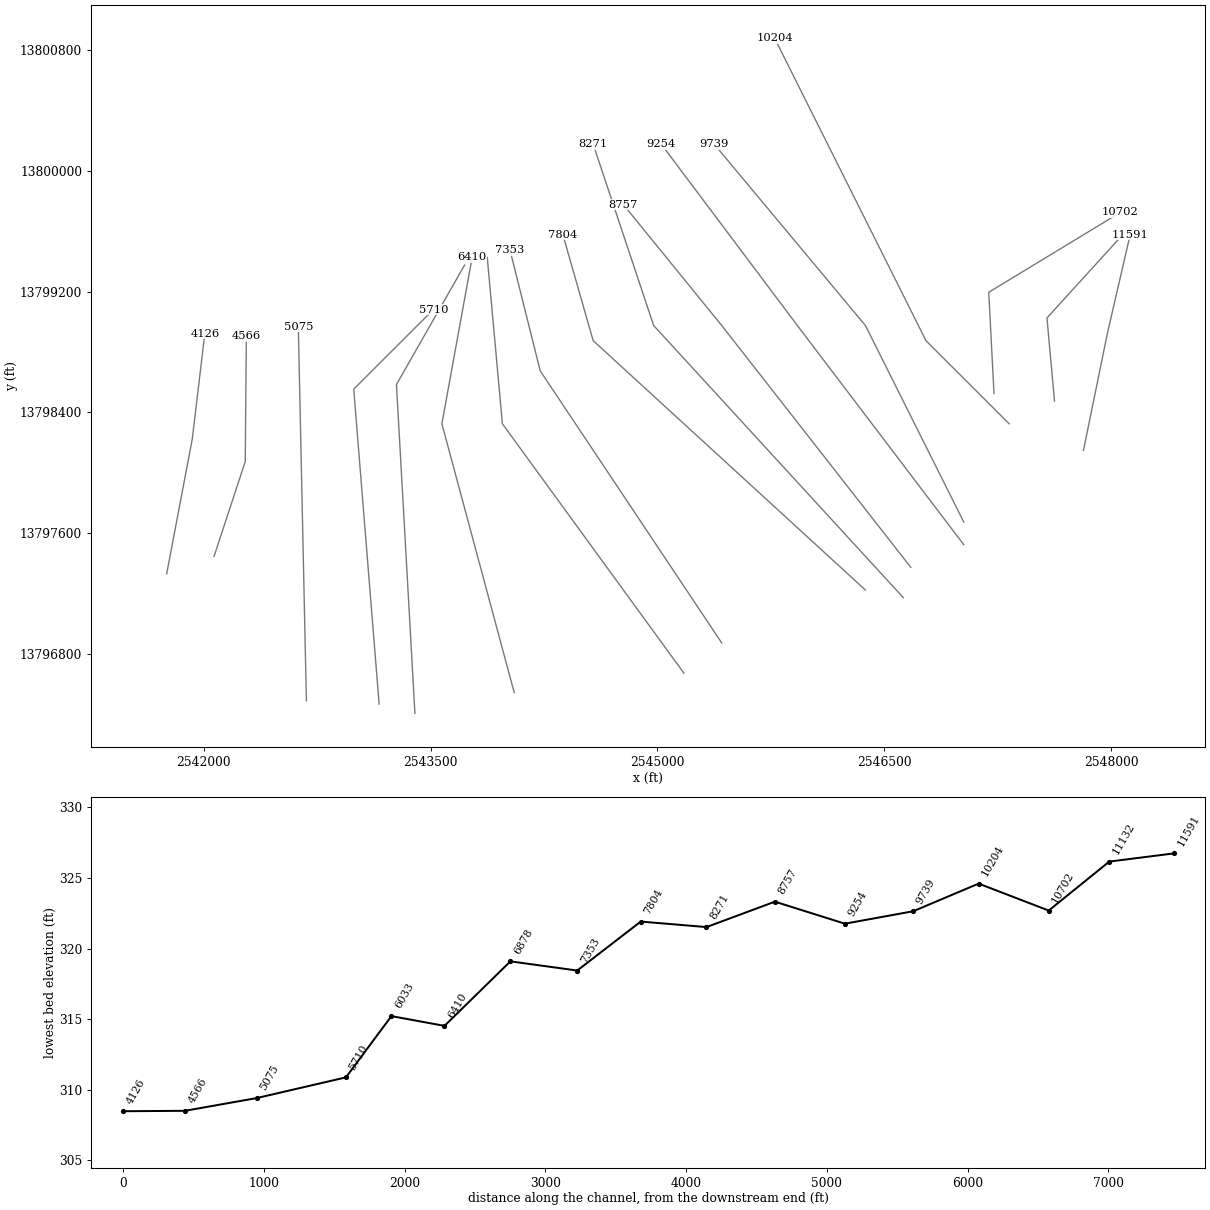
HEC-RAS study Cedar Creek.prj: Cedar Creek Base Level Engineering

--- Cedar Creek.g01 (geometry) --- (continued)

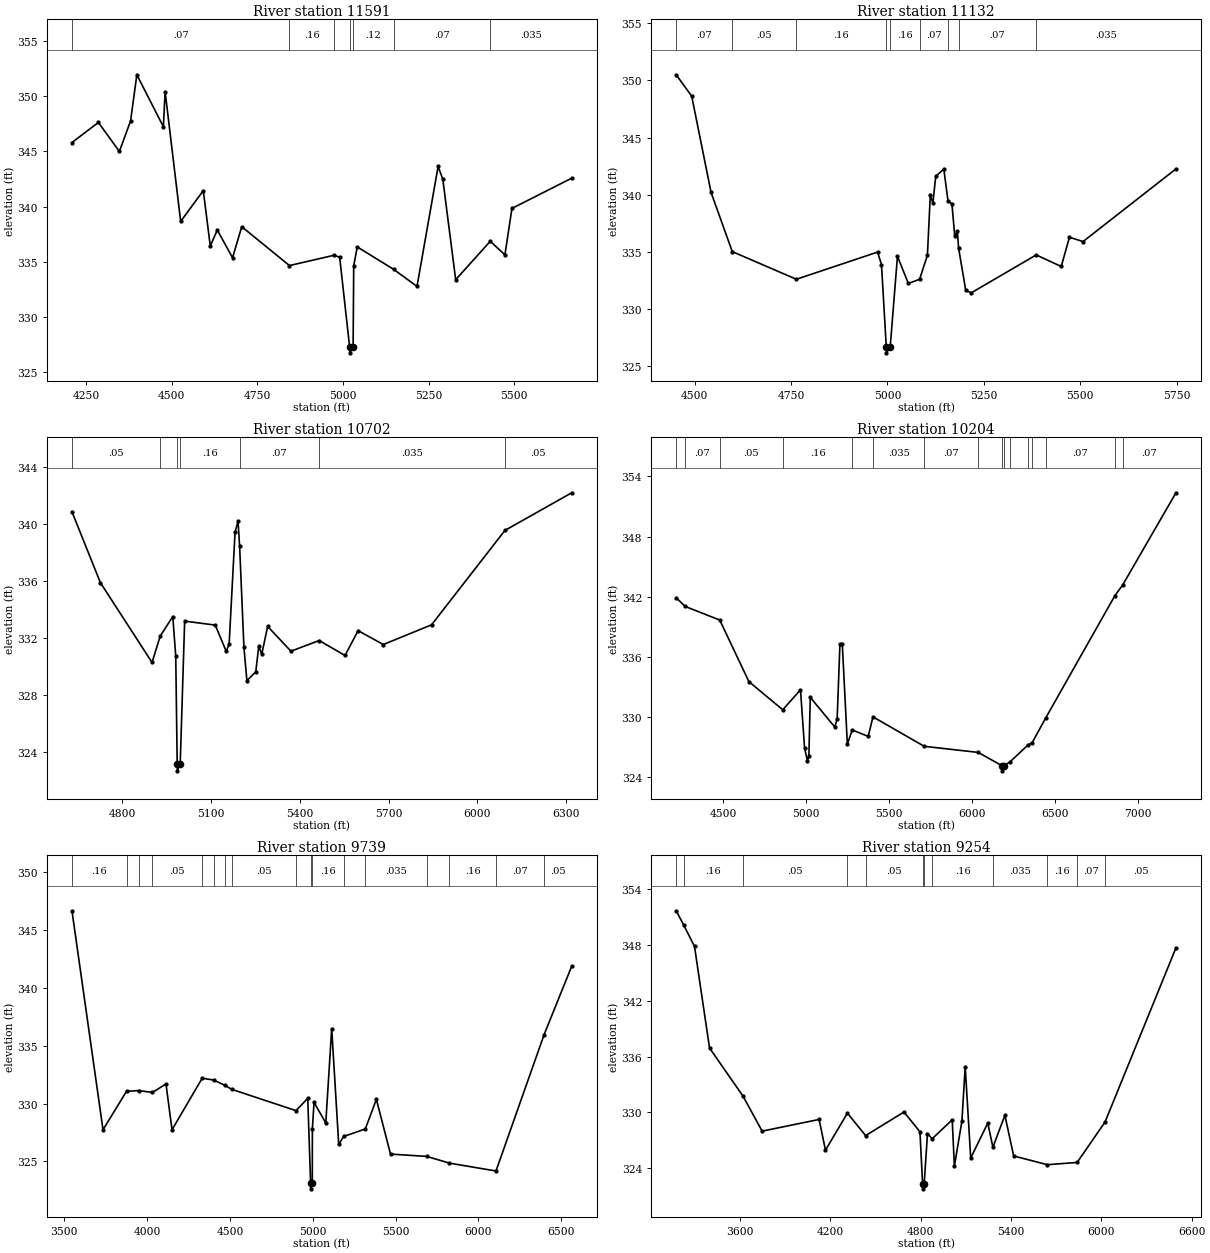
Type RM Length L Ch R = 1,11591,459,459,459
BEGIN DESCRIPTION:
Cedar Creek 15.0
END DESCRIPTION:
XS GIS Cut Line= 3
      2547816.37     13798149.44      2547975.00     13798925.00
      2548125.00     13799575.00
#Sta/Elev= 30
  4208.8  345.80  4285.9  347.62  4347.2  344.99  4379.8  347.75  4398.2  351.94
  4475.6  347.23  4480.7  350.41  4526.1  338.65  4592.1  341.44  4612.5  336.42
  4633.0  337.87  4677.5  335.36  4704.4  338.17  4843.6  334.65  4973.4  335.58
  4990.2  335.41  5019.3  327.24  5019.8  326.74  5029.4  327.24  5031.2  334.64
  5041.5  336.34  5147.6  334.31  5215.9  332.76  5277.5  343.63  5291.2  342.48
  5328.8  333.37  5429.7  336.85  5472.5  335.62  5493.0  339.83  5667.5  342.57
#Mann=7,-1,0
  4208.8    0.07       0  4843.6    0.16       0  4973.4    0.12       0
  5019.3    0.07       0  5029.4    0.12       0  5147.6    0.07       0
  5429.7   0.035       0
Bank Sta=5019.3,5029.4
Exp/Cntr=0.3,0.1

Type RM Length L Ch R = 1,11132,430,430,430
BEGIN DESCRIPTION:
Cedar Creek 14.0
END DESCRIPTION:
XS GIS Cut Line= 3
      2547625.00     13798475.00      2547575.00     13799025.00
      2548075.02     13799575.02
#Sta/Elev= 30
  4452.5  350.50  4492.7  348.63  4542.9  340.20  4597.9  335.02  4764.1  332.60
  4974.6  334.98  4984.7  333.89  4997.2  326.66  4997.7  326.16  5007.3  326.66
  5026.1  334.61  5054.4  332.23  5083.5  332.60  5103.8  334.70  5111.2  339.94
  5118.0  339.29  5125.4  341.61  5146.3  342.25  5157.3  339.42  5167.3  339.21
  5174.7  336.35  5181.5  336.80  5184.7  335.31  5203.1  331.64  5217.3  331.41
  5385.8  334.73  5450.7  333.72  5472.0  336.28  5507.2  335.90  5748.1  342.26
#Mann=9,-1,0
  4452.5    0.07       0  4597.9    0.05       0  4764.1    0.16       0
  4997.2    0.07       0  5007.3    0.16       0  5083.5    0.07       0
  5157.3    0.16       0  5184.7    0.07       0  5385.8   0.035       0
Bank Sta=4997.2,5007.3
Exp/Cntr=0.3,0.1

Type RM Length L Ch R = 1,10702,498,498,498
BEGIN DESCRIPTION:
Cedar Creek 13.0
END DESCRIPTION:
XS GIS Cut Line= 3
      2547225.00     13798524.96      2547190.24     13799195.04
      2548059.48     13799722.80
#Sta/Elev= 30
  4630.5  340.86  4726.4  335.89  4900.9  330.29  4928.6  332.14  4971.0  333.51
  4981.0  330.74  4985.9  323.19  4986.4  322.69  4996.1  323.19  5011.1  333.19
  5114.6  332.91  5151.2  331.08  5161.3  331.56  5181.3  339.42  5191.3  340.20
  5196.8  338.43  5211.3  331.35  5221.3  329.01  5251.4  329.64  5261.4  331.45
  5271.4  330.86  5291.4  332.82  5370.1  331.08  5465.5  331.83  5552.7  330.78
  5596.9  332.52  5682.2  331.55  5845.0  332.93  6092.8  339.55  6318.4  342.19
#Mann=7,-1,0
  4630.5    0.05       0  4928.6    0.16       0  4985.9    0.07       0
  4996.1    0.16       0  5196.8    0.07       0  5465.5   0.035       0
  6092.8    0.05       0
Bank Sta=4985.9,4996.1
Exp/Cntr=0.3,0.1

Type RM Length L Ch R = 1,10204,465,465,465
BEGIN DESCRIPTION:
Cedar Creek 12.0
END DESCRIPTION:
XS GIS Cut Line= 3
      2547325.03     13798324.97      2546775.00     13798875.00
      2545775.01     13800874.97
#Sta/Elev= 30
  4215.3  341.89  4269.2  341.02  4477.9  339.66  4653.8  333.51  4857.9  330.70
  4964.9  332.69  4989.6  326.88  5007.1  325.58  5015.5  326.10  5023.9  331.94
  5172.0  328.97  5186.0  329.79  5202.8  337.27  5216.8  337.31  5247.5  327.27
  5276.9  328.68  5373.3  328.04  5402.0  329.99  5711.0  327.05  6036.5  326.44
  6181.6  325.10  6182.1  324.60  6191.8  325.10  6228.4  325.50  6337.1  327.18
  6362.0  327.41  6444.0  329.89  6861.2  342.10  6908.2  343.17  7229.2  352.37
#Mann=16,-1,0
  4215.3   0.035       0  4269.2    0.07       0  4477.9    0.05       0
  4857.9    0.16       0  5276.9    0.07       0  5402.0   0.035       0
  5711.0    0.07       0  6036.5    0.12       0  6181.6    0.07       0
  6191.8    0.12       0  6228.4    0.05       0  6337.1    0.07       0
  6362.0    0.05       0  6444.0    0.07       0  6861.2    0.16       0
  6908.2    0.07       0
Bank Sta=6181.6,6191.8
Exp/Cntr=0.3,0.1

Type RM Length L Ch R = 1,9739,485,485,485
BEGIN DESCRIPTION:
Cedar Creek 11.0
END DESCRIPTION:
XS GIS Cut Line= 3
      2547025.00     13797675.01      2546375.00     13798975.00
      2545374.99     13800175.01
#Sta/Elev= 30
  3547.0  346.64  3734.3  327.74  3876.1  331.06  3949.4  331.12  4032.5  330.96
  4114.4  331.69  4150.7  327.74  4332.9  332.19  4402.0  332.03  4470.3  331.57
  4510.5  331.23  4898.8  329.39  4969.7  330.45  4987.0  323.14  4987.5  322.64
  4997.2  323.14  4997.6  327.84  5007.6  330.10  5078.5  328.33  5114.3  336.47
  5156.6  326.47  5186.4  327.16  5317.1  327.81  5383.8  330.36  5469.1  325.64
  5687.1  325.44  5824.1  324.86  6105.5  324.18  6395.9  335.95  6562.5  341.86
#Mann=17,-1,0
  3547.0    0.16       0  3876.1    0.05       0  3949.4    0.16       0
  4032.5    0.05       0  4332.9   0.035       0  4402.0    0.05       0
  4470.3   0.035       0  4510.5    0.05       0  4898.8    0.16       0
  4987.0    0.07       0  4997.2    0.16       0  5186.4    0.07       0
  5317.1   0.035       0  5687.1    0.07       0  5824.1    0.16       0
  6105.5    0.07       0  6395.9    0.05       0
Bank Sta=4987,4997.2
Exp/Cntr=0.3,0.1

Type RM Length L Ch R = 1,9254,497,497,497
BEGIN DESCRIPTION:
Cedar Creek 10.0
END DESCRIPTION:
XS GIS Cut Line= 3
      2547024.99     13797525.01      2545925.00     13798975.00
      2545025.01     13800174.99
#Sta/Elev= 30
  3175.7  351.69  3224.5  350.19  3297.4  347.85  3397.2  336.92  3620.0  331.73
  3746.7  327.97  4125.2  329.23  4167.3  325.92  4313.2  329.91  4434.1  327.49
  4688.9  330.03  4795.0  327.90  4812.7  322.26  4813.2  321.76  4823.0  322.26
  4845.1  327.71  4876.2  327.15  5009.3  329.19  5023.8  324.20  5073.8  329.05
  5095.7  334.92  5132.2  325.07  5245.7  328.84  5279.7  326.23  5359.3  329.68
  5417.6  325.30  5641.2  324.36  5839.2  324.60  6024.6  328.95  6495.7  347.70
#Mann=12,-1,0
  3175.7    0.07       0  3224.5    0.16       0  3620.0    0.05       0
  4313.2   0.035       0  4434.1    0.05       0  4812.7    0.07       0
  4823.0    0.05       0  4876.2    0.16       0  5279.7   0.035       0
  5641.2    0.16       0  5839.2    0.07       0  6024.6    0.05       0
Bank Sta=4812.7,4823
Exp/Cntr=0.3,0.1

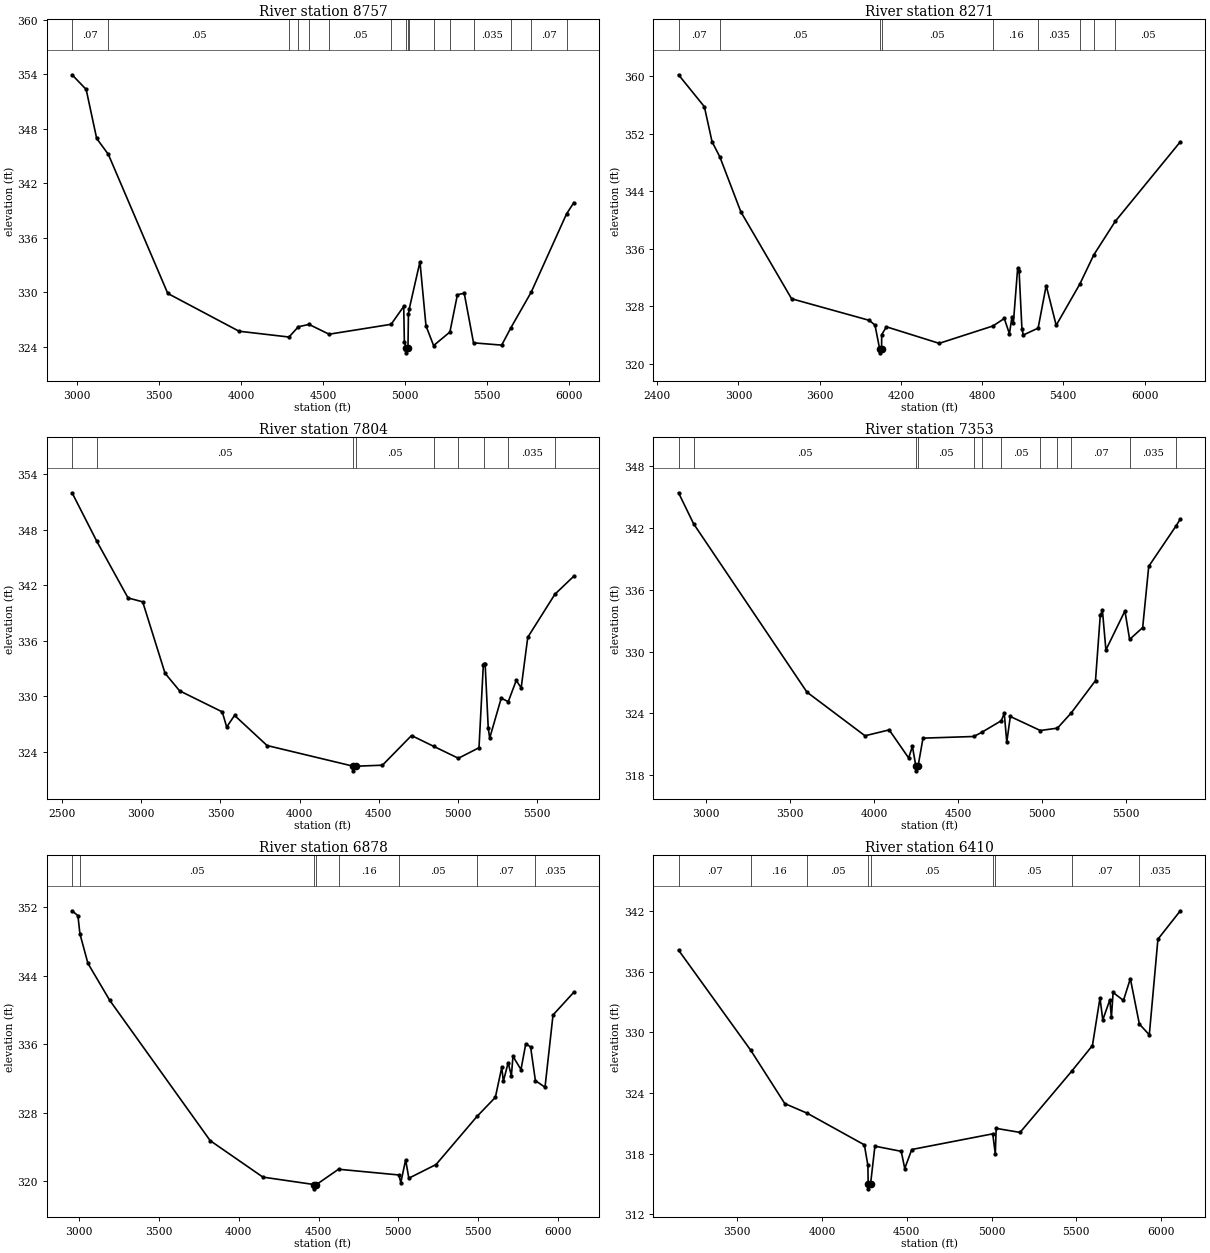
Type RM Length L Ch R = 1,8757,486,486,486
BEGIN DESCRIPTION:
Cedar Creek 9.0
END DESCRIPTION:
XS GIS Cut Line= 3
      2546675.01     13797374.99      2545425.00     13798975.00
      2544774.99     13799775.01
#Sta/Elev= 30
  2969.7  353.93  3055.6  352.32  3119.8  346.92  3190.9  345.17  3553.5  329.86
  3988.1  325.70  4293.1  325.06  4350.0  326.19  4415.3  326.45  4537.5  325.37
  4916.0  326.46  4992.9  328.43  4996.9  324.50  5008.6  323.82  5009.1  323.32
  5018.9  323.82  5021.7  327.62  5026.8  328.17  5092.0  333.34  5128.7  326.30
  5175.2  324.12  5274.7  325.61  5320.5  329.72  5362.1  329.88  5418.8  324.42
  5590.6  324.17  5646.7  326.08  5770.7  330.00  5986.4  338.62  6030.9  339.86
#Mann=16,-1,0
  2969.7    0.07       0  3190.9    0.05       0  4293.1   0.035       0
  4350.0    0.05       0  4415.3   0.035       0  4537.5    0.05       0
  4916.0    0.16       0  5008.6    0.07       0  5018.9    0.16       0
  5026.8   0.063       0  5175.2    0.16       0  5274.7   0.063       0
  5418.8   0.035       0  5646.7    0.16       0  5770.7    0.07       0
  5986.4    0.05       0
Bank Sta=5008.6,5018.9
Exp/Cntr=0.3,0.1

Type RM Length L Ch R = 1,8271,467,467,467
BEGIN DESCRIPTION:
Cedar Creek 8.0
END DESCRIPTION:
XS GIS Cut Line= 3
      2546624.99     13797175.01      2544975.00     13798975.00
      2544575.01     13800174.98
#Sta/Elev= 30
  2557.8  360.19  2748.6  355.75  2805.4  350.88  2863.2  348.76  3018.1  341.13
  3393.0  329.04  3966.5  326.04  4009.0  325.37  4043.9  322.02  4044.4  321.52
  4058.0  322.02  4058.3  324.04  4093.5  325.14  4483.2  322.84  4880.8  325.26
  4964.2  326.30  5002.2  324.16  5020.7  326.53  5031.2  325.67  5062.9  333.31
  5073.4  332.94  5094.5  324.83  5105.0  324.00  5214.1  324.96  5273.7  330.88
  5347.5  325.35  5522.5  331.10  5625.2  335.14  5783.5  339.80  6264.5  350.87
#Mann=9,-1,0
  2557.8    0.07       0  2863.2    0.05       0  4043.9    0.07       0
  4058.0    0.05       0  4880.8    0.16       0  5214.1   0.035       0
  5522.5    0.16       0  5625.2    0.07       0  5783.5    0.05       0
Bank Sta=4043.9,4058
Exp/Cntr=0.3,0.1

Type RM Length L Ch R = 1,7804,451,451,451
BEGIN DESCRIPTION:
Cedar Creek 7.0
END DESCRIPTION:
XS GIS Cut Line= 3
      2546375.00     13797225.00      2544575.00     13798875.00
      2544375.01     13799574.96
#Sta/Elev= 30
  2562.9  352.00  2719.5  346.74  2916.5  340.62  3009.0  340.20  3150.2  332.47
  3242.1  330.57  3511.6  328.29  3539.6  326.65  3589.3  327.91  3794.6  324.65
  4339.4  322.41  4339.9  321.91  4353.5  322.41  4523.5  322.52  4707.2  325.73
  4848.6  324.55  5003.3  323.27  5133.4  324.41  5160.7  333.34  5166.1  333.52
  5172.4  333.42  5191.9  326.53  5201.0  325.45  5273.8  329.77  5318.4  329.40
  5368.7  331.69  5399.9  330.89  5441.5  336.36  5612.9  341.02  5732.7  342.98
#Mann=9,-1,0
  2562.9    0.07       0  2719.5    0.05       0  4339.4    0.07       0
  4353.5    0.05       0  4848.6    0.07       0  5003.3    0.16       0
  5166.1    0.07       0  5318.4   0.035       0  5612.9    0.05       0
Bank Sta=4339.4,4353.5
Exp/Cntr=0.3,0.1

Type RM Length L Ch R = 1,7353,475,475,475
BEGIN DESCRIPTION:
Cedar Creek 6.0
END DESCRIPTION:
XS GIS Cut Line= 3
      2545425.03     13796874.96      2544225.00     13798675.00
      2544025.00     13799475.00
#Sta/Elev= 30
  2836.6  345.40  2926.5  342.39  3601.3  326.07  3946.9  321.84  4091.1  322.41
  4206.8  319.69  4229.3  320.81  4249.3  318.94  4249.8  318.44  4263.4  318.94
  4292.4  321.61  4594.6  321.77  4642.6  322.18  4758.7  323.30  4776.1  324.03
  4791.2  321.22  4812.2  323.71  4990.9  322.35  5092.8  322.58  5175.3  324.06
  5319.5  327.19  5347.9  333.52  5360.7  334.01  5381.4  330.16  5494.7  333.94
  5522.7  331.18  5600.4  332.33  5636.5  338.27  5798.0  342.16  5824.6  342.85
#Mann=12,-1,0
  2836.6    0.07       0  2926.5    0.05       0  4249.3    0.07       0
  4263.4    0.05       0  4594.6    0.07       0  4642.6    0.16       0
  4758.7    0.05       0  4990.9    0.07       0  5092.8    0.05       0
  5175.3    0.07       0  5522.7   0.035       0  5798.0    0.05       0
Bank Sta=4249.3,4263.4
Exp/Cntr=0.3,0.1

Type RM Length L Ch R = 1,6878,468,468,468
BEGIN DESCRIPTION:
Cedar Creek 5.0
END DESCRIPTION:
XS GIS Cut Line= 3
      2545175.02     13796674.98      2543975.00     13798325.00
      2543875.00     13799425.02
#Sta/Elev= 30
  2955.2  351.57  2991.9  351.00  3004.4  348.88  3054.5  345.43  3190.5  341.13
  3820.8  324.72  4151.2  320.46  4472.5  319.59  4473.0  319.09  4486.6  319.59
  4625.3  321.38  5003.5  320.71  5015.5  319.81  5045.7  322.48  5065.7  320.33
  5236.4  321.93  5492.6  327.54  5608.0  329.78  5648.1  333.27  5658.2  331.65
  5688.3  333.83  5708.4  332.29  5718.4  334.57  5768.6  333.02  5798.7  336.04
  5828.9  335.66  5858.9  331.73  5919.2  330.96  5969.4  339.40  6100.0  342.06
#Mann=8,-1,0
  2955.2    0.07       0  3004.4    0.05       0  4472.5    0.07       0
  4486.6    0.05       0  4625.3    0.16       0  5003.5    0.05       0
  5492.6    0.07       0  5858.9   0.035       0
Bank Sta=4472.5,4486.6
Exp/Cntr=0.3,0.1

Type RM Length L Ch R = 1,6410,377,377,377
BEGIN DESCRIPTION:
Cedar Creek 4.0
END DESCRIPTION:
XS GIS Cut Line= 3
      2544053.24     13796546.45      2543575.00     13798325.00
      2543775.01     13799425.04
#Sta/Elev= 30
  3153.8  338.13  3579.4  328.23  3780.6  322.95  3912.6  322.00  4249.9  318.87
  4270.7  316.84  4272.4  315.02  4272.9  314.52  4286.6  315.02  4312.1  318.74
  4467.4  318.23  4488.1  316.53  4529.5  318.41  5007.1  319.96  5022.3  317.95
  5027.3  320.50  5168.3  320.10  5471.7  326.13  5595.2  328.69  5639.7  333.40
  5656.2  331.23  5698.1  333.22  5707.0  331.48  5717.2  333.94  5778.1  333.15
  5818.8  335.31  5871.9  330.82  5930.6  329.75  5981.4  339.21  6113.6  342.02
#Mann=9,-1,0
  3153.8    0.07       0  3579.4    0.16       0  3912.6    0.05       0
  4272.4    0.05       0  4286.6    0.05       0  5007.1    0.16       0
  5022.3    0.05       0  5471.7    0.07       0  5871.9   0.035       0
Bank Sta=4272.4,4286.6
Exp/Cntr=0.3,0.1

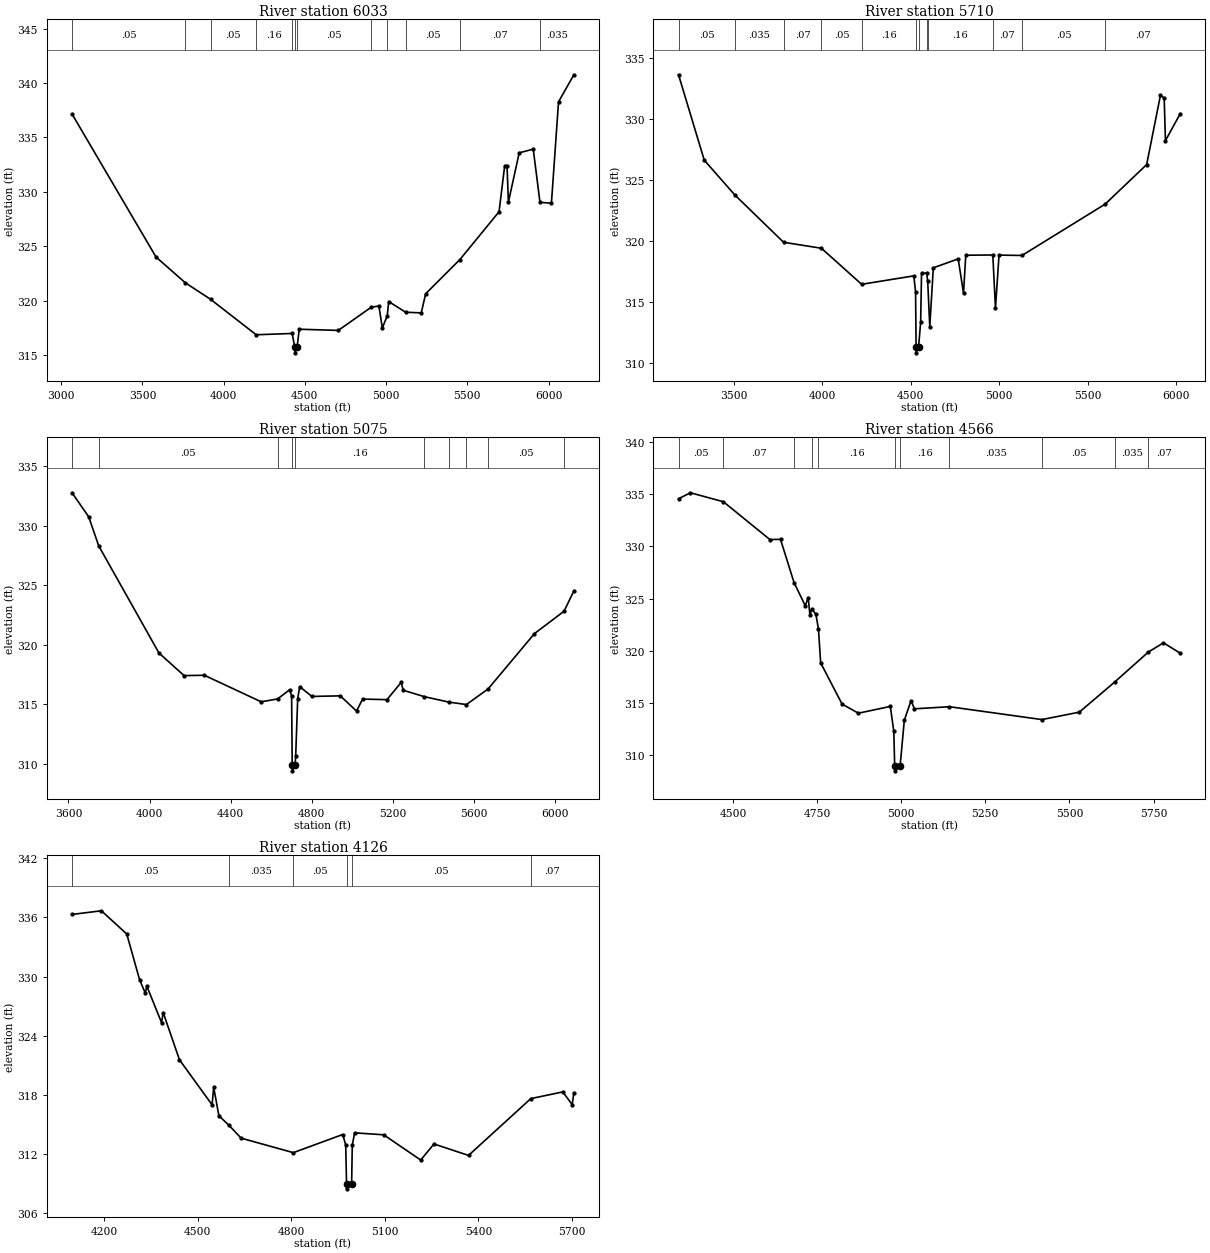
Type RM Length L Ch R = 1,6033,323,323,323
BEGIN DESCRIPTION:
Cedar Creek 3.0
END DESCRIPTION:
XS GIS Cut Line= 3
      2543396.79     13796409.04      2543274.66     13798584.51
      2543725.02     13799375.03
#Sta/Elev= 30
  3067.2  337.14  3584.0  324.01  3763.9  321.65  3919.4  320.13  4200.4  316.87
  4421.9  316.99  4438.2  315.71  4438.7  315.21  4452.4  315.71  4465.4  317.38
  4705.7  317.27  4908.7  319.40  4956.1  319.51  4976.8  317.49  5007.1  318.61
  5016.2  319.92  5120.5  318.94  5216.5  318.88  5243.8  320.64  5454.5  323.78
  5695.5  328.17  5730.0  332.39  5744.5  332.40  5753.0  329.06  5819.4  333.58
  5905.9  333.92  5947.3  329.04  6017.8  328.95  6061.5  338.26  6155.9  340.75
#Mann=12,-1,0
  3067.2    0.05       0  3763.9    0.07       0  3919.4    0.05       0
  4200.4    0.16       0  4421.9    0.05       0  4438.2    0.07       0
  4452.4    0.05       0  4908.7    0.16       0  5007.1    0.07       0
  5120.5    0.05       0  5454.5    0.07       0  5947.3   0.035       0
Bank Sta=4438.2,4452.4
Exp/Cntr=0.3,0.1

Type RM Length L Ch R = 1,5710,635,635,635
BEGIN DESCRIPTION:
X18421
END DESCRIPTION:
XS GIS Cut Line= 3
      2543160.16     13796470.14      2542992.23     13798553.98
      2543518.61     13799080.35
#Sta/Elev= 30
  3188.9  333.63  3334.2  326.64  3505.8  323.81  3782.3  319.92  3996.2  319.43
  4223.4  316.48  4518.1  317.17  4528.1  315.87  4531.0  311.37  4531.5  310.87
  4545.2  311.37  4556.8  313.38  4561.8  317.38  4591.0  317.40  4596.7  316.71
  4608.3  313.02  4628.4  317.83  4768.9  318.56  4799.0  315.75  4811.7  318.86
  4964.4  318.88  4979.5  314.53  4999.6  318.87  5129.4  318.84  5599.0  323.04
  5833.7  326.28  5911.5  331.95  5932.7  331.73  5939.8  328.24  6023.9  330.46
#Mann=12,-1,0
  3188.9    0.05       0  3505.8   0.035       0  3782.3    0.07       0
  3996.2    0.05       0  4223.4    0.16       0  4531.0    0.07       0
  4545.2    0.16       0  4591.0    0.05       0  4596.7    0.16       0
  4964.4    0.07       0  5129.4    0.05       0  5599.0    0.07       0
Bank Sta=4531,4545.2
Exp/Cntr=0.3,0.1

Type RM Length L Ch R = 1,5075,509,509,509
BEGIN DESCRIPTION:
X18422
END DESCRIPTION:
XS GIS Cut Line= 2
      2542679.28     13796493.00      2542625.85     13798966.12
#Sta/Elev= 30
  3618.1  332.76  3700.1  330.74  3749.7  328.29  4046.4  319.30  4170.2  317.40
  4270.3  317.43  4550.3  315.20  4631.3  315.44  4690.4  316.21  4700.4  315.70
  4703.3  309.90  4703.8  309.40  4717.5  309.90  4720.4  310.61  4730.4  315.47
  4740.4  316.47  4800.4  315.65  4940.4  315.70  5020.4  314.42  5050.4  315.43
  5170.5  315.38  5240.5  316.83  5250.5  316.17  5354.9  315.63  5476.7  315.17
  5562.0  314.97  5669.0  316.28  5897.6  320.93  6043.5  322.81  6091.8  324.51
#Mann=10,-1,0
  3618.1    0.07       0  3749.7    0.05       0  4631.3    0.16       0
  4703.3    0.07       0  4717.5    0.16       0  5354.9    0.07       0
  5476.7    0.05       0  5562.0    0.07       0  5669.0    0.05       0
  6043.5   0.035       0
Bank Sta=4703.3,4717.5
Exp/Cntr=0.3,0.1

Type RM Length L Ch R = 1,4566,440,440,440
BEGIN DESCRIPTION:
Cedar Creek 2.0
END DESCRIPTION:
XS GIS Cut Line= 3
      2542068.63     13797447.19      2542275.00     13798075.00
      2542282.35     13798905.11
#Sta/Elev= 30
  4338.5  334.56  4374.0  335.13  4471.9  334.27  4609.9  330.65  4641.5  330.67
  4681.7  326.53  4715.1  324.31  4723.8  325.10  4729.0  323.38  4734.2  324.01
  4746.7  323.49  4754.3  322.08  4760.8  318.84  4824.5  314.89  4873.0  314.02
  4967.8  314.67  4978.2  312.27  4980.7  309.00  4981.2  308.50  4997.0  309.00
  5009.4  313.35  5029.4  315.22  5039.4  314.44  5143.5  314.64  5418.0  313.41
  5529.4  314.12  5635.7  317.04  5734.2  319.87  5779.4  320.76  5829.5  319.76
#Mann=11,-1,0
  4338.5    0.05       0  4471.9    0.07       0  4681.7    0.05       0
  4734.2    0.07       0  4754.3    0.16       0  4980.7    0.07       0
  4997.0    0.16       0  5143.5   0.035       0  5418.0    0.05       0
  5635.7   0.035       0  5734.2    0.07       0
Bank Sta=4980.7,4997
Exp/Cntr=0.3,0.1

Type RM Length L Ch R = 1,4126,544,544,544
BEGIN DESCRIPTION:
Cedar Creek 1.0
END DESCRIPTION:
XS GIS Cut Line= 3
      2541755.66     13797332.64      2541925.00     13798225.00
      2542007.54     13798920.23
#Sta/Elev= 30
  4097.3  336.30  4191.3  336.67  4272.7  334.31  4313.5  329.70  4331.9  328.32
  4337.0  329.02  4384.2  325.32  4389.3  326.35  4441.5  321.56  4546.1  316.99
  4551.2  318.77  4567.9  315.88  4600.1  314.92  4639.2  313.61  4806.4  312.14
  4964.9  313.98  4974.4  312.92  4977.1  308.97  4977.6  308.47  4993.4  308.97
  4995.4  312.88  5003.0  314.15  5096.2  313.95  5214.8  311.39  5257.3  313.02
  5368.1  311.86  5567.7  317.62  5670.2  318.30  5700.4  317.01  5705.7  318.22
#Mann=6,-1,0
  4097.3    0.05       0  4600.1   0.035       0  4806.4    0.05       0
  4977.1    0.05       0  4993.4    0.05       0  5567.7    0.07       0
Bank Sta=4977.1,4993.4
Exp/Cntr=0.3,0.1