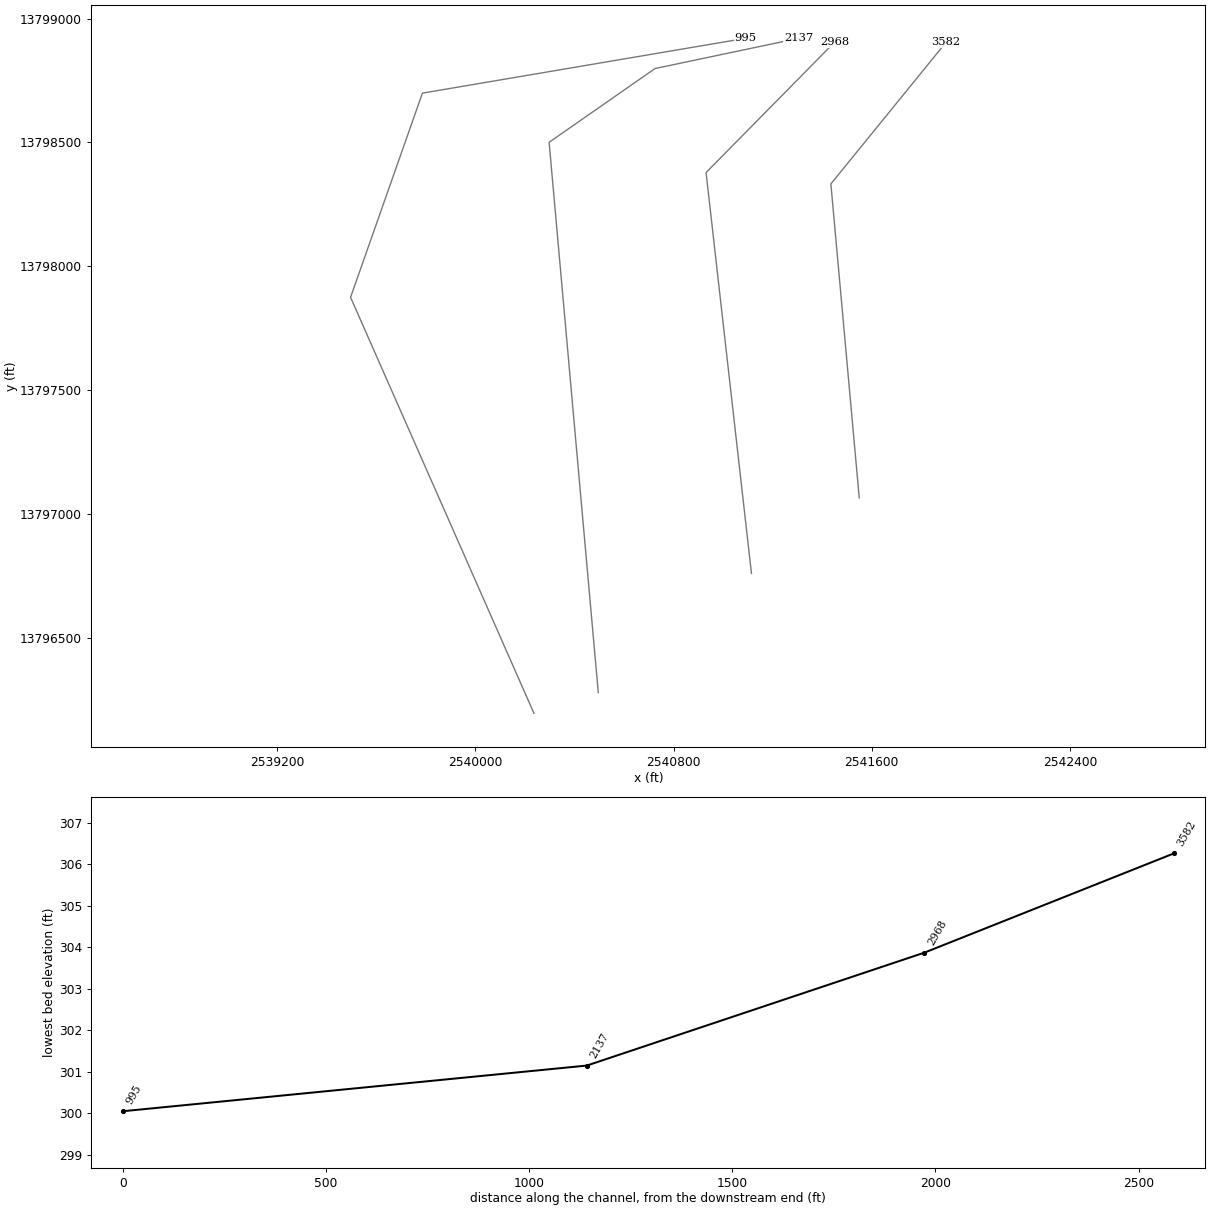
HEC-RAS study Cedar Creek.prj: Cedar Creek Base Level Engineering

--- Cedar Creek.g01 (geometry) --- (continued)

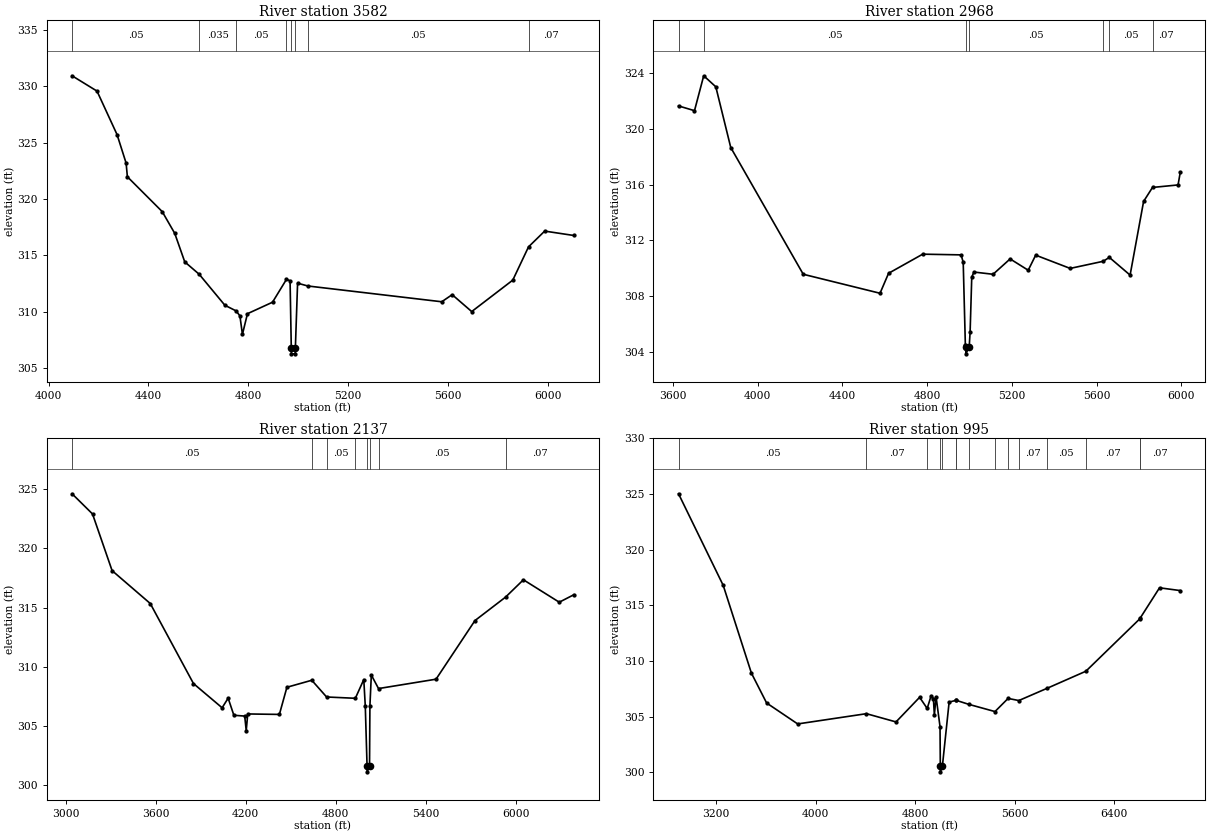
Type RM Length L Ch R = 1,3582,614,614,614
BEGIN DESCRIPTION:
X18420
END DESCRIPTION:
XS GIS Cut Line= 3
      2541549.58     13797065.48      2541435.08     13798332.62
      2541900.36     13798904.69
#Sta/Elev= 30
  4094.0  330.93  4193.9  329.57  4274.2  325.71  4310.5  323.18  4315.5  321.97
  4455.0  318.88  4505.2  316.95  4545.3  314.42  4603.1  313.32  4706.0  310.57
  4750.9  310.07  4766.2  309.63  4776.3  307.99  4796.4  309.82  4896.8  310.84
  4952.7  312.87  4967.1  312.74  4972.0  306.76  4972.5  306.26  4987.8  306.26
  4988.3  306.76  4997.2  312.53  5038.1  312.28  5574.6  310.88  5616.3  311.51
  5694.6  310.01  5859.1  312.80  5922.1  315.75  5986.9  317.15  6103.7  316.76
#Mann=8,-1,0
  4094.0    0.05       0  4603.1   0.035       0  4750.9    0.05       0
  4952.7    0.07       0  4972.0    0.07       0  4988.3    0.07       0
  5038.1    0.05       0  5922.1    0.07       0
Bank Sta=4972,4988.3
Exp/Cntr=0.3,0.1

Type RM Length L Ch R = 1,2968,831,831,831
BEGIN DESCRIPTION:
X18419
END DESCRIPTION:
XS GIS Cut Line= 3
      2541114.49     13796760.21      2540931.29     13798378.42
      2541450.19     13798904.95
#Sta/Elev= 30
  3627.2  321.63  3702.5  321.29  3746.0  323.79  3803.1  323.00  3873.6  318.65
  4215.7  309.57  4578.0  308.21  4618.3  309.64  4779.3  311.01  4960.5  310.96
  4970.5  310.43  4980.6  304.52  4982.5  304.37  4983.0  303.87  4998.8  304.37
  5003.1  305.45  5010.8  309.36  5020.8  309.73  5111.4  309.57  5191.9  310.67
  5277.2  309.86  5312.5  310.94  5475.2  309.99  5631.1  310.50  5660.0  310.78
  5758.0  309.51  5821.7  314.79  5863.7  315.79  5984.3  315.97  5995.0  316.90
#Mann=7,-1,0
  3627.2   0.035       0  3746.0    0.05       0  4982.5    0.05       0
  4998.8    0.05       0  5631.1    0.07       0  5660.0    0.05       0
  5863.7    0.07       0
Bank Sta=4982.5,4998.8
Exp/Cntr=0.3,0.1

Type RM Length L Ch R = 1,2137,1142,1142,1142
BEGIN DESCRIPTION:
X18418
END DESCRIPTION:
XS GIS Cut Line= 4
      2540496.20     13796279.36      2540297.74     13798500.55
      2540725.20     13798798.24      2541304.46     13798920.19
#Sta/Elev= 30
  3043.0  324.59  3179.2  322.89  3309.7  318.11  3563.9  315.34  3851.9  308.59
  4042.6  306.55  4082.8  307.36  4120.9  305.92  4193.2  305.85  4203.2  304.62
  4213.3  306.03  4424.1  305.99  4474.3  308.28  4640.0  308.87  4738.6  307.46
  4930.2  307.35  4986.4  308.93  4996.4  306.69  5008.2  301.65  5008.7  301.15
  5024.7  301.65  5027.2  306.69  5036.6  309.31  5084.6  308.17  5467.7  308.96
  5726.9  313.90  5931.0  315.88  6049.8  317.34  6288.6  315.45  6385.9  316.08
#Mann=8,-1,0
  3043.0    0.05       0  4640.0   0.035       0  4738.6    0.05       0
  4930.2    0.16       0  5008.2    0.07       0  5024.7    0.16       0
  5084.6    0.05       0  5931.0    0.07       0
Bank Sta=5008.2,5024.7
Exp/Cntr=0.3,0.1

Type RM Length L Ch R = 1,995,0,0,0
BEGIN DESCRIPTION:
X18417
END DESCRIPTION:
XS GIS Cut Line= 4
      2540236.69     13796195.32      2539496.26     13797874.63
      2539786.32     13798699.01      2541089.70     13798920.05
#Sta/Elev= 30
  2899.2  325.01  3258.4  316.78  3484.7  308.91  3606.8  306.23  3856.4  304.35
  4408.5  305.27  4646.4  304.53  4835.9  306.74  4896.8  305.74  4928.8  306.89
  4946.9  306.61  4954.4  305.15  4968.1  306.79  4999.9  304.11  5002.3  300.55
  5002.8  300.05  5018.8  300.55  5073.0  306.31  5125.5  306.46  5126.7  306.48
  5230.7  306.11  5441.4  305.46  5546.8  306.64  5633.0  306.45  5858.3  307.54
  6171.4  309.08  6604.4  313.78  6606.2  313.82  6763.3  316.57  6930.4  316.32
#Mann=15,-1,0
  2899.2    0.05       0  4408.5    0.07       0  4896.8    0.12       0
  5002.3    0.07       0  5018.8    0.12       0  5125.5    0.05       0
  5126.7    0.07       0  5230.7    0.05       0  5441.4    0.07       0
  5546.8    0.12       0  5633.0    0.07       0  5858.3    0.05       0
  6171.4    0.07       0  6604.4    0.05       0  6606.2    0.07       0
Bank Sta=5002.3,5018.8
Exp/Cntr=0.3,0.1

Chan Stop Cuts=-1