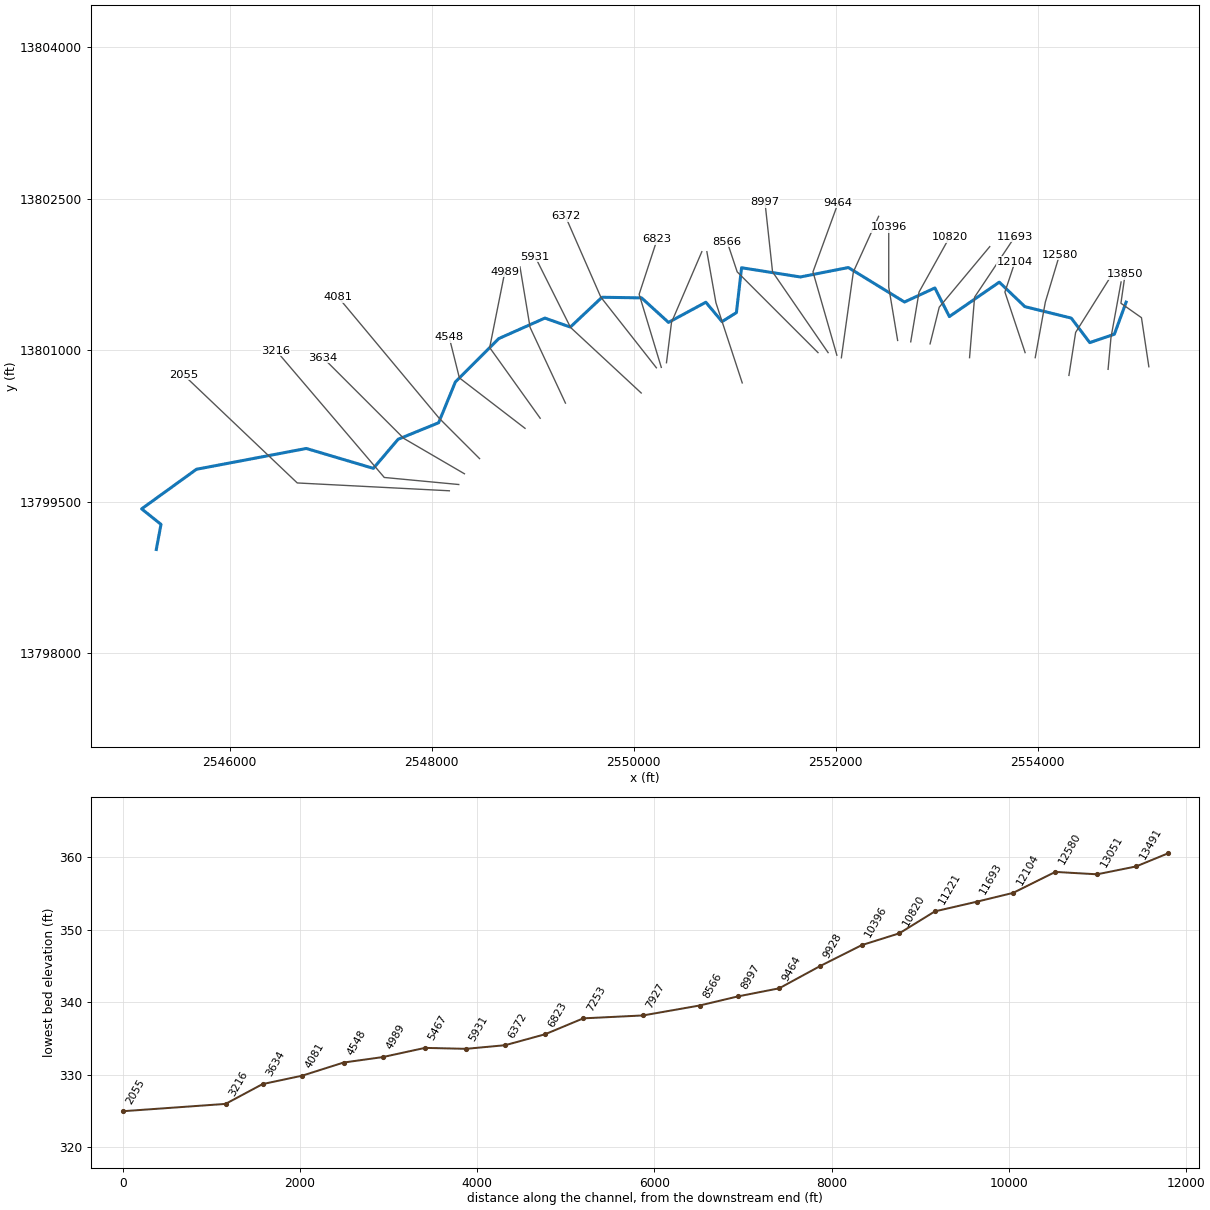
--- Cedar Spring Branch.prj (project) ---

Proj Title=Cedar Spring Branch Base Level Engineering
Current Plan=p01
Default Exp/Contr=0.3,0.1
English Units
Geom File=g01
Flow File=f01
Plan File=p01
BEGIN DESCRIPTION:
Cedar Spring Branch
END DESCRIPTION:

--- Cedar Spring Branch.p01 (plan) ---

Plan Title=Multiple Run
Short Identifier=Multiple
Geom File=g01
Flow File=f01
Subcritical Flow
K Sum by GR= 0
Std Step Tol= 0.01
Critical Tol= 0.01
Num of Std Step Trials= 20
Max Error Tol= 0.3
Flow Tol Ratio= 0.001
Split Flow NTrial= 30
Split Flow Tol= 0.02
Split Flow Ratio= 0.02
Log Output Level= 0
Friction Slope Method= 1
Unsteady Friction Slope Method= 2
Unsteady Bridges Friction Slope Method= 1
Parabolic Critical Depth
Global Vel Dist=  1 , 1 , 1
Global Log Level= 0
CheckData=True
Encroach Param= -1, 0, 0, 0
BEGIN DESCRIPTION:
Multiple Run
END DESCRIPTION:

--- Cedar Spring Branch.f01 (steady flow) ---

Flow Title=Multiple
Number of Profiles=7
Profile Names=10-year,25-year,50-year,1pct_min,100-year,1pct_plu,500-year
River Rch & RM= Cedar Spring Bra,Reach-1,13850
     718    1149    1536     995    1984    3959    3276
River Rch & RM= Cedar Spring Bra,Reach-1,8997
    1038    1685    2274    1483    2959    5904    4958
Boundary for River Rch & Prof#=Cedar Spring Bra,Reach-1,1
Up Type=0
Dn Type=3
Dn Slope=0.005
Boundary for River Rch & Prof#=Cedar Spring Bra,Reach-1,2
Up Type=0
Dn Type=3
Dn Slope=0.005
Boundary for River Rch & Prof#=Cedar Spring Bra,Reach-1,3
Up Type=0
Dn Type=3
Dn Slope=0.005
Boundary for River Rch & Prof#=Cedar Spring Bra,Reach-1,4
Up Type=0
Dn Type=3
Dn Slope=0.005
Boundary for River Rch & Prof#=Cedar Spring Bra,Reach-1,5
Up Type=0
Dn Type=3
Dn Slope=0.005
Boundary for River Rch & Prof#=Cedar Spring Bra,Reach-1,6
Up Type=0
Dn Type=3
Dn Slope=0.005
Boundary for River Rch & Prof#=Cedar Spring Bra,Reach-1,7
Up Type=0
Dn Type=3
Dn Slope=0.005

--- Cedar Spring Branch.g01 (geometry) ---

Geom Title=Existing Conditions

River Reach=Cedar Spring Bra,Reach-1
Reach XY= 30
      2554875.00     13801475.00      2554758.54     13801157.39
      2554514.93     13801074.16      2554331.50     13801317.27
      2553872.58     13801430.41      2553619.29     13801673.12
      2553124.99     13801332.07      2552982.00     13801615.85
      2552680.87     13801476.50      2552125.01     13801817.91
      2551649.96     13801724.51      2551068.31     13801815.72
      2551017.31     13801371.33      2550874.90     13801282.28
      2550714.67     13801474.13      2550345.06     13801274.49
      2550078.33     13801517.38      2549686.88     13801523.47
      2549373.37     13801228.13      2549121.59     13801317.19
      2548665.30     13801114.23      2548235.63     13800685.00
      2548069.74     13800280.47      2547668.94     13800116.86
      2547423.55     13799828.53      2546759.81     13800025.53
      2545672.57     13799819.48      2545130.06     13799427.24
      2545321.47     13799273.56      2545275.00     13799025.00

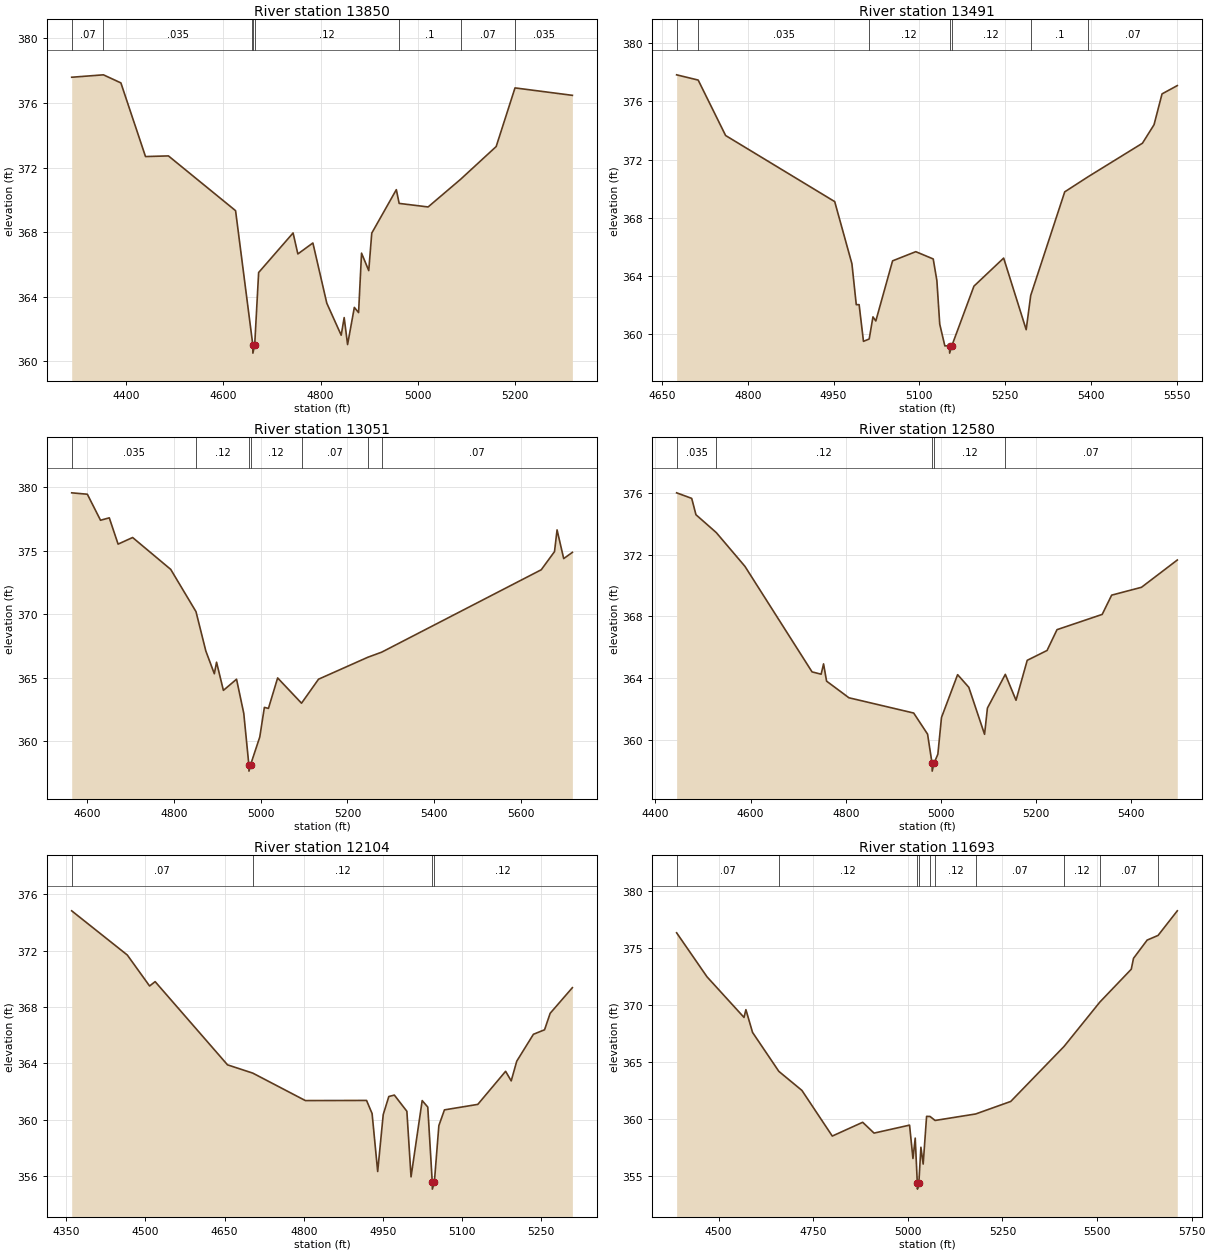
Type RM Length L Ch R = 1,13850,359,359,359
BEGIN DESCRIPTION:
X18425
END DESCRIPTION:
XS GIS Cut Line= 4
      2555099.79     13800835.03      2555026.71     13801321.18
      2554823.37     13801464.15      2554864.66     13801750.00
#Sta/Elev= 30
  4288.3  377.59  4353.5  377.74  4389.4  377.24  4440.0  372.68  4487.1  372.72
  4625.1  369.33  4659.3  361.31  4660.4  361.01  4660.7  360.51  4664.4  361.01
  4672.5  365.50  4743.3  367.95  4753.1  366.65  4784.0  367.33  4812.6  363.60
  4842.2  361.62  4848.3  362.71  4855.3  361.04  4869.2  363.34  4877.9  363.02
  4884.0  366.70  4898.8  365.62  4905.0  367.94  4955.5  370.63  4961.3  369.78
  5020.8  369.56  5087.5  371.27  5160.7  373.30  5199.4  376.93  5317.3  376.47
#Mann=8,-1,0
  4288.3    0.07       0  4353.5   0.035       0  4659.3    0.12       0
  4660.4    0.05       0  4664.4    0.12       0  4961.3     0.1       0
  5087.5    0.07       0  5199.4   0.035       0
Bank Sta=4660.4,4664.4
Exp/Cntr=0.3,0.1

Type RM Length L Ch R = 1,13491,440,440,440
BEGIN DESCRIPTION:
Cedar Spring Branch 21.0
END DESCRIPTION:
XS GIS Cut Line= 3
      2554696.29     13800809.63      2554725.00     13801125.00
      2554825.00     13801675.01
#Sta/Elev= 30
  4675.6  377.83  4713.3  377.47  4761.3  373.66  4952.1  369.12  4982.2  364.85
  4989.8  362.04  4994.8  362.04  5002.4  359.52  5012.4  359.68  5019.0  361.20
  5024.0  360.92  5053.3  365.05  5093.9  365.68  5124.4  365.18  5130.8  363.69
  5135.8  360.70  5144.7  359.21  5152.9  359.21  5153.1  358.71  5156.9  359.21
  5195.6  363.31  5247.6  365.24  5287.0  360.32  5294.9  362.67  5354.4  369.79
  5395.4  370.83  5490.3  373.13  5510.6  374.40  5524.6  376.52  5551.3  377.09
#Mann=7,-1,0
  4675.6    0.07       0  4713.3   0.035       0  5012.4    0.12       0
  5152.9   0.035       0  5156.9    0.12       0  5294.9     0.1       0
  5395.4    0.07       0
Bank Sta=5152.9,5156.9
Exp/Cntr=0.3,0.1

Type RM Length L Ch R = 1,13051,471,471,471
BEGIN DESCRIPTION:
Cedar Spring Branch 20.0
END DESCRIPTION:
XS GIS Cut Line= 3
      2554308.68     13800749.29      2554375.00     13801175.00
      2554759.82     13801788.20
#Sta/Elev= 30
  4564.1  379.55  4600.2  379.44  4630.6  377.39  4650.8  377.58  4671.1  375.51
  4704.6  376.03  4792.5  373.52  4850.8  370.19  4873.5  367.09  4893.1  365.30
  4898.2  366.21  4914.0  363.99  4944.3  364.87  4961.0  362.18  4972.7  358.13
  4973.0  357.63  4976.7  358.13  4997.9  360.32  5008.5  362.65  5017.9  362.57
  5039.1  364.97  5094.2  362.98  5133.4  364.87  5247.2  366.60  5279.1  367.00
  5647.1  373.49  5677.7  374.92  5683.6  376.63  5698.9  374.37  5718.9  374.86
#Mann=7,-1,0
  4564.1   0.035       0  4850.8    0.12       0  4972.7    0.05       0
  4976.7    0.12       0  5094.2    0.07       0  5247.2     0.1       0
  5279.1    0.07       0
Bank Sta=4972.7,4976.7
Exp/Cntr=0.3,0.1

Type RM Length L Ch R = 1,12580,476,476,476
BEGIN DESCRIPTION:
Cedar Spring Branch 19.0
END DESCRIPTION:
XS GIS Cut Line= 3
      2553975.01     13800925.04      2554075.00     13801475.00
      2554216.54     13801947.06
#Sta/Elev= 30
  4444.7  376.02  4476.4  375.66  4485.3  374.60  4528.0  373.44  4588.2  371.25
  4729.2  364.40  4748.3  364.25  4753.4  364.92  4759.7  363.80  4806.7  362.72
  4942.7  361.73  4971.9  360.36  4981.3  358.46  4981.6  357.96  4985.3  358.46
  4993.5  359.06  5001.1  361.44  5035.0  364.22  5058.5  363.40  5091.6  360.35
  5097.6  362.05  5135.2  364.24  5157.7  362.56  5181.2  365.15  5222.9  365.79
  5243.8  367.14  5338.7  368.13  5358.6  369.38  5421.3  369.89  5496.5  371.66
#Mann=5,-1,0
  4444.7   0.035       0  4528.0    0.12       0  4981.3    0.05       0
  4985.3    0.12       0  5135.2    0.07       0
Bank Sta=4981.3,4985.3
Exp/Cntr=0.3,0.1

Type RM Length L Ch R = 1,12104,411,411,411
BEGIN DESCRIPTION:
Cedar Spring Branch 18.0
END DESCRIPTION:
XS GIS Cut Line= 3
      2553875.01     13800974.97      2553675.00     13801575.00
      2553775.00     13801874.99
#Sta/Elev= 30
  4360.3  374.84  4465.7  371.70  4507.9  369.50  4518.4  369.81  4655.5  363.90
  4703.5  363.31  4803.1  361.36  4919.0  361.37  4929.5  360.44  4940.1  356.32
  4950.6  360.37  4961.2  361.65  4971.7  361.75  4995.4  360.60  5003.3  355.94
  5024.4  361.36  5035.0  360.90  5043.5  355.57  5043.7  355.07  5047.5  355.57
  5056.0  359.58  5066.6  360.70  5129.8  361.09  5182.5  363.44  5193.1  362.76
  5203.6  364.16  5235.2  366.07  5256.3  366.39  5266.9  367.56  5309.0  369.38
#Mann=4,-1,0
  4360.3    0.07       0  4703.5    0.12       0  5043.5    0.05       0
  5047.5    0.12       0
Bank Sta=5043.5,5047.5
Exp/Cntr=0.3,0.1

Type RM Length L Ch R = 1,11693,472,472,472
BEGIN DESCRIPTION:
Cedar Spring Branch 17.0
END DESCRIPTION:
XS GIS Cut Line= 3
      2553325.00     13800925.03      2553375.00     13801525.00
      2553775.02     13802125.03
#Sta/Elev= 30
  4388.9  376.36  4469.1  372.50  4567.0  368.93  4572.0  369.61  4589.6  367.61
  4659.1  364.19  4720.0  362.52  4800.3  358.51  4880.6  359.72  4910.7  358.77
  5004.5  359.47  5013.5  356.54  5019.5  358.33  5025.0  354.35  5025.3  353.85
  5029.0  354.35  5034.5  357.53  5040.5  356.05  5049.5  360.24  5058.7  360.23
  5072.0  359.88  5179.2  360.45  5271.9  361.55  5412.8  366.38  5507.5  370.28
  5590.4  373.16  5596.4  374.12  5632.4  375.72  5661.3  376.13  5712.1  378.29
#Mann=10,-1,0
  4388.9    0.07       0  4659.1    0.12       0  5025.0    0.05       0
  5029.0    0.12       0  5058.7    0.07       0  5072.0    0.12       0
  5179.2    0.07       0  5412.8    0.12       0  5507.5    0.07       0
  5661.3    0.12       0
Bank Sta=5025,5029
Exp/Cntr=0.3,0.1

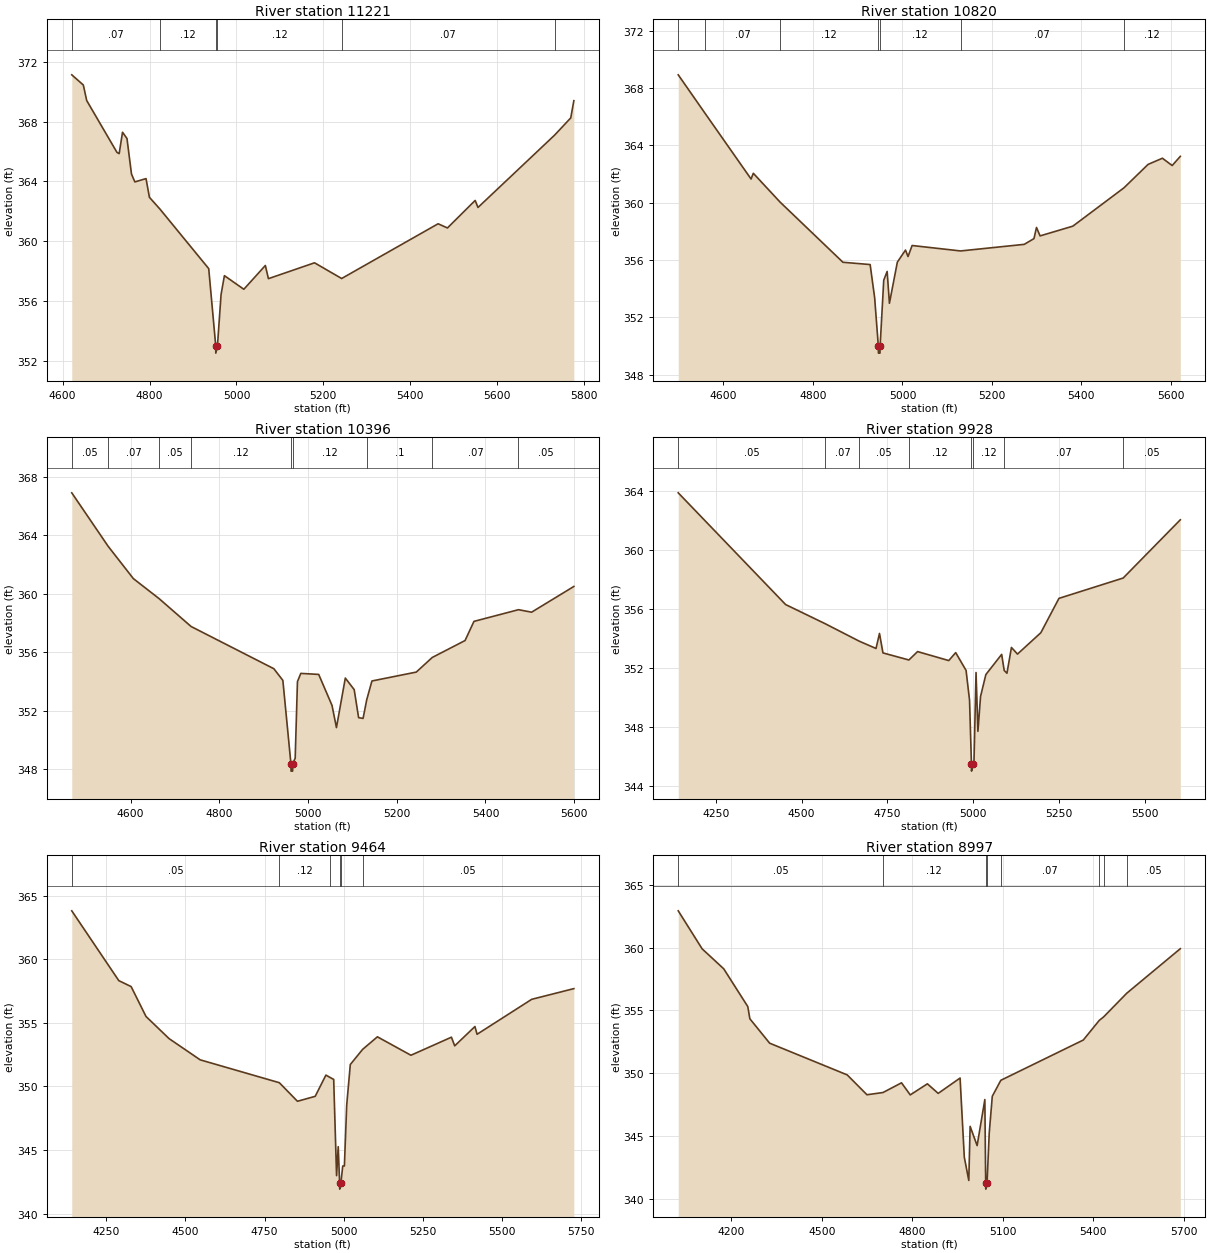
Type RM Length L Ch R = 1,11221,401,401,401
BEGIN DESCRIPTION:
Cedar Spring Branch 16.0
END DESCRIPTION:
XS GIS Cut Line= 4
      2552934.17     13801061.67      2552975.00     13801225.00
      2553025.00     13801425.00      2553524.97     13802024.97
#Sta/Elev= 30
  4621.0  371.13  4647.6  370.45  4655.4  369.41  4724.9  365.95  4730.1  365.86
  4737.8  367.29  4748.1  366.87  4758.4  364.50  4766.2  363.97  4791.9  364.19
  4799.7  362.94  4824.0  362.15  4936.2  358.17  4952.3  353.02  4952.5  352.52
  4956.3  353.02  4964.6  356.44  4972.3  357.70  5017.0  356.79  5066.5  358.38
  5073.6  357.50  5179.7  358.56  5242.1  357.51  5464.1  361.17  5485.6  360.89
  5549.4  362.73  5555.9  362.26  5732.3  367.10  5769.4  368.25  5776.5  369.40
#Mann=6,-1,0
  4621.0    0.07       0  4824.0    0.12       0  4952.3    0.05       0
  4956.3    0.12       0  5242.1    0.07       0  5732.3    0.12       0
Bank Sta=4952.3,4956.3
Exp/Cntr=0.3,0.1

Type RM Length L Ch R = 1,10820,424,424,424
BEGIN DESCRIPTION:
Cedar Spring Branch 15.0
END DESCRIPTION:
XS GIS Cut Line= 5
      2552742.83     13801081.95      2552775.00     13801275.00
      2552825.00     13801575.00      2553075.00     13802025.00
      2553127.19     13802118.95
#Sta/Elev= 30
  4498.9  368.92  4559.4  366.21  4661.7  361.65  4666.7  362.05  4726.5  360.04
  4867.0  355.84  4927.8  355.68  4937.9  353.36  4946.1  350.00  4946.3  349.50
  4949.8  349.50  4950.1  350.00  4958.2  354.59  4965.8  355.20  4970.9  352.98
  4988.6  355.85  5006.8  356.69  5012.5  356.24  5021.6  357.01  5129.9  356.63
  5272.2  357.09  5293.9  357.49  5299.6  358.27  5307.6  357.68  5380.8  358.36
  5494.9  361.03  5549.0  362.67  5581.0  363.10  5602.8  362.59  5621.0  363.23
#Mann=7,-1,0
  4498.9    0.05       0  4559.4    0.07       0  4726.5    0.12       0
  4946.1    0.05       0  4950.1    0.12       0  5129.9    0.07       0
  5494.9    0.12       0
Bank Sta=4946.1,4950.1
Exp/Cntr=0.3,0.1

Type RM Length L Ch R = 1,10396,468,468,468
BEGIN DESCRIPTION:
Cedar Spring Branch 14.0
END DESCRIPTION:
XS GIS Cut Line= 5
      2552613.23     13801095.62      2552575.00     13801325.00
      2552525.00     13801625.00      2552525.00     13802075.00
      2552525.00     13802220.22
#Sta/Elev= 30
  4467.3  366.92  4549.1  363.27  4606.1  361.05  4664.1  359.68  4736.3  357.77
  4922.9  354.88  4943.2  354.08  4961.4  348.37  4961.7  347.87  4965.2  347.87
  4965.4  348.37  4971.0  348.76  4976.1  354.00  4983.7  354.56  5024.0  354.49
  5054.0  352.37  5064.0  350.85  5084.0  354.24  5104.0  353.45  5114.0  351.53
  5124.0  351.48  5132.4  352.77  5144.0  354.04  5244.0  354.65  5280.0  355.65
  5354.0  356.81  5374.0  358.12  5474.4  358.92  5504.0  358.75  5599.2  360.51
#Mann=9,-1,0
  4467.3    0.05       0  4549.1    0.07       0  4664.1    0.05       0
  4736.3    0.12       0  4961.4    0.05       0  4965.4    0.12       0
  5132.4     0.1       0  5280.0    0.07       0  5474.4    0.05       0
Bank Sta=4961.4,4965.4
Exp/Cntr=0.3,0.1

Type RM Length L Ch R = 1,9928,464,464,464
BEGIN DESCRIPTION:
Cedar Spring Branch 13.0
END DESCRIPTION:
XS GIS Cut Line= 3
      2552056.11     13800924.06      2552175.00     13801775.00
      2552425.02     13802325.04
#Sta/Elev= 30
  4140.2  363.88  4453.2  356.30  4568.6  355.00  4668.3  353.81  4716.7  353.32
  4726.8  354.34  4736.9  353.02  4812.5  352.54  4837.8  353.11  4928.7  352.50
  4948.9  353.04  4979.2  351.83  4989.3  349.81  4994.8  345.50  4995.1  345.00
  4998.9  345.50  5002.1  345.50  5008.2  351.69  5013.7  347.70  5021.4  350.07
  5036.8  351.55  5082.9  352.92  5090.3  351.83  5098.3  351.64  5111.4  353.39
  5129.0  352.94  5197.1  354.39  5249.9  356.72  5437.1  358.10  5603.6  362.05
#Mann=8,-1,0
  4140.2    0.05       0  4568.6    0.07       0  4668.3    0.05       0
  4812.5    0.12       0  4994.8    0.05       0  4998.9    0.12       0
  5090.3    0.07       0  5437.1    0.05       0
Bank Sta=4994.8,4998.9
Exp/Cntr=0.3,0.1

Type RM Length L Ch R = 1,9464,467,467,467
BEGIN DESCRIPTION:
Cedar Spring Branch 12.0
END DESCRIPTION:
XS GIS Cut Line= 3
      2552011.62     13800949.46      2551775.00     13801775.00
      2552024.33     13802458.57
#Sta/Elev= 30
  4140.8  363.81  4289.4  358.32  4328.4  357.85  4375.4  355.50  4448.2  353.76
  4546.5  352.09  4796.7  350.29  4853.9  348.83  4910.0  349.22  4943.8  350.89
  4955.7  350.72  4968.4  350.55  4977.5  342.98  4982.7  345.26  4987.1  342.42
  4987.4  341.92  4991.2  342.42  4997.0  343.74  5002.2  343.74  5009.5  348.52
  5020.9  351.72  5059.7  352.91  5106.5  353.90  5212.5  352.45  5340.4  353.87
  5350.8  353.19  5414.7  354.71  5421.4  354.10  5594.1  356.85  5727.2  357.69
#Mann=6,-1,0
  4140.8    0.05       0  4796.7    0.12       0  4955.7    0.07       0
  4987.1    0.05       0  4991.2    0.07       0  5059.7    0.05       0
Bank Sta=4987.1,4991.2
Exp/Cntr=0.3,0.1

Type RM Length L Ch R = 1,8997,431,431,431
BEGIN DESCRIPTION:
Cedar Spring Branch 11.0
END DESCRIPTION:
XS GIS Cut Line= 3
      2551925.02     13800974.97      2551375.00     13801775.00
      2551299.97     13802464.77
#Sta/Elev= 30
  4024.3  362.92  4103.5  359.90  4175.2  358.31  4254.9  355.31  4261.8  354.34
  4327.4  352.40  4584.5  349.88  4650.1  348.30  4703.4  348.48  4764.6  349.25
  4793.6  348.29  4850.4  349.17  4886.2  348.41  4958.8  349.63  4972.8  343.34
  4987.7  341.49  4992.1  345.79  5015.3  344.26  5040.9  347.92  5043.7  341.30
  5044.0  340.80  5048.2  341.30  5055.5  345.28  5065.6  348.18  5093.9  349.45
  5367.3  352.65  5420.2  354.21  5434.8  354.49  5511.4  356.37  5689.0  359.91
#Mann=8,-1,0
  4024.3    0.05       0  4703.4    0.12       0  5043.7    0.05       0
  5048.2    0.12       0  5093.9    0.07       0  5420.2    0.05       0
  5434.8    0.07       0  5511.4    0.05       0
Bank Sta=5043.7,5048.2
Exp/Cntr=0.3,0.1

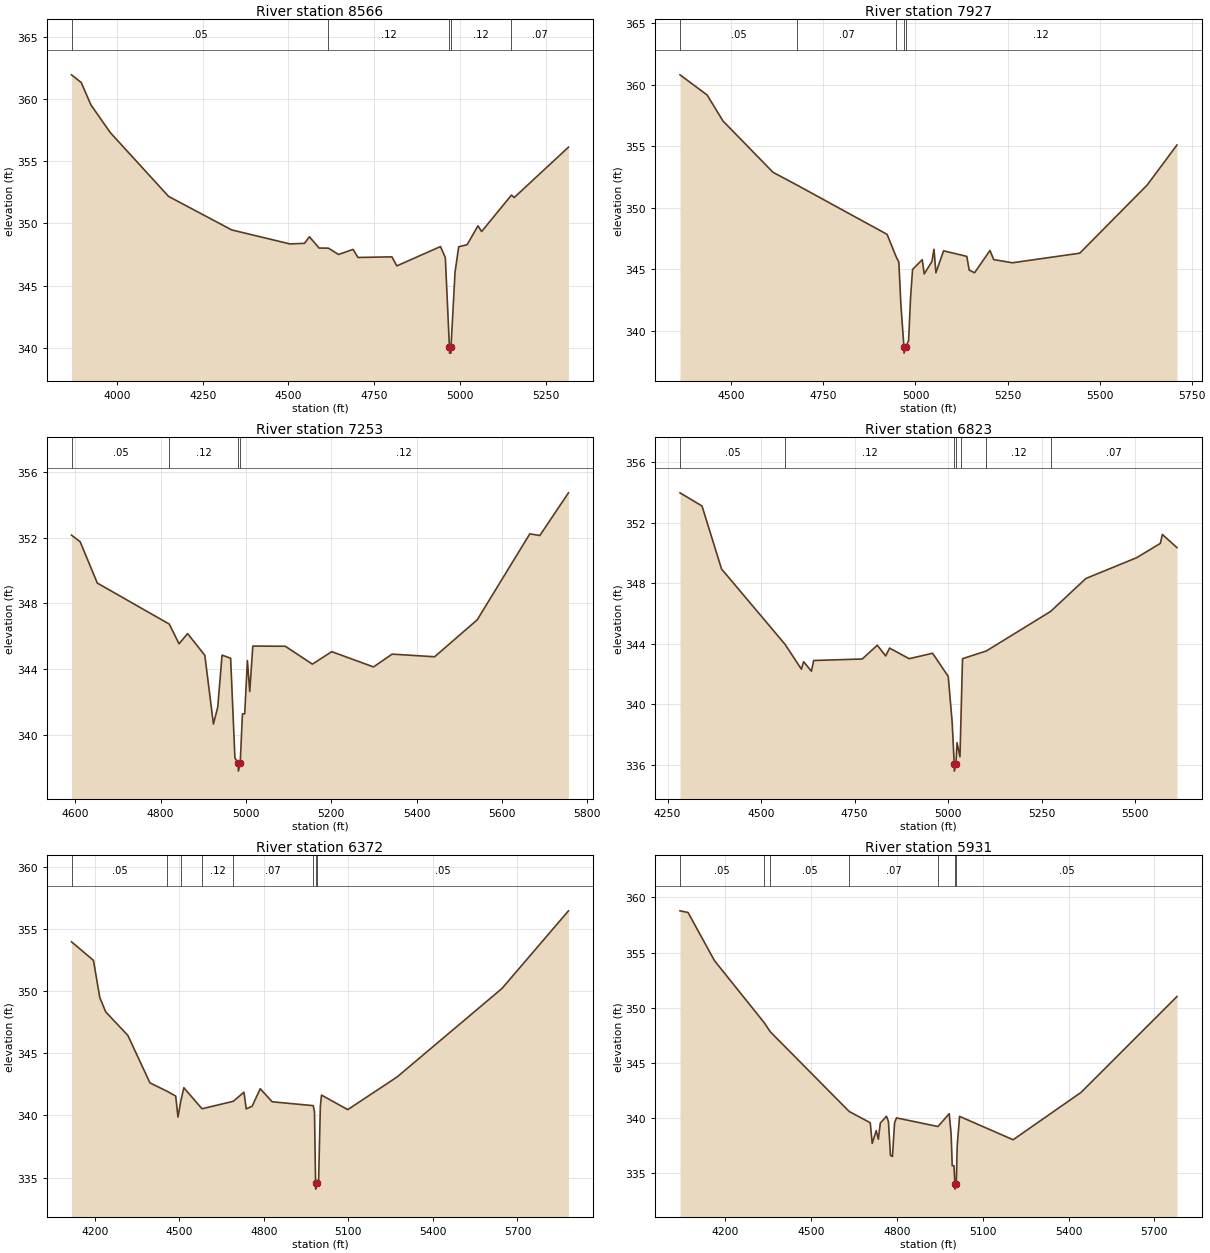
Type RM Length L Ch R = 1,8566,639,639,639
BEGIN DESCRIPTION:
Cedar Spring Branch 10.0
END DESCRIPTION:
XS GIS Cut Line= 3
      2551824.98     13800975.02      2551025.00     13801775.00
      2550924.99     13802075.03
#Sta/Elev= 30
  3868.0  361.98  3896.3  361.36  3924.5  359.56  3981.1  357.32  4150.8  352.18
  4334.7  349.48  4504.4  348.35  4546.8  348.40  4560.9  348.93  4589.2  348.02
  4616.5  348.01  4645.8  347.50  4688.2  347.91  4702.4  347.26  4801.4  347.31
  4815.5  346.58  4942.8  348.14  4956.9  347.25  4968.8  340.05  4969.1  339.55
  4973.0  339.55  4973.4  340.05  4985.2  346.08  4995.8  348.12  5020.4  348.29
  5052.0  349.81  5062.6  349.35  5149.6  352.29  5157.5  352.09  5315.6  356.15
#Mann=5,-1,0
  3868.0    0.05       0  4616.5    0.12       0  4968.8    0.05       0
  4973.4    0.12       0  5149.6    0.07       0
Bank Sta=4968.8,4973.4
Exp/Cntr=0.3,0.1

Type RM Length L Ch R = 1,7927,674,674,674
BEGIN DESCRIPTION:
Cedar Spring Branch 9.0
END DESCRIPTION:
XS GIS Cut Line= 3
      2551075.01     13800674.96      2550814.61     13801469.01
      2550725.00     13801974.98
#Sta/Elev= 30
  4360.7  360.79  4434.4  359.15  4477.4  357.04  4613.3  352.87  4679.2  351.82
  4923.0  347.83  4947.8  346.00  4954.9  345.57  4960.6  342.07  4968.8  338.68
  4969.1  338.18  4973.5  338.68  4981.4  339.19  4986.7  342.66  4992.2  344.98
  5018.5  345.77  5023.8  344.61  5044.8  345.63  5050.4  346.62  5055.6  344.71
  5076.4  346.49  5139.5  346.04  5145.9  344.93  5160.6  344.71  5202.4  346.52
  5212.6  345.78  5263.4  345.52  5446.2  346.30  5629.1  351.83  5710.2  355.09
#Mann=5,-1,0
  4360.7    0.05       0  4679.2    0.07       0  4947.8    0.12       0
  4968.8    0.05       0  4973.5    0.12       0
Bank Sta=4968.8,4973.5
Exp/Cntr=0.3,0.1

Type RM Length L Ch R = 1,7253,430,430,430
BEGIN DESCRIPTION:
Cedar Spring Branch 8.0
END DESCRIPTION:
XS GIS Cut Line= 3
      2550325.00     13800874.97      2550375.00     13801275.00
      2550674.99     13801974.98
#Sta/Elev= 30
  4591.4  352.16  4611.6  351.76  4651.9  349.24  4820.5  346.74  4843.4  345.54
  4863.5  346.16  4903.8  344.84  4924.0  340.65  4934.1  341.68  4944.2  344.85
  4964.3  344.66  4974.4  338.58  4982.1  338.28  4982.5  337.78  4986.8  338.28
  4992.0  341.27  4997.3  341.27  5003.6  344.52  5009.1  342.63  5016.3  345.40
  5092.5  345.39  5155.9  344.30  5201.3  345.06  5299.2  344.13  5342.7  344.91
  5442.4  344.75  5542.2  347.00  5665.5  352.24  5689.0  352.14  5756.1  354.74
#Mann=4,-1,0
  4591.4    0.05       0  4820.5    0.12       0  4982.1    0.05       0
  4986.8    0.12       0
Bank Sta=4982.1,4986.8
Exp/Cntr=0.3,0.1

Type RM Length L Ch R = 1,6823,451,451,451
BEGIN DESCRIPTION:
X18426
END DESCRIPTION:
XS GIS Cut Line= 3
      2550273.75     13800828.71      2550054.52     13801553.10
      2550232.44     13802096.38
#Sta/Elev= 30
  4283.3  353.98  4342.1  353.11  4394.3  348.95  4564.4  343.96  4607.7  342.33
  4613.8  342.82  4634.6  342.19  4640.7  342.90  4770.5  343.00  4810.6  343.91
  4833.2  343.20  4843.5  343.72  4895.8  343.02  4958.5  343.38  5000.3  341.85
  5010.8  338.84  5016.3  336.09  5016.6  335.59  5021.0  336.09  5023.8  337.47
  5031.7  336.54  5033.4  338.16  5038.5  343.02  5102.2  343.53  5273.9  346.14
  5368.3  348.32  5503.7  349.69  5567.4  350.64  5572.7  351.23  5611.8  350.36
#Mann=7,-1,0
  4283.3    0.05       0  4564.4    0.12       0  5016.3    0.05       0
  5021.0    0.12       0  5033.4    0.07       0  5102.2    0.12       0
  5273.9    0.07       0
Bank Sta=5016.3,5021
Exp/Cntr=0.3,0.1

Type RM Length L Ch R = 1,6372,441,441,441
BEGIN DESCRIPTION:
Cedar Spring Branch 7.0
END DESCRIPTION:
XS GIS Cut Line= 3
      2550225.03     13800824.96      2549675.00     13801525.00
      2549324.99     13802325.01
#Sta/Elev= 30
  4117.5  353.96  4195.3  352.47  4217.8  349.49  4238.7  348.33  4317.3  346.44
  4395.9  342.62  4458.1  341.93  4487.2  341.56  4495.3  339.87  4504.9  341.11
  4516.1  342.23  4580.6  340.54  4691.6  341.14  4729.4  341.87  4737.5  340.53
  4758.3  340.74  4787.2  342.15  4829.7  341.10  4975.3  340.79  4979.7  340.29
  4983.6  334.58  4983.9  334.08  4988.6  334.58  4994.2  334.63  5000.5  340.74
  5004.6  341.64  5097.8  340.47  5272.5  343.09  5645.1  350.21  5881.0  356.45
#Mann=8,-1,0
  4117.5    0.05       0  4458.1    0.12       0  4504.9    0.05       0
  4580.6    0.12       0  4691.6    0.07       0  4975.3    0.05       0
  4983.6    0.05       0  4988.6    0.05       0
Bank Sta=4983.6,4988.6
Exp/Cntr=0.3,0.1

Type RM Length L Ch R = 1,5931,464,464,464
BEGIN DESCRIPTION:
Cedar Spring Branch 6.0
END DESCRIPTION:
XS GIS Cut Line= 3
      2550075.02     13800574.98      2549375.00     13801225.00
      2549025.00     13801925.00
#Sta/Elev= 30
  4041.2  358.78  4069.3  358.63  4161.7  354.27  4335.7  348.65  4356.8  347.83
  4632.9  340.61  4706.5  339.59  4713.3  337.72  4727.5  338.88  4734.8  338.10
  4741.7  339.56  4763.2  340.18  4770.0  339.71  4777.3  336.63  4784.2  336.54
  4791.5  339.59  4798.3  340.03  4943.3  339.25  4982.6  340.41  4989.4  338.55
  4993.1  335.70  4999.3  335.70  5002.4  334.08  5002.7  333.58  5007.4  334.08
  5010.4  337.46  5018.8  340.17  5206.1  338.05  5443.7  342.34  5779.1  351.02
#Mann=7,-1,0
  4041.2    0.05       0  4335.7    0.07       0  4356.8    0.05       0
  4632.9    0.07       0  4943.3    0.05       0  5002.4    0.05       0
  5007.4    0.05       0
Bank Sta=5002.4,5007.4
Exp/Cntr=0.3,0.1

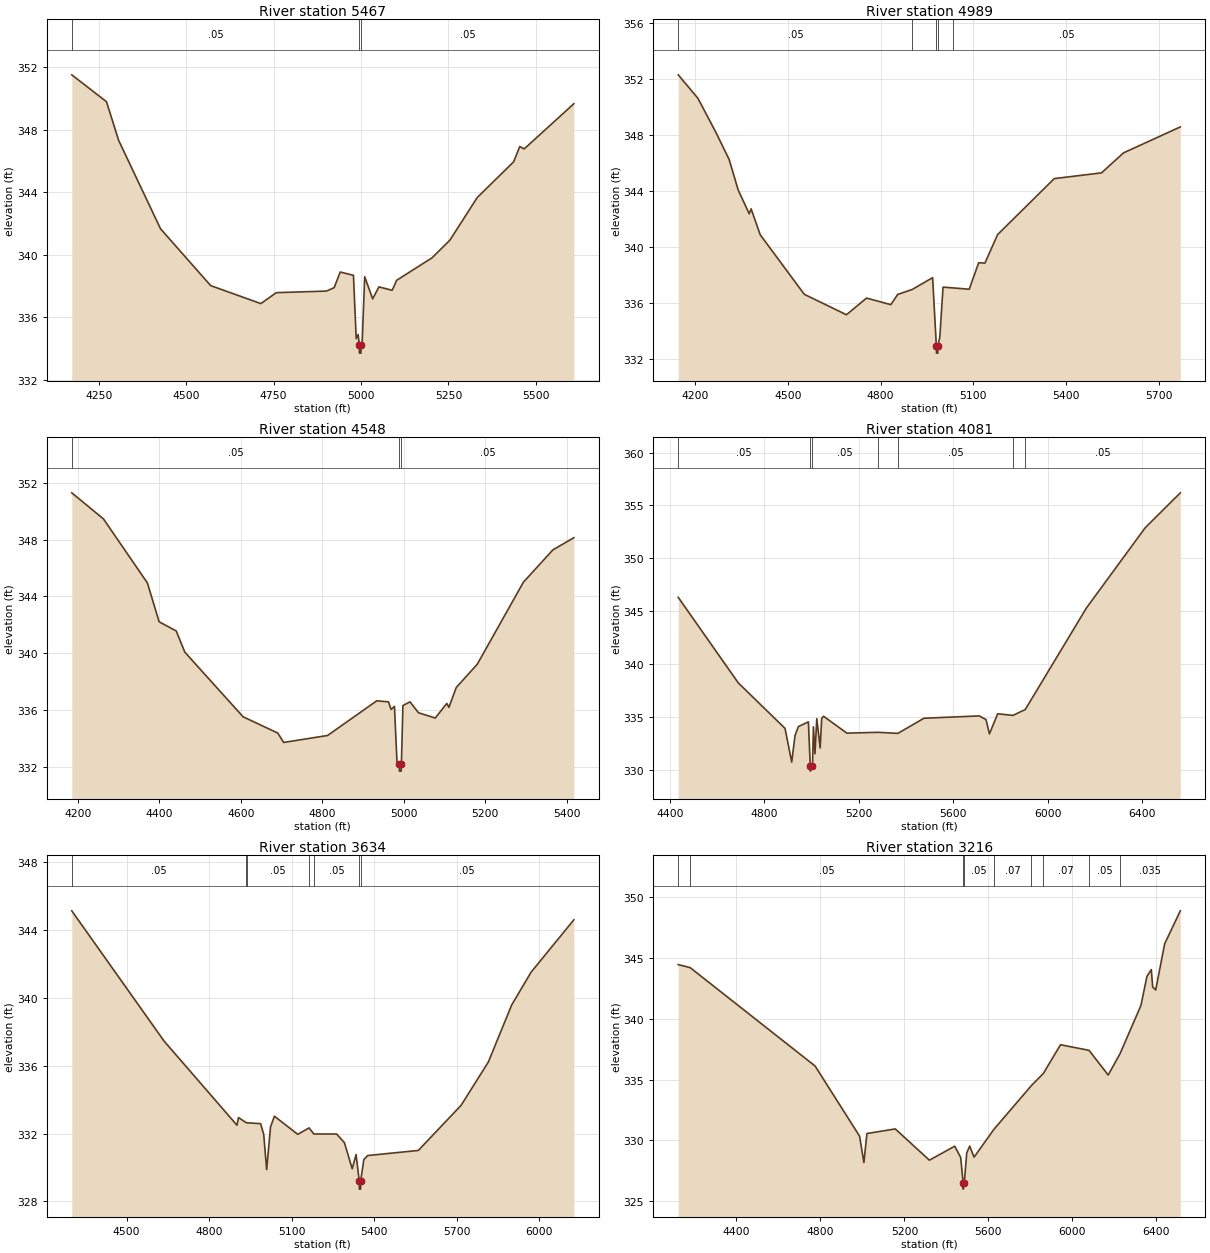
Type RM Length L Ch R = 1,5467,478,478,478
BEGIN DESCRIPTION:
Cedar Spring Branch 5.0
END DESCRIPTION:
XS GIS Cut Line= 3
      2549325.01     13800474.98      2548975.00     13801225.00
      2548875.01     13801824.95
#Sta/Elev= 30
  4172.8  351.52  4272.1  349.80  4306.8  347.33  4426.6  341.67  4570.1  338.03
  4713.6  336.88  4757.7  337.58  4901.2  337.68  4923.2  337.90  4940.6  338.90
  4978.4  338.69  4986.3  334.64  4991.8  334.90  4995.2  334.21  4995.6  333.71
  4999.9  333.71  5000.3  334.21  5003.0  334.21  5010.6  338.60  5033.4  337.18
  5051.2  337.95  5089.2  337.73  5101.9  338.37  5203.2  339.81  5253.9  340.93
  5332.5  343.67  5436.4  345.95  5454.1  346.93  5466.8  346.78  5608.7  349.67
#Mann=3,-1,0
  4172.8    0.05       0  4995.2    0.05       0  5000.3    0.05       0
Bank Sta=4995.2,5000.3
Exp/Cntr=0.3,0.1

Type RM Length L Ch R = 1,4989,441,441,441
BEGIN DESCRIPTION:
Cedar Spring Branch 4.0
END DESCRIPTION:
XS GIS Cut Line= 3
      2549074.99     13800325.01      2548575.00     13801025.00
      2548725.01     13801775.03
#Sta/Elev= 30
  4145.1  352.31  4209.0  350.63  4268.0  348.16  4309.8  346.27  4339.3  344.08
  4374.9  342.39  4381.0  342.74  4410.5  340.89  4553.1  336.64  4689.5  335.18
  4754.6  336.37  4833.3  335.90  4855.4  336.63  4903.0  336.99  4968.5  337.83
  4980.6  332.94  4981.0  332.44  4985.3  332.44  4985.7  332.94  4991.8  333.60
  5002.2  337.15  5033.3  337.10  5086.9  337.00  5117.5  338.89  5137.9  338.87
  5178.7  340.90  5362.2  344.90  5515.2  345.31  5586.6  346.74  5770.2  348.59
#Mann=5,-1,0
  4145.1    0.05       0  4903.0     0.1       0  4980.6    0.05       0
  4985.7     0.1       0  5033.3    0.05       0
Bank Sta=4980.6,4985.7
Exp/Cntr=0.3,0.1

Type RM Length L Ch R = 1,4548,467,467,467
BEGIN DESCRIPTION:
Cedar Spring Branch 3.0
END DESCRIPTION:
XS GIS Cut Line= 3
      2548924.97     13800225.02      2548275.00     13800725.00
      2548175.01     13801124.96
#Sta/Elev= 30
  4185.0  351.29  4262.9  349.45  4370.7  344.94  4399.4  342.21  4441.4  341.56
  4462.5  340.07  4605.4  335.52  4690.6  334.37  4705.1  333.71  4812.9  334.20
  4933.4  336.64  4962.4  336.57  4968.8  336.03  4977.0  336.25  4983.3  332.29
  4988.9  332.19  4989.3  331.69  4993.6  331.69  4994.0  332.19  4997.8  336.31
  5015.3  336.57  5036.0  335.80  5077.2  335.43  5105.5  336.46  5110.7  336.18
  5128.7  337.58  5180.3  339.22  5293.6  345.00  5365.8  347.27  5417.3  348.13
#Mann=3,-1,0
  4185.0    0.05       0  4988.9    0.05       0  4994.0    0.05       0
Bank Sta=4988.9,4994
Exp/Cntr=0.3,0.1

Type RM Length L Ch R = 1,4081,447,447,447
BEGIN DESCRIPTION:
Cedar Spring Branch 2.0
END DESCRIPTION:
XS GIS Cut Line= 3
      2548475.03     13799924.97      2548075.00     13800325.00
      2547074.98     13801525.02
#Sta/Elev= 30
  4434.5  346.31  4689.1  338.22  4887.1  333.92  4915.4  330.74  4929.5  333.25
  4943.7  334.09  4986.1  334.54  4994.1  330.38  4994.5  329.88  4999.3  330.38
  5003.5  330.38  5007.4  334.07  5013.9  331.52  5021.7  334.84  5036.0  332.07
  5042.5  334.87  5050.3  335.07  5149.3  333.47  5280.4  333.55  5365.5  333.45
  5476.0  334.88  5710.3  335.10  5738.9  334.75  5753.3  333.40  5788.4  335.30
  5853.1  335.15  5905.1  335.70  6164.6  345.31  6413.2  352.88  6562.3  356.19
#Mann=7,-1,0
  4434.5    0.05       0  4994.1    0.05       0  4999.3    0.05       0
  5280.4    0.07       0  5365.5    0.05       0  5853.1    0.07       0
  5905.1    0.05       0
Bank Sta=4994.1,4999.3
Exp/Cntr=0.3,0.1

Type RM Length L Ch R = 1,3634,418,418,418
BEGIN DESCRIPTION:
Cedar Spring Branch 1.0
END DESCRIPTION:
XS GIS Cut Line= 3
      2548324.99     13799775.00      2547725.00     13800125.00
      2546924.99     13800925.01
#Sta/Elev= 30
  4300.3  345.13  4636.0  337.45  4901.1  332.49  4906.8  332.94  4935.5  332.63
  4938.0  332.63  4987.1  332.58  4998.4  331.95  5009.1  329.87  5023.2  332.39
  5037.3  333.02  5122.2  331.95  5163.4  332.33  5180.8  331.97  5263.6  331.97
  5291.9  331.46  5320.2  329.92  5334.3  330.76  5345.8  329.22  5346.3  328.72
  5350.7  328.72  5351.1  329.22  5362.6  330.47  5376.8  330.70  5560.6  331.00
  5716.2  333.66  5815.2  336.21  5900.0  339.57  5970.7  341.51  6126.3  344.60
#Mann=7,-1,0
  4300.3    0.05       0  4935.5    0.07       0  4938.0    0.05       0
  5163.4    0.07       0  5180.8    0.05       0  5345.8    0.05       0
  5351.1    0.05       0
Bank Sta=5345.8,5351.1
Exp/Cntr=0.3,0.1

Type RM Length L Ch R = 1,3216,1161,1161,1161
BEGIN DESCRIPTION:
X18424
END DESCRIPTION:
XS GIS Cut Line= 3
      2548269.05     13799668.46      2547531.72     13799738.31
      2546460.73     13800995.56
#Sta/Elev= 30
  4122.5  344.45  4179.4  344.20  4774.7  336.11  4986.4  330.35  5007.2  328.18
  5021.5  330.56  5156.6  330.94  5319.1  328.37  5439.9  329.52  5468.4  328.59
  5480.0  326.49  5480.5  325.99  5485.3  326.49  5497.0  328.96  5511.2  329.53
  5532.1  328.62  5626.8  330.91  5804.5  334.49  5862.1  335.50  5943.9  337.86
  6079.9  337.40  6171.2  335.37  6227.7  337.13  6327.1  341.09  6355.7  343.48
  6376.5  344.04  6383.1  342.61  6397.4  342.36  6440.2  346.16  6514.7  348.87
#Mann=9,-1,0
  4122.5   0.035       0  4179.4    0.05       0  5480.0    0.05       0
  5485.3    0.05       0  5626.8    0.07       0  5804.5    0.05       0
  5862.1    0.07       0  6079.9    0.05       0  6227.7   0.035       0
Bank Sta=5480,5485.3
Exp/Cntr=0.3,0.1

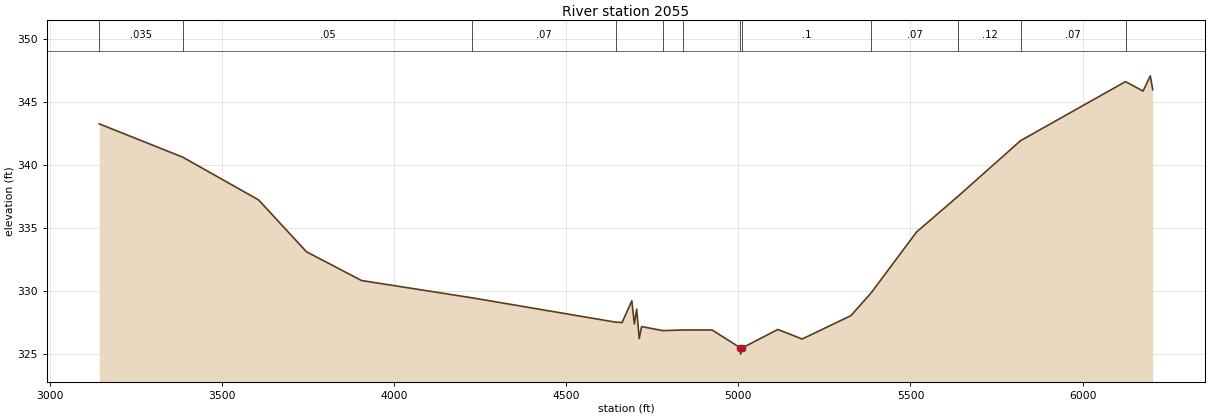
Type RM Length L Ch R = 1,2055,0,0,0
BEGIN DESCRIPTION:
X18423
END DESCRIPTION:
XS GIS Cut Line= 3
      2548175.86     13799606.38      2546670.25     13799683.99
      2545544.94     13800754.98
#Sta/Elev= 30
  3142.9  343.28  3385.7  340.63  3605.6  337.24  3744.6  333.12  3904.8  330.83
  4227.2  329.45  4643.3  327.52  4661.9  327.49  4690.3  329.22  4697.5  327.38
  4704.4  328.56  4711.7  326.22  4718.6  327.17  4780.0  326.85  4839.8  326.90
  4923.6  326.90  5005.7  325.48  5006.2  324.98  5011.4  325.48  5114.6  326.94
  5185.3  326.18  5326.9  328.04  5385.1  329.83  5517.8  334.69  5638.8  337.54
  5820.1  341.95  6124.9  346.64  6175.8  345.89  6196.9  347.10  6204.0  346.00
#Mann=12,-1,0
  3142.9   0.035       0  3385.7    0.05       0  4227.2    0.07       0
  4643.3   0.035       0  4780.0    0.07       0  4839.8     0.1       0
  5005.7    0.05       0  5011.4     0.1       0  5385.1    0.07       0
  5638.8    0.12       0  5820.1    0.07       0  6124.9    0.05       0
Bank Sta=5005.7,5011.4
Exp/Cntr=0.3,0.1

Chan Stop Cuts=-1