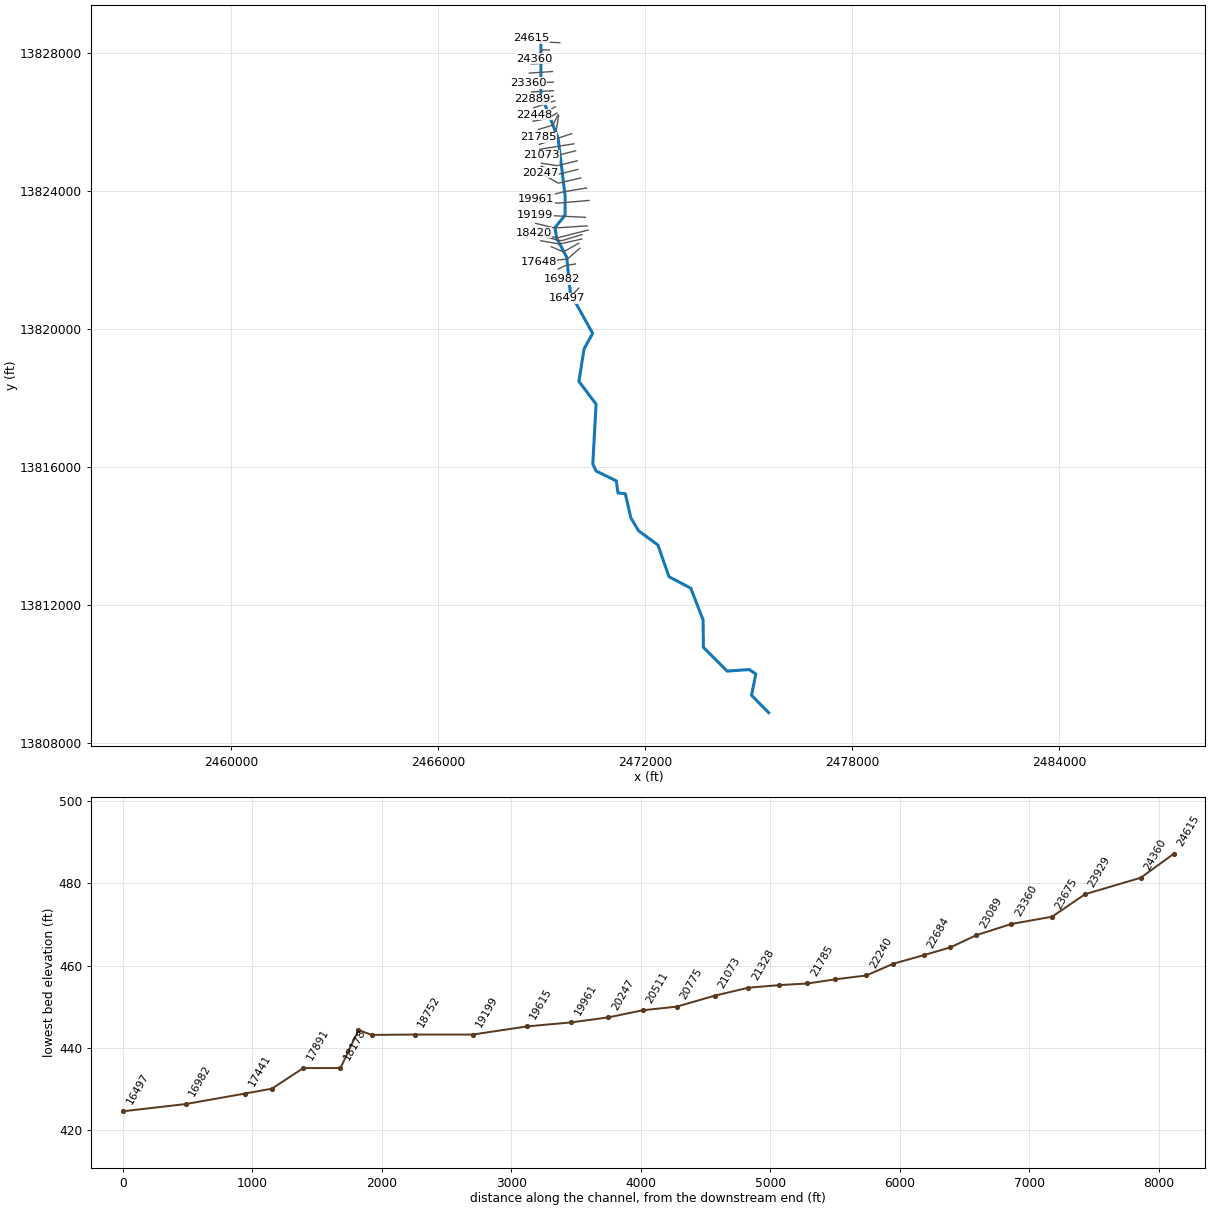
--- Chalk Hollow.prj (project) ---

Proj Title=Chalk Hollow Base Level Engineering
Current Plan=p01
Default Exp/Contr=0.3,0.1
English Units
Geom File=g01
Flow File=f01
Plan File=p01
Y Axis Title=Elevation
X Axis Title(PF)=Main Channel Distance
X Axis Title(XS)=Station
BEGIN DESCRIPTION:
Chalk Hollow
END DESCRIPTION:
DSS Export Rating Curves= 0
DSS Export Rating Curve Sorted= 0
DSS Export Volume Flow Curves= 0
DXF OffsetX= 0
DXF OffsetY= 0
DXF ScaleX= 1
DXF ScaleY= 10

--- Chalk Hollow.p01 (plan) ---

Plan Title=Multiple Run
Short Identifier=Multiple
Geom File=g01
Flow File=f01
Subcritical Flow
K Sum by GR= 0
Std Step Tol= 0.01
Critical Tol= 0.01
Num of Std Step Trials= 20
Max Error Tol= 0.3
Flow Tol Ratio= 0.001
Split Flow NTrial= 30
Split Flow Tol= 0.02
Split Flow Ratio= 0.02
Log Output Level= 0
Friction Slope Method= 1
Unsteady Friction Slope Method= 2
Unsteady Bridges Friction Slope Method= 1
Parabolic Critical Depth
Global Vel Dist=  1 , 1 , 1
Global Log Level= 0
CheckData=True
Encroach Param= -1, 0, 0, 0
BEGIN DESCRIPTION:
Multiple Run
END DESCRIPTION:

--- Chalk Hollow.f01 (steady flow) ---

Flow Title=Multiple
Number of Profiles=7
Profile Names=10-year,25-year,50-year,1pct_min,100-year,1pct_plu,500-year
River Rch & RM= Chalk Hollow,Reach-1,24615
     520     826    1097     707    1411    2816    2309
River Rch & RM= Chalk Hollow,Reach-1,15055
     675    1088    1460     949    1893    3778    3153
River Rch & RM= Chalk Hollow,Reach-1,13318
    1048    1726    2351    1549    3090    6166    5287
River Rch & RM= Chalk Hollow,Reach-1,10075
    1210    2004    2741    1811    3613    7210    6223
River Rch & RM= Chalk Hollow,Reach-1,6402
    1390    2313    3172    2100    4190    8360    7247
River Rch & RM= Chalk Hollow,Reach-1,3653
    1784    2999    4140    2758    5502   10978    9630
Boundary for River Rch & Prof#=Chalk Hollow,Reach-1,1
Up Type=0
Dn Type=3
Dn Slope=0.005
Boundary for River Rch & Prof#=Chalk Hollow,Reach-1,2
Up Type=0
Dn Type=3
Dn Slope=0.005
Boundary for River Rch & Prof#=Chalk Hollow,Reach-1,3
Up Type=0
Dn Type=3
Dn Slope=0.005
Boundary for River Rch & Prof#=Chalk Hollow,Reach-1,4
Up Type=0
Dn Type=3
Dn Slope=0.005
Boundary for River Rch & Prof#=Chalk Hollow,Reach-1,5
Up Type=0
Dn Type=3
Dn Slope=0.005
Boundary for River Rch & Prof#=Chalk Hollow,Reach-1,6
Up Type=0
Dn Type=3
Dn Slope=0.005
Boundary for River Rch & Prof#=Chalk Hollow,Reach-1,7
Up Type=0
Dn Type=3
Dn Slope=0.005

--- Chalk Hollow.g01 (geometry) ---

Geom Title=Existing Conditions
Program Version=4.10

River Reach=Chalk Hollow    ,Reach-1
Reach XY= 30
        2468975.       13828325.      2468976.22      13826785.5
      2469472.93     13825519.14      2469674.95     13823854.96
      2469673.95     13823285.43      2469382.61     13822928.33
      2469432.79     13822621.57      2469722.94     13822069.14
      2469828.74     13821026.53      2470474.16     13819863.05
      2470227.24     13819419.07        2470075.       13818475.
       2470573.8      13817814.5      2470478.55     13816076.47
        2470575.       13815875.      2471158.72     13815591.74
      2471207.78     13815241.24        2471422.     13815217.05
      2471580.54     13814522.58      2471804.61     13814144.84
      2472366.86     13813731.06      2472685.61     13812814.94
        2473317.     13812481.39      2473673.95     13811564.56
      2473682.75     13810768.81      2474372.33      13810080.3
      2475009.64      13810125.1       2475202.7     13809998.73
      2475077.14     13809380.97        2475575.       13808875.

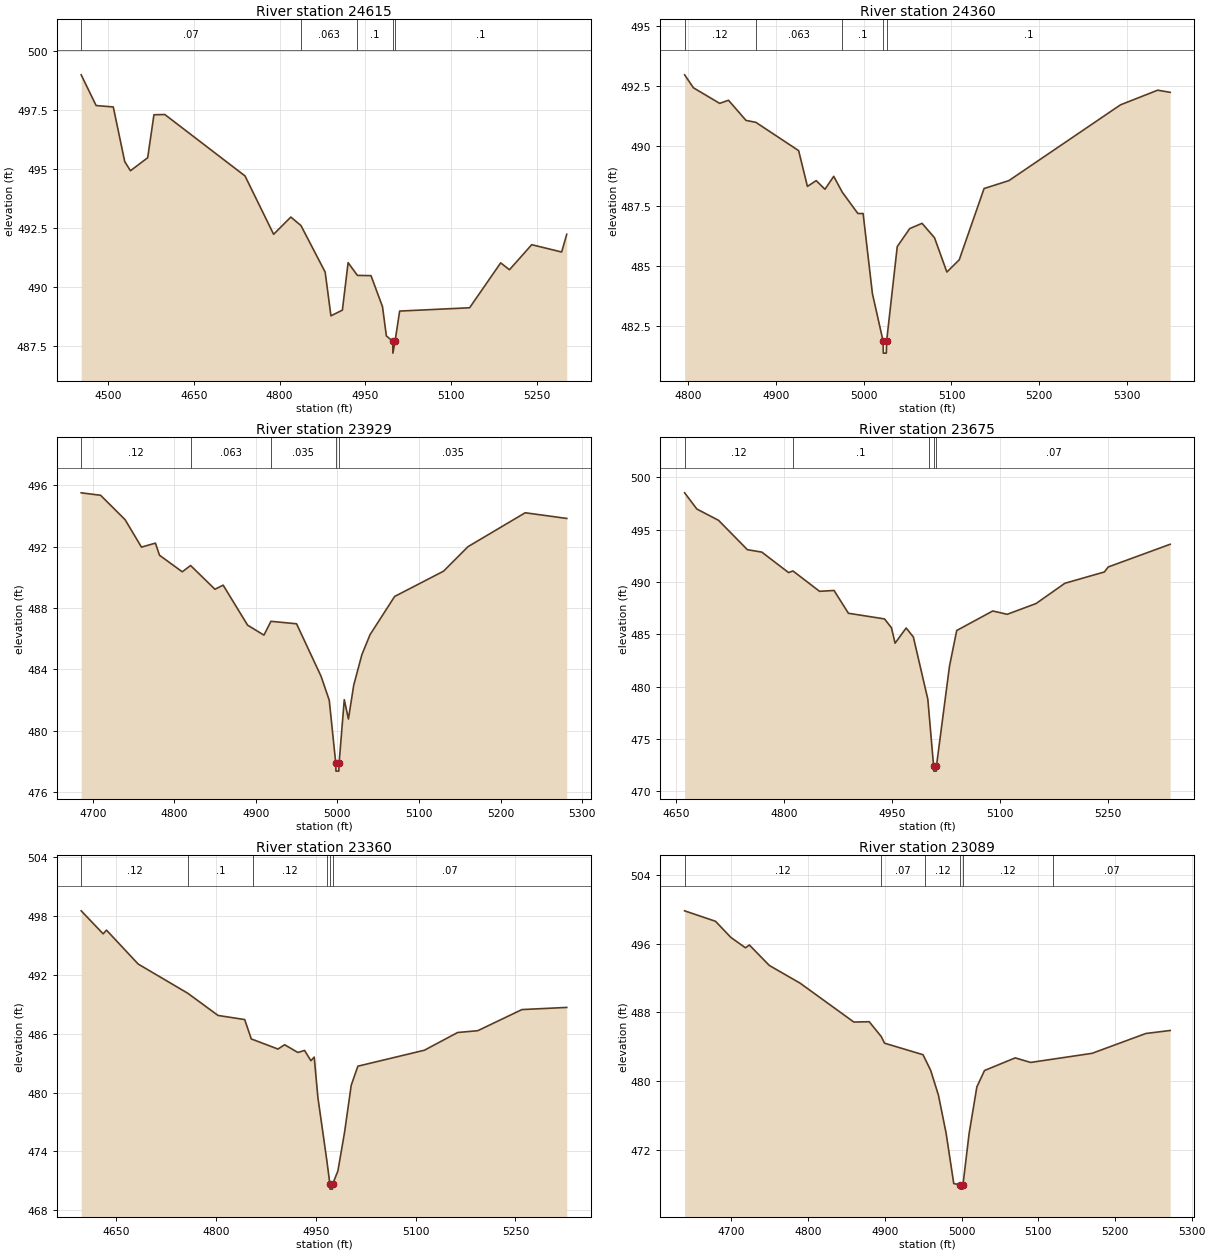
Type RM Length L Ch R = 1 ,24615   ,255,255,255
BEGIN DESCRIPTION:
X18427
END DESCRIPTION:
XS GIS Cut Line= 3
      2469521.04     13828284.03       2468947.3      13828311.9
      2468691.75      13828411.8
#Sta/Elev= 30
  4453.3  498.98  4479.4  497.68  4509.4  497.62  4529.4  495.31  4539.4  494.92
  4569.5  495.47  4580.5  497.29  4599.5   497.3  4739.7   494.7  4789.7  492.23
  4819.8  492.96  4837.5   492.6  4879.8  490.63  4889.9  488.78  4909.9  489.02
  4919.9  491.03  4936.2  490.49  4959.9  490.48    4980  489.17  4986.8  487.93
    4998   487.7  4998.2   487.2    5002   487.7    5010  488.98  5132.3  489.12
  5186.6  491.02    5202  490.73  5240.9  491.79  5293.2  491.48  5302.1  492.23
#Mann= 5 ,-1 , 0
  4453.3     .07       0  4837.5    .063       0  4936.2      .1       0
    4998     .05       0    5002      .1       0
Bank Sta=4998,5002
XS Rating Curve= 0 ,0
Exp/Cntr=0.3,0.1

Type RM Length L Ch R = 1 ,24360   ,431,431,431
BEGIN DESCRIPTION:
Chalk Hollow 48.0
END DESCRIPTION:
XS GIS Cut Line= 3
        2469225.       13828075.        2469025.       13828075.
      2468774.97     13827824.97
#Sta/Elev= 30
  4795.8  492.97  4805.8  492.43  4835.8  491.78  4845.8  491.91  4865.8  491.07
    4877  490.99  4925.8  489.81  4935.8  488.32  4945.8  488.56  4955.8   488.2
  4965.8  488.74  4975.5  488.08  4993.3  487.19  4999.3  487.19  5009.9  483.85
  5022.1  481.87  5022.3  481.37  5025.8  481.37  5026.1  481.87  5038.2  485.81
  5052.4  486.56  5066.5  486.78  5080.7  486.18  5094.8  484.75  5108.9  485.26
  5137.2  488.23  5165.5  488.56  5292.8  491.72  5335.2  492.33  5349.4  492.24
#Mann= 5 ,-1 , 0
  4795.8     .12       0    4877    .063       0  4975.5      .1       0
  5022.1     .05       0  5026.1      .1       0
Bank Sta=5022.1,5026.1
XS Rating Curve= 0 ,0
Exp/Cntr=0.3,0.1

Type RM Length L Ch R = 1 ,23929   ,254,254,254
BEGIN DESCRIPTION:
X18428
END DESCRIPTION:
XS GIS Cut Line= 2
       2469288.8       13827694.      2468694.15     13827668.44
#Sta/Elev= 30
  4685.9  495.52  4709.7  495.36  4739.7  493.77  4759.8  491.98  4776.9  492.24
  4781.9  491.45  4809.8  490.37    4820  490.78  4849.9  489.23  4859.9   489.5
  4889.9  486.89  4909.9  486.24  4918.5  487.14  4949.9  486.98    4980  483.55
    4990  481.99    4998  477.87  4998.2  477.37  5001.7  477.37    5002  477.87
  5008.4  482.03  5013.5  480.77    5020  482.98    5030  484.97    5040  486.27
  5070.1  488.76  5130.1  490.41  5160.1  492.01  5230.2  494.22  5281.1  493.85
#Mann= 5 ,-1 , 0
  4685.9     .12       0    4820    .063       0  4918.5    .035       0
    4998    .035       0    5002    .035       0
Bank Sta=4998,5002
XS Rating Curve= 0 ,0
Exp/Cntr=0.3,0.1

Type RM Length L Ch R = 1 ,23675   ,315,315,315
BEGIN DESCRIPTION:
X18429
END DESCRIPTION:
XS GIS Cut Line= 2
      2469311.98     13827450.08      2468639.18     13827403.68
#Sta/Elev= 30
  4662.3  498.53  4679.3  496.98  4709.4   495.9  4749.5  493.09  4769.5  492.86
  4806.7   490.9  4812.7  491.06  4849.7  489.11  4869.8  489.19  4889.8  487.01
  4939.9  486.47  4949.6  485.62  4954.6  484.15    4970   485.6    4980  484.74
  5000.1  478.78  5001.8  477.43  5008.1  472.41  5008.4  471.91  5011.9  471.91
  5012.1  472.41  5030.2  481.96  5040.2  485.36  5090.3  487.23  5110.3  486.91
  5150.4  487.94  5190.5  489.88  5245.3  490.96  5250.7  491.44  5336.7  493.61
#Mann= 5 ,-1 , 0
  4662.3     .12       0  4812.7      .1       0  5001.8     .07       0
  5008.1     .05       0  5012.1     .07       0
Bank Sta=5008.1,5012.1
XS Rating Curve= 0 ,0
Exp/Cntr=0.3,0.1

Type RM Length L Ch R = 1 ,23360   ,271,271,271
BEGIN DESCRIPTION:
X18430
END DESCRIPTION:
XS GIS Cut Line= 2
      2469330.56     13827141.13      2468601.23      13827117.9
#Sta/Elev= 30
  4597.4  498.55  4630.4   496.2  4635.4  496.58    4683  493.12  4757.5  490.14
  4803.1  487.87  4843.1  487.45  4853.1  485.46  4855.9   485.4  4893.1  484.44
  4903.1  484.88  4923.1  484.09  4933.1   484.3  4942.6  483.25  4947.6  483.62
  4953.1  479.51  4966.4  473.15  4971.2  470.64  4971.4  470.14  4974.9  470.14
  4975.2  470.64  4983.2     472  4993.2  475.94  5003.2  480.74  5013.2  482.69
  5113.2  484.32  5163.2  486.13  5193.3  486.31  5259.8  488.47  5327.1  488.69
#Mann= 6 ,-1 , 0
  4597.4     .12       0  4757.5      .1       0  4855.9     .12       0
  4966.4     .07       0  4971.2     .05       0  4975.2     .07       0
Bank Sta=4971.2,4975.2
XS Rating Curve= 0 ,0
Exp/Cntr=0.3,0.1

Type RM Length L Ch R = 1 ,23089   ,200,200,200
BEGIN DESCRIPTION:
X18431
END DESCRIPTION:
XS GIS Cut Line= 2
      2469335.19      13826894.9      2468703.39     13826857.73
#Sta/Elev= 30
  4639.1  499.82  4679.4   498.6  4699.4  496.72  4718.4  495.52  4723.5  495.84
  4749.5  493.46  4789.6   491.4  4859.7  486.87  4879.7  486.91  4895.4  485.18
  4899.7  484.41  4949.8  483.07  4952.4   482.6  4959.8  481.25  4969.9  478.37
  4979.9  473.95  4989.9  468.07  4997.9  467.92  4998.2  467.42  5001.7  467.42
  5001.9  467.92  5009.9  473.88    5020  479.32    5030  481.23    5070   482.7
  5090.1  482.17  5119.7  482.56  5170.2  483.23  5240.3  485.54    5272  485.89
#Mann= 6 ,-1 , 0
  4639.1     .12       0  4895.4     .07       0  4952.4     .12       0
  4997.9     .05       0  5001.9     .12       0  5119.7     .07       0
Bank Sta=4997.9,5001.9
XS Rating Curve= 0 ,0
Exp/Cntr=0.3,0.1

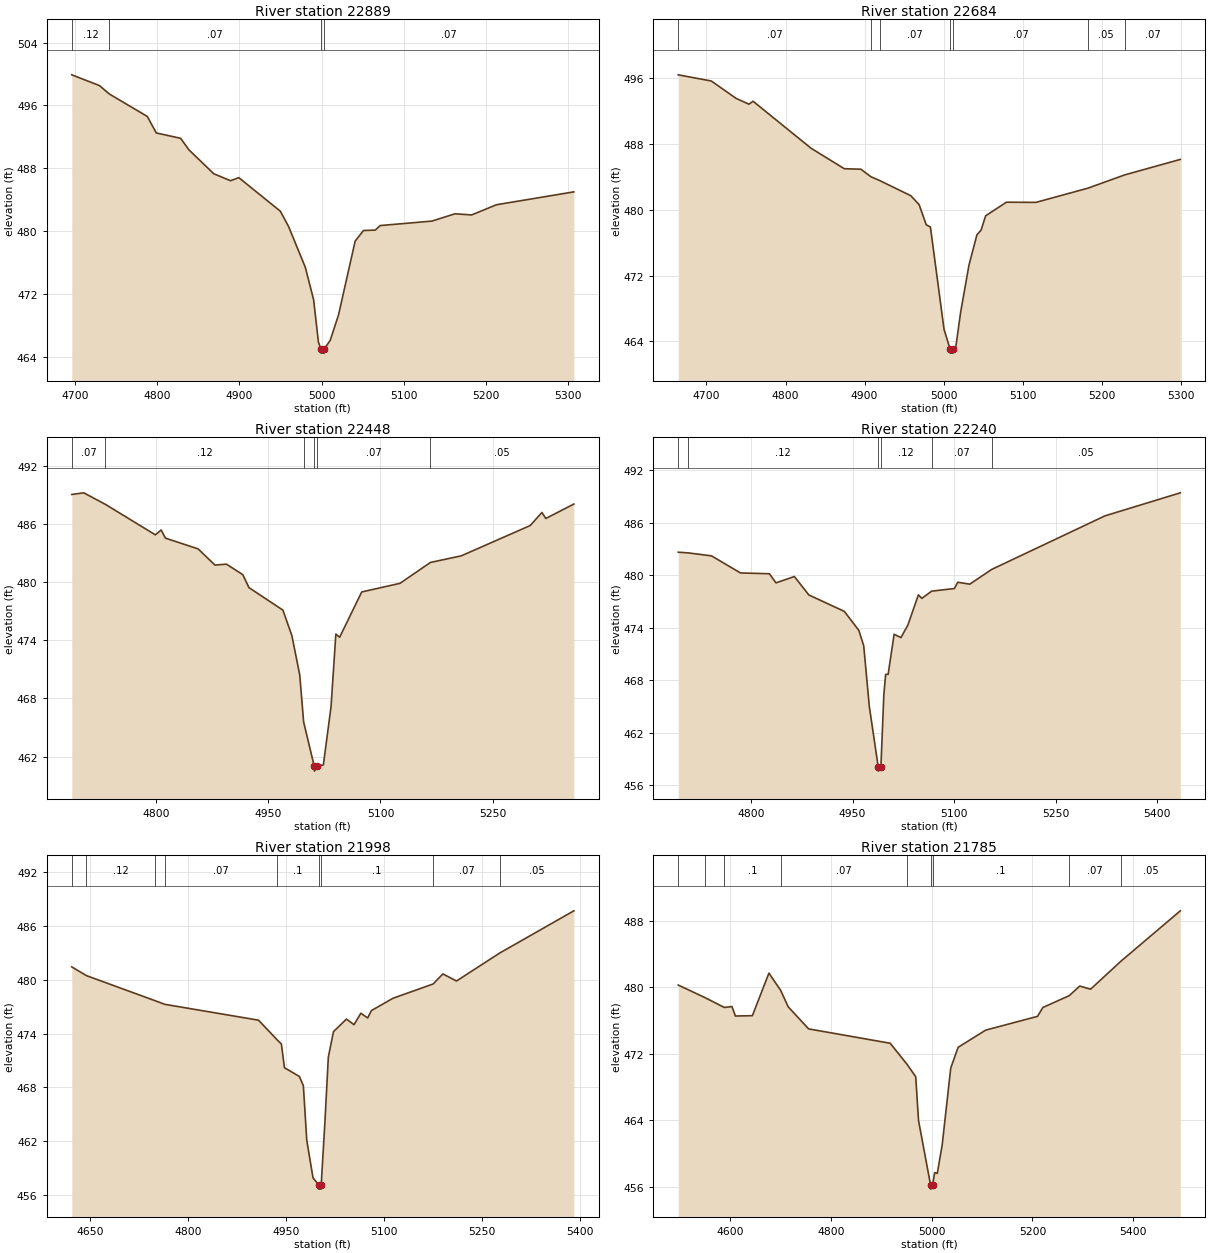
Type RM Length L Ch R = 1 ,22889   ,205,205,205
BEGIN DESCRIPTION:
X18432
END DESCRIPTION:
XS GIS Cut Line= 2
      2469325.92     13826734.61      2468721.98     13826644.02
#Sta/Elev= 30
  4696.1  499.89  4729.8  498.52  4741.8  497.45    4788  494.59  4798.9  492.49
  4828.5  491.81  4838.6  490.34  4868.9  487.29  4889.2  486.41  4899.3   486.8
  4949.8  482.53  4959.9  480.56  4980.2  475.38  4990.3  471.24  4996.1  465.89
  4999.1  464.96  4999.4  464.46  5002.9  464.46  5003.1  464.96  5010.5   466.1
  5020.6  469.34  5040.8  478.72  5050.9  480.07  5065.2  480.12  5071.2   480.7
  5134.3  481.27  5162.2   482.2  5182.4  482.05  5212.7  483.35  5306.8  484.99
#Mann= 4 ,-1 , 0
  4696.1     .12       0  4741.8     .07       0  4999.1     .05       0
  5003.1     .07       0
Bank Sta=4999.1,5003.1
XS Rating Curve= 0 ,0
Exp/Cntr=0.3,0.1

Type RM Length L Ch R = 1 ,22684   ,236,236,236
BEGIN DESCRIPTION:
X18433
END DESCRIPTION:
XS GIS Cut Line= 2
      2469374.74     13826597.56      2468770.78     13826402.44
#Sta/Elev= 30
  4664.4  496.39  4706.2  495.64  4737.7  493.52  4753.8  492.82    4759  493.18
  4832.3  487.47  4874.3  484.98  4895.3  484.92  4908.1     484  4918.9  483.55
  4958.4   481.7  4968.9  480.62  4977.9  478.17  4983.2  477.89  5000.4  465.48
    5008  463.07  5008.2  462.57  5011.7  462.57    5012  463.07  5015.2  463.25
  5021.4  467.54  5031.9  473.25    5042  476.95  5047.3  477.53    5053  479.26
  5079.3  480.91  5116.6  480.89  5182.1  482.61  5228.8  484.23  5299.1  486.11
#Mann= 7 ,-1 , 0
  4664.4     .07       0  4908.1     .12       0  4918.9     .07       0
    5008     .05       0    5012     .07       0  5182.1     .05       0
  5228.8     .07       0
Bank Sta=5008,5012
XS Rating Curve= 0 ,0
Exp/Cntr=0.3,0.1

Type RM Length L Ch R = 1 ,22448   ,208,208,208
BEGIN DESCRIPTION:
X18434
END DESCRIPTION:
XS GIS Cut Line= 3
      2469393.32     13826427.99       2469119.2     13826279.31
      2468768.02     13826200.76
#Sta/Elev= 30
    4687  489.07    4703  489.24    4732  488.05  4798.8   484.9  4806.6   485.4
  4812.3  484.56    4856  483.45  4878.5  481.78    4894  481.87  4915.9  480.78
    4924  479.45  4969.5  477.12  4981.5  474.48    4992  470.42  4997.2  465.57
  5011.4  460.99  5011.6  460.49  5015.4  460.99  5023.6  461.13  5033.9  467.17
  5040.3  474.65  5045.4  474.32  5074.9     479  5126.1  479.89  5166.9  482.05
  5208.1  482.73  5300.3  485.86    5316  487.21  5321.2  486.59  5358.7  488.08
#Mann= 6 ,-1 , 0
    4687     .07       0    4732     .12       0  4997.2     .07       0
  5011.4     .05       0  5015.4     .07       0  5166.9     .05       0
Bank Sta=5011.4,5015.4
XS Rating Curve= 0 ,0
Exp/Cntr=0.3,0.1

Type RM Length L Ch R = 1 ,22240   ,242,242,242
BEGIN DESCRIPTION:
X18435
END DESCRIPTION:
XS GIS Cut Line= 3
      2469439.78      13826246.8      2469177.28     13826088.83
      2468749.12     13826010.14
#Sta/Elev= 30
  4692.4  482.64  4707.4  482.56  4741.6  482.22  4784.3  480.27  4827.1  480.18
  4836.8  479.14    4864  479.86  4885.3  477.76  4937.8  475.88  4959.2  473.71
  4966.4  471.96  4974.7  465.02  4987.8  458.14    4988  457.64  4991.8  458.14
  4996.1  466.31  4998.8  468.69  5002.5  468.69  5011.3  473.27  5021.4  472.89
  5031.6  474.31  5047.2  477.77  5052.3  477.37  5066.7  478.19  5100.3  478.49
  5105.4  479.21  5123.1  478.99  5155.4  480.67  5322.8  486.79  5434.1  489.42
#Mann= 6 ,-1 , 0
  4692.4     .07       0  4707.4     .12       0  4987.8     .05       0
  4991.8     .12       0  5066.7     .07       0  5155.4     .05       0
Bank Sta=4987.8,4991.8
XS Rating Curve= 0 ,0
Exp/Cntr=0.3,0.1

Type RM Length L Ch R = 1 ,21998   ,213,213,213
BEGIN DESCRIPTION:
X18436
END DESCRIPTION:
XS GIS Cut Line= 3
       2469465.3     13826193.32      2469325.94     13825898.35
      2468903.16     13825770.59
#Sta/Elev= 30
  4622.4  481.42  4644.8  480.45  4749.8  477.66  4764.4  477.26  4908.1  475.49
  4936.8  473.28    4943  472.84  4947.7   470.2  4970.5  469.23  4976.6   468.2
  4981.8  462.14  4991.4  457.94  4999.9  457.19  5000.1  456.69  5003.6  456.69
  5003.9  457.19  5009.6  464.18  5014.8  471.38  5022.7  474.22  5042.5  475.61
  5054.1  474.99  5064.5  476.26    5075  475.74  5080.7  476.56  5113.7  477.93
  5175.1  479.52    5190  480.64  5210.8  479.85  5277.1  482.97  5390.3  487.66
#Mann= 9 ,-1 , 0
  4622.4     .07       0  4644.8     .12       0  4749.8      .1       0
  4764.4     .07       0  4936.8      .1       0  4999.9     .05       0
  5003.9      .1       0  5175.1     .07       0  5277.1     .05       0
Bank Sta=4999.9,5003.9
XS Rating Curve= 0 ,0
Exp/Cntr=0.3,0.1

Type RM Length L Ch R = 1 ,21785   ,220,220,220
BEGIN DESCRIPTION:
X18437
END DESCRIPTION:
XS GIS Cut Line= 3
      2469488.56     13826170.18      2469414.22     13825714.84
      2468905.64     13825549.96
#Sta/Elev= 30
  4497.3  480.27  4550.6  478.75  4588.7  477.57  4603.9  477.68  4610.7  476.54
  4644.4  476.58  4677.2  481.71  4700.6  479.62  4715.3  477.66  4755.9  474.99
  4917.8  473.26  4951.4  470.71  4968.4  469.23    4974  463.95  4997.9  456.19
  4998.1  455.69  5001.9  456.19    5006  457.68  5011.2  457.59  5020.9     461
  5037.9  470.27  5052.5  472.77  5107.2  474.84  5210.1   476.5  5220.7  477.57
  5272.9  478.99  5293.8  480.15  5315.3  479.77  5375.5  483.14  5493.3  489.21
#Mann= 9 ,-1 , 0
  4497.3     .07       0  4550.6     .12       0  4588.7      .1       0
  4700.6     .07       0  4951.4      .1       0  4997.9     .05       0
  5001.9      .1       0  5272.9     .07       0  5375.5     .05       0
Bank Sta=4997.9,5001.9
XS Rating Curve= 0 ,0
Exp/Cntr=0.3,0.1

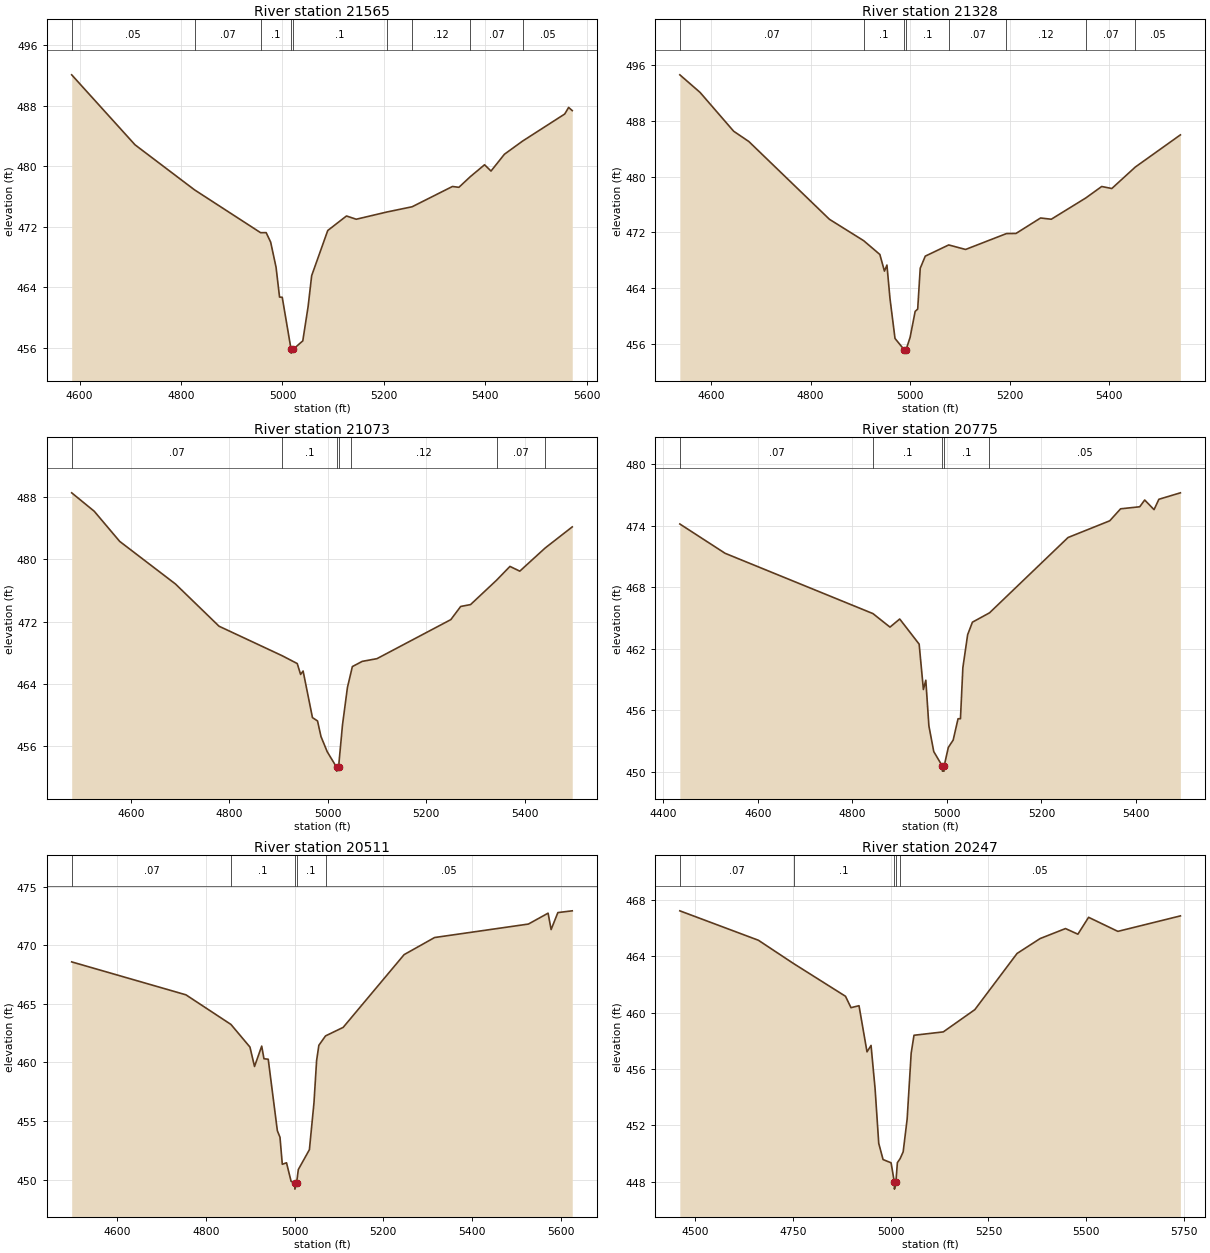
Type RM Length L Ch R = 1 ,21565   ,237,237,237
BEGIN DESCRIPTION:
X18438
END DESCRIPTION:
XS GIS Cut Line= 2
      2469867.21      13825649.8        2468931.      13825338.5
#Sta/Elev= 30
  4584.6  492.08  4709.4  482.83  4826.8  476.87    4957  471.21  4967.9  471.22
  4976.8  469.96  4987.4  466.65  4994.3   462.7  4999.6  462.67    5017  455.79
  5017.2  455.29    5021  455.79  5040.1  456.91  5050.6  461.45  5057.6  465.53
  5089.3   471.5  5126.2  473.42  5145.5  472.99  5205.5  473.94  5255.7  474.64
  5335.1  477.32  5347.8  477.21  5370.5  478.63  5398.4  480.19  5411.1  479.36
  5437.5  481.58  5473.3  483.32  5556.4   486.9  5564.1  487.77  5571.2  487.35
#Mann= 9 ,-1 , 0
  4584.6     .05       0  4826.8     .07       0    4957      .1       0
    5017     .05       0    5021      .1       0  5205.5     .07       0
  5255.7     .12       0  5370.5     .07       0  5473.3     .05       0
Bank Sta=5017,5021
XS Rating Curve= 0 ,0
Exp/Cntr=0.3,0.1

Type RM Length L Ch R = 1 ,21328   ,255,255,255
BEGIN DESCRIPTION:
X18439
END DESCRIPTION:
XS GIS Cut Line= 2
      2469931.79     13825356.21      2468938.97      13825195.8
#Sta/Elev= 30
  4537.3  494.61  4577.9  492.09  4645.5  486.51  4675.9  485.04  4837.9  473.87
  4906.5  470.81  4939.2  468.82  4948.4  466.43  4953.4   467.3  4959.5  462.52
  4969.6  456.77  4987.9  455.16  4988.1  454.66  4991.9  455.16    5000  456.94
  5010.1  460.65  5015.2  460.98  5020.3  466.84  5030.4  468.58  5077.5  470.19
  5111.4  469.54  5193.5  471.82  5212.7  471.84  5262.1  474.06  5283.6  473.88
  5353.1  476.94  5384.9  478.58  5405.2  478.29  5452.4  481.37    5543  485.99
#Mann= 8 ,-1 , 0
  4537.3     .07       0  4906.5      .1       0  4987.9     .05       0
  4991.9      .1       0  5077.5     .07       0  5193.5     .12       0
  5353.1     .07       0  5452.4     .05       0
Bank Sta=4987.9,4991.9
XS Rating Curve= 0 ,0
Exp/Cntr=0.3,0.1

Type RM Length L Ch R = 1 ,21073   ,298,298,298
BEGIN DESCRIPTION:
X18440
END DESCRIPTION:
XS GIS Cut Line= 3
      2469979.53     13825152.22      2469471.74     13825026.35
       2468978.5     13825026.35
#Sta/Elev= 30
  4480.2  488.55    4526  486.18  4577.6  482.31  4690.9  476.83  4779.4   471.4
  4907.5  467.61  4938.2   466.6    4945   465.2  4950.1  465.64  4969.1  459.65
  4979.4  459.22  4986.4  457.22  4999.1  455.26  5018.1  453.27  5018.3  452.77
  5022.1  453.27  5030.1  458.72  5040.1  463.52  5047.4  465.48  5050.1  466.21
  5070.1  466.88  5100.1  467.23  5250.1  472.25  5270.1  473.94  5290.1  474.18
    5343  477.32  5370.1  479.09  5390.1  478.48  5441.5  481.45  5496.6  484.17
#Mann= 7 ,-1 , 0
  4480.2     .07       0  4907.5      .1       0  5018.1     .05       0
  5022.1      .1       0  5047.4     .12       0    5343     .07       0
  5441.5     .05       0
Bank Sta=5018.1,5022.1
XS Rating Curve= 0 ,0
Exp/Cntr=0.3,0.1

Type RM Length L Ch R = 1 ,20775   ,264,264,264
BEGIN DESCRIPTION:
X18441
END DESCRIPTION:
XS GIS Cut Line= 3
      2470027.28     13824861.42      2469450.04     13824722.54
      2468989.96     13824791.98
#Sta/Elev= 30
  4434.9  474.18  4530.7  471.32  4843.4  465.44  4879.5  464.12  4900.1  464.91
  4941.2  462.46  4950.2  458.03  4955.3  458.94  4961.8  454.49  4972.1  451.98
  4990.1  450.57  4990.4  450.07  4993.9  450.07  4994.1  450.57  5002.9  452.38
  5013.2   453.1  5023.5  455.18  5028.6  455.18  5033.7  460.16  5043.8  463.38
  5053.9   464.6    5090  465.51  5256.2  472.86  5344.4  474.49  5367.4  475.66
  5407.9  475.86  5418.4  476.52  5438.2  475.58  5448.4  476.59  5493.9  477.22
#Mann= 5 ,-1 , 0
  4434.9     .07       0  4843.4      .1       0  4990.1     .05       0
  4994.1      .1       0    5090     .05       0
Bank Sta=4990.1,4994.1
XS Rating Curve= 0 ,0
Exp/Cntr=0.3,0.1

Type RM Length L Ch R = 1 ,20511   ,264,264,264
BEGIN DESCRIPTION:
X18442
END DESCRIPTION:
XS GIS Cut Line= 3
      2470044.68     13824614.03       2469489.1     13824475.14
      2468985.65      13824709.5
#Sta/Elev= 30
  4497.8  468.58  4755.2  465.77  4856.7  463.24  4899.5  461.31  4909.8  459.65
    4926  461.39  4931.1  460.31  4940.7  460.27  4961.3  454.16  4967.2  453.61
  4972.4   451.3  4981.9  451.43  4992.2  449.85  5000.5  449.68  5000.8  449.18
  5004.5  449.68  5008.5  450.85  5033.5  452.55  5043.8  456.56  5049.7  460.15
  5054.8  461.46  5069.8  462.26  5109.6  462.99  5246.9   469.2  5315.6  470.66
    5527  471.81  5571.4  472.74  5578.2  471.34  5593.4  472.79  5625.8  472.94
#Mann= 5 ,-1 , 0
  4497.8     .07       0  4856.7      .1       0  5000.5     .05       0
  5004.5      .1       0  5069.8     .05       0
Bank Sta=5000.5,5004.5
XS Rating Curve= 0 ,0
Exp/Cntr=0.3,0.1

Type RM Length L Ch R = 1 ,20247   ,286,286,286
BEGIN DESCRIPTION:
X18443
END DESCRIPTION:
XS GIS Cut Line= 3
      2470131.51     13824366.64      2469480.42     13824214.72
      2468948.24     13824517.59
#Sta/Elev= 30
  4460.2  467.23  4661.2  465.14  4751.5  463.48  4884.1  461.16  4898.2  460.35
  4918.7  460.49  4939.2  457.21  4949.5  457.67  4959.8  454.61  4969.2  450.71
  4980.3  449.56  5000.8  449.33  5009.1  447.96  5009.4  447.46  5013.1  447.96
  5016.9  449.34    5024  449.63  5031.7  450.11  5041.9  452.44  5052.2  457.12
  5059.4  458.39  5134.4  458.63  5215.1  460.21  5323.1   464.2  5382.2  465.26
  5447.1  465.97  5478.8  465.57  5506.2  466.77  5581.1  465.77  5741.1  466.87
#Mann= 5 ,-1 , 0
  4460.2     .07       0  4751.5      .1       0  5009.1     .05       0
  5013.1      .1       0    5024     .05       0
Bank Sta=5009.1,5013.1
XS Rating Curve= 0 ,0
Exp/Cntr=0.3,0.1

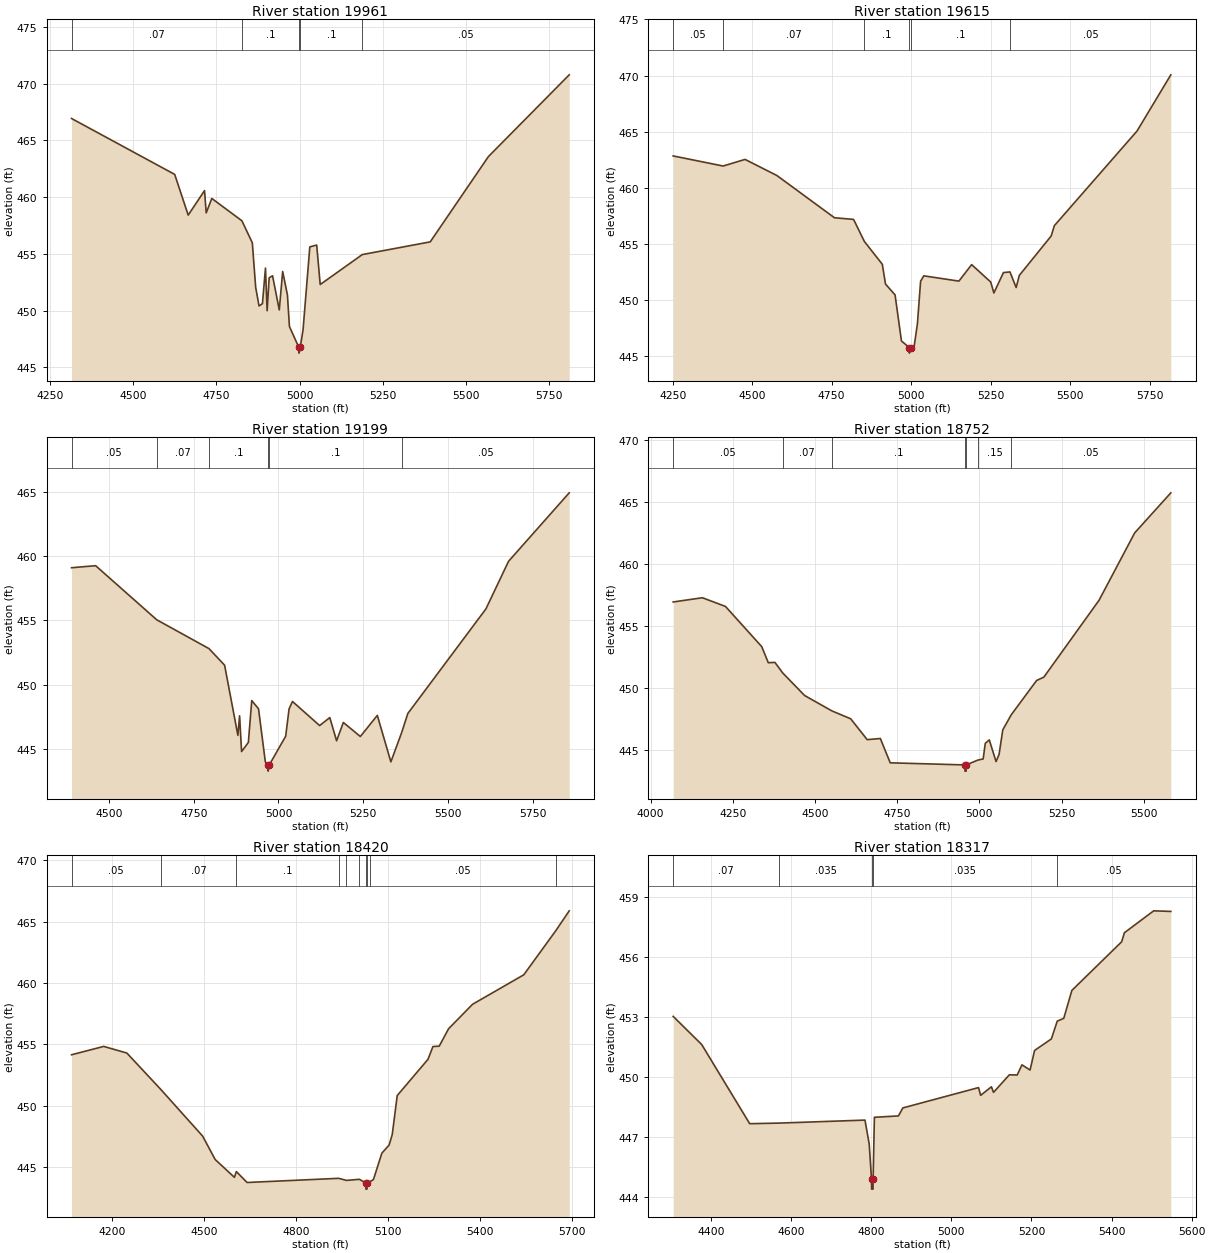
Type RM Length L Ch R = 1 ,19961   ,346,346,346
BEGIN DESCRIPTION:
X18444
END DESCRIPTION:
XS GIS Cut Line= 3
      2470300.76     13824075.84      2469619.31     13823962.99
      2468840.94     13823759.74
#Sta/Elev= 30
  4314.6  466.94  4624.5  462.01  4665.1  458.42  4714.1  460.58  4719.2  458.62
    4736  459.89  4826.4  457.92  4857.7  455.98  4867.8  452.05  4877.9  450.41
  4888.1  450.61  4897.2  453.75  4902.2  449.99  4908.3  452.89  4918.5  453.07
  4938.7  450.06  4948.9  453.45  4963.2  451.38  4969.2   448.6  4997.6  446.75
  4997.8  446.25  5001.6  446.75  5010.1   448.3  5030.5  455.62  5051.1  455.78
  5061.7   452.3  5188.1  454.94  5392.2  456.06    5567  463.58  5809.8  470.79
#Mann= 5 ,-1 , 0
  4314.6     .07       0  4826.4      .1       0  4997.6     .05       0
  5001.6      .1       0  5188.1     .05       0
Bank Sta=4997.6,5001.6
XS Rating Curve= 0 ,0
Exp/Cntr=0.3,0.1

Type RM Length L Ch R = 1 ,19615   ,416,416,416
BEGIN DESCRIPTION:
X18445
END DESCRIPTION:
XS GIS Cut Line= 3
      2470370.21     13823715.59      2469484.76     13823637.47
      2468808.79     13823659.13
#Sta/Elev= 30
  4251.5  462.83  4408.6  461.93  4477.6  462.52    4578  461.08  4758.7  457.32
  4818.9  457.17    4853   455.2  4909.3  453.17  4919.3  451.41  4949.4  450.44
  4969.5  446.33  4994.2  445.75  4994.4  445.25  4998.2  445.75  5009.6  445.89
  5019.7  447.86  5029.7  451.66  5039.8  452.14  5150.2  451.67  5190.2  453.14
  5250.2  451.59  5260.2  450.61  5290.2  452.43  5310.8  452.49  5330.2   451.1
  5340.2  452.18  5440.3  455.69  5450.3  456.61  5710.4  465.05  5816.7  470.06
#Mann= 6 ,-1 , 0
  4251.5     .05       0  4408.6     .07       0    4853      .1       0
  4994.2     .05       0  4998.2      .1       0  5310.8     .05       0
Bank Sta=4994.2,4998.2
XS Rating Curve= 0 ,0
Exp/Cntr=0.3,0.1

Type RM Length L Ch R = 1 ,19199   ,447,447,447
BEGIN DESCRIPTION:
X18446
END DESCRIPTION:
XS GIS Cut Line= 2
      2470266.03     13823225.14      2468799.48      13823298.9
#Sta/Elev= 30
  4389.5  459.09  4460.6  459.25  4640.7  455.05  4794.9  452.81  4841.1  451.52
  4880.3  446.07  4885.3  447.59  4891.2  444.81  4911.2  445.52  4921.2  448.77
  4941.2  448.13  4961.3  444.01  4969.3  443.79  4969.5  443.29  4973.3  443.79
  5021.3     446  5031.3  448.12  5041.4   448.7  5121.5  446.83  5151.5  447.45
  5171.5  445.65  5191.5  447.07  5241.6  445.98  5291.7  447.62  5331.7  444.01
  5363.3  446.27  5381.8  447.77  5612.1  455.89  5678.9  459.59  5857.9  464.91
#Mann= 6 ,-1 , 0
  4389.5     .05       0  4640.7     .07       0  4794.9      .1       0
  4969.3     .05       0  4973.3      .1       0  5363.3     .05       0
Bank Sta=4969.3,4973.3
XS Rating Curve= 0 ,0
Exp/Cntr=0.3,0.1

Type RM Length L Ch R = 1 ,18752   ,332,332,332
BEGIN DESCRIPTION:
X18447
END DESCRIPTION:
XS GIS Cut Line= 3
      2470313.73     13822977.74      2469376.25     13822916.98
      2468818.18     13823051.09
#Sta/Elev= 30
  4068.8  456.93  4157.7  457.27  4227.9  456.57  4338.1  453.33  4358.1  452.03
  4378.2  452.06  4401.8  451.21  4468.4  449.39  4551.2  448.15  4608.7  447.51
  4658.8  445.83  4698.8  445.92  4728.9  443.96    4956  443.79  4956.2  443.29
  4959.7  443.29    4960  443.79  4995.3  444.18  5011.5  444.27  5017.9  445.53
  5030.1  445.81  5050.7  444.06  5059.9  444.64  5071.2  446.62  5096.8  447.83
  5174.1   450.6  5196.1  450.87    5364  457.07  5472.3   462.5  5582.2  465.73
#Mann= 7 ,-1 , 0
  4068.8     .05       0  4401.8     .07       0  4551.2      .1       0
    4956     .05       0    4960      .1       0  4995.3     .15       0
  5096.8     .05       0
Bank Sta=4956,4960
XS Rating Curve= 0 ,0
Exp/Cntr=0.3,0.1

Type RM Length L Ch R = 1 ,18420   ,103,103,103
BEGIN DESCRIPTION:
X18448
END DESCRIPTION:
XS GIS Cut Line= 3
      2470339.83     13822856.23      2469450.04     13822630.52
      2468759.92     13822773.75
#Sta/Elev= 30
  4067.2  454.15    4172  454.83  4247.6  454.29  4357.4  451.35  4494.6  447.53
  4535.6  445.62  4598.3  444.17  4604.6  444.64  4639.6  443.75  4938.2  444.09
  4963.5  443.92  5005.7  444.01  5026.9  443.71  5027.2  443.21  5030.7  443.21
  5030.9  443.71  5039.3   443.8  5051.6  443.99  5079.1  446.14  5102.7   446.8
  5112.9  447.65  5129.2  450.83  5229.5  453.78  5245.6  454.82  5266.1  454.85
  5296.7  456.27  5374.8  458.26  5541.8  460.66  5646.5  464.26    5690  465.87
#Mann= 10 ,-1 , 0
  4067.2     .05       0  4357.4     .07       0  4604.6      .1       0
  4938.2     .15       0  4963.5    .035       0  5005.7     .15       0
  5026.9    .035       0  5030.9     .15       0  5039.3     .05       0
  5646.5    .035       0
Bank Sta=5026.9,5030.9
XS Rating Curve= 0 ,0
Exp/Cntr=0.3,0.1

Type RM Length L Ch R = 1 ,18317   ,139,139,139
BEGIN DESCRIPTION:
Chalk Hollow 35.2
END DESCRIPTION:
XS GIS Cut Line= 5
      2470163.16     13822725.54      2469604.43     13822555.49
      2469471.76     13822555.49      2469238.17     13822630.24
      2468959.89     13822665.72
#Sta/Elev= 30
  4305.5  453.04  4376.7  451.63  4496.6  447.66  4570.7  447.69  4784.4  447.84
  4794.9  446.65  4800.7  444.88    4801  444.38  4804.5  444.38  4804.7  444.88
  4807.9  447.98    4868  448.05  4878.9  448.45  5067.9  449.47  5073.2  449.08
  5100.1  449.51  5105.3  449.23  5144.8  450.11  5164.4   450.1  5176.3  450.61
  5196.6  450.35  5207.8  451.33  5249.8  451.91  5264.4   452.8  5280.7  452.94
  5300.9  454.34  5425.3  456.78    5432  457.23  5505.2  458.33    5548   458.3
#Mann= 5 ,-1 , 0
  4305.5     .07       0  4570.7    .035       0  4800.7    .035       0
  4804.7    .035       0  5264.4     .05       0
Bank Sta=4800.7,4804.7
XS Rating Curve= 0 ,0
Exp/Cntr=0.3,0.1

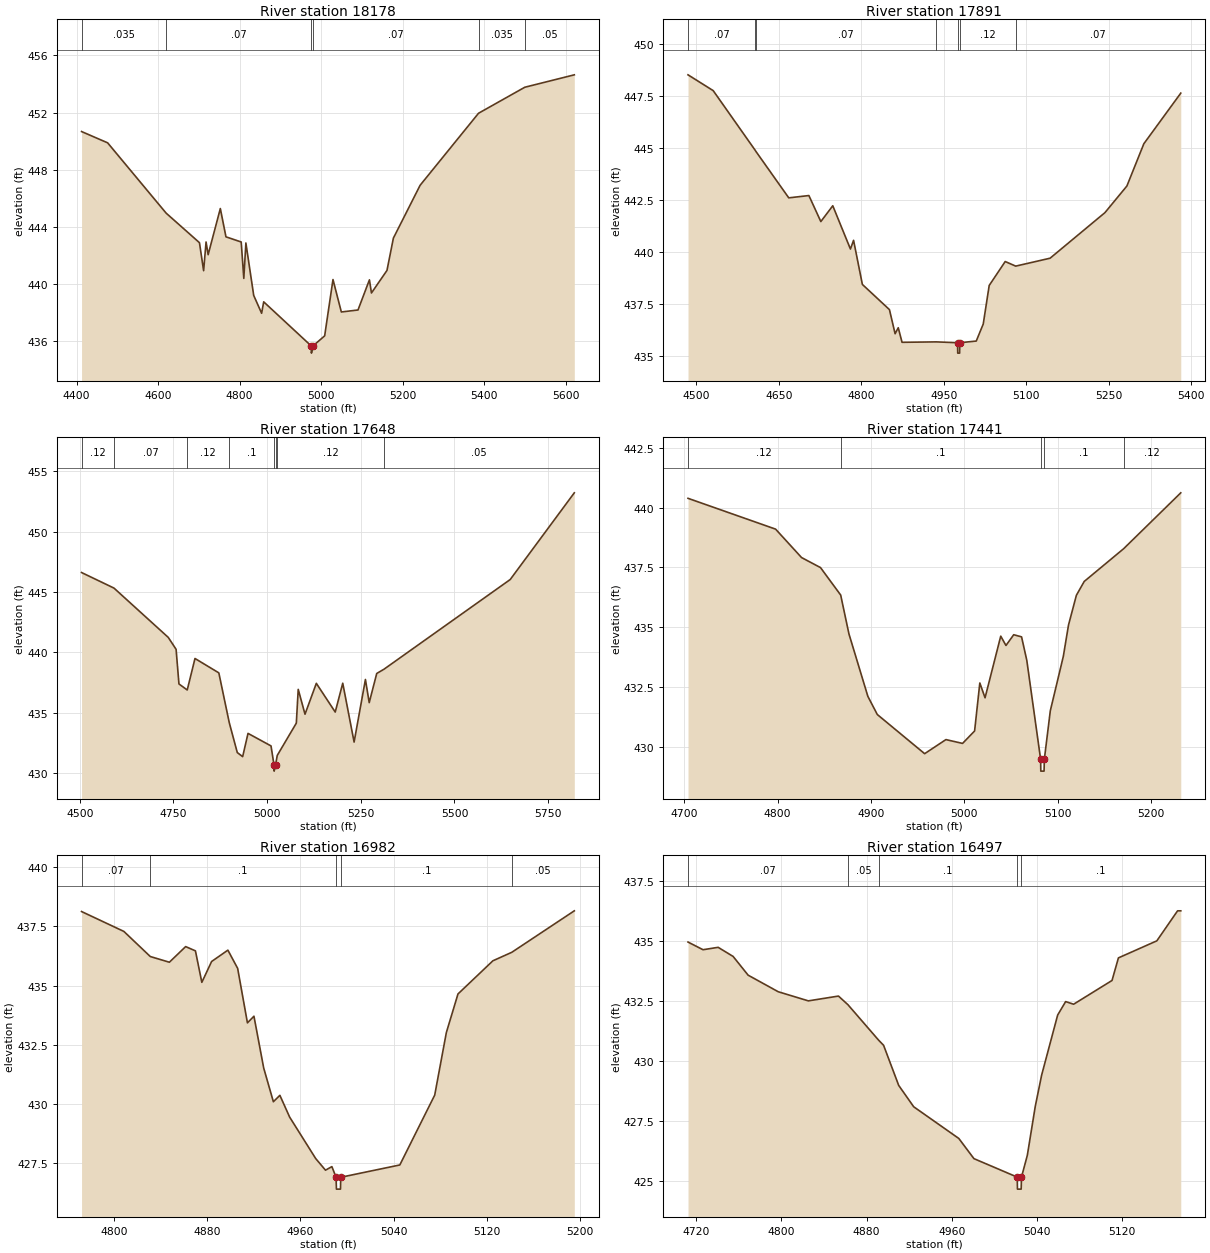
Type RM Length L Ch R = 1 ,18178   ,287,287,287
BEGIN DESCRIPTION:
X18449
END DESCRIPTION:
XS GIS Cut Line= 3
      2470157.53     13822595.81      2469506.46     13822452.57
      2468972.57     13822548.06
#Sta/Elev= 30
  4412.3  450.67  4476.3  449.88  4619.8  444.96  4701.6  442.89  4711.8  440.93
  4717.8  442.94  4722.9  442.05  4752.8  445.28  4766.6   443.3    4804  442.94
  4810.4  440.39  4815.5  442.87  4834.7   439.2  4854.1  437.95  4859.2  438.75
    4976  435.66  4976.3  435.16    4980  435.66  5008.8  436.37  5029.2  440.31
  5049.7  438.04  5090.6  438.18  5118.6  440.29  5123.6  439.37  5161.7  440.95
  5177.4  443.21    5243  446.91  5386.3  451.95  5499.8  453.77  5621.3  454.64
#Mann= 6 ,-1 , 0
  4412.3    .035       0  4619.8     .07       0    4976     .05       0
    4980     .07       0  5386.3    .035       0  5499.8     .05       0
Bank Sta=4976,4980
XS Rating Curve= 0 ,0
Exp/Cntr=0.3,0.1

Type RM Length L Ch R = 1 ,17891   ,243,243,243
BEGIN DESCRIPTION:
Chalk Hollow 35.0
END DESCRIPTION:
XS GIS Cut Line= 3
      2470075.02     13822475.01        2469625.       13822225.
        2469275.       13822375.
#Sta/Elev= 30
  4485.1  448.52  4530.9  447.76  4606.8  444.91  4609.3  444.81  4668.2  442.61
  4704.8  442.72  4726.5  441.47  4748.2  442.23  4780.3  440.15    4786  440.57
    4802  438.45  4851.2  437.24  4861.5  436.08  4867.2  436.37  4874.1  435.67
  4936.2  435.69    4975  435.65  4975.3  435.15  4978.8  435.15    4979  435.65
    5009  435.73  5021.7  436.55  5032.5   438.4  5061.6  439.55  5080.7  439.33
  5143.2  439.71  5242.9   441.9  5282.8  443.18  5313.6  445.21  5380.7  447.64
#Mann= 7 ,-1 , 0
  4485.1     .07       0  4606.8     .12       0  4609.3     .07       0
  4936.2     .12       0    4975     .05       0    4979     .12       0
  5080.7     .07       0
Bank Sta=4975,4979
XS Rating Curve= 0 ,0
Exp/Cntr=0.3,0.1

Type RM Length L Ch R = 1 ,17648   ,207,207,207
BEGIN DESCRIPTION:
X18450
END DESCRIPTION:
XS GIS Cut Line= 3
      2470105.42     13822331.04      2469749.52     13822022.88
      2468911.85     13821918.72
#Sta/Elev= 30
  4504.9  446.62  4591.4  445.33  4736.3  441.24  4757.2  440.25  4764.8  437.38
  4786.9  436.88  4807.6  439.49  4871.2   438.3  4899.2  434.15  4920.5  431.69
  4934.8  431.35  4949.1  433.28  5010.5  432.24  5018.5  430.65  5018.8  430.15
  5022.5  430.65  5027.1  431.45    5078  434.13  5083.1  436.93  5101.2  434.87
  5131.4  437.43  5181.8  435.05  5201.9  437.44  5232.2  432.56  5262.4  437.75
  5272.5  435.83  5292.6  438.25  5311.9   438.6  5648.8  446.04  5819.8  453.23
#Mann= 8 ,-1 , 0
  4504.9     .12       0  4591.4     .07       0  4786.9     .12       0
  4899.2      .1       0  5018.5     .05       0  5022.5      .1       0
  5027.1     .12       0  5311.9     .05       0
Bank Sta=5018.5,5022.5
XS Rating Curve= 0 ,0
Exp/Cntr=0.3,0.1

Type RM Length L Ch R = 1 ,17441   ,459,459,459
BEGIN DESCRIPTION:
Chalk Hollow 34.0
END DESCRIPTION:
XS GIS Cut Line= 3
      2469974.98       13821875.        2469675.       13821825.
      2469475.02     13821725.01
#Sta/Elev= 30
    4704  440.39  4797.8   439.1  4825.6  437.91  4845.9  437.49  4867.5  436.34
  4876.3  434.72  4896.6   432.1  4906.7  431.34  4957.4   429.7  4980.2  430.29
    4998  430.13  5010.9  430.65  5016.5  432.66  5022.1  432.04  5038.9  434.62
  5044.5  434.23  5052.8  434.68  5061.2  434.59  5066.8  433.61  5081.6  429.47
  5081.8  428.97  5085.3  428.97  5085.6  429.47    5092   431.5  5105.9  433.77
  5111.5  435.09  5119.9  436.33  5128.3  436.91  5170.5  438.28  5231.7  440.62
#Mann= 5 ,-1 , 0
    4704     .12       0  4867.5      .1       0  5081.6     .05       0
  5085.6      .1       0  5170.5     .12       0
Bank Sta=5081.6,5085.6
XS Rating Curve= 0 ,0
Exp/Cntr=0.3,0.1

Type RM Length L Ch R = 1 ,16982   ,485,485,485
BEGIN DESCRIPTION:
Chalk Hollow 33.0
END DESCRIPTION:
XS GIS Cut Line= 3
      2469975.02     13821525.01        2469775.       13821425.
      2469575.03       13821425.
#Sta/Elev= 30
  4771.8  438.13  4808.2  437.29  4830.9  436.23  4847.3  435.99  4861.3  436.65
  4869.7  436.47  4875.2  435.14  4883.6  436.02  4897.6   436.5    4906  435.73
  4914.4  433.43    4920  433.71  4928.4  431.52  4936.7   430.1  4942.3  430.37
  4950.7  429.45  4973.1   427.7  4981.5  427.21    4987  427.36  4990.6  426.91
  4990.9  426.41  4994.4  426.41  4994.6  426.91  5045.4  427.43  5075.4  430.38
  5085.4  433.02  5095.4  434.65  5125.4  436.05  5141.7  436.41  5195.4  438.16
#Mann= 5 ,-1 , 0
  4771.8     .07       0  4830.9      .1       0  4990.6     .05       0
  4994.6      .1       0  5141.7     .05       0
Bank Sta=4990.6,4994.6
XS Rating Curve= 0 ,0
Exp/Cntr=0.3,0.1

Type RM Length L Ch R = 1 ,16497   ,439,439,439
BEGIN DESCRIPTION:
Chalk Hollow 32.0
END DESCRIPTION:
XS GIS Cut Line= 3
      2470074.98     13821174.98        2469875.       13820975.
      2469724.99       13820875.
#Sta/Elev= 30
  4712.2  434.95  4726.3  434.63  4740.5  434.73  4754.6  434.35  4768.7  433.57
    4797  432.88  4825.3   432.5  4853.6   432.7  4862.5  432.34  4891.4  430.86
    4896  430.65  4910.2  428.98  4924.3  428.09  4966.7  426.77  4980.9  425.93
  5021.6  425.16  5021.8  424.66  5025.3  424.66  5025.6  425.16  5031.1  426.07
  5038.6  428.12  5044.6  429.42  5059.6  431.91  5067.1  432.47  5074.6  432.36
  5110.7  433.35  5116.7  434.29  5152.8     435  5172.3  436.25  5175.3  436.25
#Mann= 5 ,-1 , 0
  4712.2     .07       0  4862.5     .05       0  4891.4      .1       0
  5021.6     .05       0  5025.6      .1       0
Bank Sta=5021.6,5025.6
XS Rating Curve= 0 ,0
Exp/Cntr=0.3,0.1