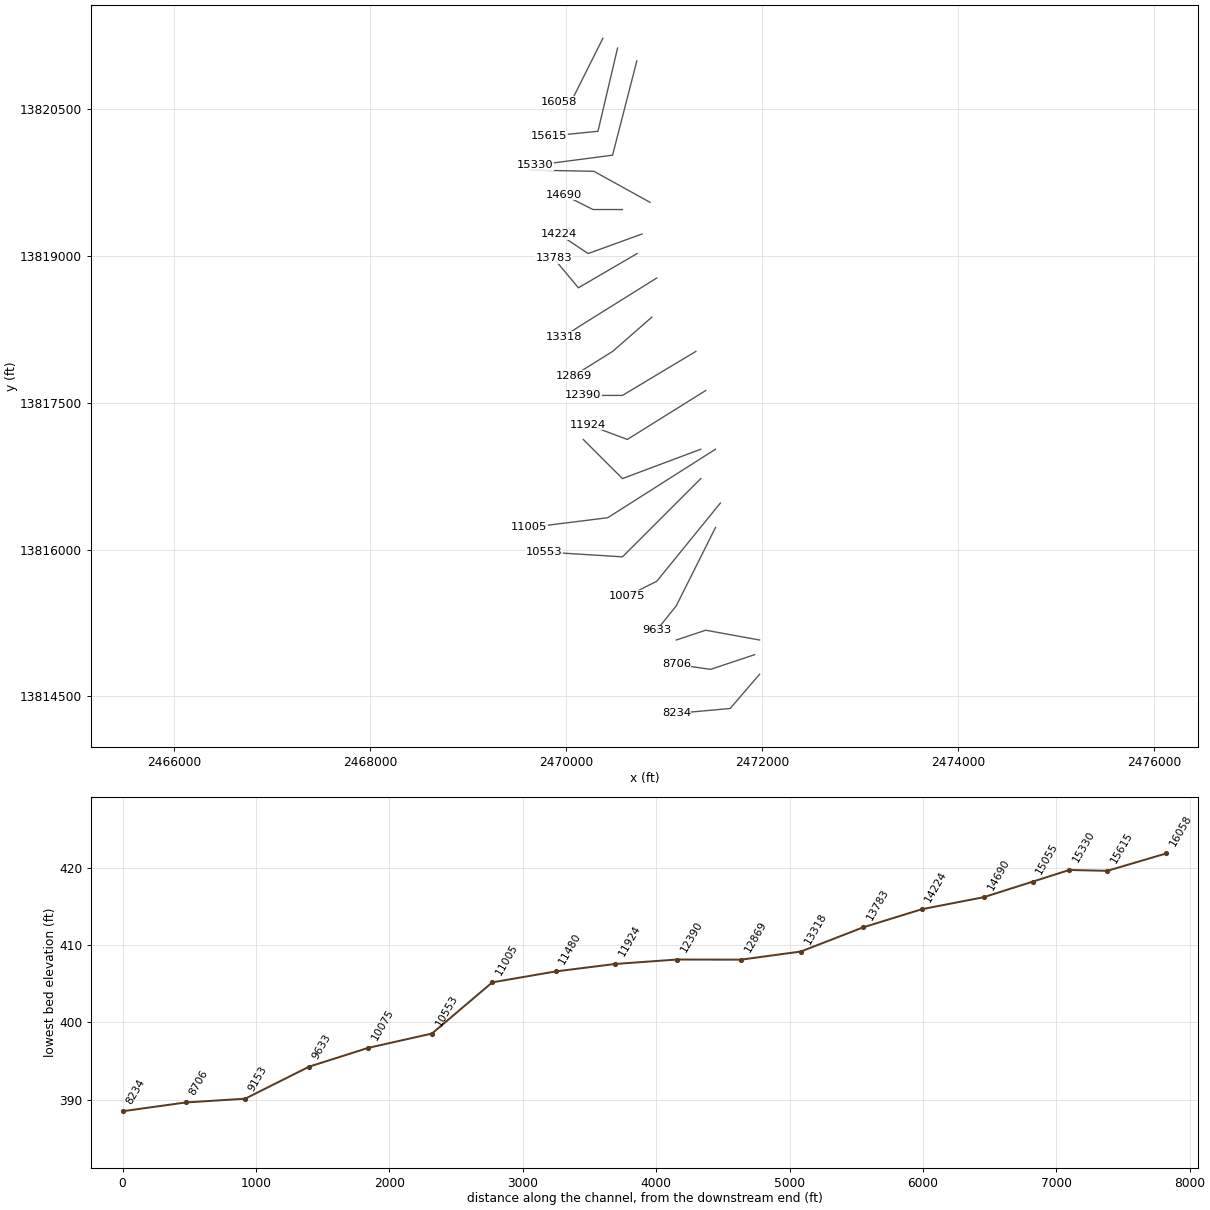
HEC-RAS study Chalk Hollow.prj: Chalk Hollow Base Level Engineering

--- Chalk Hollow.g01 (geometry) --- (continued)

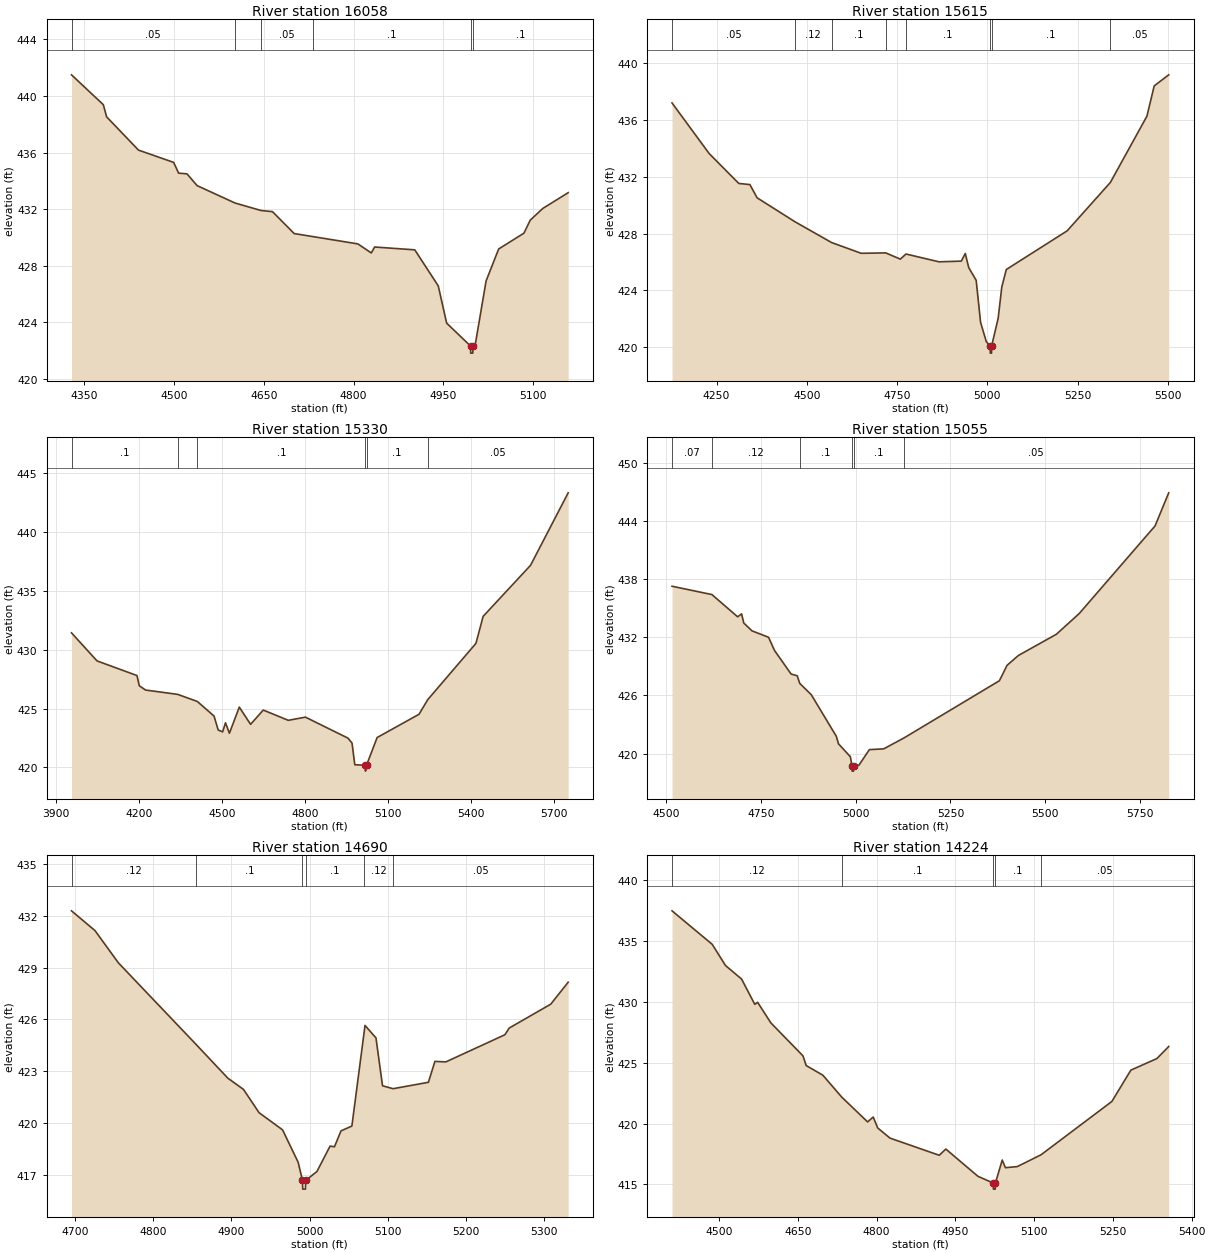
Type RM Length L Ch R = 1 ,16058   ,443,443,443
BEGIN DESCRIPTION:
Chalk Hollow 31.0
END DESCRIPTION:
XS GIS Cut Line= 3
      2470374.98     13821224.96        2470075.       13820625.
      2469924.99       13820575.
#Sta/Elev= 30
  4329.2   441.5  4382.3  439.39  4387.8  438.53    4441  436.18  4499.7  435.31
    4508  434.55    4522   434.5  4538.8  433.67  4602.1  432.44  4645.5  431.91
  4664.6  431.83  4700.9  430.28  4731.6  430.07  4807.1  429.55  4829.5  428.91
  4835.1  429.33  4902.1  429.13  4941.3  426.58  4955.3  423.95  4995.2  422.33
  4995.4  421.83  4998.9  421.83  4999.2  422.33  5002.6  422.33  5021.1  426.93
  5042.1  429.19  5084.3  430.31  5094.8  431.23  5115.9  432.06  5158.1  433.17
#Mann= 6 ,-1 , 0
  4329.2     .05       0  4602.1     .07       0  4645.5     .05       0
  4731.6      .1       0  4995.2     .05       0  4999.2      .1       0
Bank Sta=4995.2,4999.2
XS Rating Curve= 0 ,0
Exp/Cntr=0.3,0.1

Type RM Length L Ch R = 1 ,15615   ,285,285,285
BEGIN DESCRIPTION:
Chalk Hollow 30.0
END DESCRIPTION:
XS GIS Cut Line= 3
      2470524.99     13821124.97        2470325.       13820275.
      2469824.98       13820225.
#Sta/Elev= 30
  4126.8   437.2  4229.5  433.64  4311.7  431.53  4342.5  431.45  4362.4  430.52
  4466.8  428.84  4568.6  427.37  4650.7  426.61  4718.6  426.64  4759.2   426.2
  4774.8  426.56  4866.4  426.01  4928.1  426.06    4939   426.6  4948.6   425.6
  4969.2  424.71  4981.4  421.75  4997.4  420.38    5008  420.08  5008.3  419.58
  5011.8  419.58    5012  420.08  5030.1  422.03  5040.2  424.24  5052.7  425.47
  5221.1  428.19  5340.9   431.6  5442.2  436.27  5462.3   438.4  5502.5  439.18
#Mann= 8 ,-1 , 0
  4126.8     .05       0  4466.8     .12       0  4568.6      .1       0
  4718.6     .12       0  4774.8      .1       0    5008     .05       0
    5012      .1       0  5340.9     .05       0
Bank Sta=5008,5012
XS Rating Curve= 0 ,0
Exp/Cntr=0.3,0.1

Type RM Length L Ch R = 1 ,15330   ,275,275,275
BEGIN DESCRIPTION:
X18451
END DESCRIPTION:
XS GIS Cut Line= 3
      2470721.75     13820994.27      2470474.34     13820030.69
      2469680.07     13819926.53
#Sta/Elev= 30
  3955.4  431.42  4047.8  429.04  4192.1   427.8  4200.5  426.93  4223.1  426.57
  4339.6   426.2  4410.4   425.6  4470.9  424.36  4485.8  423.18  4501.8  423.02
  4512.2  423.79  4526.5  422.91  4562.1  425.12  4602.9  423.66  4648.8  424.87
  4739.3     424  4801.2  424.27  4955.1  422.49  4969.7  422.07  4979.8  420.23
  5018.2  420.19  5018.4  419.69  5022.2  420.19  5060.5  422.54  5211.8  424.51
  5243.4  425.75  5417.8  430.53  5443.8  432.82  5615.2  437.15  5751.3   443.3
#Mann= 6 ,-1 , 0
  3955.4      .1       0  4339.6     .12       0  4410.4      .1       0
  5018.2     .05       0  5022.2      .1       0  5243.4     .05       0
Bank Sta=5018.2,5022.2
XS Rating Curve= 0 ,0
Exp/Cntr=0.3,0.1

Type RM Length L Ch R = 1 ,15055   ,365,365,365
BEGIN DESCRIPTION:
X18452
END DESCRIPTION:
XS GIS Cut Line= 3
      2470856.26     13819548.94      2470283.37     13819865.76
      2469628.96     13819878.77
#Sta/Elev= 30
  4516.3  437.28  4621.4  436.42  4689.3  434.12  4699.7  434.43  4705.4  433.48
  4727.1  432.67  4770.7  432.01  4786.7  430.63  4830.2  428.21  4846.3  428.03
  4852.9  427.25  4883.4  426.07  4949.3  421.78  4955.1     421  4986.3  419.67
  4990.9  418.68  4991.1  418.18  4994.6  418.18  4994.9  418.68  5008.9  418.79
  5036.4   420.4  5074.2  420.48  5127.4   421.6  5379.3  427.52  5399.4  429.11
  5429.4  430.13  5529.4  432.32  5589.4  434.45  5789.5  443.51  5825.5  446.93
#Mann= 6 ,-1 , 0
  4516.3     .07       0  4621.4     .12       0  4852.9      .1       0
  4990.9     .05       0  4994.9      .1       0  5127.4     .05       0
Bank Sta=4990.9,4994.9
XS Rating Curve= 0 ,0
Exp/Cntr=0.3,0.1

Type RM Length L Ch R = 1 ,14690   ,466,466,466
BEGIN DESCRIPTION:
Chalk Hollow 29.0
END DESCRIPTION:
XS GIS Cut Line= 3
      2470575.03       13819475.        2470275.       13819475.
      2469975.04     13819624.98
#Sta/Elev= 30
  4695.4  432.28  4725.4  431.14  4755.4  429.27  4854.8  424.55  4895.4   422.6
  4915.4  421.95  4935.4   420.6  4965.4  419.61  4985.4  417.73  4990.9  416.68
  4991.2  416.18  4994.7  416.18  4994.9  416.68  5009.4   417.2  5026.2  418.67
  5031.8  418.63  5040.2  419.55  5054.1  419.83  5069.2  425.06  5070.9  425.65
  5084.9  424.93  5093.3  422.16  5106.8  421.99    5152  422.36  5160.3  423.57
  5174.3  423.54  5249.8  425.11  5255.4   425.5  5308.5  426.88  5330.8  428.15
#Mann= 6 ,-1 , 0
  4695.4     .12       0  4854.8      .1       0  4990.9     .05       0
  4994.9      .1       0  5069.2     .12       0  5106.8     .05       0
Bank Sta=4990.9,4994.9
XS Rating Curve= 0 ,0
Exp/Cntr=0.3,0.1

Type RM Length L Ch R = 1 ,14224   ,441,441,441
BEGIN DESCRIPTION:
Chalk Hollow 28.0
END DESCRIPTION:
XS GIS Cut Line= 3
      2470775.02     13819225.01        2470225.       13819025.
      2469925.01     13819224.99
#Sta/Elev= 30
  4410.5  437.47    4487  434.72  4512.3  432.98  4542.9  431.87  4568.1  429.79
  4573.5  429.96  4598.7  428.27  4659.9  425.56  4665.9  424.77  4697.8  423.97
  4733.8  422.17  4782.9  420.14  4793.6  420.54  4802.2  419.64  4825.5  418.81
  4919.3   417.4  4931.9  417.91  4993.1  415.67  5022.3  415.12  5022.5  414.62
    5026  414.62  5026.3  415.12  5039.3  417.01  5045.3  416.38  5067.9  416.47
  5113.2  417.44  5248.1  421.82  5284.2  424.39  5333.8  425.34  5356.3  426.33
#Mann= 5 ,-1 , 0
  4410.5     .12       0  4733.8      .1       0  5022.3     .05       0
  5026.3      .1       0  5113.2     .05       0
Bank Sta=5022.3,5026.3
XS Rating Curve= 0 ,0
Exp/Cntr=0.3,0.1

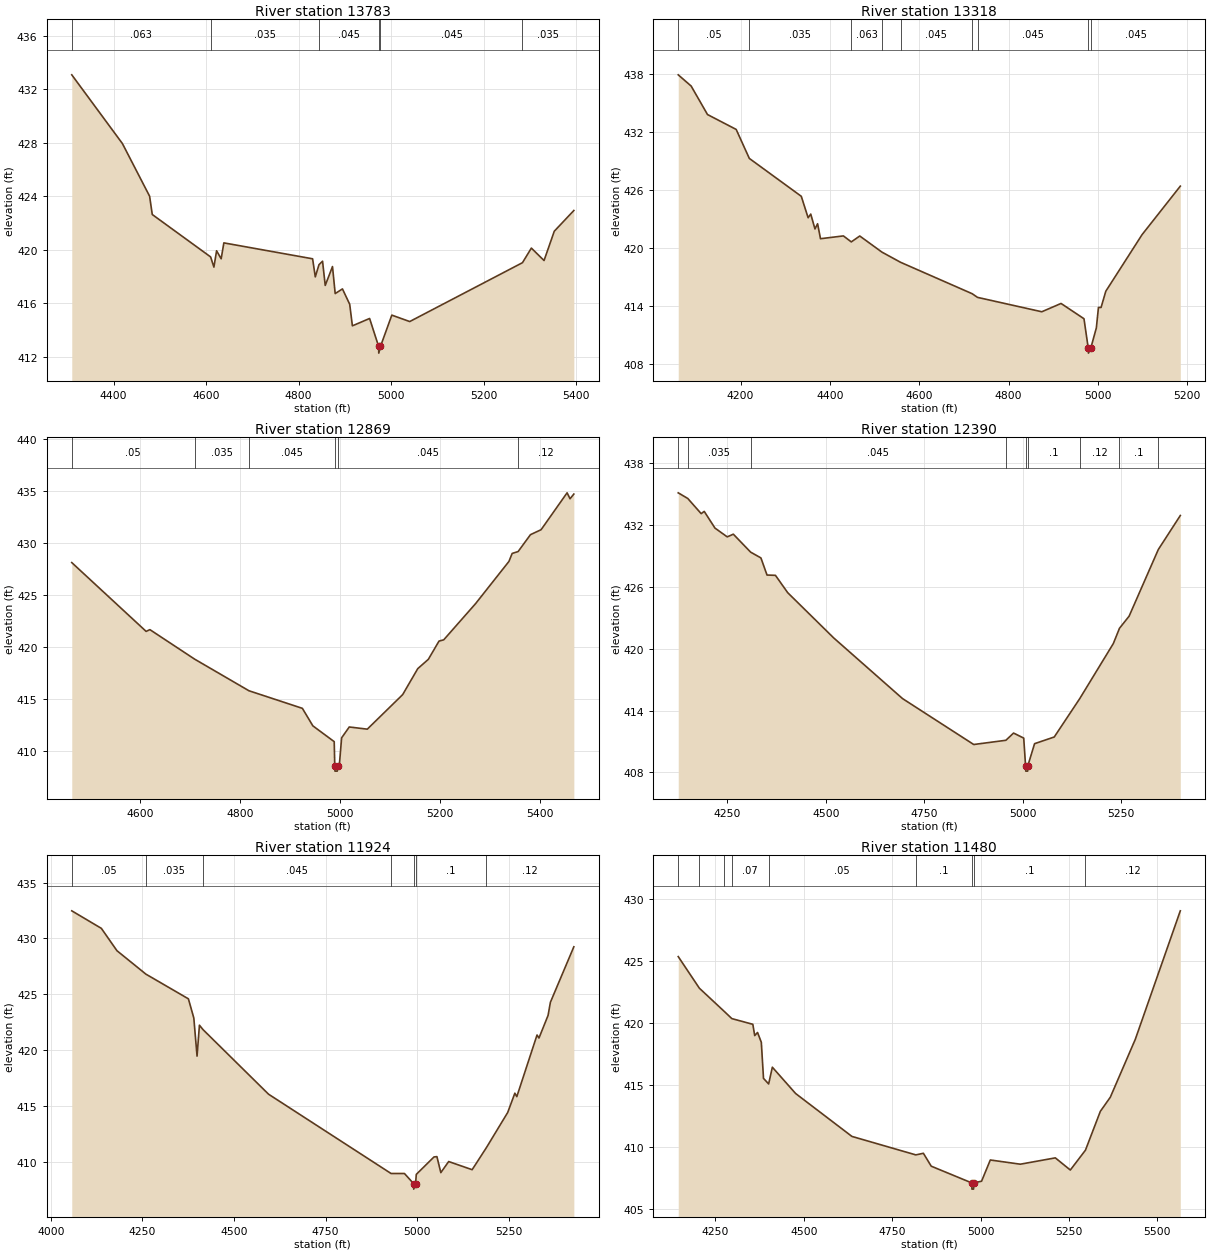
Type RM Length L Ch R = 1 ,13783   ,465,465,465
BEGIN DESCRIPTION:
Chalk Hollow 27.0
END DESCRIPTION:
XS GIS Cut Line= 3
      2470724.97     13819024.98        2470125.       13818675.
        2469875.       13818975.
#Sta/Elev= 30
  4309.7  433.07  4419.2  427.93  4477.9     424  4483.7  422.63  4609.8  419.46
  4616.9   418.7  4622.7  419.92  4632.6  419.32  4638.4  420.51  4830.2  419.32
    4836  417.97    4844  418.88  4851.7  419.14  4857.5  417.33  4873.2  418.74
    4879  416.72  4894.7  417.07  4910.4  415.92  4916.2  414.31  4953.4  414.86
  4972.9  412.77  4973.2  412.27  4976.9  412.77  5001.4  415.11  5040.1  414.63
  5283.8  419.03    5303  420.12  5330.4  419.19  5352.5  421.38  5394.8  422.93
#Mann= 6 ,-1 , 0
  4309.7    .063       0  4609.8    .035       0    4844    .045       0
  4972.9    .045       0  4976.9    .045       0  5283.8    .035       0
Bank Sta=4972.9,4976.9
XS Rating Curve= 0 ,0
Exp/Cntr=0.3,0.1

Type RM Length L Ch R = 1 ,13318   ,449,449,449
BEGIN DESCRIPTION:
Chalk Hollow 26.0
END DESCRIPTION:
XS GIS Cut Line= 3
      2470925.03     13818775.02        2470125.       13818275.
      2469975.01       13818175.
#Sta/Elev= 30
  4060.5  437.96  4089.4   436.8    4126  433.85  4190.2  432.31  4219.6  429.31
  4335.9  425.39  4351.2  423.17  4357.1  423.55  4366.5  422.01  4372.4  422.55
  4378.9     421  4430.2  421.29  4447.8  420.67  4466.8  421.28  4516.5  419.61
  4558.1  418.56  4718.3  415.31  4730.3  414.93  4874.2  413.44  4917.3   414.3
  4968.6  412.72  4978.2  409.66  4978.6  409.16  4983.7  409.66  4996.3  411.77
    5001  413.89  5006.9  413.89  5017.4  415.56  5098.6  421.42  5184.2  426.44
#Mann= 9 ,-1 , 0
  4060.5     .05       0  4219.6    .035       0  4447.8    .063       0
  4516.5    .035       0  4558.1    .045       0  4718.3    .035       0
  4730.3    .045       0  4978.2    .045       0  4983.7    .045       0
Bank Sta=4978.2,4983.7
XS Rating Curve= 0 ,0
Exp/Cntr=0.3,0.1

Type RM Length L Ch R = 1 ,12869   ,479,479,479
BEGIN DESCRIPTION:
Chalk Hollow 25.0
END DESCRIPTION:
XS GIS Cut Line= 3
      2470875.01     13818375.01        2470475.       13818025.
      2470075.02     13817775.01
#Sta/Elev= 30
  4464.1  428.14  4612.7  421.53  4620.2   421.7  4709.8  418.86  4818.1  415.83
  4924.9  414.14  4945.8  412.46  4988.5  410.94  4989.6  408.61    4990  408.11
  4994.6  408.11  4995.1  408.61  4998.6  408.61  5003.3  411.31  5018.6  412.35
  5054.6  412.14  5125.3  415.46  5155.4  417.95  5176.6  418.85  5197.9   420.6
  5207.3  420.72    5271   424.2  5337.6  428.25  5344.1  429.02    5356   429.2
  5380.6  430.82  5401.9   431.3  5453.8  434.84  5459.7  434.27  5467.3  434.72
#Mann= 6 ,-1 , 0
  4464.1     .05       0  4709.8    .035       0  4818.1    .045       0
  4989.6    .045       0  4995.1    .045       0    5356     .12       0
Bank Sta=4989.6,4995.1
XS Rating Curve= 0 ,0
Exp/Cntr=0.3,0.1

Type RM Length L Ch R = 1 ,12390   ,466,466,466
BEGIN DESCRIPTION:
Chalk Hollow 24.0
END DESCRIPTION:
XS GIS Cut Line= 3
      2471324.97     13818024.98        2470575.       13817575.
      2470175.01       13817575.
#Sta/Elev= 30
  4125.4  435.11  4149.7  434.56  4183.7  433.09  4191.4  433.31  4218.7  431.69
  4249.8  430.84  4265.3   431.1  4309.2  429.36  4335.3   428.8  4350.8  427.14
  4372.2  427.11  4403.3  425.43  4519.9  421.05  4694.9  415.16  4875.6  410.71
  4957.2  411.12  4976.7  411.82  5002.5  411.33  5007.2  408.63  5007.7  408.13
  5012.4  408.13  5012.8  408.63    5030  410.79    5080  411.44  5144.7  415.16
    5230   420.5  5245.6  421.98    5270  423.15  5344.1  429.61    5400  432.91
#Mann= 9 ,-1 , 0
  4125.4     .12       0  4149.7    .035       0  4309.2    .045       0
  4957.2      .1       0  5007.2     .05       0  5012.8      .1       0
  5144.7     .12       0  5245.6      .1       0  5344.1     .12       0
Bank Sta=5007.2,5012.8
XS Rating Curve= 0 ,0
Exp/Cntr=0.3,0.1

Type RM Length L Ch R = 1 ,11924   ,444,444,444
BEGIN DESCRIPTION:
Chalk Hollow 23.0
END DESCRIPTION:
XS GIS Cut Line= 3
      2471425.04     13817625.02        2470625.       13817125.
      2470225.04     13817274.99
#Sta/Elev= 30
    4057  432.47  4137.8   430.9  4180.3   428.9  4259.4   426.8  4375.4  424.59
  4390.2  422.87    4399  419.46  4405.5  422.23  4415.1  421.84  4594.2  416.05
  4928.6  408.95  4965.1  408.95    4990  408.05  4990.4  407.55  4995.6  408.05
  4997.5  408.87  5045.8  410.43  5053.8  410.46  5064.5  409.03  5085.9  410.02
    5150  409.29  5188.8  411.26    5247  414.41  5266.6  416.14  5271.9  415.83
  5327.1  421.35  5332.4  421.08  5357.3  423.11  5363.6  424.28  5427.6  429.25
#Mann= 7 ,-1 , 0
    4057     .05       0  4259.4    .035       0  4415.1    .045       0
  4928.6      .1       0    4990     .05       0  4995.6      .1       0
  5188.8     .12       0
Bank Sta=4990,4995.6
XS Rating Curve= 0 ,0
Exp/Cntr=0.3,0.1

Type RM Length L Ch R = 1 ,11480   ,475,475,475
BEGIN DESCRIPTION:
Chalk Hollow 22.0
END DESCRIPTION:
XS GIS Cut Line= 3
      2471375.04     13817025.01        2470575.       13816725.
      2470175.02     13817124.98
#Sta/Elev= 30
    4145  425.34  4204.8  422.79  4275.5  420.91  4296.6  420.34    4356  419.88
  4361.3  418.97  4369.3  419.22    4380  418.43  4386.2  415.52  4400.7  415.07
  4411.2  416.42    4477   414.3  4636.3  410.84    4817  409.35  4838.4  409.48
  4860.6  408.44  4975.3  407.09  4975.7  406.59  4980.4  406.59  4980.9  407.09
    5003  407.23  5027.7  408.94  5112.6   408.6  5211.6  409.11    5254  408.13
  5296.8  409.73  5338.9  412.86  5367.1     414  5437.8  418.67  5565.1  429.03
#Mann= 9 ,-1 , 0
    4145    .035       0  4204.8     .05       0  4275.5    .035       0
  4296.6     .07       0  4400.7     .05       0    4817      .1       0
  4975.3     .05       0  4980.9      .1       0  5296.8     .12       0
Bank Sta=4975.3,4980.9
XS Rating Curve= 0 ,0
Exp/Cntr=0.3,0.1

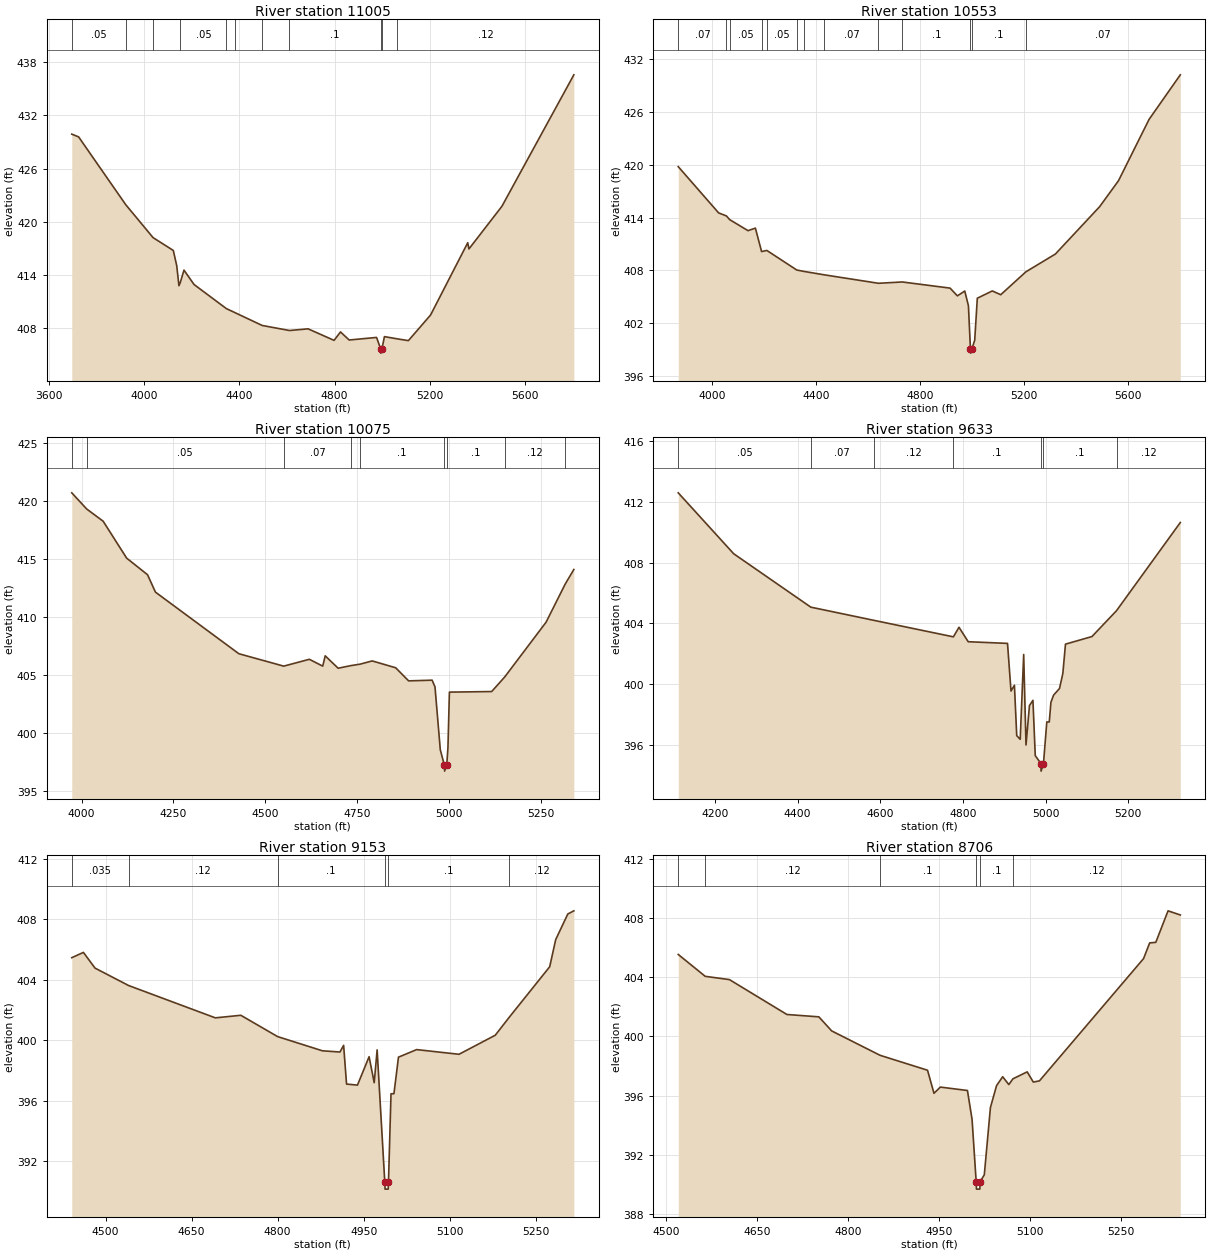
Type RM Length L Ch R = 1 ,11005   ,452,452,452
BEGIN DESCRIPTION:
Chalk Hollow 21.0
END DESCRIPTION:
XS GIS Cut Line= 3
      2471524.97     13817024.98        2470425.       13816325.
      2469625.04       13816225.
#Sta/Elev= 30
  3695.2  429.88    3724  429.57  3922.1  421.92  4036.8  418.21  4121.9  416.76
  4136.3  415.05  4145.6  412.78  4151.4  413.16  4166.8  414.54  4209.1  412.92
    4345   410.2  4380.8  409.75  4495.5   408.3  4610.2  407.73  4688.3  407.92
  4797.5  406.62  4824.6  407.57    4861  406.66  4976.2  406.95  4993.1  405.68
  4993.6  405.18  4998.9  405.68  5009.1  407.04  5063.4  406.79  5109.9  406.59
  5203.1  409.48  5359.3  417.63  5364.3  416.93  5502.9  421.74  5805.2  436.57
#Mann= 11 ,-1 , 0
  3695.2     .05       0  3922.1    .035       0  4036.8     .07       0
  4151.4     .05       0    4345    .035       0  4380.8     .05       0
  4495.5     .07       0  4610.2      .1       0  4993.1     .05       0
  4998.9      .1       0  5063.4     .12       0
Bank Sta=4993.1,4998.9
XS Rating Curve= 0 ,0
Exp/Cntr=0.3,0.1

Type RM Length L Ch R = 1 ,10553   ,478,478,478
BEGIN DESCRIPTION:
Chalk Hollow 20.0
END DESCRIPTION:
XS GIS Cut Line= 3
        2471375.       13816725.        2470575.       13815925.
      2469775.03       13815975.
#Sta/Elev= 30
  3869.6   419.8  4025.2  414.53  4055.1  414.19  4067.5  413.77  4138.3  412.51
  4166.6   412.8  4190.5  410.13  4210.7  410.26    4326  408.03    4354  407.87
  4432.4  407.48  4640.5  406.52  4732.3  406.67  4916.1  405.97  4944.4  405.09
  4972.7  405.64  4986.8  403.96  4994.5  399.07    4995  398.57  5000.3  399.07
    5011  400.04    5021  404.82  5078.6  405.65  5111.2  405.22  5208.2  407.83
  5321.6  409.85  5491.9  415.24  5564.6   418.2  5682.3  425.18  5802.5  430.25
#Mann= 13 ,-1 , 0
  3869.6     .07       0  4055.1    .035       0  4067.5     .05       0
  4190.5    .035       0  4210.7     .05       0    4326     .07       0
    4354     .05       0  4432.4     .07       0  4640.5     .12       0
  4732.3      .1       0  4994.5     .05       0  5000.3      .1       0
  5208.2     .07       0
Bank Sta=4994.5,5000.3
XS Rating Curve= 0 ,0
Exp/Cntr=0.3,0.1

Type RM Length L Ch R = 1 ,10075   ,442,442,442
BEGIN DESCRIPTION:
Chalk Hollow 19.0
END DESCRIPTION:
XS GIS Cut Line= 3
      2471575.01     13816475.02        2470925.       13815675.
      2470625.01       13815525.
#Sta/Elev= 30
  3973.3  420.71  4013.8  419.32  4058.8  418.26  4122.7  415.08  4179.5  413.65
    4201  412.15    4428  406.84  4550.1  405.77  4619.8  406.36  4656.2  405.77
  4662.9  406.66  4698.1  405.59  4733.6  405.82  4757.7  405.94  4790.8  406.22
  4854.7  405.63  4889.9   404.5  4953.8  404.56  4961.7  403.98  4976.1  398.56
  4987.3  397.22  4987.8  396.72  4993.6  397.22  4996.9  398.73  5000.9  403.53
  5115.9  403.58  5151.2  404.83    5264  409.56  5315.9  412.84  5339.5   414.1
#Mann= 9 ,-1 , 0
  3973.3     .07       0  4013.8     .05       0  4550.1     .07       0
  4733.6     .12       0  4757.7      .1       0  4987.3     .05       0
  4993.6      .1       0  5151.2     .12       0  5315.9     .07       0
Bank Sta=4987.3,4993.6
XS Rating Curve= 0 ,0
Exp/Cntr=0.3,0.1

Type RM Length L Ch R = 1 ,9633    ,480,480,480
BEGIN DESCRIPTION:
Chalk Hollow 18.0
END DESCRIPTION:
XS GIS Cut Line= 3
      2471524.99     13816224.98        2471125.       13815425.
      2470924.98     13815174.97
#Sta/Elev= 30
  4111.2  412.58  4245.3  408.58    4432  405.07  4583.6  404.21  4776.9  403.12
  4790.4  403.75  4812.7   402.8  4907.8  402.69  4916.2  399.56  4924.5  399.94
  4930.1  396.63  4938.5  396.39  4946.9  401.96  4952.5  396.02  4960.9  398.61
  4969.3  398.95  4974.9  395.32  4988.5   394.8    4989   394.3  4994.8   394.8
  5002.8  397.53  5008.8  397.53  5012.8  398.82  5019.2  399.29  5033.6  399.73
  5041.6  400.71    5048  402.64  5112.1  403.14  5171.5  404.84  5325.8  410.63
#Mann= 7 ,-1 , 0
  4111.2     .05       0    4432     .07       0  4583.6     .12       0
  4776.9      .1       0  4988.5     .05       0  4994.8      .1       0
  5171.5     .12       0
Bank Sta=4988.5,4994.8
XS Rating Curve= 0 ,0
Exp/Cntr=0.3,0.1

Type RM Length L Ch R = 1 ,9153    ,447,447,447
BEGIN DESCRIPTION:
Chalk Hollow 17.0
END DESCRIPTION:
XS GIS Cut Line= 3
      2471974.99       13815075.        2471425.       13815175.
      2471125.03     13815075.01
#Sta/Elev= 30
  4441.2  405.47  4461.5  405.82  4481.8  404.78  4540.2  403.63  4691.5  401.49
  4735.9  401.66    4800  400.25  4878.2  399.31  4908.7  399.23  4915.1  399.67
  4920.2  397.11  4939.2  397.04  4959.5  398.92  4968.4   397.2  4973.5  399.37
  4986.8  390.66  4987.3  390.16  4992.8  390.16  4993.3  390.66  4997.7  396.47
  5002.8  396.47  5010.7  398.89  5042.4  399.39  5116.2  399.08  5179.4  400.34
  5203.6  401.52  5274.3  404.87  5284.8  406.67  5305.9  408.36  5316.4  408.57
#Mann= 6 ,-1 , 0
  4441.2    .035       0  4540.2     .12       0    4800      .1       0
  4986.8     .05       0  4993.3      .1       0  5203.6     .12       0
Bank Sta=4986.8,4993.3
XS Rating Curve= 0 ,0
Exp/Cntr=0.3,0.1

Type RM Length L Ch R = 1 ,8706    ,472,472,472
BEGIN DESCRIPTION:
Chalk Hollow 16.0
END DESCRIPTION:
XS GIS Cut Line= 3
      2471925.04     13814925.01        2471475.       13814775.
      2471125.04     13814824.99
#Sta/Elev= 30
  4520.1  405.54  4564.6  404.06  4604.5  403.84  4699.3  401.48    4752  401.32
  4773.1  400.37  4852.9  398.72  4931.2  397.71  4941.8  396.15  4952.3  396.57
    4997  396.34  5004.6  394.39  5011.4  390.17  5011.9  389.67  5017.4  389.67
  5017.9  390.17  5024.8  390.64  5034.9  395.19    5045  396.67  5055.1  397.27
  5065.2  396.74    5072  397.13  5095.5   397.6  5105.6  396.91  5115.7  396.99
  5287.4  405.26  5297.5  406.32  5307.6  406.36  5327.8  408.49    5348  408.21
#Mann= 6 ,-1 , 0
  4520.1    .035       0  4564.6     .12       0  4852.9      .1       0
  5011.4     .05       0  5017.9      .1       0    5072     .12       0
Bank Sta=5011.4,5017.9
XS Rating Curve= 0 ,0
Exp/Cntr=0.3,0.1

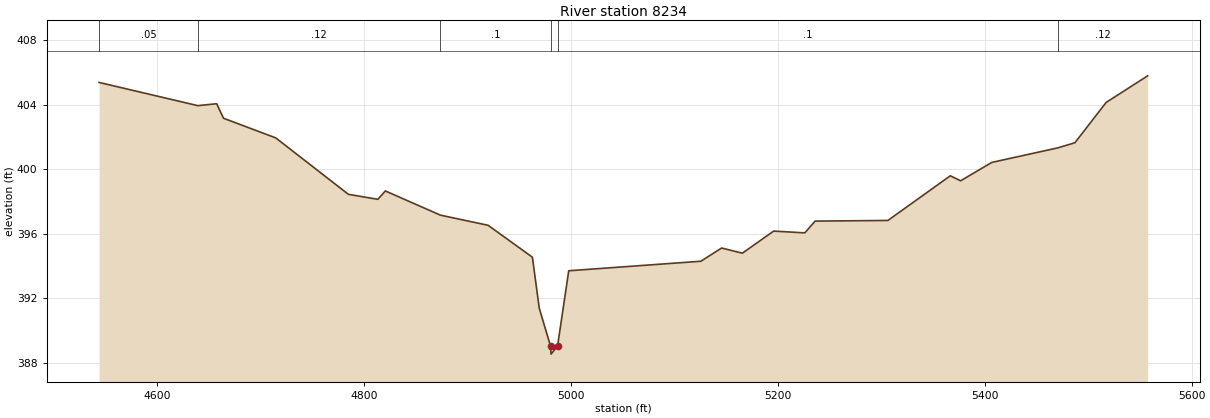
Type RM Length L Ch R = 1 ,8234    ,444,444,444
BEGIN DESCRIPTION:
Chalk Hollow 15.0
END DESCRIPTION:
XS GIS Cut Line= 3
      2471974.99     13814724.99        2471675.       13814375.
      2471125.04       13814325.
#Sta/Elev= 30
  4544.3  405.39  4639.7  403.95  4657.9  404.07  4664.5  403.17    4715  401.95
  4785.2  398.45  4813.7  398.14  4820.9  398.66  4874.1  397.16  4920.2  396.53
    4963  394.55  4969.6  391.39  4980.5  389.04    4981  388.54  4987.3  389.04
  4998.1  393.71  5125.8   394.3  5145.8  395.12  5165.9   394.8  5196.1  396.17
  5226.2  396.06  5236.2  396.79  5306.5  396.83  5366.8   399.6  5376.8  399.29
  5406.9  400.43  5470.6  401.33  5487.2  401.65  5517.4  404.15  5557.5   405.8
#Mann= 6 ,-1 , 0
  4544.3     .05       0  4639.7     .12       0  4874.1      .1       0
  4980.5     .05       0  4987.3      .1       0  5470.6     .12       0
Bank Sta=4980.5,4987.3
XS Rating Curve= 0 ,0
Exp/Cntr=0.3,0.1