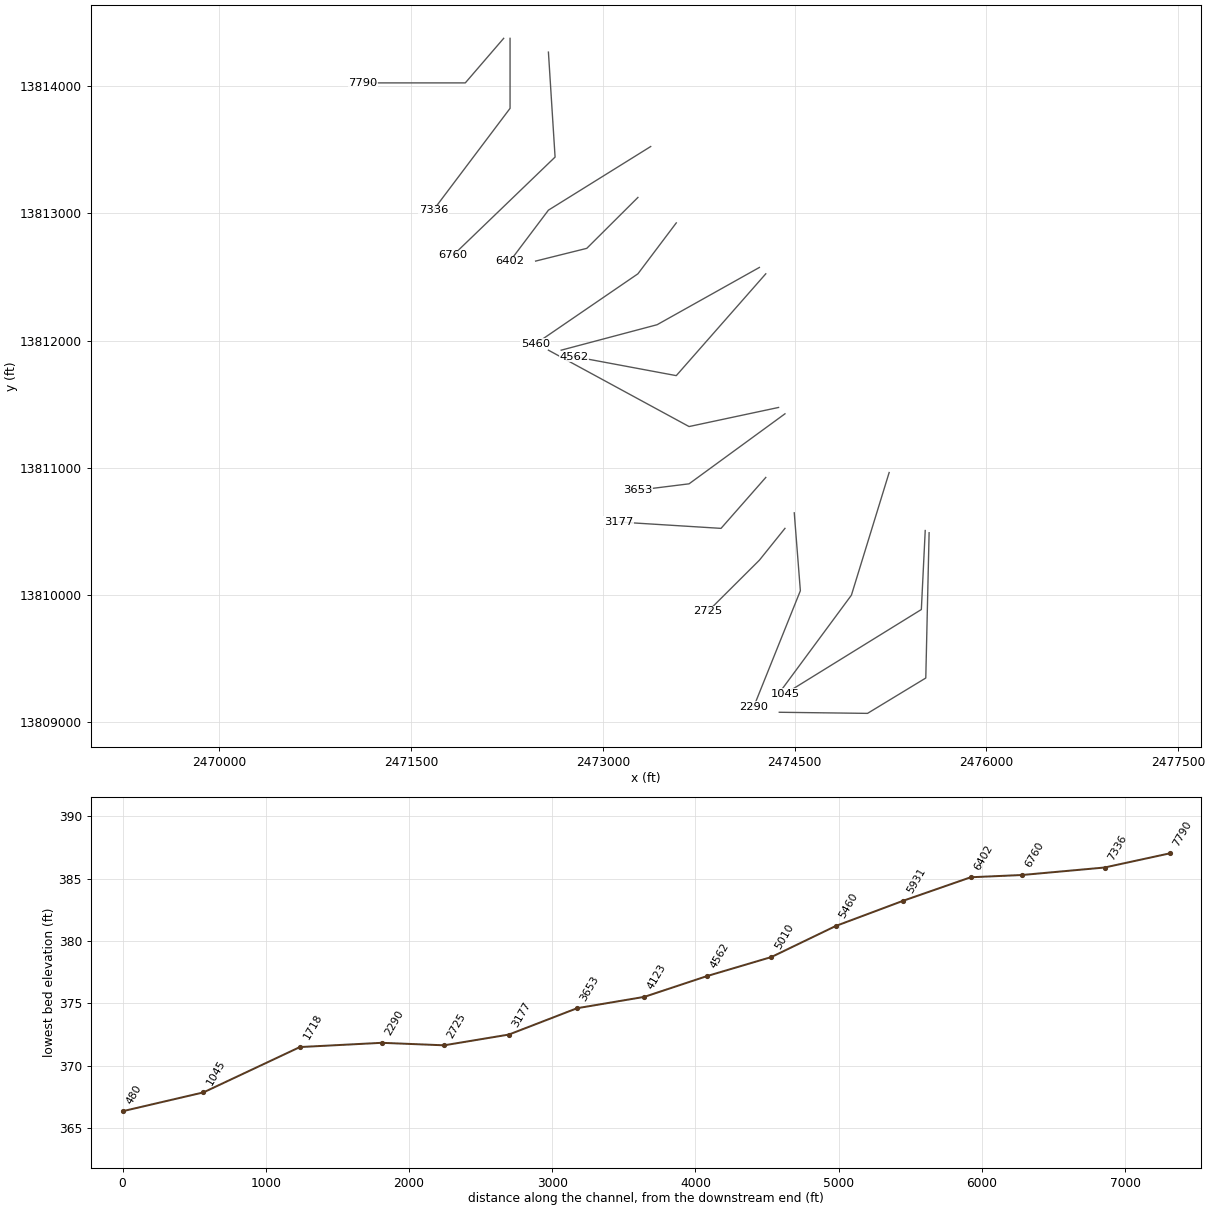
HEC-RAS study Chalk Hollow.prj: Chalk Hollow Base Level Engineering

--- Chalk Hollow.g01 (geometry) --- (continued)

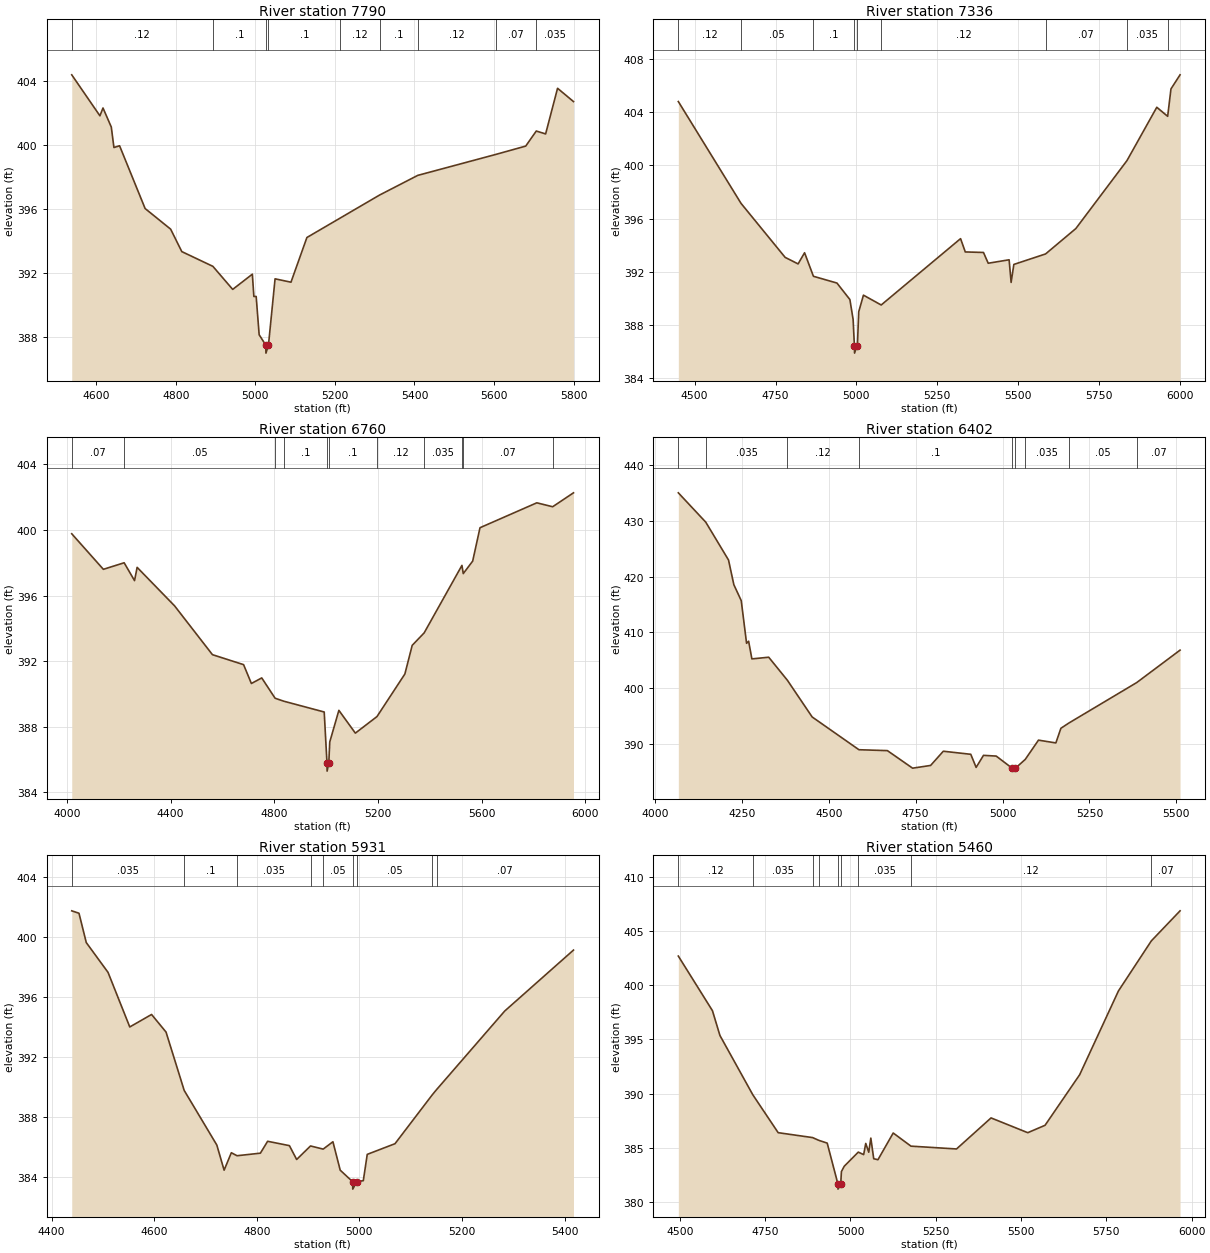
Type RM Length L Ch R = 1 ,7790    ,454,454,454
BEGIN DESCRIPTION:
Chalk Hollow 14.0
END DESCRIPTION:
XS GIS Cut Line= 3
      2472225.03     13814375.03        2471925.       13814025.
      2471125.02       13814025.
#Sta/Elev= 30
  4538.6  404.39  4609.4  401.83  4617.1  402.32    4638  401.13  4644.6  399.85
  4658.8  399.96    4723  396.04  4787.2  394.75  4815.2  393.35  4893.3  392.43
  4943.1  390.99  4992.5  391.94  4996.3  390.55  5002.1  390.55  5009.6  388.16
  5026.2  387.51  5026.7  387.01    5033  387.51  5049.6  391.65  5089.6  391.44
  5129.6  394.23  5213.6  395.45  5312.1  396.88  5408.2  398.11  5604.5  399.42
  5679.6  399.94  5706.1  400.88  5729.6   400.7  5759.6  403.55  5799.6  402.72
#Mann= 9 ,-1 , 0
  4538.6     .12       0  4893.3      .1       0  5026.2     .05       0
    5033      .1       0  5213.6     .12       0  5312.1      .1       0
  5408.2     .12       0  5604.5     .07       0  5706.1    .035       0
Bank Sta=5026.2,5033
XS Rating Curve= 0 ,0
Exp/Cntr=0.3,0.1

Type RM Length L Ch R = 1 ,7336    ,576,576,576
BEGIN DESCRIPTION:
Chalk Hollow 13.0
END DESCRIPTION:
XS GIS Cut Line= 3
        2472275.     13814374.99        2472275.       13813825.
        2471675.       13813025.
#Sta/Elev= 30
  4449.8   404.8  4643.6  397.14  4779.8  393.08  4819.8  392.59  4839.8  393.43
  4867.1  391.66  4939.8  391.15  4979.8  389.91  4989.8  388.41  4993.8  386.38
  4994.3  385.88  5000.7  386.38  5002.9  386.38  5007.1  388.99  5021.7  390.24
  5076.5   389.5  5321.7  394.49  5336.3  393.49  5392.5  393.45  5407.1  392.64
  5471.7   392.9  5477.9   391.2  5486.3  392.55  5584.4  393.34  5677.9  395.25
  5835.8  400.36  5927.9  404.37  5961.5  403.69  5971.7  405.75  5999.8  406.81
#Mann= 9 ,-1 , 0
  4449.8     .12       0  4643.6     .05       0  4867.1      .1       0
  4993.8     .05       0  5000.7      .1       0  5076.5     .12       0
  5584.4     .07       0  5835.8    .035       0  5961.5     .05       0
Bank Sta=4993.8,5000.7
XS Rating Curve= 0 ,0
Exp/Cntr=0.3,0.1

Type RM Length L Ch R = 1 ,6760    ,358,358,358
BEGIN DESCRIPTION:
X18453
END DESCRIPTION:
XS GIS Cut Line= 3
      2472575.04     13814266.78      2472627.12     13813442.15
      2471829.45      13812670.5
#Sta/Elev= 30
  4018.5  399.77  4140.5   397.6  4220.7     398  4260.8  396.91  4270.8  397.72
  4415.3  395.37  4561.4  392.39  4681.6  391.78  4711.7  390.63  4751.7  390.97
  4803.2  389.73  4836.4  389.55  4992.7  388.89  5003.4  385.78  5003.9  385.28
  5010.4  385.78  5014.1  387.06  5049.3  388.99  5112.9   387.6  5196.3  388.61
    5304  391.21  5332.3  392.96  5378.4  393.72  5524.2  397.84  5529.3  397.34
  5565.6   398.1  5593.9  400.14  5813.1  401.66  5874.3  401.42  5954.6  402.27
#Mann= 11 ,-1 , 0
  4018.5     .07       0  4220.7     .05       0  4803.2     .12       0
  4836.4      .1       0  5003.4     .05       0  5010.4      .1       0
  5196.3     .12       0  5378.4    .035       0  5524.2     .05       0
  5529.3     .07       0  5874.3     .05       0
Bank Sta=5003.4,5010.4
XS Rating Curve= 0 ,0
Exp/Cntr=0.3,0.1

Type RM Length L Ch R = 1 ,6402    ,471,471,471
BEGIN DESCRIPTION:
Chalk Hollow 12.0
END DESCRIPTION:
XS GIS Cut Line= 3
      2473374.96     13813524.98        2472575.       13813025.
      2472274.97     13812624.96
#Sta/Elev= 30
  4067.2  435.04  4146.2  429.77  4211.6  422.98  4226.9  418.56  4248.2  415.69
  4263.5  408.04  4269.4  408.41  4278.8  405.24  4327.2  405.54  4380.9  401.41
  4452.2  394.82  4586.8  388.94  4668.6  388.78  4741.1  385.63    4793  386.12
  4829.5  388.67  4908.5  388.12  4923.9  385.77  4945.1  387.93  4981.7   387.8
  5028.2   385.6  5028.7   385.1  5036.6   385.6  5065.3  387.21  5103.3  390.66
  5153.3  390.16  5167.8  392.79    5191  393.74  5385.9  400.99  5510.6  406.81
#Mann= 9 ,-1 , 0
  4067.2     .12       0  4146.2    .035       0  4380.9     .12       0
  4586.8      .1       0  5028.2     .05       0  5036.6      .1       0
  5065.3    .035       0    5191     .05       0  5385.9     .07       0
Bank Sta=5028.2,5036.6
XS Rating Curve= 0 ,0
Exp/Cntr=0.3,0.1

Type RM Length L Ch R = 1 ,5931    ,471,471,471
BEGIN DESCRIPTION:
Chalk Hollow 11.0
END DESCRIPTION:
XS GIS Cut Line= 3
        2473275.       13813125.        2472875.       13812725.
      2472474.99       13812625.
#Sta/Elev= 30
  4439.4  401.72  4453.5  401.56  4467.7  399.61  4510.1  397.63  4552.5     394
    4595  394.83  4623.2  393.66  4658.6  389.78  4722.2  386.15  4736.4  384.48
  4750.5  385.64  4761.6  385.44  4807.1  385.61  4821.2   386.4  4863.7  386.11
  4877.8  385.19  4904.8  386.09  4929.5  385.88  4948.5  386.37  4962.7  384.48
  4986.7  383.72  4987.2  383.22  4995.1  383.72  5007.7  383.78  5015.4  385.53
  5069.5  386.24  5142.4   389.5  5150.4  389.83  5283.4  395.06  5417.4  399.11
#Mann= 9 ,-1 , 0
  4439.4    .035       0  4658.6      .1       0  4761.6    .035       0
  4904.8      .1       0  4929.5     .05       0  4986.7     .05       0
  4995.1     .05       0  5142.4     .12       0  5150.4     .07       0
Bank Sta=4986.7,4995.1
XS Rating Curve= 0 ,0
Exp/Cntr=0.3,0.1

Type RM Length L Ch R = 1 ,5460    ,450,450,450
BEGIN DESCRIPTION:
Chalk Hollow 10.0
END DESCRIPTION:
XS GIS Cut Line= 3
      2473574.99     13812924.99        2473275.       13812525.
      2472475.01     13811975.01
#Sta/Elev= 30
  4495.4  402.67  4595.4  397.64  4617.3  395.36  4713.8  389.89  4788.1   386.4
  4888.8  385.95  4907.6  385.69  4931.8  385.44    4963   381.7  4963.5   381.2
  4971.5   381.7  4973.5  382.82  4981.8  383.31  5022.9  384.61  5038.7  384.38
  5044.8  385.41  5053.6   384.6  5059.7   385.9  5068.2     384  5080.6  383.91
  5125.3  386.37  5177.3  385.16  5310.9   384.9  5412.1  387.76  5519.7   386.4
  5570.4  387.08  5671.9  391.74  5785.6  399.46    5882  404.07  5966.2  406.84
#Mann= 9 ,-1 , 0
  4495.4     .12       0  4713.8    .035       0  4888.8    .045       0
  4907.6    .063       0    4963    .063       0  4971.5    .063       0
  5022.9    .035       0  5177.3     .12       0    5882     .07       0
Bank Sta=4963,4971.5
XS Rating Curve= 0 ,0
Exp/Cntr=0.3,0.1

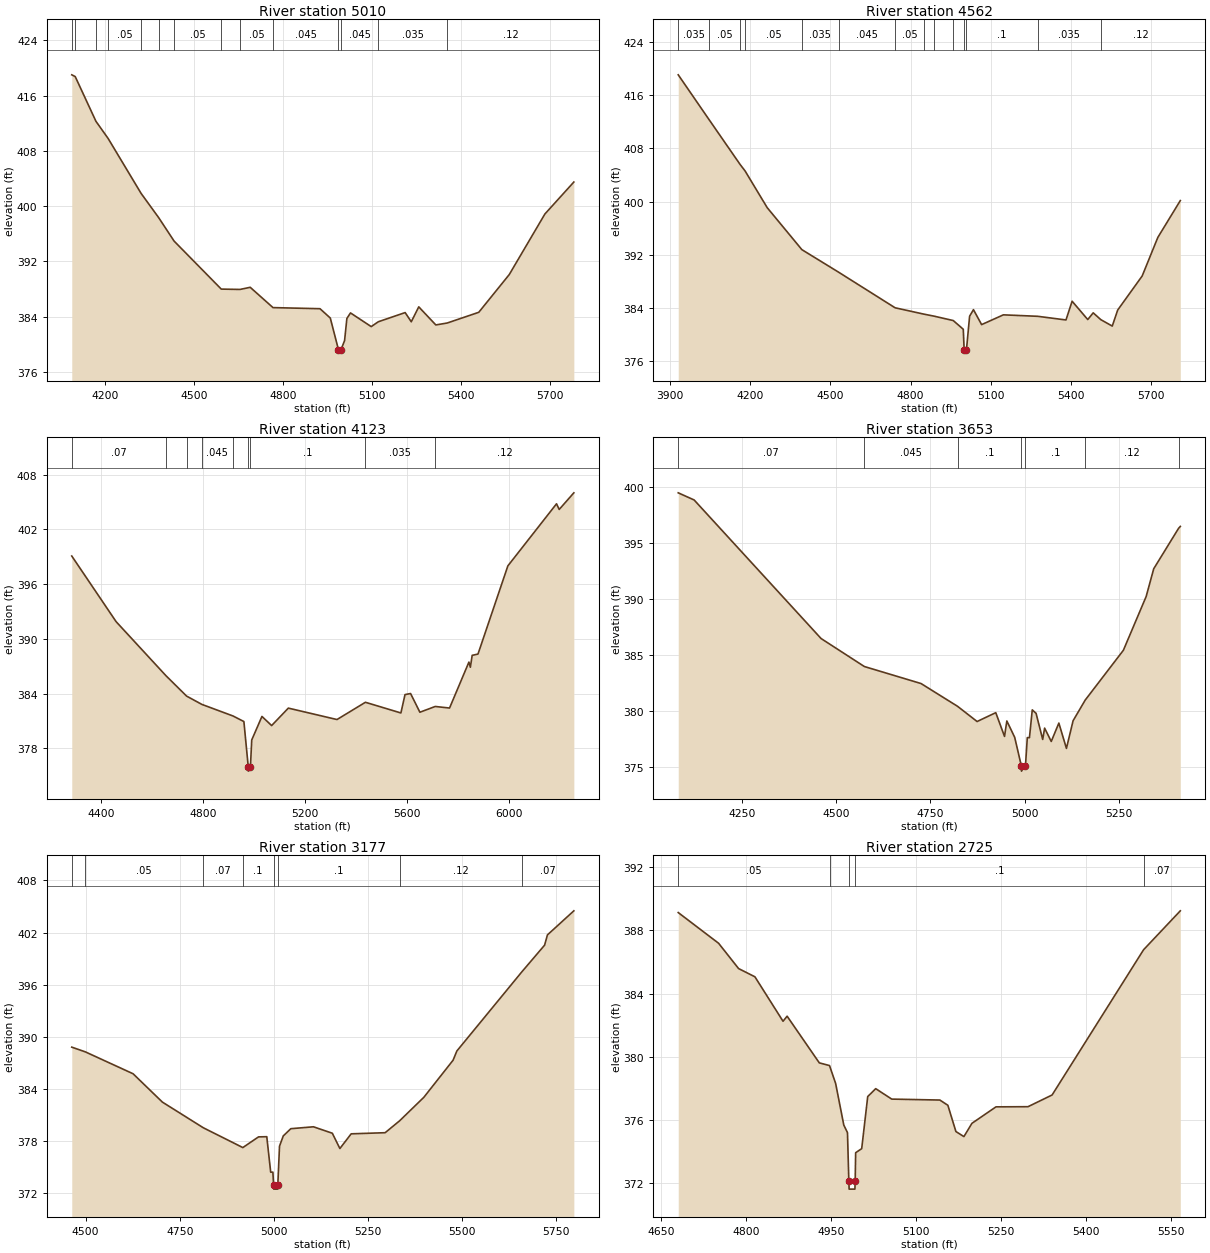
Type RM Length L Ch R = 1 ,5010    ,448,448,448
BEGIN DESCRIPTION:
Chalk Hollow 9.0
END DESCRIPTION:
XS GIS Cut Line= 3
      2474225.02     13812575.01        2473425.       13812125.
      2472675.01       13811925.
#Sta/Elev= 30
  4086.7     419  4098.3  418.75  4168.3  412.27  4209.5  409.78  4320.7  401.83
  4379.7  398.34    4432  394.93  4591.1  387.98  4654.4  387.93  4688.8  388.24
  4765.7   385.3  4924.3  385.14    4959  383.79  4986.6  379.21  4987.1  378.71
  4995.2  379.21  5007.2  380.52    5015  383.73  5027.2  384.53  5097.1  382.55
    5121  383.25  5211.6  384.58  5232.3  383.25  5257.5  385.41  5315.1  382.79
  5353.5  383.07    5460  384.62  5562.8  390.08  5683.1  398.85  5780.8  403.48
#Mann= 14 ,-1 , 0
  4086.7     .07       0  4098.3     .05       0  4168.3    .035       0
  4209.5     .05       0  4320.7     .07       0  4379.7    .035       0
    4432     .05       0  4591.1    .035       0  4654.4     .05       0
  4765.7    .045       0  4986.6     .05       0  4995.2    .045       0
    5121    .035       0  5353.5     .12       0
Bank Sta=4986.6,4995.2
XS Rating Curve= 0 ,0
Exp/Cntr=0.3,0.1

Type RM Length L Ch R = 1 ,4562    ,439,439,439
BEGIN DESCRIPTION:
Chalk Hollow 8.0
END DESCRIPTION:
XS GIS Cut Line= 3
        2474275.       13812525.        2473575.       13811725.
      2472774.96     13811875.01
#Sta/Elev= 30
  3931.3  419.06  4047.1  412.29  4162.7  405.57  4181.2   404.6    4264  399.07
  4393.5  392.76  4531.1  389.36  4742.1  384.01  4851.6  383.04    4887  382.76
  4959.5  382.09  4996.9  380.78  5000.2  377.69  5000.7  377.19  5008.8  377.69
  5020.6  382.74    5035  383.73  5065.5  381.48  5146.9  382.95  5275.1  382.73
  5380.9  382.18  5403.8     385  5462.3  382.24  5482.7  383.25    5511  382.23
  5553.9  381.26  5574.2  383.67  5665.8   388.8  5724.3   394.6  5808.3  400.14
#Mann= 14 ,-1 , 0
  3931.3    .035       0  4047.1     .05       0  4162.7    .035       0
  4181.2     .05       0  4393.5    .035       0  4531.1    .045       0
  4742.1     .05       0  4851.6      .1       0    4887    .045       0
  4959.5      .1       0  5000.2     .05       0  5008.8      .1       0
  5275.1    .035       0    5511     .12       0
Bank Sta=5000.2,5008.8
XS Rating Curve= 0 ,0
Exp/Cntr=0.3,0.1

Type RM Length L Ch R = 1 ,4123    ,470,470,470
BEGIN DESCRIPTION:
Chalk Hollow 7.0
END DESCRIPTION:
XS GIS Cut Line= 3
      2474375.02     13811475.01        2473675.       13811325.
      2472575.01     13811924.99
#Sta/Elev= 30
  4284.1  399.08    4458  391.89  4653.2  385.98  4734.3  383.74  4794.1  382.83
  4916.4  381.56  4959.1  380.95  4976.1  376.02  4976.6  375.52  4984.8  376.02
  4989.8  378.93  5029.9  381.51  5067.9  380.51  5133.4  382.42  5324.2  381.17
  5435.7  383.06  5574.8  381.89  5590.9   383.9  5612.7  384.02  5649.3  381.97
  5709.5   382.6  5765.6  382.43  5841.5  387.46  5847.2   386.9  5854.3   388.2
  5877.1  388.34  5994.3     398  6185.1   404.8  6195.6  404.18    6253     406
#Mann= 9 ,-1 , 0
  4284.1     .07       0  4653.2    .045       0  4734.3     .07       0
  4794.1    .045       0  4916.4      .1       0  4976.1     .05       0
  4984.8      .1       0  5435.7    .035       0  5709.5     .12       0
Bank Sta=4976.1,4984.8
XS Rating Curve= 0 ,0
Exp/Cntr=0.3,0.1

Type RM Length L Ch R = 1 ,3653    ,476,476,476
BEGIN DESCRIPTION:
Chalk Hollow 6.0
END DESCRIPTION:
XS GIS Cut Line= 3
        2474425.       13811425.        2473675.       13810875.
      2473274.96       13810825.
#Sta/Elev= 30
  4080.3  399.46  4122.6  398.82  4459.6  386.45  4574.5  383.95  4725.1  382.43
  4821.9   380.4  4873.9  379.04  4923.5  379.83  4946.7  377.71  4952.9  379.09
  4973.7  377.63  4991.2  375.11  4991.7  374.61  5002.4  375.11  5007.2   377.6
  5012.9   377.6  5020.4  380.08  5030.5  379.77  5048.1  377.44  5053.2  378.45
  5070.8  377.26    5091   378.9  5111.1  376.64  5128.8  379.11  5161.1  380.96
  5262.3   385.4  5322.8   390.2  5342.9  392.68  5408.9  396.29  5413.5  396.46
#Mann= 7 ,-1 , 0
  4080.3     .07       0  4574.5    .045       0  4821.9      .1       0
  4991.2     .05       0  5002.4      .1       0  5161.1     .12       0
  5408.9    .035       0
Bank Sta=4991.2,5002.4
XS Rating Curve= 0 ,0
Exp/Cntr=0.3,0.1

Type RM Length L Ch R = 1 ,3177    ,452,452,452
BEGIN DESCRIPTION:
Chalk Hollow 5.0
END DESCRIPTION:
XS GIS Cut Line= 3
      2474275.01     13810925.02        2473925.       13810525.
      2473124.99       13810575.
#Sta/Elev= 30
  4463.3  388.83  4499.2  388.29  4626.1  385.77  4703.9  382.51  4812.5  379.56
  4917.5  377.28  4959.2  378.51  4981.1  378.53  4991.5  374.45  4997.3  374.45
  4999.2     373  4999.7   372.5  5009.9   372.5  5010.4     373  5014.9  377.44
  5024.9  378.62  5044.9  379.45    5105  379.67  5155.1  378.93  5175.2  377.17
  5205.2  378.86  5295.4  378.99  5334.1  380.37  5398.1  383.06  5475.8  387.33
  5485.8  388.39  5658.3  397.49  5718.7  400.56  5726.3  401.74  5796.4  404.51
#Mann= 8 ,-1 , 0
  4463.3     .07       0  4499.2     .05       0  4812.5     .07       0
  4917.5      .1       0  4999.2     .05       0  5010.4      .1       0
  5334.1     .12       0  5658.3     .07       0
Bank Sta=4999.2,5010.4
XS Rating Curve= 0 ,0
Exp/Cntr=0.3,0.1

Type RM Length L Ch R = 1 ,2725    ,435,435,435
BEGIN DESCRIPTION:
Chalk Hollow 4.0
END DESCRIPTION:
XS GIS Cut Line= 3
        2474425.       13810525.        2474225.       13810275.
      2473825.03     13809875.03
#Sta/Elev= 30
  4680.1  389.12  4751.3  387.18  4786.6  385.58  4815.4  385.06    4865  382.25
  4872.2  382.57    4929  379.62    4947  379.45  4957.8  378.32  4972.2  375.69
  4978.7  375.21  4981.1  372.14  4981.6  371.64  4991.8  371.64  4992.3  372.14
  4993.1  373.94  5003.8   374.2  5014.4  377.49  5028.5  377.99  5056.8  377.33
  5141.7  377.27  5155.8  376.94    5170  375.28  5184.1  374.96  5198.3   375.8
  5240.7  376.84  5297.2  376.85  5339.7  377.59  5501.1  386.77  5565.9  389.23
#Mann= 5 ,-1 , 0
  4680.1     .05       0    4947      .1       0  4981.1     .05       0
  4992.3      .1       0  5501.1     .07       0
Bank Sta=4981.1,4992.3
XS Rating Curve= 0 ,0
Exp/Cntr=0.3,0.1

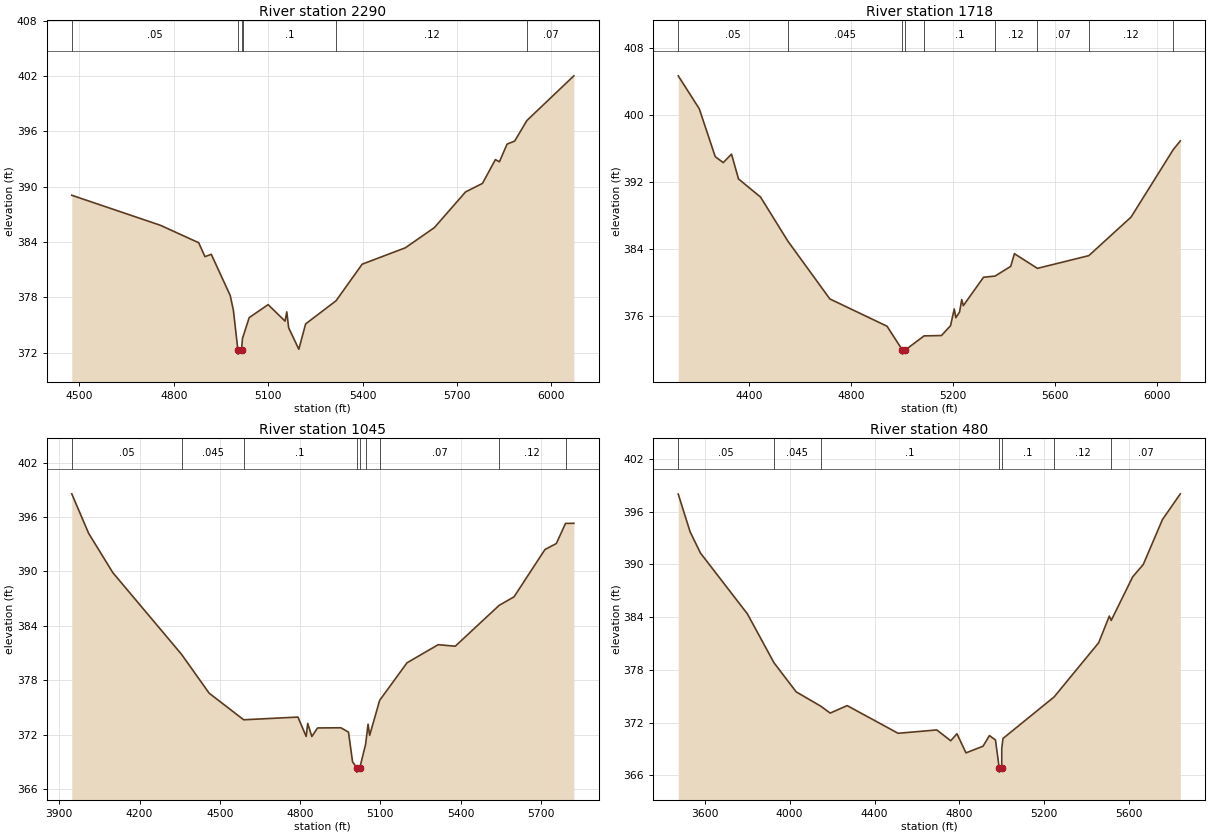
Type RM Length L Ch R = 1 ,2290    ,572,572,572
BEGIN DESCRIPTION:
Chalk Hollow 3.0
END DESCRIPTION:
XS GIS Cut Line= 3
      2474497.78     13810647.06      2474545.52     13810035.04
      2474180.92     13809123.54
#Sta/Elev= 30
  4475.6  389.08  4757.4  385.82  4878.9  383.93  4898.9  382.42    4919  382.67
  4979.2   378.2  4989.2   376.6  5003.4  372.34  5003.9  371.84  5015.1  372.34
  5018.2  373.55  5039.4   375.8  5099.6  377.21  5153.5  375.42  5158.9  376.43
  5164.9   374.7  5197.2  372.37  5218.8  375.12  5315.5  377.63  5398.5   381.6
  5535.8  383.38    5628  385.57    5727  389.44  5780.9  390.37  5821.9  392.95
  5834.7  392.71  5858.9  394.63  5883.2  394.96    5922  397.19  6071.2  402.04
#Mann= 6 ,-1 , 0
  4475.6     .05       0  5003.4     .05       0  5015.1     .05       0
  5018.2      .1       0  5315.5     .12       0    5922     .07       0
Bank Sta=5003.4,5015.1
XS Rating Curve= 0 ,0
Exp/Cntr=0.3,0.1

Type RM Length L Ch R = 1 ,1718    ,673,673,673
BEGIN DESCRIPTION:
Chalk Hollow 2.0
END DESCRIPTION:
XS GIS Cut Line= 3
      2475239.96     13810963.84      2474944.83     13810000.31
      2474375.01     13809225.01
#Sta/Elev= 30
  4121.4  404.73  4203.9   400.8  4266.6  395.08    4298  394.37  4330.4  395.38
  4357.9  392.42  4444.4  390.25  4551.4     385  4716.3  378.09  4940.7  374.83
  5000.6     372  5001.1   371.5  5012.4     372  5086.2  373.68  5154.2  373.72
  5189.7  374.89  5204.4  376.89  5210.6  375.85  5225.2  376.53  5233.7  378.01
  5239.9  377.29  5319.3  380.68  5364.5  380.82  5425.8  381.98  5440.5  383.49
  5530.6  381.74  5732.3  383.26    5898  387.86  6063.8  395.93  6091.3  396.96
#Mann= 9 ,-1 , 0
  4121.4     .05       0  4551.4    .045       0  5000.6    .045       0
  5012.4    .045       0  5086.2      .1       0  5364.5     .12       0
  5530.6     .07       0  5732.3     .12       0  6063.8     .07       0
Bank Sta=5000.6,5012.4
XS Rating Curve= 0 ,0
Exp/Cntr=0.3,0.1

Type RM Length L Ch R = 1 ,1045    ,565,565,565
BEGIN DESCRIPTION:
Chalk Hollow 1.0
END DESCRIPTION:
XS GIS Cut Line= 3
      2475522.08      13810508.1       2475491.7     13809887.47
      2474425.04     13809225.02
#Sta/Elev= 30
  3946.6  398.55  4009.8  394.19  4099.9  389.87  4356.9  380.86  4460.3  376.57
  4589.4  373.64  4792.1  373.94  4822.9  371.81  4828.7  373.24  4844.1   371.8
  4865.4  372.74  4952.6  372.76  4981.1  372.28  4996.4     369  5011.8  368.37
  5012.3  367.87  5023.6  368.37  5045.1  370.94  5054.3  373.16  5060.2  371.92
  5097.6  375.78  5199.8  379.92  5316.5  381.92  5380.2  381.75  5544.5  386.26
  5599.9  387.19  5715.6  392.41  5758.1  393.07  5792.6  395.29  5823.6   395.3
#Mann= 9 ,-1 , 0
  3946.6     .05       0  4356.9    .045       0  4589.4      .1       0
  5011.8     .05       0  5023.6      .1       0  5045.1     .12       0
  5097.6     .07       0  5544.5     .12       0  5792.6     .07       0
Bank Sta=5011.8,5023.6
XS Rating Curve= 0 ,0
Exp/Cntr=0.3,0.1

Type RM Length L Ch R = 1 ,480     ,0,0,0
BEGIN DESCRIPTION:
X18454
END DESCRIPTION:
XS GIS Cut Line= 4
      2475552.47     13810490.77      2475526.43     13809349.27
       2475070.7     13809071.49      2474380.56     13809080.17
#Sta/Elev= 30
    3475     398  3530.8  393.72  3579.5   391.3  3800.9  384.37  3926.1  378.81
  4030.9  375.49    4147  373.86    4191  373.08    4271  373.93    4511  370.78
  4693.4  371.16    4759  369.93  4788.3  370.73  4830.9  368.55  4911.2  369.31
  4941.3  370.52  4969.8  370.02  4987.3  366.86  4987.8  366.36  4999.2  366.86
  4999.4  369.07  5005.2  370.19  5246.3  374.92  5456.2  381.09  5506.2  384.12
  5515.1  383.62  5616.2  388.58  5666.2  389.99  5756.3  395.09  5840.7  398.03
#Mann= 7 ,-1 , 0
    3475     .05       0  3926.1    .045       0    4147      .1       0
  4987.3     .05       0  4999.2      .1       0  5246.3     .12       0
  5515.1     .07       0
Bank Sta=4987.3,4999.2
XS Rating Curve= 0 ,0
Exp/Cntr=0.3,0.1

Chan Stop Cuts=-1
Use User Specified Reach Order=0
Composite Channel Slope=5