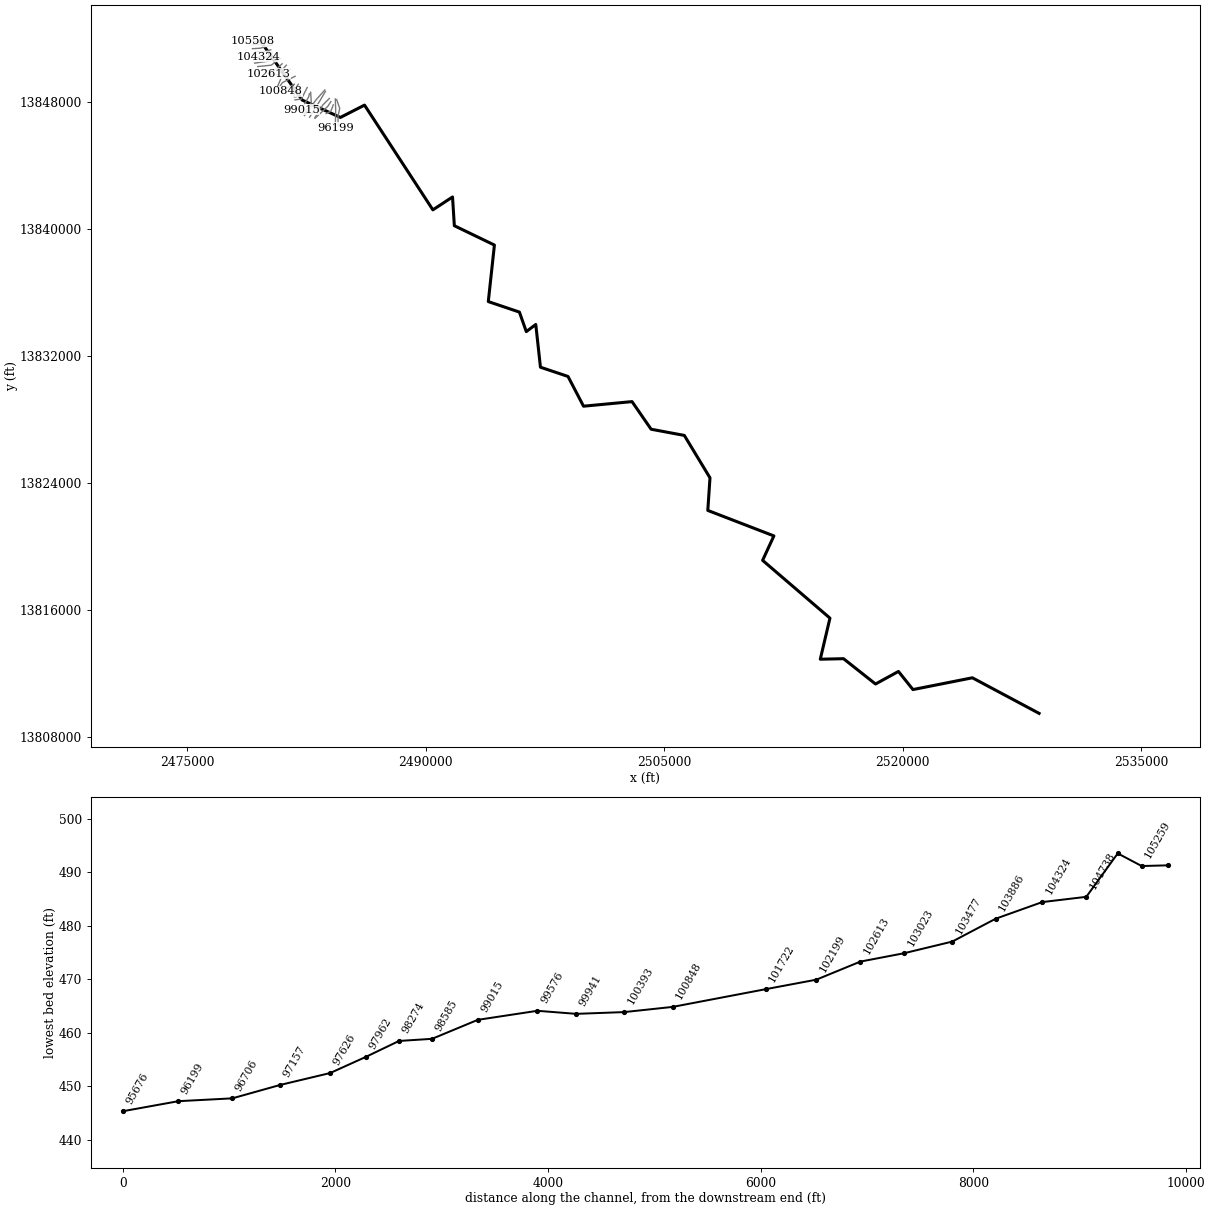
--- Copperas Creek.prj (project) ---

Proj Title=Copperas Creek Base Level Engineering
Current Plan=p01
Default Exp/Contr=0.3,0.1
English Units
Geom File=g01
Flow File=f01
Plan File=p01
Y Axis Title=Elevation
X Axis Title(PF)=Main Channel Distance
X Axis Title(XS)=Station
BEGIN DESCRIPTION:
Copperas Creek
END DESCRIPTION:
DSS Export Rating Curves= 0
DSS Export Rating Curve Sorted= 0
DSS Export Volume Flow Curves= 0
DXF OffsetX= 0
DXF OffsetY= 0
DXF ScaleX= 1
DXF ScaleY= 10

--- Copperas Creek.p01 (plan) ---

Plan Title=Multiple Run
Program Version=4.10
Short Identifier=Multiple
Geom File=g01
Flow File=f01
Subcritical Flow
K Sum by GR= 0
Std Step Tol= 0.01
Critical Tol= 0.01
Num of Std Step Trials= 20
Max Error Tol= 0.3
Flow Tol Ratio= 0.001
Split Flow NTrial= 30
Split Flow Tol= 0.02
Split Flow Ratio= 0.02
Log Output Level= 0
Friction Slope Method= 1
Unsteady Friction Slope Method= 2
Unsteady Bridges Friction Slope Method= 1
Parabolic Critical Depth
Global Vel Dist= 1 , 1 , 1
Global Log Level= 0
CheckData=True
Encroach Param=-1 ,0,0, 0
BEGIN DESCRIPTION:
Multiple Run
END DESCRIPTION:
Computation Interval=1HOUR
Output Interval=1HOUR
Run HTab= 0
Run UNet= 0
Run PostProcess= 0
Run WQNet= 0
UNET Theta= 1
UNET Theta Warmup= 1
UNET ZTol= 0.02
UNET ZSATol= 0.05
UNET MxIter= 20
UNET MaxInSteps= 0
UNET DtIC= 0
UNET DtMin= 0
UNET MaxCRTS= 20
UNET WFStab= 2
UNET SFStab= 1
UNET WFX= 1
UNET SFX= 1
UNET DSS MLevel= 4
UNET DZMax Abort= 100
UNET Convert EG Bridges= 0
UNET Use Existing IB Tables=-1
UNET Froude Reduction=False
UNET Froude Limit= 1
UNET Froude Power= 10
UNET Time Slicing=0,0, 5
UNET Junction Losses=0
Instantaneous Interval=1HOUR
Write IC File= 0
Write IC File at Sim End=0
Echo Input=False
Echo Parameters=False
Echo Output=False
Write Detailed= 0
WQ AD Non Conservative
WQ ULTIMATE=-1
WQ Max Comp Step=1HOUR
WQ Output Interval=15MIN
WQ Output Selected Increments= 0
WQ Output face flow=0
WQ Output face velocity=0
WQ Output face area=0
WQ Output face dispersion=0
WQ Output cell volume=0
WQ Output cell surface area=0
WQ Output cell continuity=0
WQ Output cumulative cell continuity=0
WQ Output face conc=0
WQ Output face dconc_dx=0
WQ Output face courant=0
WQ Output face peclet=0
WQ Output face adv mass=0
WQ Output face disp mass=0
WQ Output cell mass=0
WQ Output cell source sink temp=0
WQ Output cell source sink nsm=0
WQ Output MaxMinRange=-1
WQ Daily Max Min Mean=-1
WQ Daily Range=0
WQ Daily Time=0
WQ Create Restart=0
WQ Fixed Restart=0
WQ System Summary=0
WQ Use Fixed Temperature=0
Sorting and Armoring Iterations= 10
XS Update Threshold= 0.02
Hydraulics Update Threshold= 0.02
Energy Slope Method= 1
Volume Change Method= 0
XS Weighting Method= 0
Number of US Weighted Cross Sections= 1
Number of DS Weighted Cross Sections= 1
Upstream XS Weight=0.25
Main XS Weight=0.5
Downstream XS Weight=0.25
Number of DS XS's Weighted with US Boundary= 1
Upstream Boundary Weight= 1
Weight of XSs Associated with US Boundary= 0
Number of US XS's Weighted with DS Boundary= 1
Downstream Boundary Weight= 0.5
Weight of XSs Associated with DS Boundary= 0.5
Sediment Output Level= 4
Mass or Volume Output= 0
Output Increment Type= 1
Profile and TS Output Increment= 10
XS Output Flag= 0
XS Output Increment= 10
Disregard all LS=0
Disregard all Conn=0
Disregard all Breaches=0
Disregard all Pumps=0

--- Copperas Creek.f01 (steady flow) ---

Flow Title=Multiple
Number of Profiles=7
Profile Names=10-year,25-year,50-year,1pct_min,100-year,1pct_plu,500-year
River Rch & RM= Cooperas Creek,Reach-1,105508
     570     912    1218     789    1575    3143    2605
River Rch & RM= Cooperas Creek,Reach-1,101722
     923    1510    2049    1346    2686    5360    4568
River Rch & RM= Cooperas Creek,Reach-1,99576
    1029    1691    2301    1515    3023    6031    5163
River Rch & RM= Cooperas Creek,Reach-1,98274
    1187    1957    2668    1758    3508    6999    6003
River Rch & RM= Cooperas Creek,Reach-1,93556
    1178    1936    2633    1730    3452    6888    5878
River Rch & RM= Cooperas Creek,Reach-1,91294
    2559    4369    6098    4103    8187   16335   14623
River Rch & RM= Cooperas Creek,Reach-1,89975
    2638    4511    6301    4243    8467   16893   15148
River Rch & RM= Cooperas Creek,Reach-1,88610
    2926    5018    7022    4736    9449   18854   16954
River Rch & RM= Cooperas Creek,Reach-1,87741
    2835    4834    6738    4525    9028   18013   16062
River Rch & RM= Cooperas Creek,Reach-1,82657
    3196    5444    7582    5084   10144   20239   17989
River Rch & RM= Cooperas Creek,Reach-1,78714
    3133    5318    7389    4942    9861   19676   17402
River Rch & RM= Cooperas Creek,Reach-1,77605
    3583    6108    8512    5708   11389   22723   20200
River Rch & RM= Cooperas Creek,Reach-1,75427
    3653    6219    8659    5800   11573   23092   20483
River Rch & RM= Cooperas Creek,Reach-1,73157
    3718    6337    8828    5917   11807   23557   20922
River Rch & RM= Cooperas Creek,Reach-1,70867
    3694    6279    8733    5843   11658   23260   20581
River Rch & RM= Cooperas Creek,Reach-1,68073
    3834    6528    9088    6085   12142   24227   21475
River Rch & RM= Cooperas Creek,Reach-1,63829
    4141    7066    9853    6607   13183   26303   23380
River Rch & RM= Cooperas Creek,Reach-1,61159
    4358    7436   10368    6951   13869   27671   24581
River Rch & RM= Cooperas Creek,Reach-1,55666
    4476    7641   10657    7147   14259   28451   25287
River Rch & RM= Cooperas Creek,Reach-1,55091
    4425    7533   10486    7017   14001   27936   24726
River Rch & RM= Cooperas Creek,Reach-1,49638
    5740    9858   13807    9292   18541   36994   33110
River Rch & RM= Cooperas Creek,Reach-1,44695
    5934   10193   14277    9608   19171   38251   34232
River Rch & RM= Cooperas Creek,Reach-1,37537
    5934   10177   14240    9573   19100   38109   34027
River Rch & RM= Cooperas Creek,Reach-1,33307
    5945   10195   14263    9587   19129   38167   34072
River Rch & RM= Cooperas Creek,Reach-1,31513
    5972   10231   14306    9610   19174   38257   34106
River Rch & RM= Cooperas Creek,Reach-1,30504
    6148   10533   14726    9890   19734   39374   35089
River Rch & RM= Cooperas Creek,Reach-1,20514
    6182   10583   14789    9926   19806   39517   35176
River Rch & RM= Cooperas Creek,Reach-1,17710
    6235   10669   14904   10000   19953   39812   35411
River Rch & RM= Cooperas Creek,Reach-1,11715
    6209   10616   14823    9940   19834   39573   35160
River Rch & RM= Cooperas Creek,Reach-1,7850
    6332   10819   15098   10119   20189   40283   35745
Boundary for River Rch & Prof#=Cooperas Creek,Reach-1,1
Up Type=0
Dn Type=3
Dn Slope=0.005
Boundary for River Rch & Prof#=Cooperas Creek,Reach-1,2
Up Type=0
Dn Type=3
Dn Slope=0.005
Boundary for River Rch & Prof#=Cooperas Creek,Reach-1,3
Up Type=0
Dn Type=3
Dn Slope=0.005
Boundary for River Rch & Prof#=Cooperas Creek,Reach-1,4
Up Type=0
Dn Type=3
Dn Slope=0.005
Boundary for River Rch & Prof#=Cooperas Creek,Reach-1,5
Up Type=0
Dn Type=3
Dn Slope=0.005
Boundary for River Rch & Prof#=Cooperas Creek,Reach-1,6
Up Type=0
Dn Type=3
Dn Slope=0.005
Boundary for River Rch & Prof#=Cooperas Creek,Reach-1,7
Up Type=0
Dn Type=3
Dn Slope=0.005

--- Copperas Creek.g01 (geometry) ---

Geom Title=Existing Conditions
Program Version=4.10

River Reach=Cooperas Creek  ,Reach-1
Reach XY= 30
        2479575.       13851875.        2482225.       13848125.
      2484624.75     13847031.97      2486141.74     13847808.73
      2490441.08     13841207.94      2491677.71     13842019.72
      2491791.41     13840208.07      2494311.92     13838988.67
      2493927.71      13835426.6      2495885.16     13834764.72
      2496318.27     13833534.11      2496914.35       13833985.
      2497208.23     13831291.43      2498941.68     13830708.36
      2499918.26     13828834.13      2502969.15     13829122.96
      2504168.83     13827382.86      2506258.76     13826992.23
      2507872.95     13824319.14      2507735.51     13822265.19
      2511892.14     13820658.54        2511183.     13819118.62
      2515419.53     13815477.45      2514810.86     13812888.36
      2516273.23      13812921.7      2518285.75      13811325.7
      2519728.62     13812117.53      2520640.06     13810975.18
      2524378.58     13811717.51        2528575.       13809475.

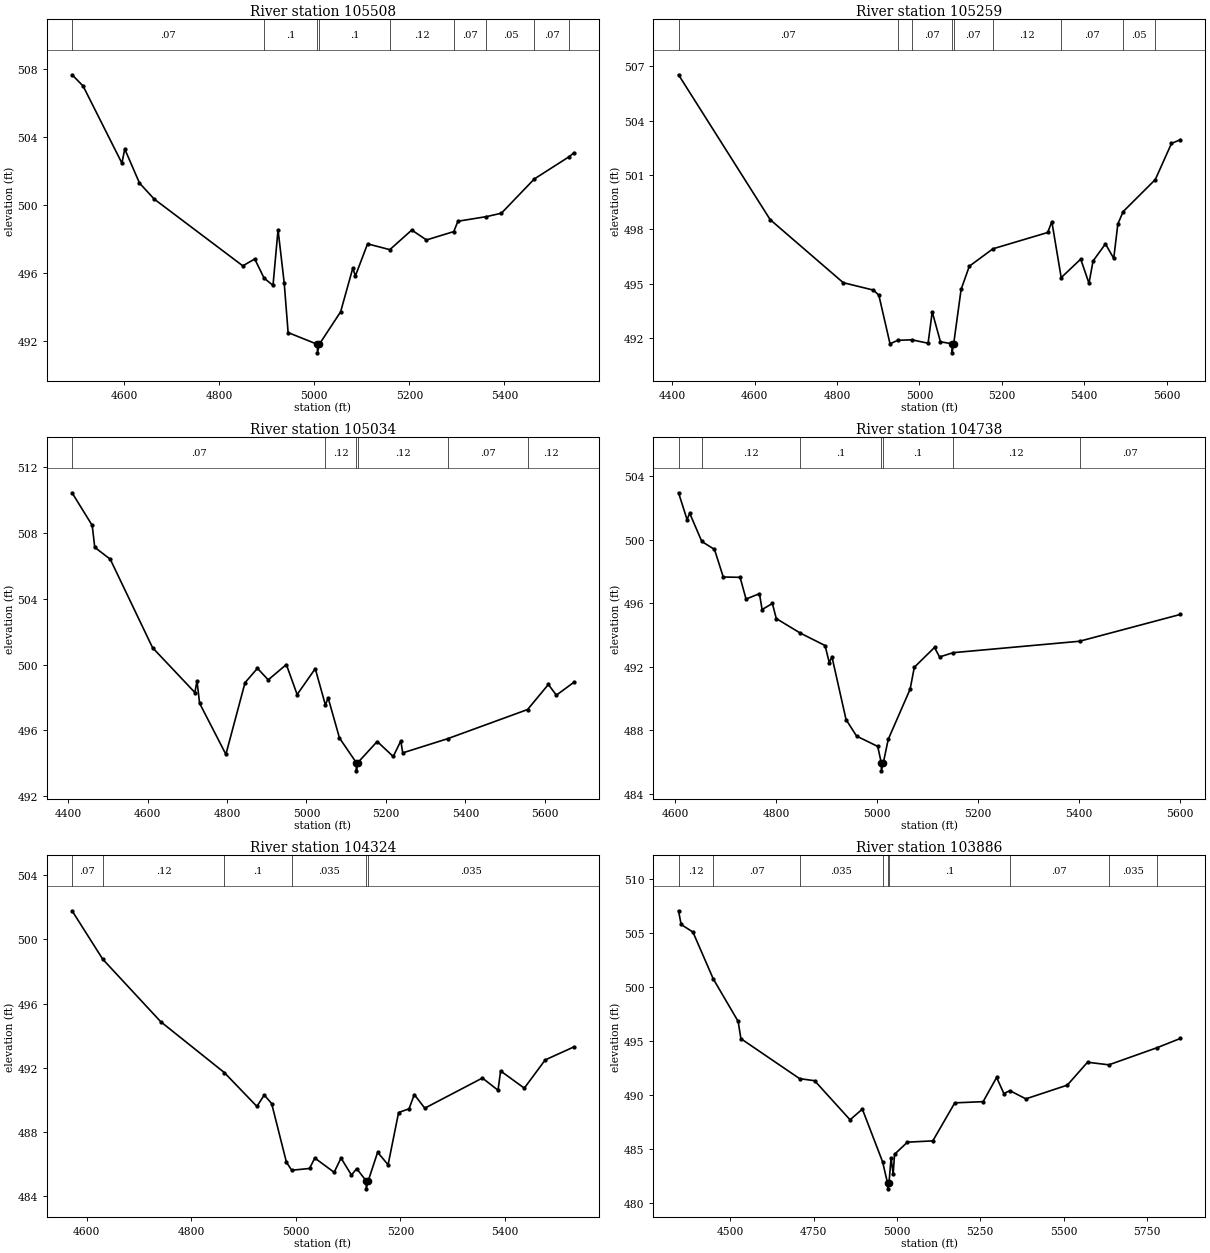
Type RM Length L Ch R = 1 ,105508  ,249,249,249
BEGIN DESCRIPTION:
Cooperas Creek 140.0
END DESCRIPTION:
XS GIS Cut Line= 3
      2480134.02     13852016.95        2479430.     13851769.83
      2479124.98       13851825.
#Sta/Elev= 30
  4490.2  507.65  4513.4  506.99  4595.1  502.46  4601.1  503.29  4632.1  501.29
  4663.1  500.35  4849.5  496.43  4874.7  496.83  4894.3  495.71  4913.1  495.28
  4923.7  498.55  4936.7  495.42  4944.9  492.51  5006.5  491.82  5006.7  491.32
  5010.5  491.82  5055.4  493.73  5081.1   496.3  5086.4  495.83  5112.1  497.72
    5159  497.38  5205.1  498.53  5236.1  497.95  5293.5  498.44  5302.4  499.05
  5362.4  499.32  5393.8  499.52    5463  501.53    5537  502.85  5546.3  503.07
#Mann= 9 ,-1 , 0
  4490.2     .07       0  4894.3      .1       0  5006.5     .05       0
  5010.5      .1       0    5159     .12       0  5293.5     .07       0
  5362.4     .05       0    5463     .07       0    5537     .05       0
Bank Sta=5006.5,5010.5
XS Rating Curve= 0 ,0
Exp/Cntr=0.3,0.1

Type RM Length L Ch R = 1 ,105259  ,225,225,225
BEGIN DESCRIPTION:
X18535
END DESCRIPTION:
XS GIS Cut Line= 3
      2480246.13     13851795.69      2479746.11     13851637.64
      2479053.53     13851606.03
#Sta/Elev= 30
  4415.5  506.53  4637.8  498.54  4815.2  495.06  4888.6  494.65  4901.6  494.37
  4928.7  491.69  4947.4  491.88  4981.5  491.91  5021.1  491.72  5031.1  493.45
  5051.1   491.8  5079.2  491.69  5079.4  491.19  5083.2  491.69  5101.2  494.69
  5121.2  495.97  5178.5  496.93  5311.4  497.83  5321.4  498.43  5344.1  495.34
  5391.5  496.36  5411.5  495.03  5421.5  496.26  5451.5   497.2  5471.6   496.4
  5481.6   498.3  5494.4  498.98  5572.5  500.75  5611.7  502.74  5633.2  502.95
#Mann= 9 ,-1 , 0
  4415.5     .07       0  4947.4      .1       0  4981.5     .07       0
  5079.2     .05       0  5083.2     .07       0  5178.5     .12       0
  5344.1     .07       0  5494.4     .05       0  5572.5     .07       0
Bank Sta=5079.2,5083.2
XS Rating Curve= 0 ,0
Exp/Cntr=0.3,0.1

Type RM Length L Ch R = 1 ,105034  ,296,296,296
BEGIN DESCRIPTION:
X18534
END DESCRIPTION:
XS GIS Cut Line= 3
      2480323.72     13851606.03      2479579.43     13851393.38
      2479090.95     13851364.64
#Sta/Elev= 30
  4409.8  510.42  4460.5  508.44  4466.9  507.11  4505.9  506.39  4612.5  501.02
  4719.1   498.3  4724.3  499.01  4730.9  497.65  4797.1  494.55  4845.3   498.9
  4876.5  499.77  4903.7  499.07  4949.3     500  4976.5  498.18  5022.1  499.75
  5047.7  497.54  5054.5  497.98  5083.1  495.54  5125.3  494.05  5125.6  493.55
  5129.3  494.05  5178.1  495.33  5218.4  494.42  5237.4  495.36  5242.4  494.64
  5355.4   495.5  5556.7  497.27    5609  498.79  5629.1  498.14  5673.2  498.92
#Mann= 6 ,-1 , 0
  4409.8     .07       0  5047.7     .12       0  5125.3     .05       0
  5129.3     .12       0  5355.4     .07       0  5556.7     .12       0
Bank Sta=5125.3,5129.3
XS Rating Curve= 0 ,0
Exp/Cntr=0.3,0.1

Type RM Length L Ch R = 1 ,104738  ,414,414,414
BEGIN DESCRIPTION:
Cooperas Creek 139.0
END DESCRIPTION:
XS GIS Cut Line= 3
      2480243.23     13851295.66      2479806.45     13851166.36
       2479268.1     13851172.08
#Sta/Elev= 30
  4606.4  502.96  4623.3  501.27  4628.5  501.67  4652.5  499.89  4677.6  499.39
    4695  497.65  4728.3  497.63  4740.1  496.26  4766.7   496.6  4771.9   495.6
  4792.3  495.98    4800  495.03  4847.8  494.11  4896.6  493.33    4905  492.25
  4910.2  492.63  4938.2  488.66  4959.1  487.62  5000.9  486.97    5008  485.93
  5008.2  485.43    5012  485.93  5021.7  487.41  5065.1  490.58  5073.4  491.96
  5113.4  493.21  5123.4  492.61  5150.5  492.88  5400.7   493.6  5600.3  495.29
#Mann= 7 ,-1 , 0
  4606.4     .07       0  4652.5     .12       0  4847.8      .1       0
    5008     .05       0    5012      .1       0  5150.5     .12       0
  5400.7     .07       0
Bank Sta=5008,5012
XS Rating Curve= 0 ,0
Exp/Cntr=0.3,0.1

Type RM Length L Ch R = 1 ,104324  ,438,438,438
BEGIN DESCRIPTION:
Cooperas Creek 138.0
END DESCRIPTION:
XS GIS Cut Line= 3
      2480325.01     13851125.01        2480025.       13850825.
      2479490.34     13850858.87
#Sta/Elev= 30
  4571.9  501.79  4630.6  498.77  4741.6  494.87  4863.2   491.7  4925.5  489.59
  4939.6   490.3  4953.7  489.77    4982  486.11  4992.1  485.61  5026.2  485.72
  5036.3  486.37  5073.3  485.48  5086.4  486.37  5106.4  485.31  5116.4  485.71
  5134.5  484.95  5134.7  484.45  5138.5  484.95  5156.5  486.73  5176.5  485.95
  5196.6  489.21  5216.6  489.44  5226.6  490.33  5246.7  489.48  5356.9  491.36
  5386.8   490.6  5391.8   491.8  5437.1  490.73  5477.1  492.49  5531.9   493.3
#Mann= 6 ,-1 , 0
  4571.9     .07       0  4630.6     .12       0  4863.2      .1       0
  4992.1    .035       0  5134.5    .035       0  5138.5    .035       0
Bank Sta=5134.5,5138.5
XS Rating Curve= 0 ,0
Exp/Cntr=0.3,0.1

Type RM Length L Ch R = 1 ,103886  ,409,409,409
BEGIN DESCRIPTION:
Cooperas Creek 137.0
END DESCRIPTION:
XS GIS Cut Line= 3
      2480597.18     13850963.93        2480075.       13850575.
      2479229.33     13850455.38
#Sta/Elev= 30
    4345  507.08  4352.8  505.81  4388.2  505.11  4449.2  500.77  4523.8  496.84
  4532.1  495.24  4708.2  491.54  4753.2  491.35  4859.5  487.73  4896.4  488.72
    4957  483.85  4972.2  481.84  4972.5  481.34  4976.2  481.84  4982.6  484.21
  4988.8  482.71    4993  484.54  5031.6  485.66  5107.7  485.78  5173.7   489.3
  5258.7  489.41  5299.1  491.65  5320.9  490.16  5338.8  490.43  5386.9  489.67
  5511.2  490.94  5571.8  493.06  5635.8  492.82    5780   494.4  5850.2  495.26
#Mann= 9 ,-1 , 0
    4345     .12       0  4449.2     .07       0  4708.2    .035       0
    4957      .1       0  4972.2     .05       0  4976.2      .1       0
  5338.8     .07       0  5635.8    .035       0    5780     .07       0
Bank Sta=4972.2,4976.2
XS Rating Curve= 0 ,0
Exp/Cntr=0.3,0.1

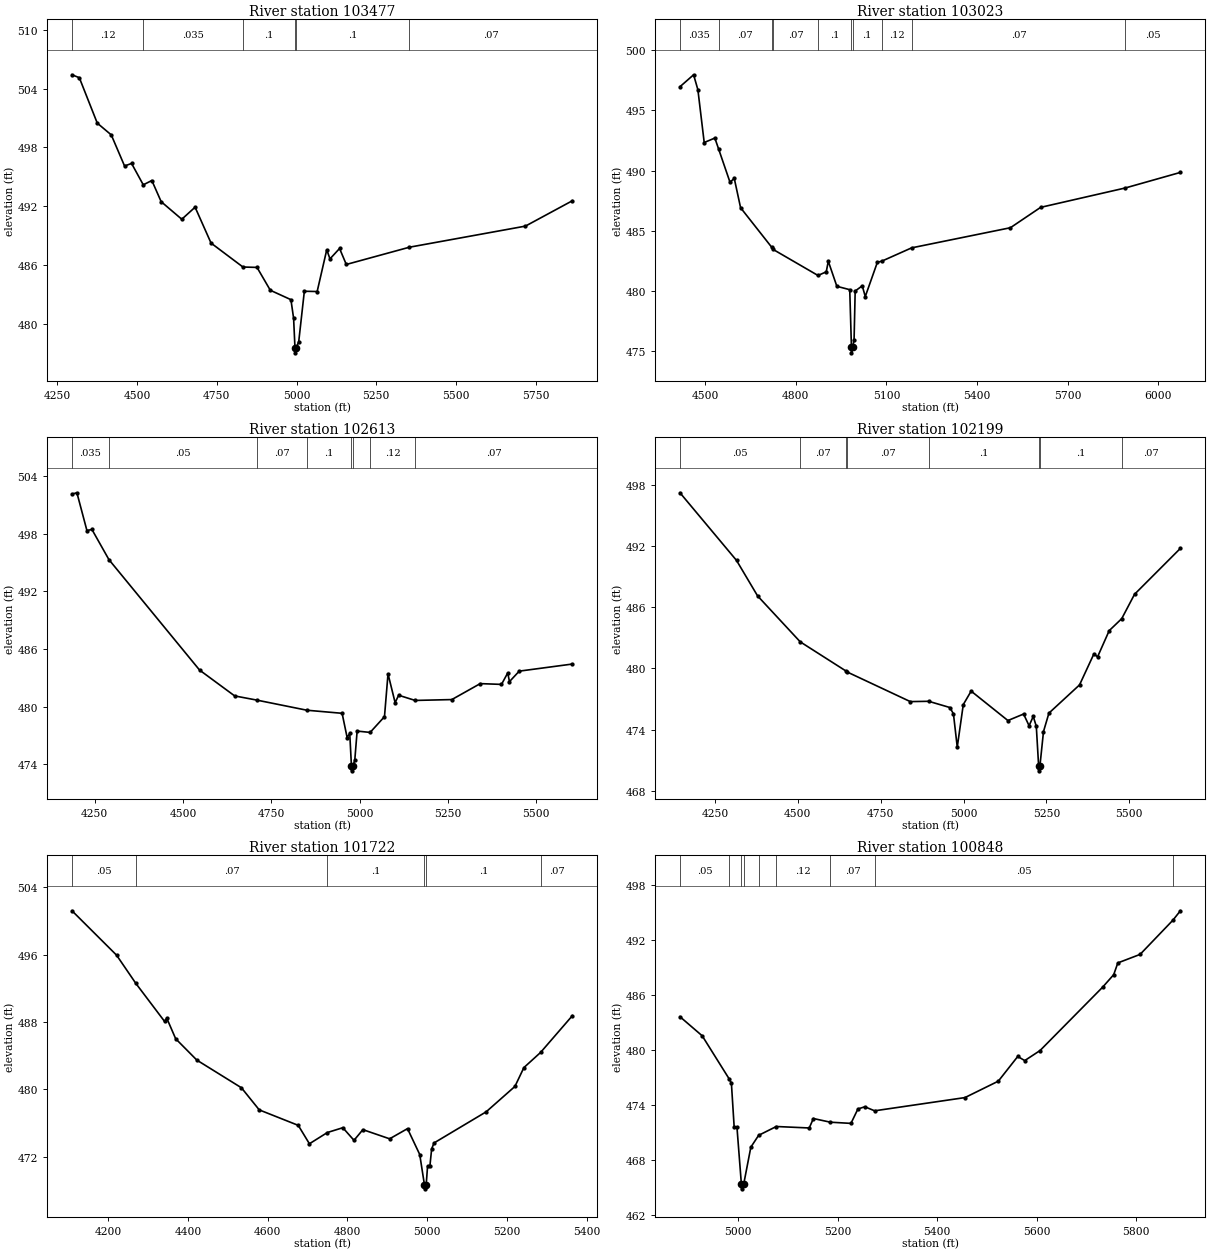
Type RM Length L Ch R = 1 ,103477  ,454,454,454
BEGIN DESCRIPTION:
Cooperas Creek 136.0
END DESCRIPTION:
XS GIS Cut Line= 3
      2480845.37     13850745.91        2480275.       13850325.
      2479418.22      13850237.5
#Sta/Elev= 30
  4295.5  505.41  4318.5  505.11  4374.8  500.48  4418.7  499.28  4460.4  496.11
  4482.4  496.37  4519.1  494.19    4546  494.63  4575.3  492.47    4640  490.68
  4681.7  491.91  4731.8  488.25  4831.8  485.81    4876  485.77  4917.7  483.44
  4982.4  482.48  4990.8  480.58  4995.1  477.56  4995.3  477.06  4999.1  477.56
  5006.9  478.21  5024.5  483.34  5064.7  483.31  5094.8  487.57  5104.9  486.64
    5135   487.7  5156.1  486.07  5354.2  487.83  5718.1  489.98  5865.6  492.57
#Mann= 6 ,-1 , 0
  4295.5     .12       0  4519.1    .035       0  4831.8      .1       0
  4995.1     .05       0  4999.1      .1       0  5354.2     .07       0
Bank Sta=4995.1,4999.1
XS Rating Curve= 0 ,0
Exp/Cntr=0.3,0.1

Type RM Length L Ch R = 1 ,103023  ,410,410,410
BEGIN DESCRIPTION:
Cooperas Creek 135.0
END DESCRIPTION:
XS GIS Cut Line= 3
      2480960.45     13850412.91        2480525.       13850025.
      2479452.77     13849989.06
#Sta/Elev= 30
  4416.9  496.96    4462  497.95  4476.2  496.71  4497.1  492.33  4532.3   492.7
  4545.1  491.77  4582.4  489.04  4596.6  489.35  4617.5  486.92  4720.8  483.63
  4725.1  483.46  4873.6   481.3    4901   481.6  4907.7  482.48  4936.1   480.4
  4978.7  480.12  4984.3  475.38  4984.5  474.88  4988.3  475.38    4993  475.91
  4996.7  480.01  5020.1  480.44  5030.1  479.55  5070.1  482.39  5085.1  482.49
  5183.5  483.59  5510.4  485.26  5610.4  486.95  5890.8  488.56  6072.9  489.85
#Mann= 10 ,-1 , 0
  4416.9    .035       0  4545.1     .07       0  4720.8      .1       0
  4725.1     .07       0  4873.6      .1       0  4984.3     .05       0
  4988.3      .1       0  5085.1     .12       0  5183.5     .07       0
  5890.8     .05       0
Bank Sta=4984.3,4988.3
XS Rating Curve= 0 ,0
Exp/Cntr=0.3,0.1

Type RM Length L Ch R = 1 ,102613  ,414,414,414
BEGIN DESCRIPTION:
Cooperas Creek 134.0
END DESCRIPTION:
XS GIS Cut Line= 3
      2481224.99     13850324.99        2480675.       13849725.
      2480075.01       13849775.
#Sta/Elev= 30
  4186.2  502.14  4200.1  502.27  4228.4  498.34  4242.6  498.45  4290.7  495.31
  4547.2  483.81  4646.5  481.12  4708.4  480.69  4850.9  479.63  4950.5  479.31
  4964.7  476.79  4972.1  477.22  4976.9  473.82  4977.1  473.32  4980.9  473.82
  4986.3  474.41    4993  477.46  5029.8  477.32  5070.4  478.96  5080.4  483.42
  5100.5  480.42  5110.5  481.19  5157.2  480.65    5261  480.74  5341.3   482.4
  5401.5  482.32  5419.1  483.51  5424.1  482.61  5451.7   483.7  5602.2  484.44
#Mann= 8 ,-1 , 0
  4186.2    .035       0  4290.7     .05       0  4708.4     .07       0
  4850.9      .1       0  4976.9     .05       0  4980.9      .1       0
  5029.8     .12       0  5157.2     .07       0
Bank Sta=4976.9,4980.9
XS Rating Curve= 0 ,0
Exp/Cntr=0.3,0.1

Type RM Length L Ch R = 1 ,102199  ,477,477,477
BEGIN DESCRIPTION:
Cooperas Creek 133.0
END DESCRIPTION:
XS GIS Cut Line= 3
      2481475.03     13850075.03      2480936.23      13849607.6
      2480624.99     13848874.97
#Sta/Elev= 30
  4144.8  497.25  4315.3  490.61  4378.9  487.12  4507.5  482.61  4645.7  479.74
    4649  479.65  4839.5  476.74    4895  476.77  4958.7  476.16  4969.6  475.54
  4981.1  472.27  4999.3  476.45    5023  477.77  5133.9  474.88  5181.2  475.52
  5197.7  474.37  5210.3  475.28  5219.5  474.32  5226.5  470.44  5226.7  469.94
  5230.5  470.44  5241.2   473.8  5257.6  475.61  5349.9  478.38  5393.3  481.43
  5404.2  481.13  5439.4  483.71  5477.2  484.89  5515.8  487.28  5654.1  491.79
#Mann= 8 ,-1 , 0
  4144.8     .05       0  4507.5     .07       0  4645.7     .05       0
    4649     .07       0    4895      .1       0  5226.5     .05       0
  5230.5      .1       0  5477.2     .07       0
Bank Sta=5226.5,5230.5
XS Rating Curve= 0 ,0
Exp/Cntr=0.3,0.1

Type RM Length L Ch R = 1 ,101722  ,874,874,874
BEGIN DESCRIPTION:
Cooperas Creek 132.0
END DESCRIPTION:
XS GIS Cut Line= 3
      2481775.03     13849625.01        2480975.       13849225.
      2480775.01     13848925.01
#Sta/Elev= 30
  4109.1  501.23  4220.9  495.95  4269.1   492.6  4341.1  488.08  4346.7  488.46
  4369.1  486.01  4422.2  483.47    4534  480.18  4578.7  477.55  4676.5  475.71
  4704.5  473.52  4749.6  474.86  4788.3  475.43  4816.3  473.93  4838.6   475.2
  4905.7  474.11  4950.5  475.32  4981.2  472.24  4992.9  468.66  4993.2  468.16
  4997.4  468.66  5000.8  470.85  5006.6  470.85  5011.1  472.92  5017.1  473.62
  5147.8  477.32  5219.9  480.34  5242.4  482.58  5284.2  484.38  5364.1  488.76
#Mann= 6 ,-1 , 0
  4109.1     .05       0  4269.1     .07       0  4749.6      .1       0
  4992.9     .05       0  4997.4      .1       0  5284.2     .07       0
Bank Sta=4992.9,4997.4
XS Rating Curve= 0 ,0
Exp/Cntr=0.3,0.1

Type RM Length L Ch R = 1 ,100848  ,455,455,455
BEGIN DESCRIPTION:
Cooperas Creek 131.0
END DESCRIPTION:
XS GIS Cut Line= 3
      2481724.99     13849124.99        2481625.       13849075.
      2480825.02     13848675.01
#Sta/Elev= 30
  4882.9   483.6  4927.6  481.52  4981.9  476.82  4986.3  476.37  4991.9  471.56
  4997.5  471.56  5006.4  465.35  5006.7  464.85    5011  465.35  5025.4  469.39
  5041.1  470.68  5076.6  471.64  5142.8  471.48  5151.2  472.51  5185.2  472.11
  5226.7  471.98  5240.7  473.55  5254.6  473.79  5274.3  473.35  5455.9  474.79
    5523  476.58  5562.1  479.27  5576.1  478.82  5606.8  479.91  5732.6  486.81
    5755  488.18  5763.3  489.46  5808.1  490.39  5873.8   494.1  5889.1  495.14
#Mann= 9 ,-1 , 0
  4882.9     .05       0  4981.9     .12       0  5006.4     .05       0
    5011     .12       0  5041.1      .1       0  5076.6     .12       0
  5185.2     .07       0  5274.3     .05       0  5873.8     .07       0
Bank Sta=5006.4,5011
XS Rating Curve= 0 ,0
Exp/Cntr=0.3,0.1

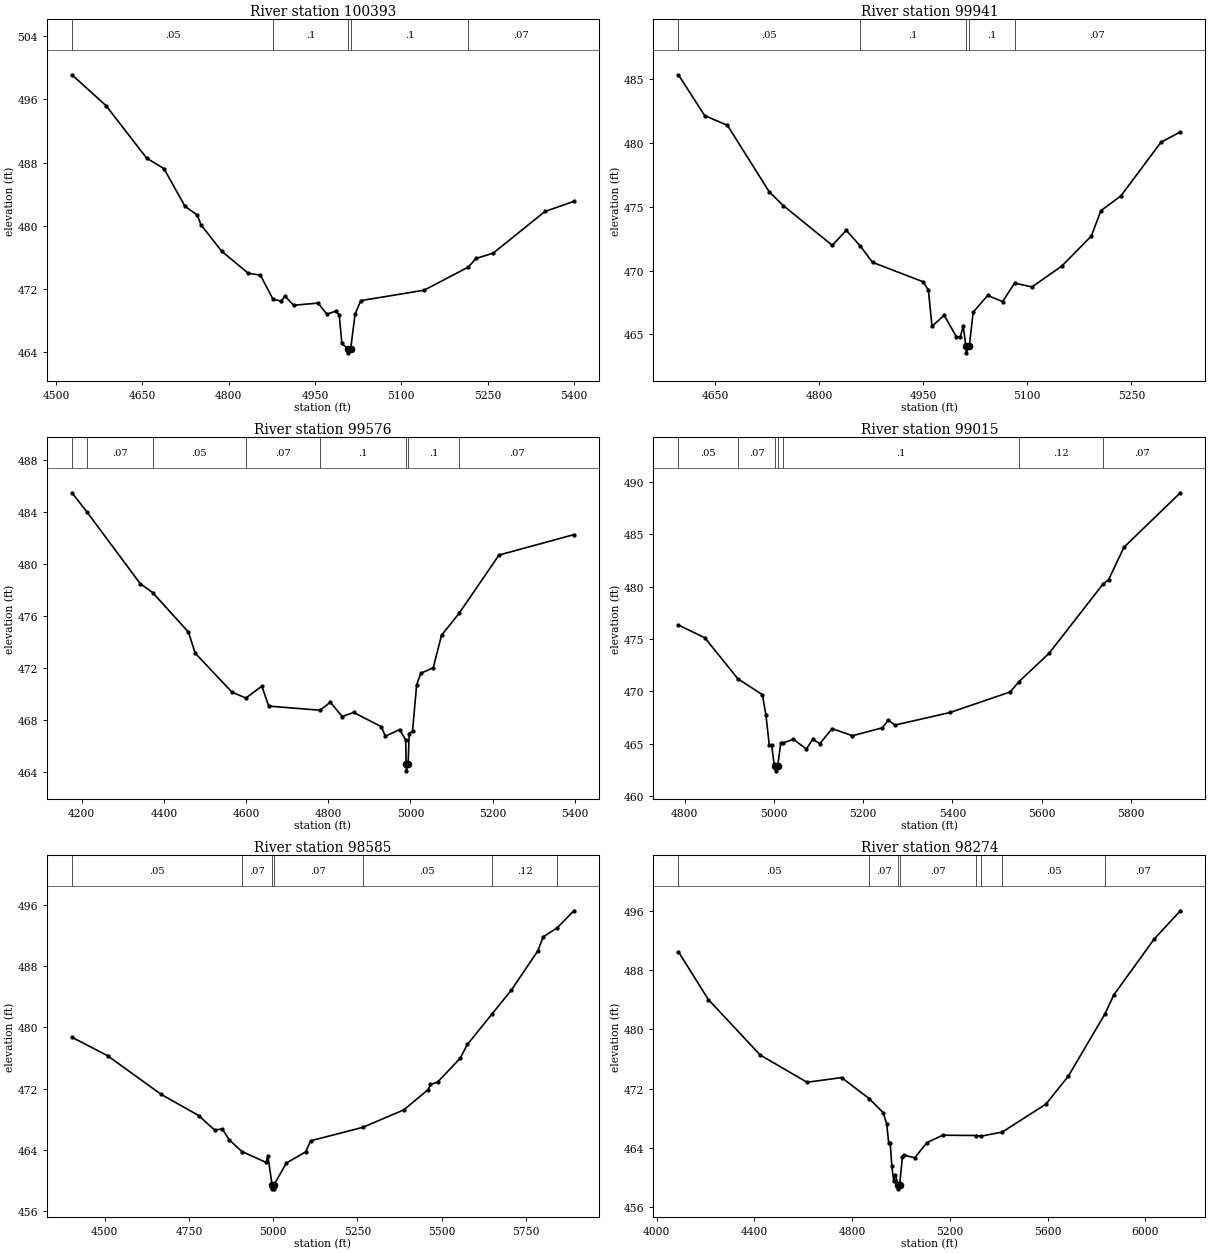
Type RM Length L Ch R = 1 ,100393  ,452,452,452
BEGIN DESCRIPTION:
Cooperas Creek 130.0
END DESCRIPTION:
XS GIS Cut Line= 3
      2481975.02     13849125.03        2481725.       13848725.
        2481725.     13848325.04
#Sta/Elev= 30
  4527.9  499.13  4586.9  495.23  4657.7  488.56  4687.7  487.23  4724.3  482.45
  4745.5  481.36    4752  480.11    4788  476.76    4834  473.97  4855.2  473.73
    4877  470.69  4891.7  470.42  4897.6  471.08    4913  469.91  4955.4  470.19
  4970.7  468.78  4986.1  469.17    4992  468.72  4996.7  465.07  5007.3  464.38
  5007.6  463.88    5012  464.38  5019.6  468.78  5029.6   470.5  5139.6  471.82
  5216.2  474.75  5229.6  475.84  5259.6  476.52  5349.6  481.81  5399.6  483.08
#Mann= 5 ,-1 , 0
  4527.9     .05       0    4877      .1       0  5007.3     .05       0
    5012      .1       0  5216.2     .07       0
Bank Sta=5007.3,5012
XS Rating Curve= 0 ,0
Exp/Cntr=0.3,0.1

Type RM Length L Ch R = 1 ,99941   ,365,365,365
BEGIN DESCRIPTION:
Cooperas Creek 129.0
END DESCRIPTION:
XS GIS Cut Line= 3
        2482125.     13848925.03        2482075.       13848525.
        2481825.       13848325.
#Sta/Elev= 30
  4597.2  485.36    4635  482.16  4667.8   481.4  4728.2  476.17  4748.4   475.1
  4818.9  471.98  4839.1  473.16  4859.3  471.93  4876.9  470.65    4950  469.12
  4957.5  468.46  4962.6  465.63  4980.2   466.5  4997.8  464.81  5003.5  464.81
  5007.6  465.66  5011.6  464.05    5012  463.55  5016.3  464.05    5022  466.74
  5042.8  468.05  5064.4  467.57  5081.6  469.02  5106.8  468.72    5150  470.37
  5192.4  472.72    5206   474.7  5234.9  475.86  5292.5  480.06  5320.5  480.88
#Mann= 5 ,-1 , 0
  4597.2     .05       0  4859.3      .1       0  5011.6     .05       0
  5016.3      .1       0  5081.6     .07       0
Bank Sta=5011.6,5016.3
XS Rating Curve= 0 ,0
Exp/Cntr=0.3,0.1

Type RM Length L Ch R = 1 ,99576   ,561,561,561
BEGIN DESCRIPTION:
Cooperas Creek 128.0
END DESCRIPTION:
XS GIS Cut Line= 3
      2482534.76     13848917.36      2482171.45     13848190.74
      2481765.78     13848136.24
#Sta/Elev= 30
  4176.1  485.51  4213.4     484  4342.1  478.53  4372.6  477.83  4459.5   474.8
  4476.2  473.17  4565.7  470.17  4599.4  469.72  4638.3  470.63  4655.1   469.1
  4780.4  468.78  4804.8   469.4    4834   468.3  4861.9  468.61    4929  467.52
    4939  466.78  4973.7   467.3  4988.5  466.49  4989.6  464.62  4989.9  464.12
  4994.3  464.62    4997  466.99  5005.1  467.18  5015.2  470.75  5025.3  471.62
  5055.5  472.05  5075.7  474.55  5118.3  476.23  5215.6  480.72  5397.8  482.29
#Mann= 8 ,-1 , 0
  4176.1     .05       0  4213.4     .07       0  4372.6     .05       0
  4599.4     .07       0  4780.4      .1       0  4989.6     .05       0
  4994.3      .1       0  5118.3     .07       0
Bank Sta=4989.6,4994.3
XS Rating Curve= 0 ,0
Exp/Cntr=0.3,0.1

Type RM Length L Ch R = 1 ,99015   ,430,430,430
BEGIN DESCRIPTION:
Cooperas Creek 127.0
END DESCRIPTION:
XS GIS Cut Line= 3
        2482675.     13848525.02        2482625.       13848325.
      2482174.98     13847524.96
#Sta/Elev= 30
  4786.2  476.34  4845.5  475.12  4919.6   471.2  4974.3   469.7  4982.1  467.78
  4989.8  464.85  4995.2  464.85  5000.3  463.13  5003.4  462.93  5003.8  462.43
  5008.7  462.93  5015.3  465.05  5020.6  465.09  5043.7  465.44  5072.7  464.51
    5087  465.44    5103  465.03  5130.4  466.46    5176  465.78  5243.2  466.54
  5256.3  467.29  5270.6  466.79  5394.9     468  5529.4  469.96  5548.8  470.94
  5616.1  473.63    5737  480.24  5749.6  480.66    5784  483.76  5910.3  488.96
#Mann= 7 ,-1 , 0
  4786.2     .05       0  4919.6     .07       0  5003.4     .05       0
  5008.7     .07       0  5020.6      .1       0  5548.8     .12       0
    5737     .07       0
Bank Sta=5003.4,5008.7
XS Rating Curve= 0 ,0
Exp/Cntr=0.3,0.1

Type RM Length L Ch R = 1 ,98585   ,311,311,311
BEGIN DESCRIPTION:
X18533
END DESCRIPTION:
XS GIS Cut Line= 3
      2482752.73     13848620.61      2482795.11     13847960.65
      2482353.63     13847259.12
#Sta/Elev= 30
  4402.4  478.72  4508.2   476.3  4667.7  471.23  4778.8  468.47  4825.9  466.57
  4848.9  466.72    4869  465.31  4907.2  463.76  4979.1  462.33  4984.1  463.23
  4996.6  459.38    4997  458.88  5001.5  458.88  5001.9  459.38  5039.3  462.27
    5096  463.71  5111.3  465.17  5265.3  466.92    5388  469.22  5460.3  471.88
  5466.9  472.54  5488.1  472.85  5554.8  475.95  5576.4  477.77  5649.4  481.75
  5707.1  484.89    5786  490.05  5801.3  491.85  5843.3  493.04  5892.6  495.27
#Mann= 7 ,-1 , 0
  4402.4     .05       0  4907.2     .07       0  4996.6     .05       0
  5001.9     .07       0  5265.3     .05       0  5649.4     .12       0
  5843.3     .07       0
Bank Sta=4996.6,5001.9
XS Rating Curve= 0 ,0
Exp/Cntr=0.3,0.1

Type RM Length L Ch R = 1 ,98274   ,312,312,312
BEGIN DESCRIPTION:
Cooperas Creek 126.0
END DESCRIPTION:
XS GIS Cut Line= 3
      2483642.81     13848759.91      2483097.86     13848148.35
      2482365.19     13847155.32
#Sta/Elev= 30
  4089.4  490.49  4211.9  484.03  4424.2  476.54  4615.7  472.87    4757   473.5
  4869.8  470.66  4926.6  468.78  4941.2  467.29  4949.6  464.72  4955.8  464.68
  4962.4   461.5  4970.5  459.49  4976.7   460.4  4988.4  458.98  4988.9  458.48
  4994.2  458.98  5005.9  462.84  5012.2  463.04  5056.1  462.67  5106.2  464.73
  5170.9  465.72  5307.8  465.68  5327.6  465.59  5414.3  466.15  5592.7  469.91
  5684.6   473.7  5834.5  482.11  5870.4  484.66  6035.4  492.19  6142.6  496.02
#Mann= 8 ,-1 , 0
  4089.4     .05       0  4869.8     .07       0  4988.4     .05       0
  4994.2     .07       0  5307.8     .05       0  5327.6     .07       0
  5414.3     .05       0  5834.5     .07       0
Bank Sta=4988.4,4994.2
XS Rating Curve= 0 ,0
Exp/Cntr=0.3,0.1

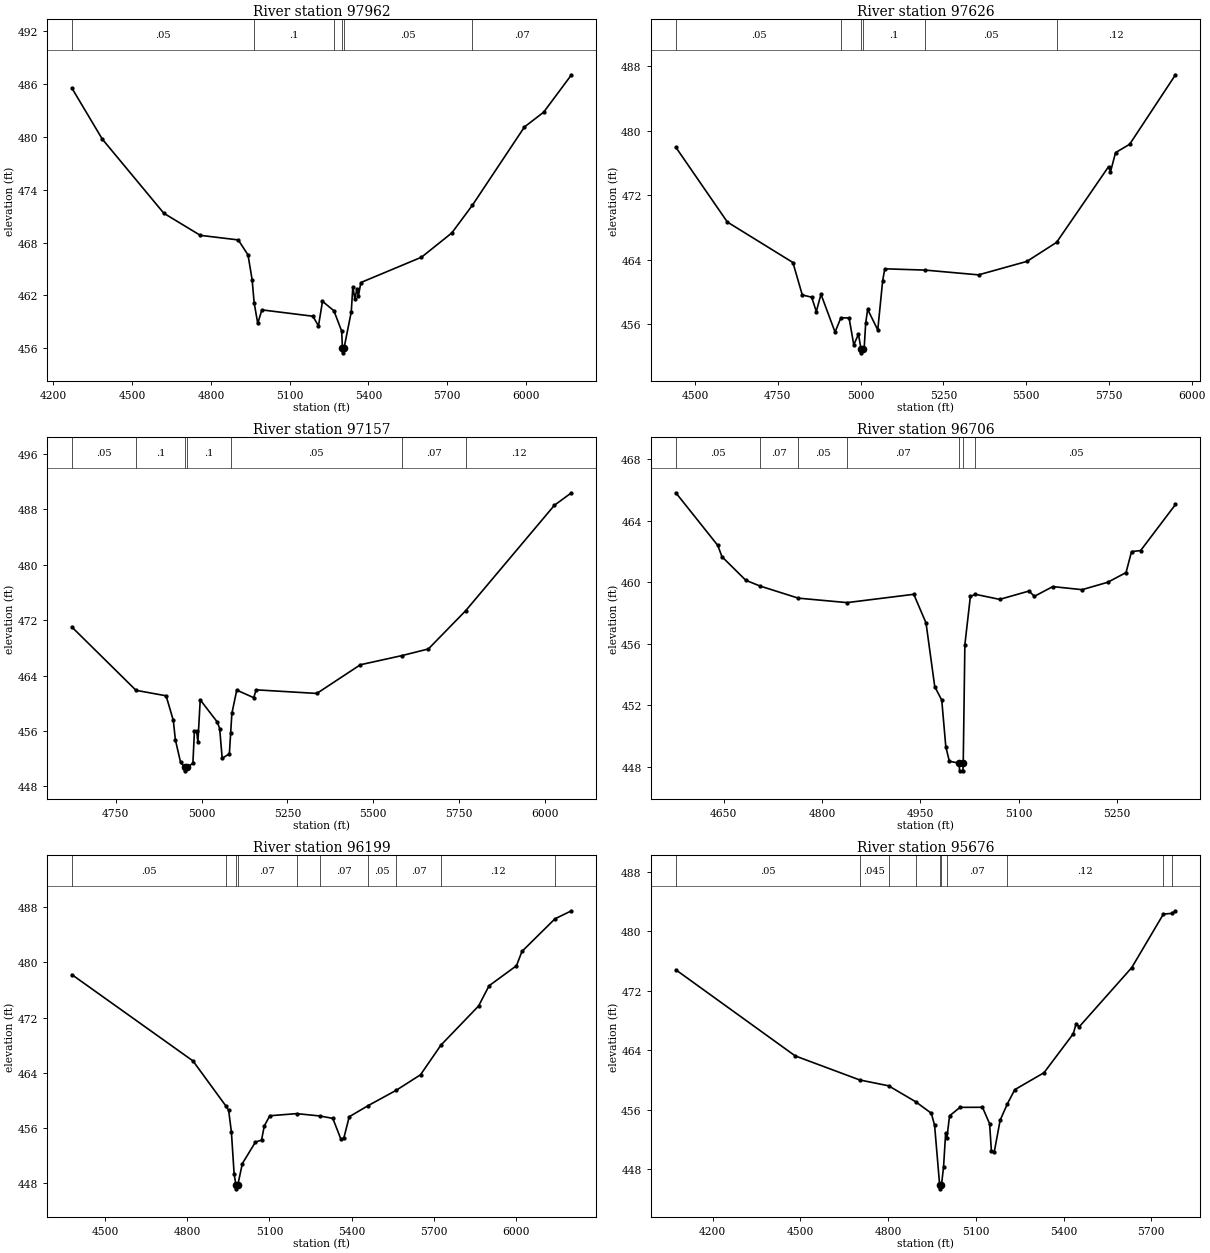
Type RM Length L Ch R = 1 ,97962   ,336,336,336
BEGIN DESCRIPTION:
Cooperas Creek 125.0
END DESCRIPTION:
XS GIS Cut Line= 3
      2483679.16     13848669.12      2483309.78     13848039.36
      2482686.13     13847046.36
#Sta/Elev= 30
  4270.4  485.52  4386.3  479.73  4620.8  471.32  4759.6  468.82  4904.1   468.3
  4941.3   466.6    4957  463.78  4964.6  461.18  4978.4  458.83    4994  460.37
  5188.4  459.65  5209.6  458.55  5224.9  461.34  5268.4  460.27  5297.9  457.96
  5300.9     456  5301.4   455.5  5306.7     456  5334.5  460.15  5340.4     463
  5348.1  461.63  5355.7   462.7  5361.6  461.93    5371  463.47  5601.9  466.34
  5717.3  469.09  5795.9  472.24  5994.1  481.11  6067.2  482.78  6173.1  487.02
#Mann= 6 ,-1 , 0
  4270.4     .05       0  4964.6      .1       0  5268.4     .05       0
  5300.9     .05       0  5306.7     .05       0  5795.9     .07       0
Bank Sta=5300.9,5306.7
XS Rating Curve= 0 ,0
Exp/Cntr=0.3,0.1

Type RM Length L Ch R = 1 ,97626   ,469,469,469
BEGIN DESCRIPTION:
Cooperas Creek 124.0
END DESCRIPTION:
XS GIS Cut Line= 3
      2483925.02     13848225.02        2483525.       13847825.
      2483025.01     13847025.01
#Sta/Elev= 30
  4442.1  477.97  4597.7   468.7  4795.7  463.68    4824  459.66  4852.3  459.38
  4866.4   457.6  4880.5  459.74    4923  455.05  4940.7  456.83  4965.4   456.8
  4979.5  453.47  4993.7  454.79  5001.3  452.98  5001.8  452.48  5007.2  452.98
  5010.8  452.98  5015.5  456.15  5021.4  457.87    5052  455.32  5066.8  461.44
  5073.3   462.9  5195.4  462.74  5356.3  462.15  5502.5  463.82  5592.1  466.18
    5749  475.56  5754.9  474.93  5770.2  477.31  5812.7  478.34  5951.2  486.96
#Mann= 6 ,-1 , 0
  4442.1     .05       0  4940.7      .1       0  5001.3     .05       0
  5007.2      .1       0  5195.4     .05       0  5592.1     .12       0
Bank Sta=5001.3,5007.2
XS Rating Curve= 0 ,0
Exp/Cntr=0.3,0.1

Type RM Length L Ch R = 1 ,97157   ,451,451,451
BEGIN DESCRIPTION:
Cooperas Creek 123.0
END DESCRIPTION:
XS GIS Cut Line= 3
      2484024.97     13848024.96        2483825.       13847725.
        2483025.       13846975.
#Sta/Elev= 30
  4621.6  471.02  4808.8  461.88  4896.5  461.09  4917.5  457.54  4923.5  454.75
  4938.5  451.52  4950.6  450.76  4951.1  450.26  4956.5  450.76  4974.6  451.33
  4979.1  455.98  4985.5  455.98  4989.2   454.4    4996  460.51  5045.8   457.3
  5052.7  456.37    5060  452.07    5081  452.72  5084.8  455.75  5088.3  458.54
  5102.5  461.91  5151.9  460.82  5159.2  461.95    5336  461.43    5463  465.57
    5584  466.89  5661.3  467.85  5770.3  473.38  6029.1   488.6  6078.7  490.39
#Mann= 7 ,-1 , 0
  4621.6     .05       0  4808.8      .1       0  4950.6     .05       0
  4956.5      .1       0  5084.8     .05       0    5584     .07       0
  5770.3     .12       0
Bank Sta=4950.6,4956.5
XS Rating Curve= 0 ,0
Exp/Cntr=0.3,0.1

Type RM Length L Ch R = 1 ,96706   ,507,507,507
BEGIN DESCRIPTION:
Cooperas Creek 122.0
END DESCRIPTION:
XS GIS Cut Line= 3
      2484175.02     13847825.04        2484025.       13847425.
      2483724.96     13847274.98
#Sta/Elev= 30
  4576.9   465.8    4641  462.38  4647.3  461.65  4683.7  460.12  4705.2  459.75
  4763.8  458.96  4838.3  458.67  4940.1  459.21  4958.8  457.35  4972.1  453.22
  4982.8  452.34    4989  449.32  4994.4  448.37  5009.5  448.25    5010  447.75
  5015.1  447.75  5015.6  448.25  5018.1  455.94  5026.5  459.07  5034.1  459.21
  5071.2  458.88  5115.9  459.42  5124.3  459.08  5152.3  459.71    5197  459.51
  5236.1  459.99  5264.1  460.62  5272.5  461.98  5286.4  462.05  5339.6  465.04
#Mann= 7 ,-1 , 0
  4576.9     .05       0  4705.2     .07       0  4763.8     .05       0
  4838.3     .07       0  5009.5     .05       0  5015.6     .07       0
  5034.1     .05       0
Bank Sta=5009.5,5015.6
XS Rating Curve= 0 ,0
Exp/Cntr=0.3,0.1

Type RM Length L Ch R = 1 ,96199   ,523,523,523
BEGIN DESCRIPTION:
Cooperas Creek 121.0
END DESCRIPTION:
XS GIS Cut Line= 3
       2484302.8     13848196.81      2484327.02     13847524.69
       2484302.8      13846374.2
#Sta/Elev= 30
  4378.8  478.21  4820.9  465.72  4941.2  459.19    4951  458.57    4961  455.47
    4971  449.38  4977.9  447.72  4978.4  447.22  4984.1  447.72    5001  450.87
  5048.7  453.98    5071  454.27    5081  456.31  5101.1  457.79  5199.3   458.1
    5284  457.76  5331.1  457.41  5361.1  454.36  5371.1  454.53  5391.1  457.65
  5460.2  459.26  5562.3  461.47  5651.2  463.72  5725.7  468.01  5863.1  473.67
  5901.2  476.59  6001.3  479.49  6021.3  481.56  6141.9  486.28  6202.1  487.44
#Mann= 10 ,-1 , 0
  4378.8     .05       0  4941.2     .07       0  4977.9     .05       0
  4984.1     .07       0  5199.3     .12       0    5284     .07       0
  5460.2     .05       0  5562.3     .07       0  5725.7     .12       0
  6141.9     .07       0
Bank Sta=4977.9,4984.1
XS Rating Curve= 0 ,0
Exp/Cntr=0.3,0.1

Type RM Length L Ch R = 1 ,95676   ,368,368,368
BEGIN DESCRIPTION:
X18532
END DESCRIPTION:
XS GIS Cut Line= 4
      2484387.56      13848160.5      2484581.33      13847603.4
      2484478.39     13847131.12      2484478.39     13846495.32
#Sta/Elev= 30
  4073.6   474.8  4481.9  463.22  4702.9  459.98  4801.2   459.2  4894.1  457.05
  4947.3  455.51  4958.6   453.9    4976  445.84  4976.5  445.34  4982.2  445.84
  4989.3   448.3  4996.4  452.82  5000.7  452.16  5009.8  455.16  5045.5   456.3
  5122.4  456.31  5146.8   454.1  5152.9  450.45  5162.9  450.34  5182.9  454.58
  5207.7  456.78  5232.9  458.68  5332.9  460.96  5432.9  466.19  5442.9  467.57
  5452.9  467.12  5632.9  475.09  5741.3   482.3  5771.1  482.39  5782.6  482.74
#Mann= 10 ,-1 , 0
  4073.6     .05       0  4702.9    .045       0  4801.2     .07       0
  4894.1     .12       0    4976     .05       0  4982.2     .12       0
  5000.7     .07       0  5207.7     .12       0  5741.3     .07       0
  5771.1     .12       0
Bank Sta=4976,4982.2
XS Rating Curve= 0 ,0
Exp/Cntr=0.3,0.1