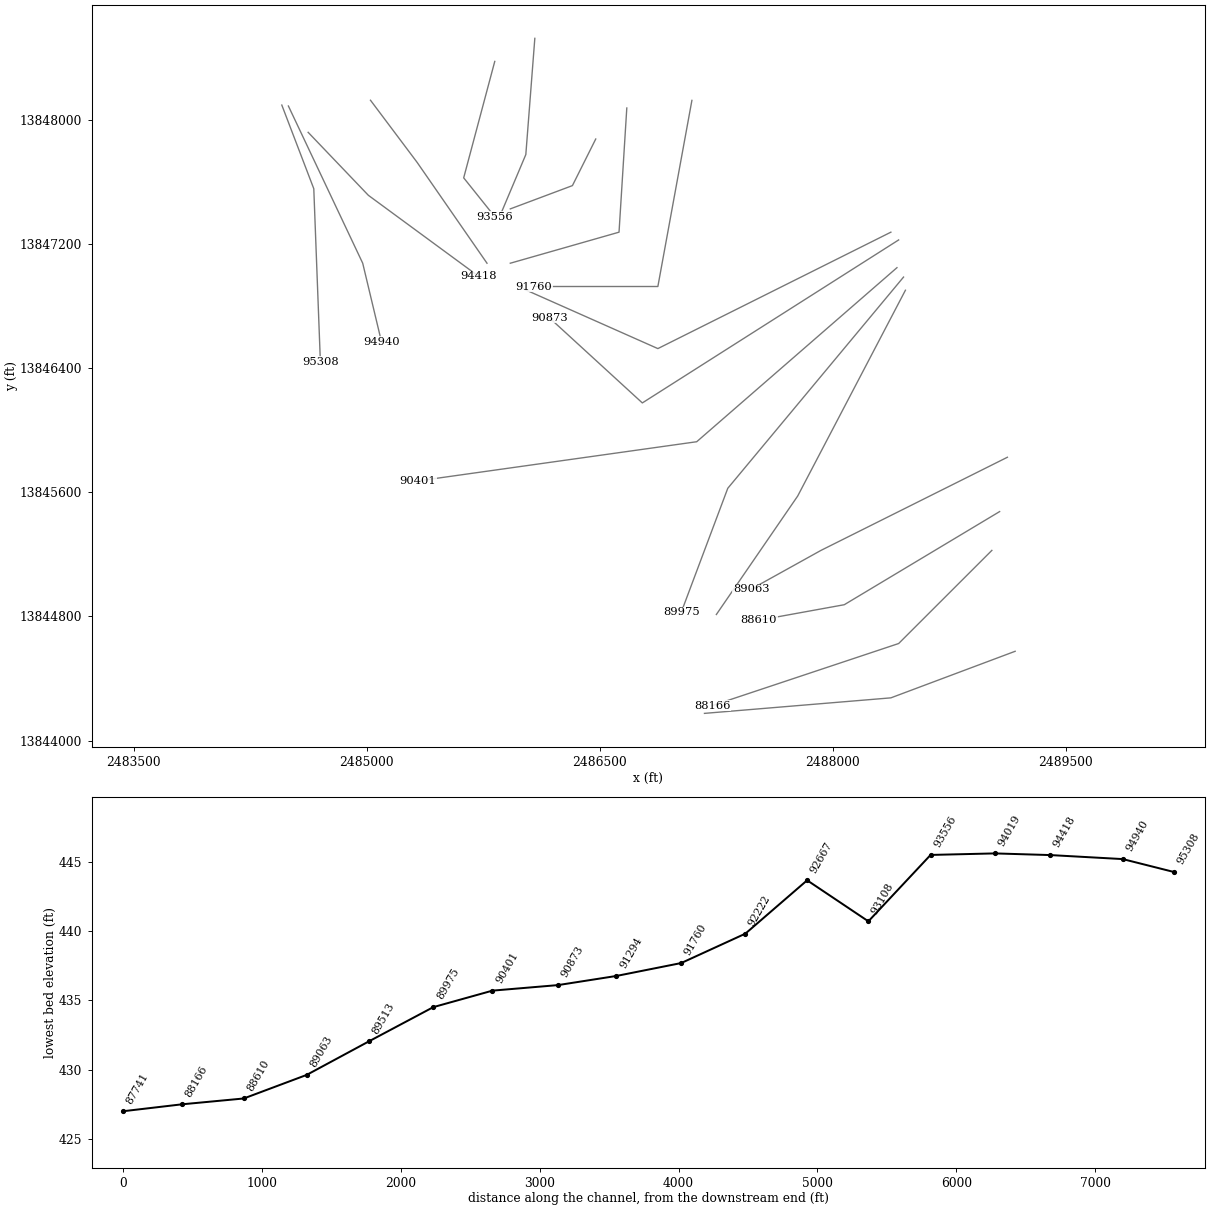
HEC-RAS study Copperas Creek.prj: Copperas Creek Base Level Engineering

--- Copperas Creek.g01 (geometry) --- (continued)

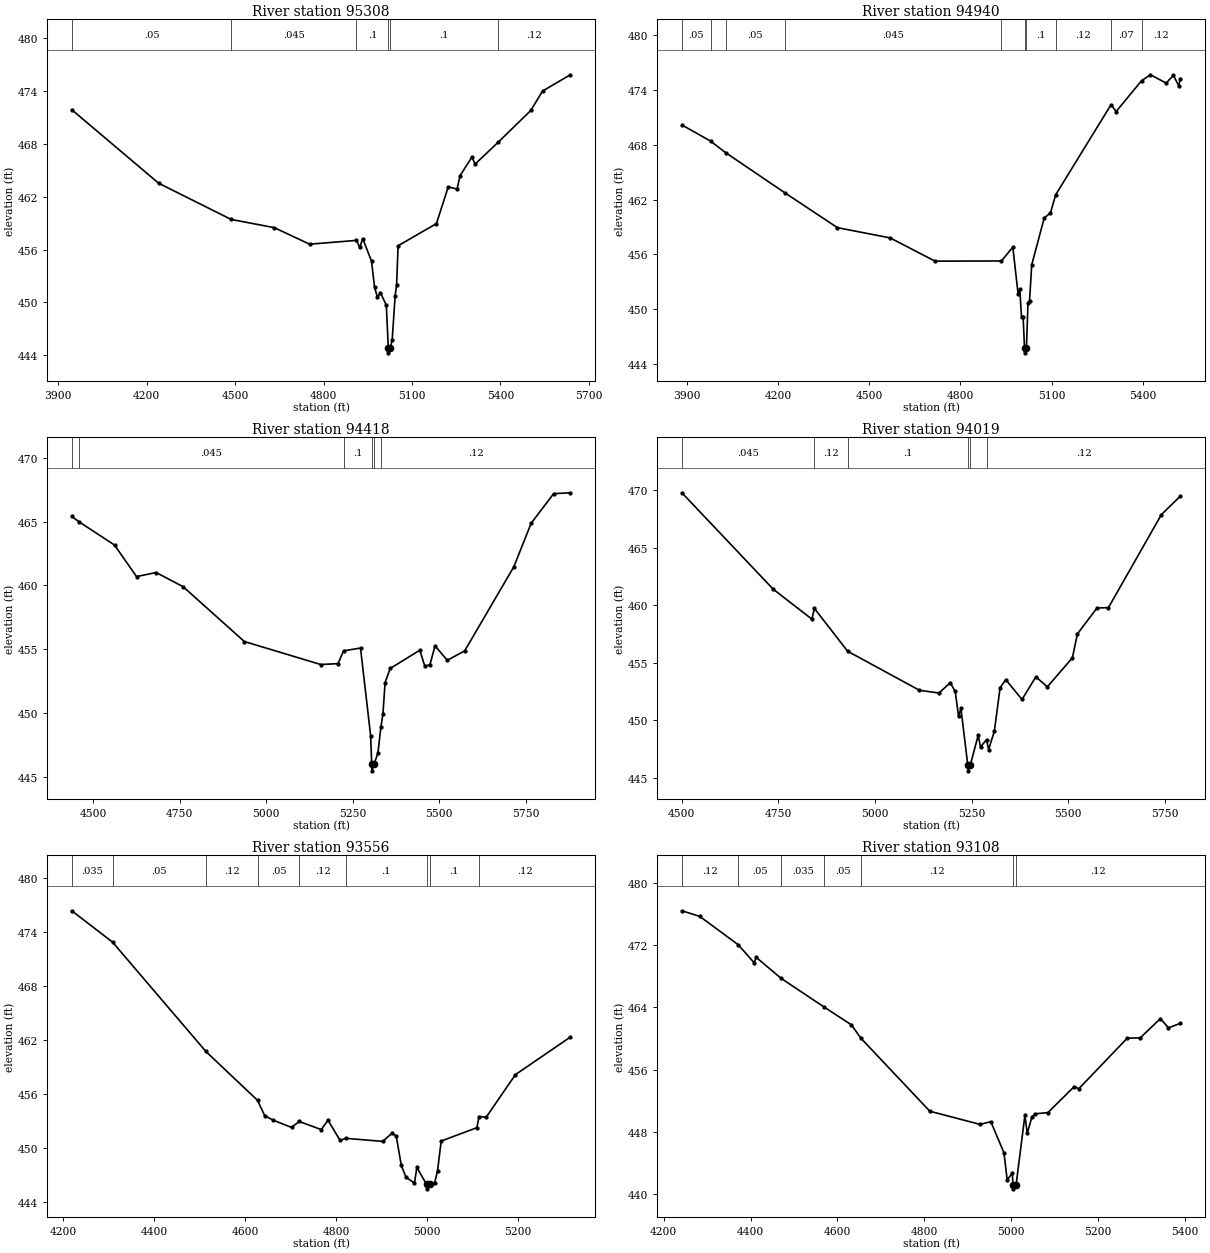
Type RM Length L Ch R = 1 ,95308   ,368,368,368
BEGIN DESCRIPTION:
X18531
END DESCRIPTION:
XS GIS Cut Line= 3
      2484454.17     13848093.87      2484660.04     13847554.96
      2484702.43     13846440.87
#Sta/Elev= 30
  3945.6  471.88  4240.5  463.53  4486.3  459.42  4632.5  458.49  4752.6  456.61
  4911.4  457.04  4922.7  456.24  4932.8  457.24  4962.8  454.67  4972.8  451.75
  4982.8  450.57  4992.8  451.11  5012.8  449.68  5019.7  444.77  5020.2  444.27
  5025.9  444.77  5032.8  445.74  5042.7  450.74  5047.7  451.96  5052.8  456.43
  5182.9  458.95    5223  463.12    5253  462.87    5263  464.39    5303  466.49
  5314.3  465.71  5393.1  468.21  5503.2   471.8  5543.2  474.01  5637.4  475.85
#Mann= 6 ,-1 , 0
  3945.6     .05       0  4486.3    .045       0  4911.4      .1       0
  5019.7     .05       0  5025.9      .1       0  5393.1     .12       0
Bank Sta=5019.7,5025.9
XS Rating Curve= 0 ,0
Exp/Cntr=0.3,0.1

Type RM Length L Ch R = 1 ,94940   ,522,522,522
BEGIN DESCRIPTION:
Cooperas Creek 120.0
END DESCRIPTION:
XS GIS Cut Line= 3
      2484496.54     13848087.85        2484975.       13847075.
      2485095.77     13846568.98
#Sta/Elev= 30
  3883.6  470.18    3978  468.41  4027.3  467.15  4223.4  462.72  4395.5  458.92
  4568.8   457.8  4716.4  455.25  4934.9  455.27  4972.4  456.79  4989.6   451.7
  4995.2   452.2    5001  449.12  5006.3  449.12  5010.9   445.7  5011.4   445.2
  5017.2   445.7  5022.3  450.68  5027.4  450.92  5034.6  454.85  5075.7  459.99
  5096.3  460.54  5113.4  462.53  5295.7  472.41  5312.2  471.65  5396.2  475.04
  5425.3  475.68  5476.7  474.77  5500.8  475.61  5517.8   474.5    5524  475.27
#Mann= 10 ,-1 , 0
  3883.6     .05       0    3978     .07       0  4027.3     .05       0
  4223.4    .045       0  4934.9      .1       0  5010.9     .05       0
  5017.2      .1       0  5113.4     .12       0  5295.7     .07       0
  5396.2     .12       0
Bank Sta=5010.9,5017.2
XS Rating Curve= 0 ,0
Exp/Cntr=0.3,0.1

Type RM Length L Ch R = 1 ,94418   ,399,399,399
BEGIN DESCRIPTION:
Cooperas Creek 119.0
END DESCRIPTION:
XS GIS Cut Line= 3
      2484623.73     13847918.24      2485011.23     13847512.58
      2485719.65     13846991.86
#Sta/Elev= 30
  4438.6   465.4  4459.5  464.98  4562.1  463.16  4625.6  460.69  4682.2  461.01
  4760.2   459.9    4937  455.61  5157.7  453.81  5207.8  453.88  5223.7  454.88
  5272.6   455.1  5301.9  448.22  5304.9  445.99  5305.4  445.49  5311.3  445.99
  5322.8  446.87  5331.4   448.9  5337.4  449.95  5343.6   452.4  5358.3   453.5
  5443.9  454.93  5458.5  453.67  5473.2   453.8  5487.8  455.27  5523.3  454.14
  5573.5  454.88  5715.5  461.46  5765.6  464.87  5830.4  467.18  5878.8  467.25
#Mann= 6 ,-1 , 0
  4438.6     .05       0  4459.5    .045       0  5223.7      .1       0
  5304.9    .045       0  5311.3      .1       0  5331.4     .12       0
Bank Sta=5304.9,5311.3
XS Rating Curve= 0 ,0
Exp/Cntr=0.3,0.1

Type RM Length L Ch R = 1 ,94019   ,463,463,463
BEGIN DESCRIPTION:
Cooperas Creek 118.0
END DESCRIPTION:
XS GIS Cut Line= 3
      2485024.99     13848125.01        2485325.       13847725.
      2485775.01     13847074.99
#Sta/Elev= 30
  4500.2  469.77  4736.7  461.39  4836.7  458.79  4843.2  459.72  4929.3     456
  5115.1  452.61  5165.8  452.37  5194.8  453.27  5207.7  452.51  5216.4  450.34
  5222.5  451.03  5240.2  446.11  5240.7  445.61  5246.8  446.11  5267.1  448.69
  5273.2  447.69  5288.8  448.32  5294.1  447.46    5309  449.05  5323.9  452.84
  5338.7  453.53  5380.6  451.81  5416.4  453.78  5446.2  452.91    5511  455.43
  5523.9   457.5  5574.6  459.76  5604.3  459.79  5741.5  467.88  5790.8  469.49
#Mann= 6 ,-1 , 0
  4500.2    .045       0  4843.2     .12       0  4929.3      .1       0
  5240.2     .05       0  5246.8      .1       0  5288.8     .12       0
Bank Sta=5240.2,5246.8
XS Rating Curve= 0 ,0
Exp/Cntr=0.3,0.1

Type RM Length L Ch R = 1 ,93556   ,448,448,448
BEGIN DESCRIPTION:
Cooperas Creek 117.0
END DESCRIPTION:
XS GIS Cut Line= 3
      2485825.01     13848375.02        2485625.       13847625.
      2485825.01     13847374.99
#Sta/Elev= 30
  4218.8  476.33  4308.5  472.85  4513.7  460.73  4627.3  455.31  4643.2   453.6
  4661.9  453.11    4702  452.31  4718.9  452.97  4767.3  452.07  4782.2  453.11
  4808.7  450.87  4821.5   451.1  4902.5  450.76  4922.6  451.65  4932.3  451.37
  4943.3  448.12  4953.6  446.79  4972.4  446.14  4977.6  447.87  4998.9     446
  4999.4   445.5  5005.5     446  5016.6  446.14    5023  447.47  5031.1   450.8
  5109.5  452.28  5114.4  453.51  5130.3  453.46  5194.3  458.16  5315.2  462.33
#Mann= 9 ,-1 , 0
  4218.8    .035       0  4308.5     .05       0  4513.7     .12       0
  4627.3     .05       0  4718.9     .12       0  4821.5      .1       0
  4998.9     .05       0  5005.5      .1       0  5114.4     .12       0
Bank Sta=4998.9,5005.5
XS Rating Curve= 0 ,0
Exp/Cntr=0.3,0.1

Type RM Length L Ch R = 1 ,93108   ,441,441,441
BEGIN DESCRIPTION:
Cooperas Creek 116.0
END DESCRIPTION:
XS GIS Cut Line= 3
      2486082.96     13848523.75        2486025.       13847775.
       2485871.1      13847409.8
#Sta/Elev= 30
  4242.1  476.39  4283.2  475.67  4371.8  472.03  4408.2  469.73  4413.2  470.41
  4470.7  467.71  4569.6  464.03    4632  461.76    4654  460.04  4812.6  450.67
  4928.1  448.98    4953  449.33  4983.1  445.35  4990.6  441.88  5002.2   442.7
  5004.3  441.21  5004.8  440.71  5011.1  441.21  5031.4  450.15  5036.8  447.83
  5047.4   449.9  5055.1  450.34  5084.3  450.49    5145  453.84  5155.5  453.56
  5266.6  460.03  5296.9  460.09  5343.3  462.56  5361.6  461.36  5389.4  461.96
#Mann= 7 ,-1 , 0
  4242.1     .12       0  4371.8     .05       0  4470.7    .035       0
  4569.6     .05       0    4654     .12       0  5004.3     .05       0
  5011.1     .12       0
Bank Sta=5004.3,5011.1
XS Rating Curve= 0 ,0
Exp/Cntr=0.3,0.1

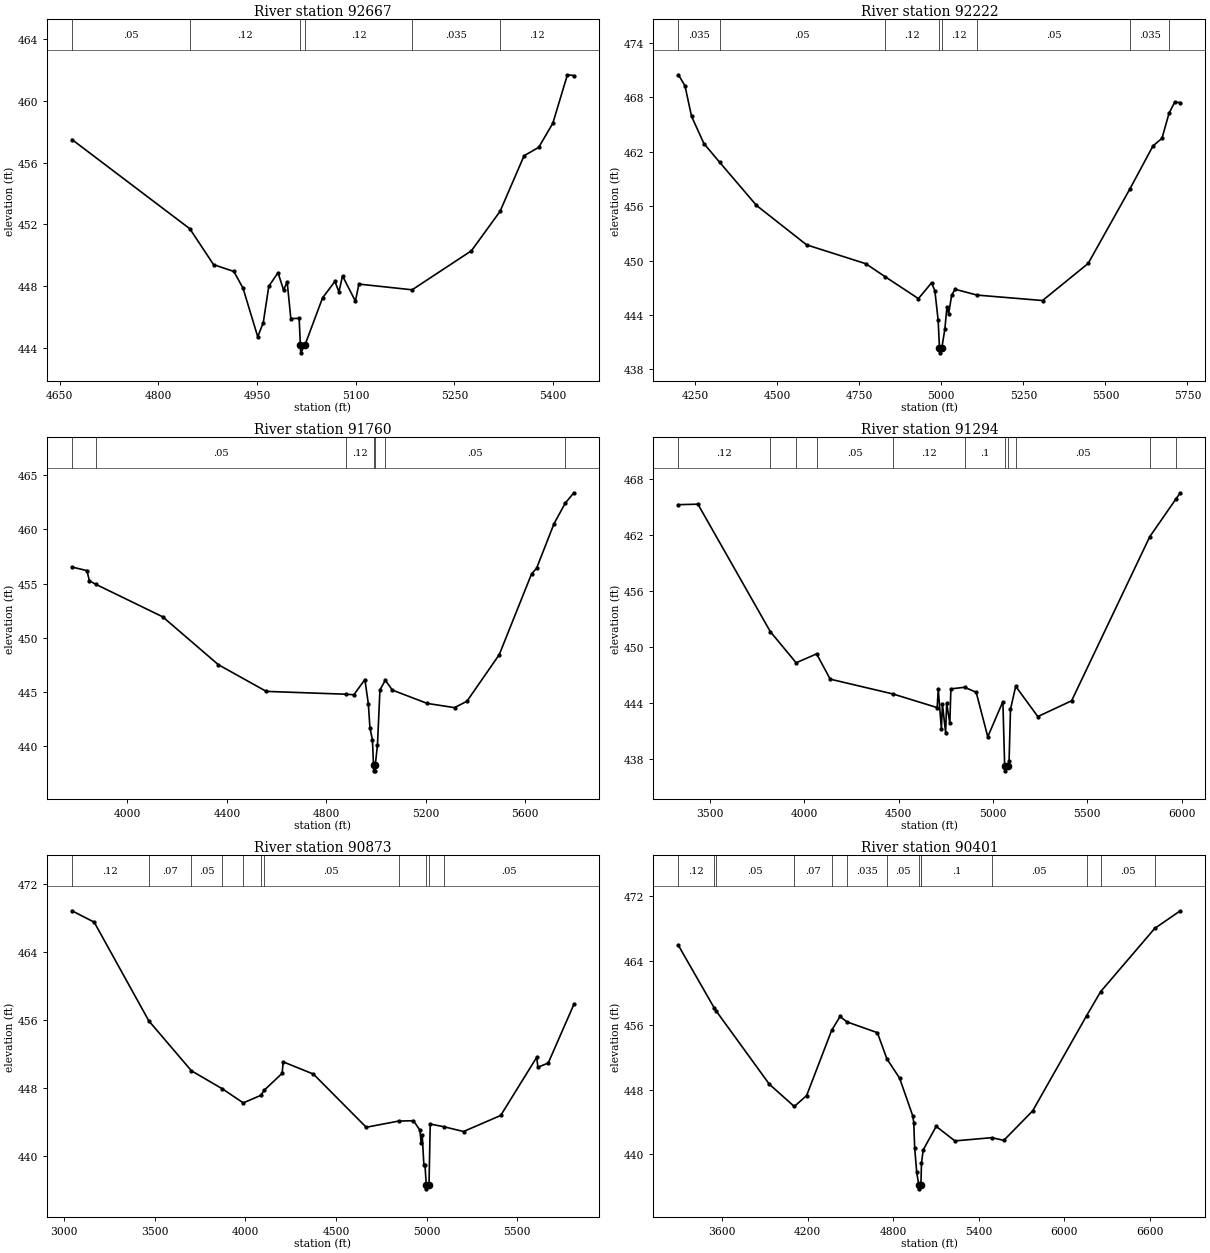
Type RM Length L Ch R = 1 ,92667   ,445,445,445
BEGIN DESCRIPTION:
Cooperas Creek 115.0
END DESCRIPTION:
XS GIS Cut Line= 3
      2486475.01     13847875.02        2486325.       13847575.
      2485925.03     13847425.01
#Sta/Elev= 30
  4668.9  457.51    4848  451.72  4884.1  449.39  4914.9  448.95  4928.9  447.86
  4951.2  444.71  4959.6  445.63    4968  447.99    4982  448.87  4990.4  447.75
  4995.9  448.27  5001.5  445.89  5014.1  445.91    5016  444.17  5016.5  443.67
  5022.9  444.17  5049.7  447.24  5068.4   448.3  5074.6  447.63    5080  448.66
  5099.6  447.02  5104.9  448.13  5185.8  447.76  5275.8  450.29  5319.4  452.85
  5355.9  456.46  5378.1     457  5399.5  458.56  5421.7  461.71  5431.5  461.66
#Mann= 6 ,-1 , 0
  4668.9     .05       0    4848     .12       0    5016     .05       0
  5022.9     .12       0  5185.8    .035       0  5319.4     .12       0
Bank Sta=5016,5022.9
XS Rating Curve= 0 ,0
Exp/Cntr=0.3,0.1

Type RM Length L Ch R = 1 ,92222   ,462,462,462
BEGIN DESCRIPTION:
Cooperas Creek 114.0
END DESCRIPTION:
XS GIS Cut Line= 3
        2486675.     13848074.96        2486625.       13847275.
      2485925.03     13847075.01
#Sta/Elev= 30
  4198.8  470.49  4218.8  469.27  4238.8  465.91  4276.4  462.91  4324.4  460.84
  4436.7  456.08  4589.5  451.73  4769.9  449.65  4827.8  448.24  4930.2   445.8
  4970.3  447.55  4980.3  446.67  4990.3  443.43  4994.4  440.32  4994.9  439.82
  5001.3  440.32  5010.7  442.43  5017.2   444.9  5022.4  444.15  5031.5  446.18
  5041.9  446.83    5109  446.19  5308.4  445.59  5447.5  449.68  5575.1  457.93
  5645.1  462.65  5672.4  463.48  5693.9  466.25  5711.4  467.48  5728.3  467.42
#Mann= 8 ,-1 , 0
  4198.8    .035       0  4324.4     .05       0  4827.8     .12       0
  4994.4     .05       0  5001.3     .12       0    5109     .05       0
  5575.1    .035       0  5693.9     .12       0
Bank Sta=4994.4,5001.3
XS Rating Curve= 0 ,0
Exp/Cntr=0.3,0.1

Type RM Length L Ch R = 1 ,91760   ,466,466,466
BEGIN DESCRIPTION:
Cooperas Creek 113.0
END DESCRIPTION:
XS GIS Cut Line= 3
      2487094.13     13848124.09        2486875.       13846925.
      2486075.05       13846925.
#Sta/Elev= 30
  3776.7  456.53  3836.8   456.2  3846.9  455.26    3873  454.93  4141.7  451.93
  4365.4  447.51  4558.5  445.04  4878.4  444.78  4910.7  444.73    4955  446.13
    4969  443.88  4975.3  441.68  4985.5  440.55  4989.7   438.2  4990.2   437.7
  4996.1   437.7  4996.6   438.2  5005.6  440.07  5015.6  445.18  5037.2  446.07
  5065.6  445.16  5205.6  443.93  5315.6  443.54  5365.6  444.13  5495.6  448.44
  5625.6   455.9  5645.6  456.41  5715.6  460.52  5760.6  462.42  5795.6  463.39
#Mann= 7 ,-1 , 0
  3776.7     .12       0    3873     .05       0  4878.4     .12       0
  4989.7     .05       0  4996.6     .12       0  5037.2     .05       0
  5760.6    .035       0
Bank Sta=4989.7,4996.6
XS Rating Curve= 0 ,0
Exp/Cntr=0.3,0.1

Type RM Length L Ch R = 1 ,91294   ,421,421,421
BEGIN DESCRIPTION:
Cooperas Creek 112.0
END DESCRIPTION:
XS GIS Cut Line= 3
        2488375.       13847275.        2486875.       13846525.
      2485975.04     13846924.98
#Sta/Elev= 30
  3331.8  465.22  3435.2  465.27  3819.2  451.65  3956.1  448.32  4064.7  449.27
  4136.8  446.57  4470.8  444.98  4704.2  443.53  4709.8  445.51  4726.5  441.26
  4732.1  443.89  4748.9  440.85  4754.5  444.01  4771.3  441.85  4776.9  445.53
  4849.5   445.7    4911  445.17  4972.5  440.41  5052.6  444.17  5062.1  437.27
  5062.6  436.77  5077.4  437.27  5085.5  437.81    5093  443.34  5120.5  445.81
    5238  442.57  5417.2  444.26  5831.8   461.8  5969.4   465.8  5993.7  466.49
#Mann= 11 ,-1 , 0
  3331.8     .12       0  3819.2     .07       0  3956.1    .035       0
  4064.7     .05       0  4470.8     .12       0  4849.5      .1       0
  5062.1     .05       0  5077.4      .1       0  5120.5     .05       0
  5831.8    .035       0  5969.4     .12       0
Bank Sta=5062.1,5077.4
XS Rating Curve= 0 ,0
Exp/Cntr=0.3,0.1

Type RM Length L Ch R = 1 ,90873   ,472,472,472
BEGIN DESCRIPTION:
Cooperas Creek 111.0
END DESCRIPTION:
XS GIS Cut Line= 3
      2488424.99     13847224.99        2486775.       13846175.
      2486174.99     13846725.01
#Sta/Elev= 30
  3043.1  468.85  3165.9  467.51  3467.2  455.89  3702.3  450.01  3873.7  447.88
  3988.4  446.23  4085.8  447.12  4103.1   447.7    4203  449.71  4208.9  451.06
  4375.7  449.62    4667  443.36  4846.3  444.09  4927.7  444.13  4963.3  443.02
  4970.1  441.51    4976  442.45  4985.3  438.87  4991.2  438.92  4998.3  436.61
  4998.8  436.11  5013.6  436.61  5020.1  443.74  5095.8  443.42  5203.9  442.86
  5409.2  444.75  5607.8   451.6  5614.5  450.43  5671.3  450.92  5812.8  457.82
#Mann= 11 ,-1 , 0
  3043.1     .12       0  3467.2     .07       0  3702.3     .05       0
  3873.7    .035       0  3988.4     .05       0  4085.8    .035       0
  4103.1     .05       0  4846.3      .1       0  4998.3     .05       0
  5013.6      .1       0  5095.8     .05       0
Bank Sta=4998.3,5013.6
XS Rating Curve= 0 ,0
Exp/Cntr=0.3,0.1

Type RM Length L Ch R = 1 ,90401   ,426,426,426
BEGIN DESCRIPTION:
Cooperas Creek 110.0
END DESCRIPTION:
XS GIS Cut Line= 3
       2488414.1     13847046.32        2487125.       13845925.
      2485328.05     13845672.14
#Sta/Elev= 30
    3292  465.92  3543.6  458.15  3556.9  457.79    3930   448.7  4105.5  445.93
  4192.1  447.29  4367.6  455.38  4426.6   457.1  4474.9  456.43  4688.6  455.09
    4756  451.82  4844.3  449.46  4936.4   444.8  4944.1  443.94  4950.7  440.72
  4964.9  437.77  4979.1  436.21  4979.6  435.71  4994.4  436.21  4998.2   438.9
  5010.6  440.56  5101.5  443.46  5232.8  441.66  5492.3  442.06  5576.2  441.73
  5778.1  445.37  6157.1  457.19  6256.2  460.19  6635.4  468.03  6815.2  470.22
#Mann= 14 ,-1 , 0
    3292     .12       0  3543.6     .07       0  3556.9     .05       0
  4105.5     .07       0  4367.6     .05       0  4474.9    .035       0
    4756     .05       0  4979.1     .05       0  4994.4     .05       0
  4998.2      .1       0  5492.3     .05       0  6157.1    .035       0
  6256.2     .05       0  6635.4    .035       0
Bank Sta=4979.1,4994.4
XS Rating Curve= 0 ,0
Exp/Cntr=0.3,0.1

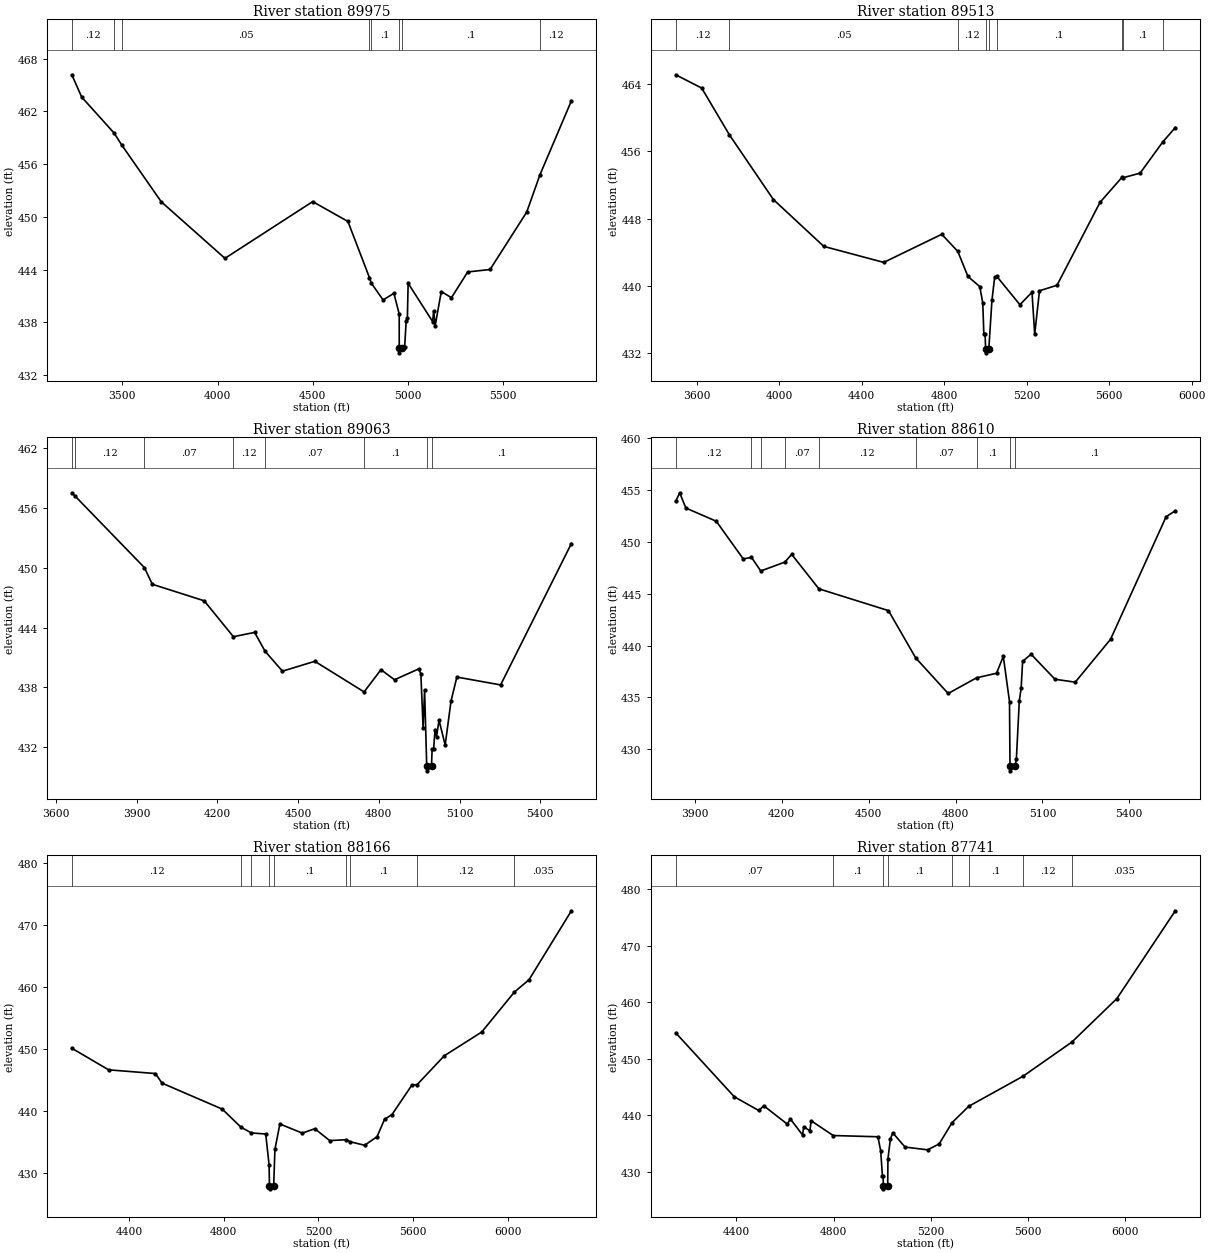
Type RM Length L Ch R = 1 ,89975   ,462,462,462
BEGIN DESCRIPTION:
Cooperas Creek 109.0
END DESCRIPTION:
XS GIS Cut Line= 3
      2488456.49     13846985.76        2487325.       13845625.
      2487025.01     13844825.03
#Sta/Elev= 30
  3234.6  466.18  3286.4  463.64  3456.9  459.54  3496.2   458.2  3704.3  451.72
  4038.9  445.28  4499.8  451.74  4684.7  449.48    4798  443.08  4806.6  442.49
  4869.6  440.54  4926.3   441.3  4954.2  438.94  4954.3  435.02  4954.8  434.52
  4969.8  435.02  4982.8  435.19  4990.7  438.13  4997.2  438.53  5001.1  442.44
  5129.8  438.08  5135.2   439.3  5143.2  437.62  5175.2   441.5  5228.6   440.8
    5314  443.73  5431.5  444.01  5623.8  450.54  5693.8  454.81  5858.7  463.22
#Mann= 8 ,-1 , 0
  3234.6     .12       0  3456.9     .07       0  3496.2     .05       0
    4798     .12       0  4806.6      .1       0  4954.3     .05       0
  4969.8      .1       0  5693.8     .12       0
Bank Sta=4954.3,4969.8
XS Rating Curve= 0 ,0
Exp/Cntr=0.3,0.1

Type RM Length L Ch R = 1 ,89513   ,450,450,450
BEGIN DESCRIPTION:
Cooperas Creek 108.0
END DESCRIPTION:
XS GIS Cut Line= 3
      2488468.62     13846901.01        2487775.       13845575.
      2487251.57     13844812.06
#Sta/Elev= 30
  3499.1  465.11    3625  463.53    3759  457.98  3972.5  450.28  4216.9  444.71
  4507.4  442.81  4788.7  446.15  4866.4  444.12  4915.5  441.14    4973  439.93
  4987.4     438  4992.7  434.26  4998.6  434.26  5001.3  432.56  5001.8  432.06
  5016.8  432.56  5031.9  438.29  5044.9  441.02  5054.3  441.18  5167.5  437.78
    5226  439.27  5239.2  434.28  5262.4  439.44  5347.3  440.09  5555.9  449.95
  5661.9  452.91  5668.8  452.88  5750.2  453.42  5859.9  457.12  5920.8  458.84
#Mann= 9 ,-1 , 0
  3499.1     .12       0    3759     .05       0  4866.4     .12       0
  5001.3     .05       0  5016.8     .12       0  5054.3      .1       0
  5661.9     .12       0  5668.8      .1       0  5859.9     .12       0
Bank Sta=5001.3,5016.8
XS Rating Curve= 0 ,0
Exp/Cntr=0.3,0.1

Type RM Length L Ch R = 1 ,89063   ,453,453,453
BEGIN DESCRIPTION:
Cooperas Creek 107.0
END DESCRIPTION:
XS GIS Cut Line= 3
      2489125.04     13845825.02        2487925.       13845225.
      2487474.97     13844974.99
#Sta/Elev= 30
  3659.3  457.53  3671.3   457.2  3929.1  450.02  3958.4  448.35  4151.3  446.69
  4259.6  443.09  4338.6  443.52  4377.2  441.64    4442  439.63  4562.2  440.62
  4745.4  437.55  4808.1  439.78  4858.4  438.77  4947.9  439.85  4956.3  439.39
  4964.7  433.95  4970.2  437.75  4978.1  430.13  4978.6  429.63  4995.9  430.13
  4998.2   431.8  5003.8   431.8    5009  433.77  5014.7  433.07  5023.9   434.7
  5046.7  432.22  5068.5  436.65  5090.2  439.04  5252.7  438.25  5515.8  452.44
#Mann= 8 ,-1 , 0
  3659.3     .07       0  3671.3     .12       0  3929.1     .07       0
  4259.6     .12       0  4377.2     .07       0  4745.4      .1       0
  4978.1     .05       0  4995.9      .1       0
Bank Sta=4978.1,4995.9
XS Rating Curve= 0 ,0
Exp/Cntr=0.3,0.1

Type RM Length L Ch R = 1 ,88610   ,444,444,444
BEGIN DESCRIPTION:
Cooperas Creek 106.0
END DESCRIPTION:
XS GIS Cut Line= 3
      2489074.98     13845474.99        2488075.       13844875.
      2487524.98       13844775.
#Sta/Elev= 30
  3833.8  453.89  3847.4  454.71  3868.8  453.24  3973.7  451.97    4067  448.34
  4095.4  448.49  4127.4  447.18  4210.5  448.03  4234.2  448.78  4328.1  445.46
  4568.5  443.36  4662.4  438.81  4774.5  435.38  4872.8  436.89  4941.7  437.33
    4965  438.96  4986.4   434.6  4988.1  428.43  4988.6  427.93  5005.9  428.43
  5010.1  429.03  5020.3   434.7  5026.6  435.88  5031.7  438.47  5060.9  439.16
  5143.5  436.75  5213.4  436.47  5335.4   440.6  5527.2   452.4    5559  452.98
#Mann= 9 ,-1 , 0
  3833.8     .12       0  4095.4     .07       0  4127.4     .12       0
  4210.5     .07       0  4328.1     .12       0  4662.4     .07       0
  4872.8      .1       0  4988.1     .05       0  5005.9      .1       0
Bank Sta=4988.1,5005.9
XS Rating Curve= 0 ,0
Exp/Cntr=0.3,0.1

Type RM Length L Ch R = 1 ,88166   ,425,425,425
BEGIN DESCRIPTION:
Cooperas Creek 105.0
END DESCRIPTION:
XS GIS Cut Line= 3
      2489024.99     13845224.99        2488425.       13844625.
      2487225.02     13844225.01
#Sta/Elev= 30
  4156.9  450.19  4312.4  446.71  4510.4  446.11  4538.7  444.56  4793.3  440.37
  4872.8  437.44  4916.9  436.53  4977.1  436.35  4991.3  431.43    4993  428.01
  4993.5  427.51  5010.8  428.01    5016  433.86    5037  437.97  5131.9   436.5
  5184.6  437.21  5247.9  435.29  5318.6  435.44  5334.1  435.11  5395.4  434.54
  5448.1  435.92  5479.8  438.73  5511.4   439.5  5595.7  444.26  5617.5  444.32
  5732.7  448.98  5890.9  452.81  6029.2  459.26  6091.1  461.25  6270.3  472.37
#Mann= 9 ,-1 , 0
  4156.9     .12       0  4872.8     .07       0  4916.9      .1       0
    4993     .05       0  5010.8      .1       0  5318.6     .12       0
  5334.1      .1       0  5617.5     .12       0  6029.2    .035       0
Bank Sta=4993,5010.8
XS Rating Curve= 0 ,0
Exp/Cntr=0.3,0.1

Type RM Length L Ch R = 1 ,87741   ,473,473,473
BEGIN DESCRIPTION:
Cooperas Creek 104.0
END DESCRIPTION:
XS GIS Cut Line= 3
      2489174.97     13844574.99        2488375.       13844275.
      2487175.03       13844175.
#Sta/Elev= 30
  4149.7   454.6  4390.9   443.3  4491.4  440.87  4512.8  441.69  4608.9  438.47
  4622.3  439.35  4672.1  436.55  4677.4  437.99  4702.4  437.27  4707.7  439.05
  4798.4  436.44  4982.7  436.22  4994.3  433.71  5001.4  429.27  5004.1  429.27
  5005.2  427.51  5005.7  427.01  5023.1  427.51  5024.1   432.3  5034.2  435.87
  5044.2  436.91  5094.4   434.4  5187.2  433.91  5234.9  434.94  5288.5  438.73
  5357.1  441.61  5580.9  446.93  5781.7  452.96  5967.4  460.66  6208.2  476.19
#Mann= 8 ,-1 , 0
  4149.7     .07       0  4798.4      .1       0  5005.2     .05       0
  5023.1      .1       0  5288.5     .12       0  5357.1      .1       0
  5580.9     .12       0  5781.7    .035       0
Bank Sta=5005.2,5023.1
XS Rating Curve= 0 ,0
Exp/Cntr=0.3,0.1