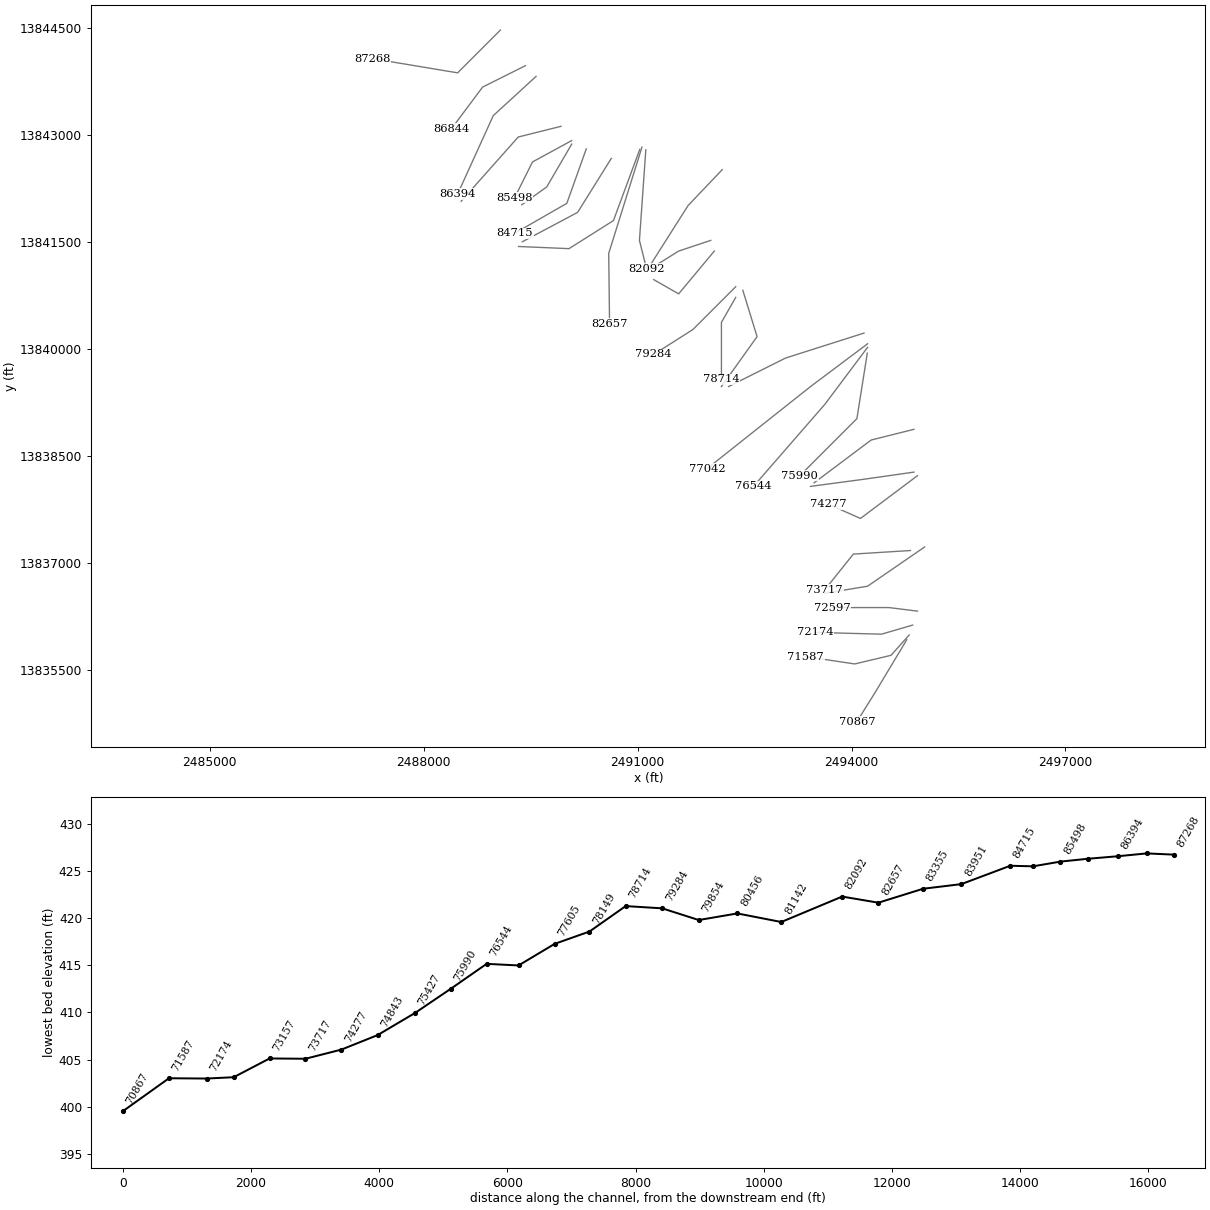
HEC-RAS study Copperas Creek.prj: Copperas Creek Base Level Engineering

--- Copperas Creek.g01 (geometry) --- (continued)

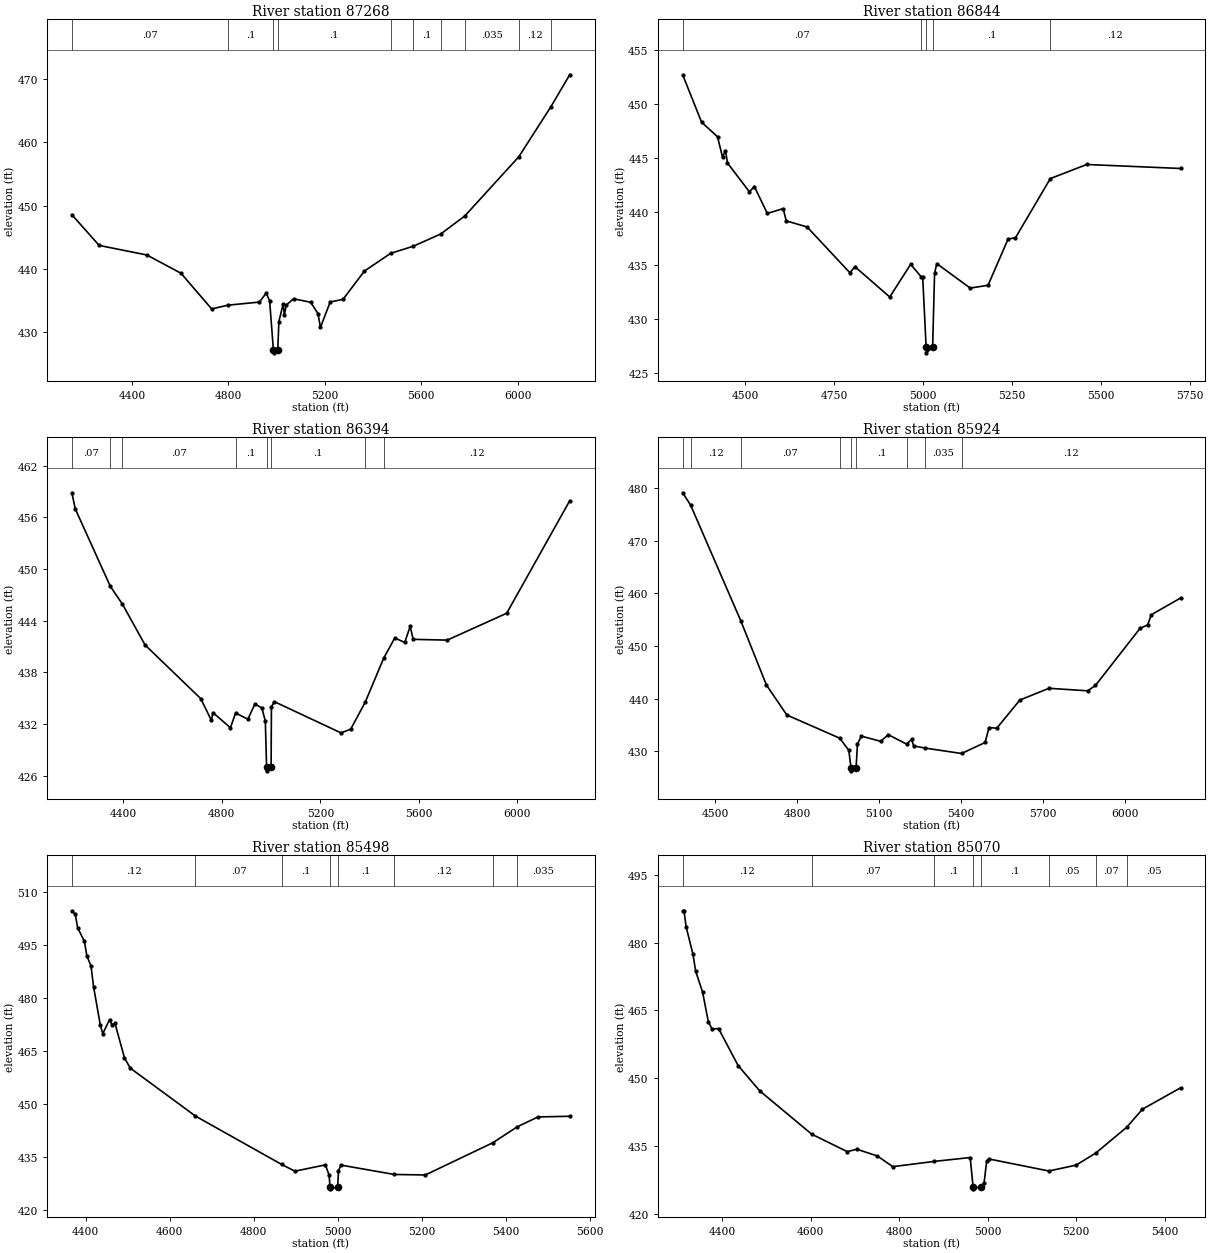
Type RM Length L Ch R = 1 ,87268   ,424,424,424
BEGIN DESCRIPTION:
Cooperas Creek 103.0
END DESCRIPTION:
XS GIS Cut Line= 3
      2489075.02     13844475.02        2488475.       13843875.
      2487275.01       13844075.
#Sta/Elev= 30
    4151  448.55  4264.2   443.7  4462.2  442.19  4603.6  439.31  4730.9  433.68
  4798.1  434.27  4928.9  434.76  4957.1  436.18  4971.3  434.95  4986.9  427.25
  4987.4  426.75  5005.1  427.25  5009.7  431.67  5027.4  434.47  5032.5  432.69
  5040.1  434.28  5070.5  435.28  5141.5  434.73  5171.9  432.95    5182  430.75
  5222.6  434.78  5275.8  435.19  5364.5  439.65  5473.1  442.45  5566.4  443.56
  5680.4  445.49  5780.7  448.34  6004.9  457.69  6137.9  465.58  6216.1  470.63
#Mann= 10 ,-1 , 0
    4151     .07       0  4798.1      .1       0  4986.9     .05       0
  5005.1      .1       0  5473.1     .12       0  5566.4      .1       0
  5680.4     .12       0  5780.7    .035       0  6004.9     .12       0
  6137.9    .035       0
Bank Sta=4986.9,5005.1
XS Rating Curve= 0 ,0
Exp/Cntr=0.3,0.1

Type RM Length L Ch R = 1 ,86844   ,450,450,450
BEGIN DESCRIPTION:
Cooperas Creek 102.0
END DESCRIPTION:
XS GIS Cut Line= 3
      2489425.01       13843975.        2488825.       13843675.
      2488389.92     13843092.47
#Sta/Elev= 30
  4324.8  452.73  4377.9  448.32  4422.6  446.97  4436.6  445.08    4445  445.69
  4450.6  444.53  4512.1  441.85  4526.1  442.34  4562.4  439.84  4607.1  440.29
  4615.5  439.15  4674.2  438.58  4794.4  434.32  4808.4  434.89  4906.2  432.07
  4964.9  435.11  4994.3  433.96  4998.7  433.96  5008.4  427.38  5008.9  426.88
  5026.6  427.38  5032.1  434.28  5038.4  435.17  5132.2   432.9  5182.2  433.16
  5238.5  437.46  5259.3  437.58  5357.1  443.08  5459.4  444.39  5722.7  444.02
#Mann= 5 ,-1 , 0
  4324.8     .07       0  4994.3      .1       0  5008.4     .05       0
  5026.6      .1       0  5357.1     .12       0
Bank Sta=5008.4,5026.6
XS Rating Curve= 0 ,0
Exp/Cntr=0.3,0.1

Type RM Length L Ch R = 1 ,86394   ,470,470,470
BEGIN DESCRIPTION:
Cooperas Creek 101.0
END DESCRIPTION:
XS GIS Cut Line= 3
      2489575.02     13843825.01        2488975.       13843275.
      2488474.99     13842174.97
#Sta/Elev= 30
  4190.7  458.87  4204.6  456.99  4346.7  448.02  4396.2  445.93  4488.2  441.19
  4714.5  434.96  4757.1  432.45  4763.9  433.34  4834.8  431.58  4855.8   433.3
  4905.7  432.57  4934.1  434.34  4962.4  433.88  4976.6  432.36  4981.6  427.08
  4982.1  426.58    5000  427.08  5001.3  434.02  5013.4  434.61  5283.7  430.99
  5323.2  431.41  5382.6  434.57    5457  439.64  5502.3  442.01  5542.9  441.49
  5564.9  443.36    5577  441.85  5715.4  441.76    5957  444.88    6213  457.94
#Mann= 8 ,-1 , 0
  4190.7     .07       0  4346.7     .12       0  4396.2     .07       0
  4855.8      .1       0  4981.6     .05       0    5000      .1       0
  5382.6    .035       0    5457     .12       0
Bank Sta=4981.6,5000
XS Rating Curve= 0 ,0
Exp/Cntr=0.3,0.1

Type RM Length L Ch R = 1 ,85924   ,426,426,426
BEGIN DESCRIPTION:
Cooperas Creek 100.0
END DESCRIPTION:
XS GIS Cut Line= 3
      2489925.04     13843125.01        2489325.       13842975.
      2488524.98     13842074.97
#Sta/Elev= 30
  4381.8  479.06  4410.7  476.73  4594.4  454.79  4688.5  442.58  4763.2   436.9
  4956.5  432.51    4990  430.21  4998.2  426.81  4998.7  426.31  5016.6  426.81
  5021.6  431.36  5035.8   432.9  5106.9  431.91  5134.5  433.17  5201.6  431.38
  5219.8  432.27  5227.3  431.05  5267.9  430.64  5402.9   429.6  5489.1  431.69
  5503.3  434.53  5531.7  434.39  5616.2  439.74  5722.8  441.97  5864.5  441.49
    5893  442.51    6056  453.32    6084  453.99  6097.8  455.93  6204.5  459.09
#Mann= 9 ,-1 , 0
  4381.8     .07       0  4410.7     .12       0  4594.4     .07       0
  4956.5      .1       0  4998.2     .05       0  5016.6      .1       0
  5201.6     .07       0  5267.9    .035       0  5402.9     .12       0
Bank Sta=4998.2,5016.6
XS Rating Curve= 0 ,0
Exp/Cntr=0.3,0.1

Type RM Length L Ch R = 1 ,85498   ,428,428,428
BEGIN DESCRIPTION:
Cooperas Creek 99.0
END DESCRIPTION:
XS GIS Cut Line= 3
      2490075.01     13842925.01        2489525.       13842625.
      2489275.01     13842125.02
#Sta/Elev= 30
    4367  504.76  4375.1  503.78  4380.8  499.92  4396.9  496.09  4402.6  492.02
  4412.6  489.09  4418.7  483.22  4434.9  472.29  4440.6  469.97  4456.7  473.92
  4462.4  472.42  4469.5  472.93  4492.3  463.08  4506.1  460.19  4661.3  446.62
  4866.2  432.94  4898.1  431.01  4970.7   432.8  4979.7  429.87  4981.5  426.51
    4982  426.01  4999.9  426.51  5001.9  431.06  5007.5  432.74  5134.7  430.08
  5208.7  429.94  5369.2  439.05  5427.6  443.58  5477.1  446.38  5552.5  446.56
#Mann= 8 ,-1 , 0
    4367     .12       0  4661.3     .07       0  4866.2      .1       0
  4981.5     .05       0  4999.9      .1       0  5134.7     .12       0
  5369.2     .07       0  5427.6    .035       0
Bank Sta=4981.5,4999.9
XS Rating Curve= 0 ,0
Exp/Cntr=0.3,0.1

Type RM Length L Ch R = 1 ,85070   ,355,355,355
BEGIN DESCRIPTION:
Cooperas Creek 98.0
END DESCRIPTION:
XS GIS Cut Line= 3
      2490074.99     13842874.98        2489725.       13842275.
      2489375.02     13842025.01
#Sta/Elev= 30
  4311.1  487.08    4314  487.08  4318.9  483.52  4334.2  477.51  4340.4  473.72
  4356.1  469.05    4369  462.53  4377.6  460.86  4392.1  461.01  4436.4  452.79
  4485.2   447.2  4602.5  437.62  4682.8  433.75  4704.7  434.28    4751  432.78
  4785.7  430.42  4879.7  431.59  4960.6  432.44  4967.1  426.01  4967.6  425.51
  4985.5  426.01  4992.1  426.87  4997.8  431.62  5002.8  432.13  5138.3  429.46
  5199.9  430.76  5244.4  433.44  5314.5  439.17  5349.8  443.15  5435.8  447.87
#Mann= 8 ,-1 , 0
  4311.1     .12       0  4602.5     .07       0  4879.7      .1       0
  4967.1     .05       0  4985.5      .1       0  5138.3     .05       0
  5244.4     .07       0  5314.5     .05       0
Bank Sta=4967.1,4985.5
XS Rating Curve= 0 ,0
Exp/Cntr=0.3,0.1

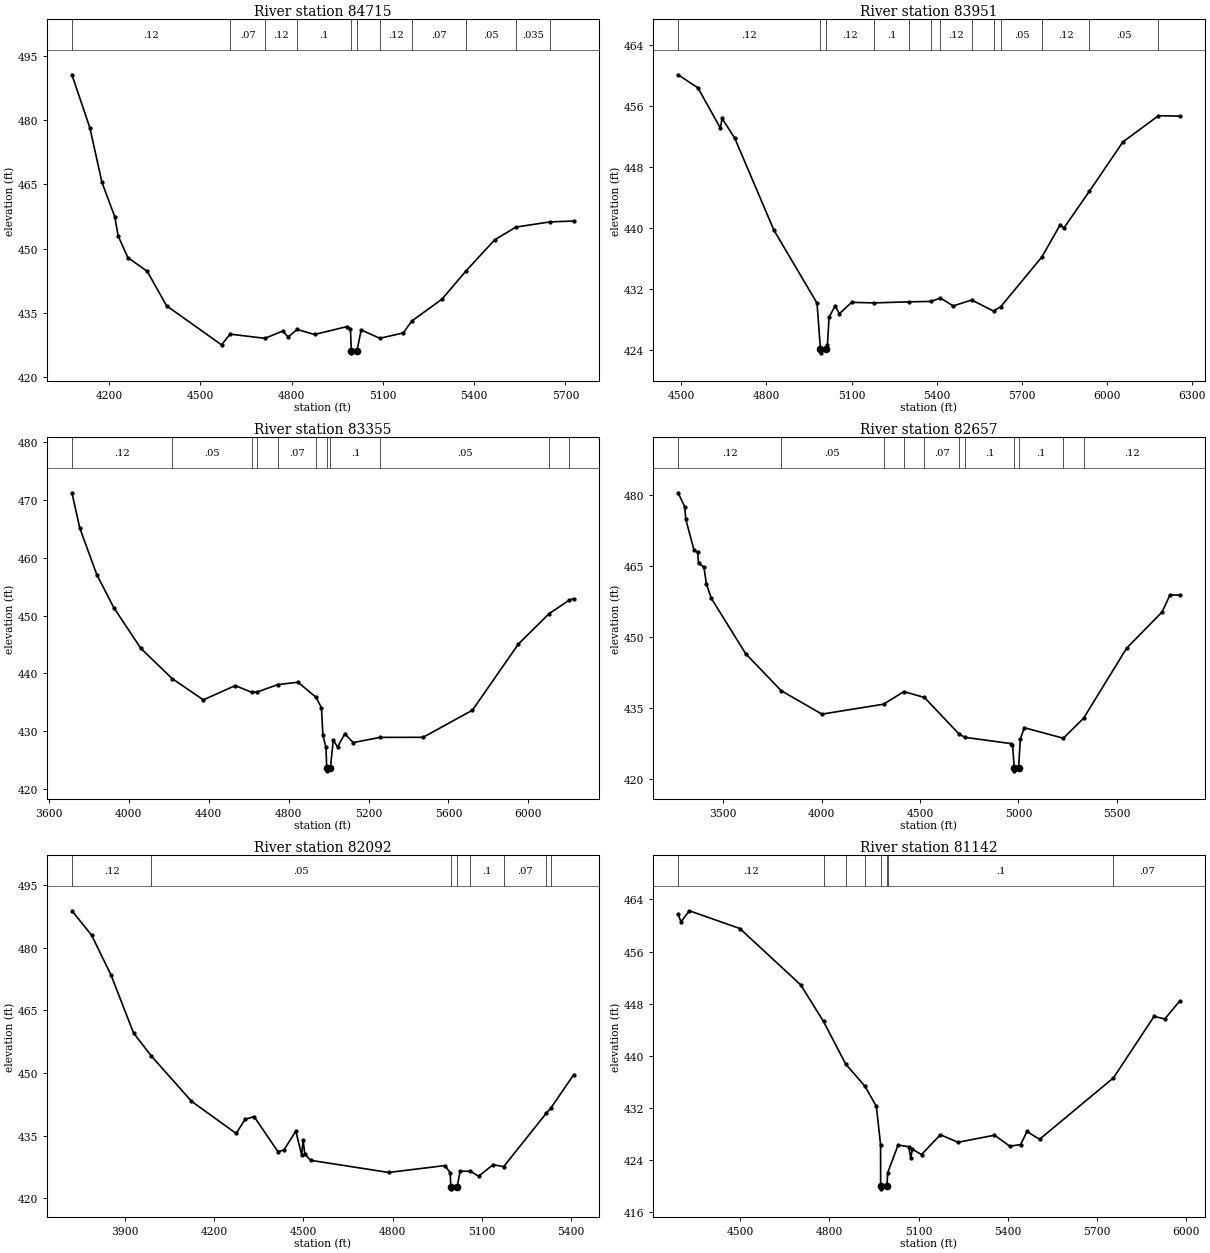
Type RM Length L Ch R = 1 ,84715   ,764,764,764
BEGIN DESCRIPTION:
X18530
END DESCRIPTION:
XS GIS Cut Line= 3
      2490279.07      13842807.9      2490006.59     13842044.94
        2489280.     13841627.15
#Sta/Elev= 30
  4078.4  490.68  4137.5  478.22    4177   465.5  4219.3  457.42  4230.1  452.97
    4262  447.88  4325.7  444.67  4389.4  436.59  4569.9  427.44  4597.9  429.95
  4712.6  428.97  4771.7  430.69  4788.4  429.25  4818.1  431.04  4875.5  429.87
  4983.6  431.73  4993.6  431.13  4996.5  426.07    4997  425.57    5015  426.07
  5028.8  430.92  5090.2  428.98  5167.2  430.23  5194.8     433    5294  438.12
  5372.8   444.7  5467.2  452.02  5537.5  455.02  5649.3  456.23  5726.7  456.43
#Mann= 11 ,-1 , 0
  4078.4     .12       0  4597.9     .07       0  4712.6     .12       0
  4818.1      .1       0  4996.5     .05       0    5015      .1       0
  5090.2     .12       0  5194.8     .07       0  5372.8     .05       0
  5537.5    .035       0  5649.3     .05       0
Bank Sta=4996.5,5015
XS Rating Curve= 0 ,0
Exp/Cntr=0.3,0.1

Type RM Length L Ch R = 1 ,83951   ,596,596,596
BEGIN DESCRIPTION:
Cooperas Creek 97.0
END DESCRIPTION:
XS GIS Cut Line= 3
      2490630.26     13842674.67      2490157.96     13841917.78
      2489382.91     13841506.03
#Sta/Elev= 30
  4488.2  460.08  4558.4  458.36  4637.5  453.08  4643.4  454.36  4688.2  451.76
  4826.2  439.71  4978.4  430.13  4990.4  424.12  4990.9  423.62  5008.9  424.12
    5015  424.66  5020.9   428.3  5042.1  429.76  5057.4  428.76  5100.7  430.24
  5180.1  430.17  5302.2  430.31    5380  430.36  5413.7   430.8  5459.1  429.77
  5523.6  430.55  5601.2   429.1    5627  429.69  5771.8   436.2  5836.7  440.44
  5849.1  439.98  5938.8  444.78  6057.6  451.28    6183  454.71    6258  454.66
#Mann= 13 ,-1 , 0
  4488.2     .12       0  4990.4     .05       0  5008.9     .12       0
  5180.1      .1       0  5302.2     .12       0    5380     .07       0
  5413.7     .12       0  5523.6      .1       0  5601.2     .07       0
    5627     .05       0  5771.8     .12       0  5938.8     .05       0
    6183    .035       0
Bank Sta=4990.4,5008.9
XS Rating Curve= 0 ,0
Exp/Cntr=0.3,0.1

Type RM Length L Ch R = 1 ,83355   ,698,698,698
BEGIN DESCRIPTION:
X18529
END DESCRIPTION:
XS GIS Cut Line= 4
      2491029.87     13842801.79      2490660.52     13841802.74
      2490036.86     13841409.16      2489329.22     13841439.41
#Sta/Elev= 30
  3715.5  471.24  3754.7  465.15    3840  457.07  3925.3  451.35  4059.9  444.34
    4217   439.1  4373.1  435.41    4533  437.88  4614.8  436.72    4641  436.75
    4747  438.06  4847.1  438.46  4937.6  435.85  4964.5  434.03  4971.8  429.25
  4987.1  427.18  4990.8  423.63  4991.3  423.13  5009.3  423.63  5023.6  428.46
  5044.8  427.25  5081.2  429.53  5123.6  428.02  5258.6  428.92    5473  428.93
  5720.2  433.62  5950.4  445.08  6103.3   450.3  6202.1  452.61  6226.4  452.92
#Mann= 11 ,-1 , 0
  3715.5     .12       0    4217     .05       0  4614.8     .07       0
    4641      .1       0    4747     .07       0  4937.6      .1       0
  4990.8     .05       0  5009.3      .1       0  5258.6     .05       0
  6103.3    .035       0  6202.1     .05       0
Bank Sta=4990.8,5009.3
XS Rating Curve= 0 ,0
Exp/Cntr=0.3,0.1

Type RM Length L Ch R = 1 ,82657   ,565,565,565
BEGIN DESCRIPTION:
Cooperas Creek 96.0
END DESCRIPTION:
XS GIS Cut Line= 3
      2491060.16      13842832.1      2490593.92     13841342.56
      2490606.03     13840355.63
#Sta/Elev= 30
  3271.1  480.49  3304.9  477.51  3310.2  474.87  3351.9  468.38  3369.8  467.87
  3375.1  465.56  3402.3  464.76  3414.8  461.19    3440  458.14  3613.8  446.47
  3794.3  438.62  4001.5  433.65  4314.4  435.75  4418.4  438.42  4522.4  437.17
  4699.7  429.37  4730.5  428.72  4959.5  427.43  4969.5  427.11  4978.8  422.15
  4979.3  421.65  5000.1  422.15  5009.5  428.44  5029.5  430.78  5227.8  428.55
  5330.4  432.77  5549.5  447.62  5729.5  455.27  5769.5  458.88  5818.9  458.83
#Mann= 11 ,-1 , 0
  3271.1     .12       0  3794.3     .05       0  4314.4     .07       0
  4418.4     .12       0  4522.4     .07       0  4699.7     .12       0
  4730.5      .1       0  4978.8     .05       0  5000.1      .1       0
  5227.8     .07       0  5330.4     .12       0
Bank Sta=4978.8,5000.1
XS Rating Curve= 0 ,0
Exp/Cntr=0.3,0.1

Type RM Length L Ch R = 1 ,82092   ,950,950,950
BEGIN DESCRIPTION:
Cooperas Creek 95.0
END DESCRIPTION:
XS GIS Cut Line= 3
      2491114.65     13842795.78        2491025.       13841525.
      2491124.99     13841125.05
#Sta/Elev= 30
  3721.9  488.83  3787.9     483    3853   473.5  3929.1  459.58  3988.3  454.13
  4123.7  443.26    4274  435.55  4304.1  438.94  4334.2  439.58  4414.4   431.2
  4434.4  431.58  4474.5  436.11    4494  430.43    4499  434.07  4504.6  430.58
  4524.7  429.12  4786.5  426.22  4975.8  427.87  4993.3  426.17  4995.5   422.8
    4996   422.3  5016.8   422.8  5026.8  426.52  5061.5  426.51  5088.6  425.31
  5137.6  428.07  5173.1  427.61  5316.1  440.37    5332  441.65  5408.1  449.57
#Mann= 8 ,-1 , 0
  3721.9     .12       0  3988.3     .05       0  4995.5     .05       0
  5016.8     .05       0  5061.5      .1       0  5173.1     .07       0
  5316.1      .1       0    5332     .07       0
Bank Sta=4995.5,5016.8
XS Rating Curve= 0 ,0
Exp/Cntr=0.3,0.1

Type RM Length L Ch R = 1 ,81142   ,686,686,686
BEGIN DESCRIPTION:
Cooperas Creek 94.0
END DESCRIPTION:
XS GIS Cut Line= 3
      2492186.39     13842517.23      2491708.03     13842014.66
        2491175.     13841174.99
#Sta/Elev= 30
  4290.7  461.75  4300.3  460.57  4328.6  462.26  4498.5  459.54  4703.6  450.88
  4780.1  445.28  4854.8  438.74  4919.7  435.34    4958  432.26  4972.2  426.39
  4972.4   420.1  4972.9   419.6  4993.9   420.1    4996  422.06  5031.2  426.32
    5067  426.06  5073.6  424.34  5079.5  425.67    5110  424.86  5173.6   427.9
  5232.9  426.74  5355.6  427.83  5407.3  426.14  5443.7  426.39  5464.9   428.4
  5507.3   427.2  5756.1  436.63  5892.7  446.05  5929.1  445.67  5979.1  448.42
#Mann= 8 ,-1 , 0
  4290.7     .12       0  4780.1     .07       0  4854.8     .05       0
  4919.7     .07       0  4972.4     .05       0  4993.9     .07       0
    4996      .1       0  5756.1     .07       0
Bank Sta=4972.4,4993.9
XS Rating Curve= 0 ,0
Exp/Cntr=0.3,0.1

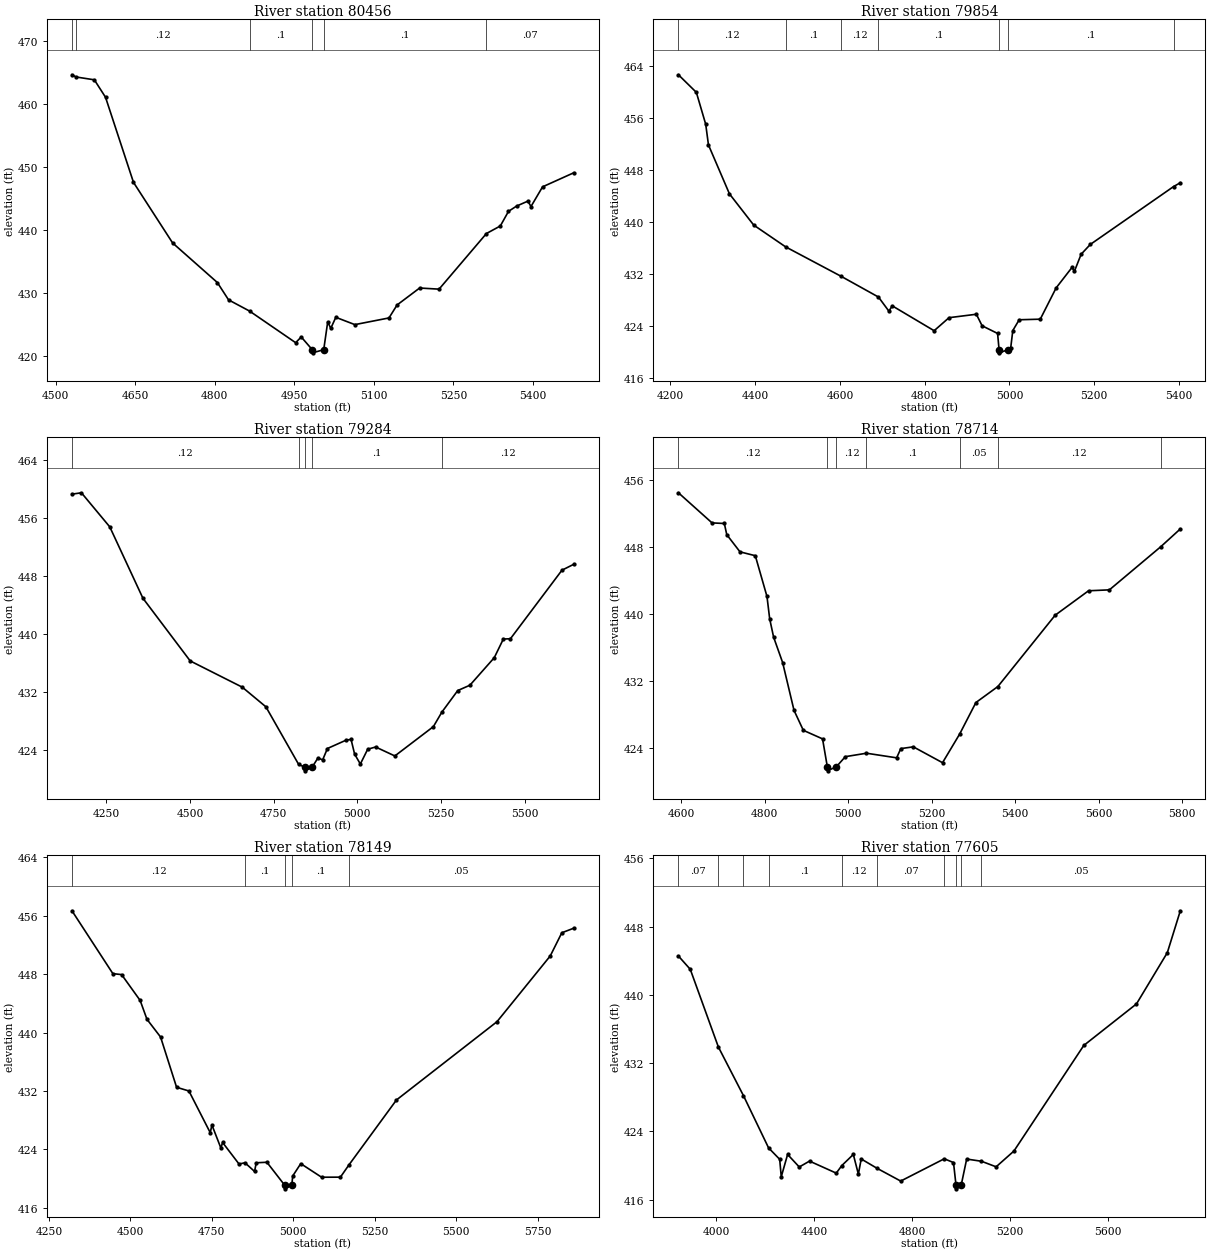
Type RM Length L Ch R = 1 ,80456   ,602,602,602
BEGIN DESCRIPTION:
Cooperas Creek 93.0
END DESCRIPTION:
XS GIS Cut Line= 3
      2492025.04     13841525.01        2491575.       13841375.
      2491174.99     13841124.99
#Sta/Elev= 30
    4531  464.65  4538.8   464.3  4573.2  463.85  4594.3  461.08    4647  447.57
  4720.8  437.95  4805.1  431.67  4826.2  428.92  4865.8  427.14  4952.7  422.12
  4963.2  423.03    4984  421.01  4984.5  420.51  5005.6  421.01  5013.1  425.42
  5018.9   424.4  5028.4  426.15  5064.3  424.99  5128.6  426.05  5143.9  428.11
  5186.4   430.8    5223  430.62  5312.3  439.45  5338.5  440.65  5353.9  442.97
  5369.2  443.81  5390.4  444.59  5396.3  443.74  5418.1  446.86  5477.1   449.1
#Mann= 6 ,-1 , 0
    4531     .07       0  4538.8     .12       0  4865.8      .1       0
    4984     .05       0  5005.6      .1       0  5312.3     .07       0
Bank Sta=4984,5005.6
XS Rating Curve= 0 ,0
Exp/Cntr=0.3,0.1

Type RM Length L Ch R = 1 ,79854   ,570,570,570
BEGIN DESCRIPTION:
Cooperas Creek 92.0
END DESCRIPTION:
XS GIS Cut Line= 3
      2492074.97     13841374.97        2491575.       13840775.
        2491225.       13840975.
#Sta/Elev= 30
    4219  462.68  4261.3  459.97  4283.4  455.05  4289.9  451.86  4339.4  444.32
  4396.6  439.51  4471.9  436.15  4603.1   431.6    4691  428.41  4715.6  426.23
  4723.4  427.06  4822.3  423.22  4857.4  425.23  4921.9  425.76  4935.5  423.98
    4972   422.8  4975.5  420.31    4976  419.81  4997.1  420.31  5002.9  420.55
  5007.9  423.25    5023  424.91  5072.7     425  5110.1  429.82  5147.6  432.98
  5153.3  432.39  5169.1  435.01  5190.7  436.52  5387.3  445.45  5403.1  446.03
#Mann= 7 ,-1 , 0
    4219     .12       0  4471.9      .1       0  4603.1     .12       0
    4691      .1       0  4975.5     .05       0  4997.1      .1       0
  5387.3     .07       0
Bank Sta=4975.5,4997.1
XS Rating Curve= 0 ,0
Exp/Cntr=0.3,0.1

Type RM Length L Ch R = 1 ,79284   ,570,570,570
BEGIN DESCRIPTION:
Cooperas Creek 91.0
END DESCRIPTION:
XS GIS Cut Line= 3
      2492374.99     13840874.99        2491775.       13840275.
      2491225.02     13839925.02
#Sta/Elev= 30
    4147  459.34  4175.3  459.53  4260.1  454.81  4359.1  444.94  4500.5  436.26
  4656.1  432.63  4726.8  429.91  4824.7  421.94  4843.3  421.55  4843.8  421.05
  4864.9  421.55  4882.4  422.83  4896.5  422.57  4910.7  424.14  4967.2  425.31
  4981.4  425.39    4992  423.37  5009.1  421.99  5031.1  424.04  5054.8  424.35
  5112.3  423.11  5227.5  427.17  5252.9  429.18  5300.3  432.16  5336.7   432.9
  5409.5  436.71  5436.6  439.29  5457.8  439.33  5611.9  448.82  5647.4  449.64
#Mann= 5 ,-1 , 0
    4147     .12       0  4824.7      .1       0  4843.3     .05       0
  4864.9      .1       0  5252.9     .12       0
Bank Sta=4843.3,4864.9
XS Rating Curve= 0 ,0
Exp/Cntr=0.3,0.1

Type RM Length L Ch R = 1 ,78714   ,565,565,565
BEGIN DESCRIPTION:
Cooperas Creek 90.0
END DESCRIPTION:
XS GIS Cut Line= 3
        2492375.     13840724.99        2492175.       13840375.
        2492175.     13839575.01
#Sta/Elev= 30
  4592.9  454.43  4673.5  450.84    4703  450.77  4708.8  449.44  4740.5  447.39
  4777.2  446.93  4805.2  442.07  4811.7   439.4  4821.1  437.22  4842.7   434.2
    4870   428.5  4892.3  426.12  4938.4   425.1  4949.8  421.79  4950.3  421.29
  4971.7  421.79  4993.1  422.98  5043.7  423.39    5116  422.84    5126  423.94
    5156  424.15    5226  422.26  5266.9  425.66    5306  429.43  5358.7  431.34
    5496  439.84    5576  442.75    5626  442.86  5749.1     448    5796  450.12
#Mann= 7 ,-1 , 0
  4592.9     .12       0  4949.8     .05       0  4971.7     .12       0
  5043.7      .1       0  5266.9     .05       0  5358.7     .12       0
  5749.1     .05       0
Bank Sta=4949.8,4971.7
XS Rating Curve= 0 ,0
Exp/Cntr=0.3,0.1

Type RM Length L Ch R = 1 ,78149   ,544,544,544
BEGIN DESCRIPTION:
Cooperas Creek 89.0
END DESCRIPTION:
XS GIS Cut Line= 3
        2492475.     13840825.01        2492675.       13840175.
      2492175.01     13839475.01
#Sta/Elev= 30
    4321  456.67  4446.6  448.06  4473.4  447.93  4530.3  444.39  4551.2  441.81
    4593  439.38  4642.1   432.5    4680  431.99  4745.4  426.28  4750.6  427.33
  4778.1  424.17  4783.3  424.94  4833.7  421.99    4852  422.16  4881.4  420.97
  4886.6  422.16  4919.3  422.23  4973.8  419.09  4974.3  418.59  4995.7  419.09
  4998.5  420.35  5023.2  422.04  5087.1  420.18  5144.9  420.19  5170.8  421.85
  5316.9  430.76  5625.4  441.48  5788.8  450.48  5824.4  453.66  5861.3  454.29
#Mann= 5 ,-1 , 0
    4321     .12       0    4852      .1       0  4973.8     .05       0
  4995.7      .1       0  5170.8     .05       0
Bank Sta=4973.8,4995.7
XS Rating Curve= 0 ,0
Exp/Cntr=0.3,0.1

Type RM Length L Ch R = 1 ,77605   ,563,563,563
BEGIN DESCRIPTION:
Cooperas Creek 88.0
END DESCRIPTION:
XS GIS Cut Line= 3
      2494175.04     13840225.01        2493075.       13839875.
      2492275.01     13839475.01
#Sta/Elev= 30
  3846.7  444.56  3895.1     443  4009.8   433.9  4112.2   428.2  4214.7  422.08
  4260.1  420.74  4266.5  418.69  4292.4  421.31    4340  419.84  4381.9  420.53
    4491  419.12  4513.8  420.01  4560.7  421.31  4581.3     419  4592.9  420.78
  4657.3  419.69  4754.1  418.19  4931.9   420.8  4969.6  420.36  4979.6  417.78
  4980.1  417.28  5001.5  417.78  5023.4  420.77  5083.9  420.51  5143.6  419.86
  5216.3  421.71  5501.4  434.08  5716.6  438.95  5842.4  444.95  5895.5  449.86
#Mann= 10 ,-1 , 0
  3846.7     .07       0  4009.8    .035       0  4112.2     .07       0
  4214.7      .1       0  4513.8     .12       0  4657.3     .07       0
  4931.9      .1       0  4979.6     .05       0  5001.5      .1       0
  5083.9     .05       0
Bank Sta=4979.6,5001.5
XS Rating Curve= 0 ,0
Exp/Cntr=0.3,0.1

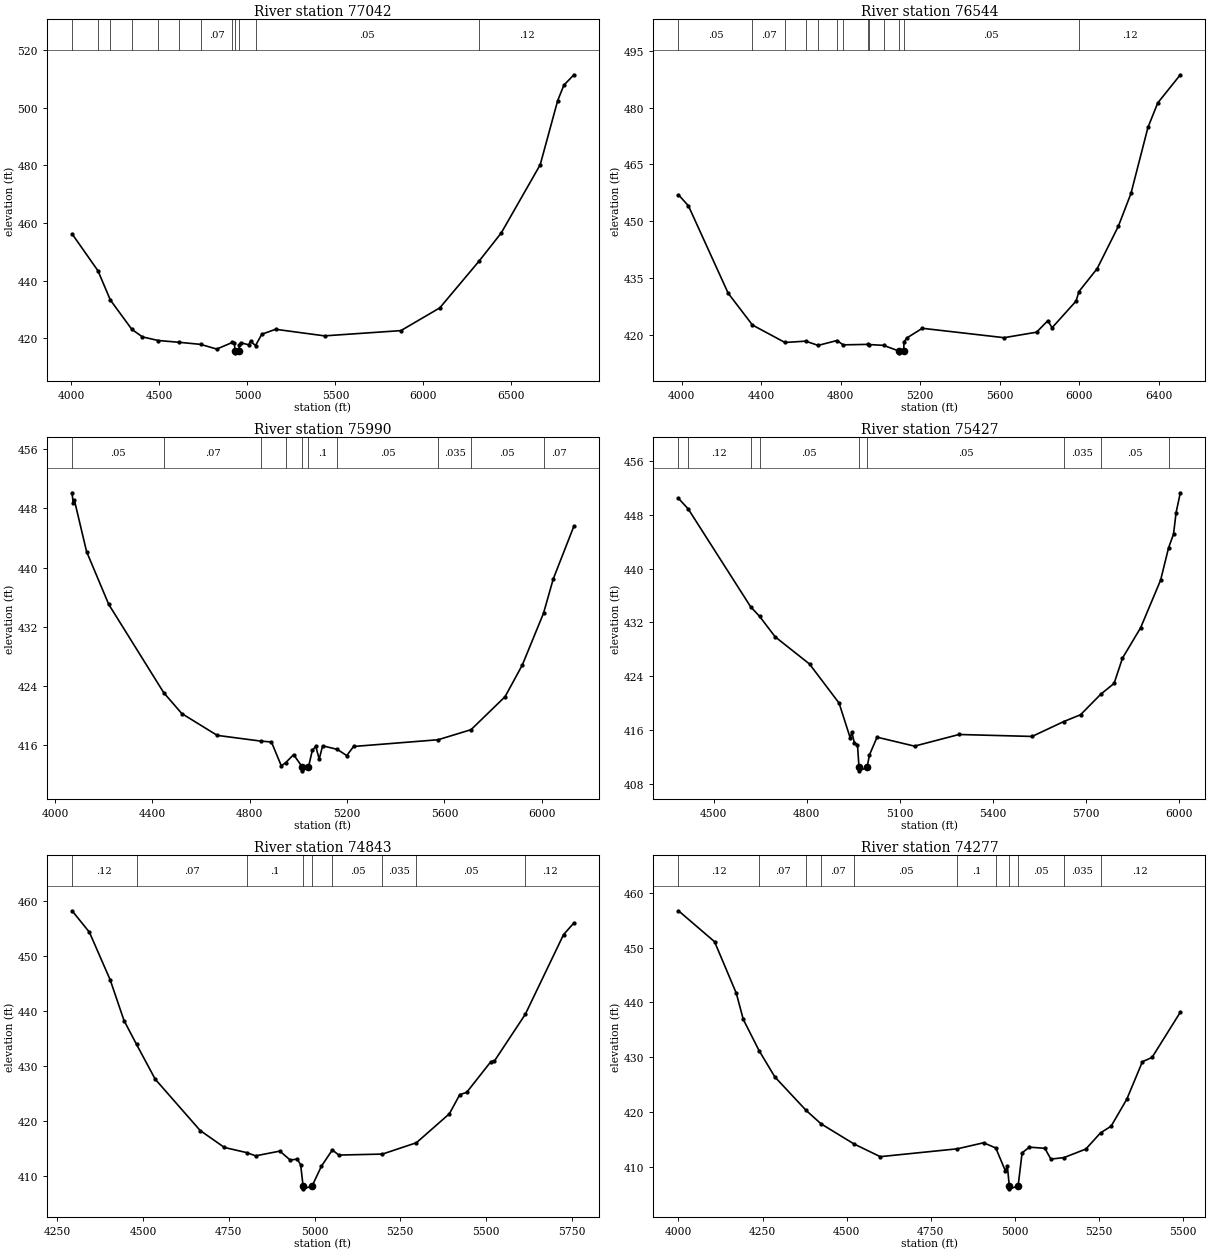
Type RM Length L Ch R = 1 ,77042   ,498,498,498
BEGIN DESCRIPTION:
Cooperas Creek 87.0
END DESCRIPTION:
XS GIS Cut Line= 3
        2494225.       13840075.        2493425.       13839475.
      2491974.98     13838324.99
#Sta/Elev= 30
  4004.2  456.26  4151.4  443.45  4221.5  433.33  4343.8  423.13  4404.2  420.52
  4493.2  419.27  4613.8  418.64  4734.4  417.93  4826.1   416.3  4914.5  418.59
  4926.1  418.56  4929.7  415.49  4930.2  414.99  4951.7  415.49  4954.2  417.82
  4961.5  418.53  5007.4  417.78  5017.8  419.01  5046.2  417.51  5081.9  421.44
  5160.4  423.16  5438.2  420.88  5872.1   422.7    6093  430.59  6316.3  446.83
  6442.3   456.6  6663.4  480.25  6762.8  502.53    6798  507.87  6854.9  511.46
#Mann= 12 ,-1 , 0
  4004.2     .05       0  4151.4    .035       0  4221.5     .05       0
  4343.8     .07       0  4493.2     .12       0  4613.8      .1       0
  4734.4     .07       0  4914.5      .1       0  4929.7     .05       0
  4951.7      .1       0  5046.2     .05       0  6316.3     .12       0
Bank Sta=4929.7,4951.7
XS Rating Curve= 0 ,0
Exp/Cntr=0.3,0.1

Type RM Length L Ch R = 1 ,76544   ,554,554,554
BEGIN DESCRIPTION:
Cooperas Creek 86.0
END DESCRIPTION:
XS GIS Cut Line= 3
      2494224.98     13840024.98        2493625.       13839225.
      2492625.03     13838075.04
#Sta/Elev= 30
    3984  456.96    4034  454.04    4234  430.92  4356.2  422.51  4519.4   417.9
  4623.4  418.25  4686.3  417.13  4781.6  418.42    4812  417.27  4937.6   417.4
  4939.8  417.36  5015.4  417.14  5091.6  415.66  5092.1  415.16  5116.6  415.66
  5118.3  418.04  5132.6   419.1  5210.4  421.65  5621.6  419.17  5784.9  420.62
  5841.9  423.68  5862.7  421.79  5983.3  428.83  5998.2  431.38  6089.7  437.44
    6196  448.61  6259.6  457.31  6345.1  474.78  6394.5  481.27  6507.9   488.7
#Mann= 13 ,-1 , 0
    3984     .05       0  4356.2     .07       0  4519.4    .035       0
  4623.4      .1       0  4686.3    .035       0  4781.6     .07       0
    4812      .1       0  4937.6     .12       0  4939.8      .1       0
  5015.4     .05       0  5091.6     .05       0  5116.6     .05       0
  5998.2     .12       0
Bank Sta=5091.6,5116.6
XS Rating Curve= 0 ,0
Exp/Cntr=0.3,0.1

Type RM Length L Ch R = 1 ,75990   ,563,563,563
BEGIN DESCRIPTION:
Cooperas Creek 85.0
END DESCRIPTION:
XS GIS Cut Line= 3
      2494220.85     13839943.86        2494075.       13839025.
      2493275.02     13838225.02
#Sta/Elev= 30
    4070   450.1  4074.7  448.66  4079.7  449.08  4129.6  442.15  4220.7  435.02
  4446.9  423.08  4520.7  420.28  4666.2  417.33  4847.2  416.55    4889  416.44
  4929.5  413.22  4947.2  413.63  4980.1  414.73  5016.1  413.04  5016.6  412.54
  5041.1  413.04  5056.9  415.29  5071.1  415.86  5085.2  414.13  5099.4  415.92
  5159.7  415.44  5198.3   414.6  5226.6  415.83  5573.6  416.74  5709.1   418.1
  5848.9  422.56  5919.6  426.83  6006.8  433.83  6046.9  438.47  6131.7   445.6
#Mann= 10 ,-1 , 0
    4070     .05       0  4446.9     .07       0  4847.2     .12       0
  4947.2      .1       0  5016.1     .05       0  5041.1      .1       0
  5159.7     .05       0  5573.6    .035       0  5709.1     .05       0
  6006.8     .07       0
Bank Sta=5016.1,5041.1
XS Rating Curve= 0 ,0
Exp/Cntr=0.3,0.1

Type RM Length L Ch R = 1 ,75427   ,584,584,584
BEGIN DESCRIPTION:
Cooperas Creek 84.0
END DESCRIPTION:
XS GIS Cut Line= 3
      2494875.02     13838875.01        2494275.       13838725.
      2493474.99     13838124.99
#Sta/Elev= 30
  4386.9  450.43    4418  448.88  4619.7  434.32  4648.5   432.9  4698.7  429.86
  4809.5  425.82  4904.9  420.01    4941  414.81  4946.1  415.75  4953.9   414.1
  4964.2  413.82  4969.2  410.45  4969.7  409.95  4995.2  410.45  5002.8  412.31
  5027.3  414.95  5148.1  413.62  5291.8  415.35  5527.3  415.06  5629.4  417.27
  5683.5  418.28  5748.8  421.33  5791.8  422.94  5818.9   426.7  5877.3   431.2
  5941.8  438.28  5967.6   443.1  5983.5  445.12  5991.8  448.33  6005.4  451.26
#Mann= 9 ,-1 , 0
  4386.9     .07       0    4418     .12       0  4619.7     .07       0
  4648.5     .05       0  4969.2     .05       0  4995.2     .05       0
  5629.4    .035       0  5748.8     .05       0  5967.6     .12       0
Bank Sta=4969.2,4995.2
XS Rating Curve= 0 ,0
Exp/Cntr=0.3,0.1

Type RM Length L Ch R = 1 ,74843   ,566,566,566
BEGIN DESCRIPTION:
Cooperas Creek 83.0
END DESCRIPTION:
XS GIS Cut Line= 3
      2494874.95     13838274.99        2494175.       13838175.
        2493425.       13838075.
#Sta/Elev= 30
  4292.9  458.15  4343.4  454.26    4404   445.6  4444.4   438.2  4480.9  433.86
  4535.3  427.54  4666.6   418.2  4737.3  415.12  4801.9  414.19  4828.2   413.6
  4898.9  414.46  4929.2  412.83  4949.5  413.01  4959.6  411.98  4966.7   408.1
  4967.2   407.6  4992.9   408.1  5020.1  411.71  5052.1  414.68  5070.6  413.74
  5198.2  413.92  5297.2  415.98  5393.4  421.25  5423.7  424.73  5443.9  425.14
  5514.5  430.73  5524.6  430.83  5614.8  439.33  5726.3  453.81  5756.6  455.95
#Mann= 9 ,-1 , 0
  4292.9     .12       0  4480.9     .07       0  4801.9      .1       0
  4966.7     .05       0  4992.9      .1       0  5052.1     .05       0
  5198.2    .035       0  5297.2     .05       0  5614.8     .12       0
Bank Sta=4966.7,4992.9
XS Rating Curve= 0 ,0
Exp/Cntr=0.3,0.1

Type RM Length L Ch R = 1 ,74277   ,560,560,560
BEGIN DESCRIPTION:
Cooperas Creek 82.0
END DESCRIPTION:
XS GIS Cut Line= 3
        2494925.       13838225.        2494125.       13837625.
      2493675.04     13837824.98
#Sta/Elev= 30
  4000.1   456.7  4107.4  451.07    4172  441.69  4192.8  436.92  4240.1   431.2
  4286.6  426.45  4379.9  420.33  4424.3  417.89  4522.5  414.22  4600.1  411.92
  4829.4  413.35  4907.4  414.45  4943.7   413.5    4972  409.36  4978.2  410.17
  4983.9  406.56  4984.4  406.06  5010.1  406.56    5022  412.63  5043.9  413.65
  5089.7  413.44  5107.5  411.48    5146  411.74  5211.4   413.3  5255.2  416.25
  5286.7  417.47  5333.2  422.37  5379.7  429.21  5408.4  429.99  5492.5  438.23
#Mann= 11 ,-1 , 0
  4000.1     .12       0  4240.1     .07       0  4379.9     .05       0
  4424.3     .07       0  4522.5     .05       0  4829.4      .1       0
  4943.7     .05       0  4983.9     .05       0  5010.1     .05       0
    5146    .035       0  5255.2     .12       0
Bank Sta=4983.9,5010.1
XS Rating Curve= 0 ,0
Exp/Cntr=0.3,0.1

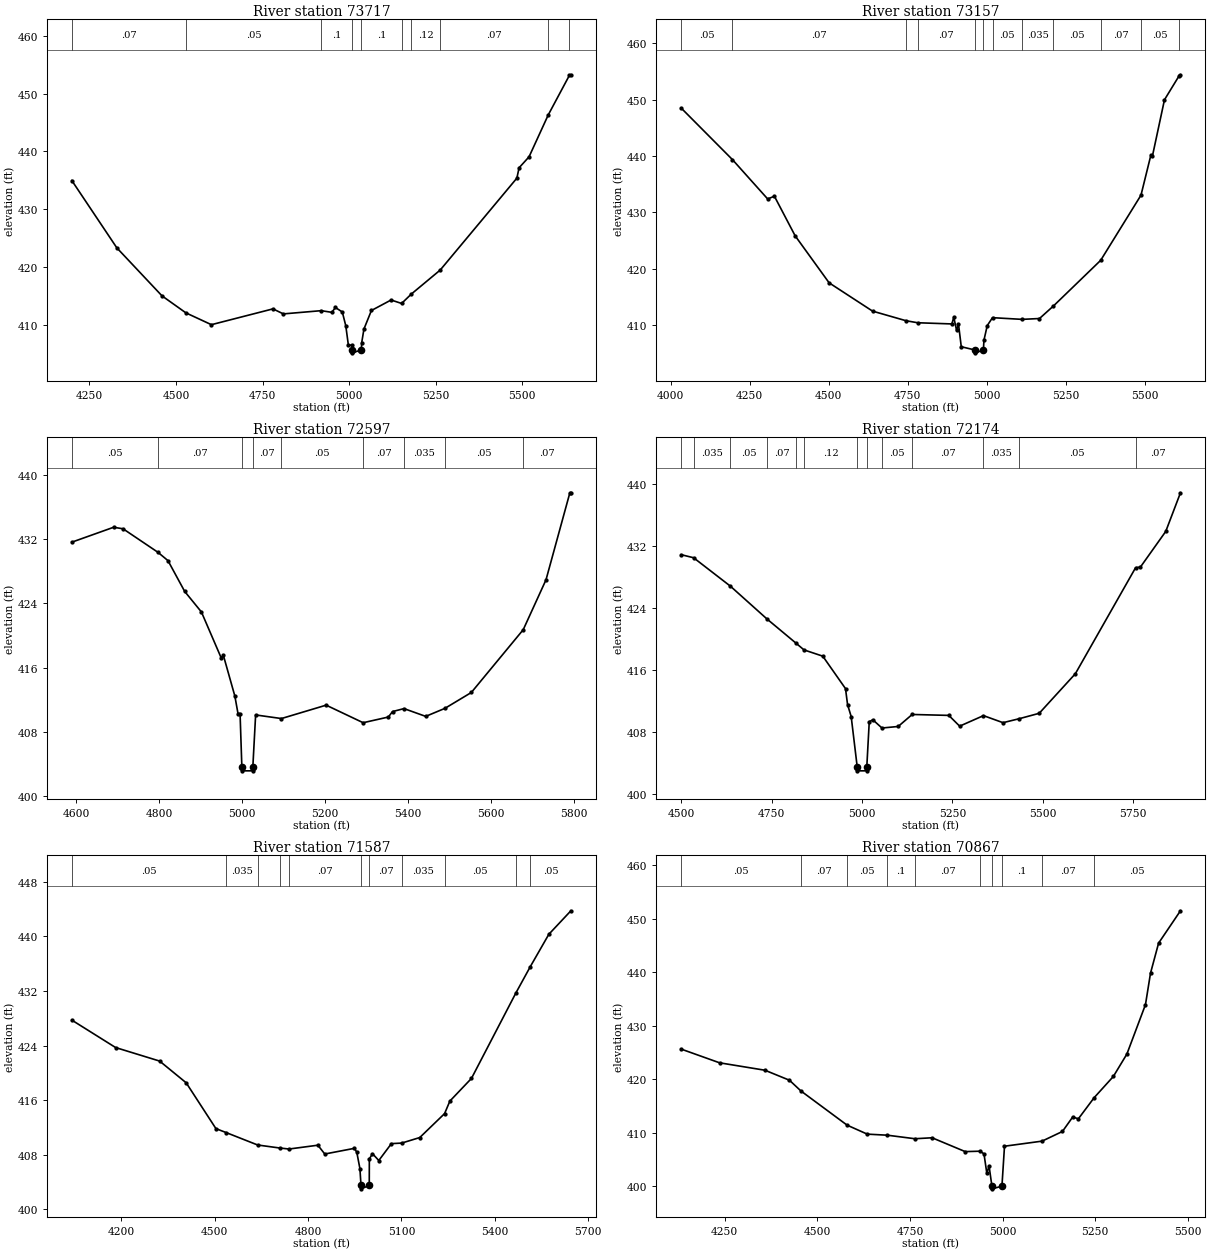
Type RM Length L Ch R = 1 ,73717   ,560,560,560
BEGIN DESCRIPTION:
Cooperas Creek 81.0
END DESCRIPTION:
XS GIS Cut Line= 3
      2494824.99       13837175.        2494025.       13837125.
      2493624.97     13836624.97
#Sta/Elev= 30
  4198.9  434.96  4329.1  423.28  4459.4  414.97  4528.5  412.02  4602.2  409.97
    4780  412.71  4810.1  411.84  4919.4   412.4  4950.3  412.11  4960.4  412.95
  4980.4  412.17  4990.4  409.79  4997.9  406.43  5007.7  406.42  5008.9  405.59
  5009.4  405.09  5035.3  405.59  5036.5  406.88  5042.9  409.22  5064.5  412.43
  5121.3  414.25  5151.7  413.65  5179.8  415.28  5263.2  419.44  5484.7  435.37
  5491.1  437.17  5519.9  439.07  5575.5  446.35  5636.7  453.22  5640.8  453.29
#Mann= 10 ,-1 , 0
  4198.9     .07       0  4528.5     .05       0  4919.4      .1       0
  5008.9     .05       0  5035.3      .1       0  5151.7      .1       0
  5179.8     .12       0  5263.2     .07       0  5575.5     .05       0
  5636.7     .07       0
Bank Sta=5008.9,5035.3
XS Rating Curve= 0 ,0
Exp/Cntr=0.3,0.1

Type RM Length L Ch R = 1 ,73157   ,560,560,560
BEGIN DESCRIPTION:
Cooperas Creek 80.0
END DESCRIPTION:
XS GIS Cut Line= 3
      2495025.03     13837225.02        2494225.       13836675.
      2493625.04     13836575.01
#Sta/Elev= 30
  4033.9  448.45  4195.5  439.35    4307  432.38  4328.2  432.87  4393.9  425.85
  4501.4  417.52  4638.8  412.51  4744.6  410.81  4781.5  410.45  4889.8  410.24
  4895.8  411.44  4904.6   409.1  4910.7  410.21  4919.5   406.2  4963.2  405.62
  4963.7  405.12  4989.6  405.62  4991.2  407.35  5001.7  409.95  5018.3  411.35
  5111.9  411.05    5167   411.2  5211.3  413.43  5360.6  421.51  5488.1  433.05
  5519.3  440.13  5524.3  439.98  5562.4  449.95    5609  454.22    5613  454.38
#Mann= 12 ,-1 , 0
  4033.9     .05       0  4195.5     .07       0  4744.6     .05       0
  4781.5     .07       0  4963.2     .05       0  4989.6     .07       0
  5018.3     .05       0  5111.9    .035       0  5211.3     .05       0
  5360.6     .07       0  5488.1     .05       0    5609     .07       0
Bank Sta=4963.2,4989.6
XS Rating Curve= 0 ,0
Exp/Cntr=0.3,0.1

Type RM Length L Ch R = 1 ,72597   ,423,423,423
BEGIN DESCRIPTION:
Cooperas Creek 79.0
END DESCRIPTION:
XS GIS Cut Line= 3
      2494925.02       13836325.        2494525.       13836375.
      2493725.04       13836375.
#Sta/Elev= 30
  4589.3  431.64  4690.1   433.5  4712.8  433.31  4796.9  430.38  4821.1  429.34
  4861.4   425.5  4901.7  422.94  4949.6  417.19  4954.6  417.54  4982.4  412.44
  4989.9  410.27  4994.9  410.27  4999.2  403.63  4999.7  403.13  5025.2  403.13
  5025.7  403.63  5032.4   410.1  5094.6  409.65  5202.4  411.32  5291.6  409.13
  5352.4  409.84  5362.4  410.52  5390.1  410.89  5442.4  409.92  5488.7  410.92
  5552.4   412.9  5677.5  420.73  5732.4  426.95  5789.9   437.8  5792.4   437.8
#Mann= 9 ,-1 , 0
  4589.3     .05       0  4796.9     .07       0  4999.2     .05       0
  5025.7     .07       0  5094.6     .05       0  5291.6     .07       0
  5390.1    .035       0  5488.7     .05       0  5677.5     .07       0
Bank Sta=4999.2,5025.7
XS Rating Curve= 0 ,0
Exp/Cntr=0.3,0.1

Type RM Length L Ch R = 1 ,72174   ,587,587,587
BEGIN DESCRIPTION:
X18528
END DESCRIPTION:
XS GIS Cut Line= 3
      2494856.61     13836129.22      2494420.66     13836002.07
      2493494.29     13836026.29
#Sta/Elev= 30
  4500.4   430.9  4534.2  430.51    4636  426.84  4737.8  422.58    4817   419.5
  4839.6  418.61  4891.6   417.8  4954.5  413.61  4960.2  411.54  4970.2     410
  4986.9  403.49  4987.4  402.99  5012.9  402.99  5013.4  403.49  5020.2  409.34
  5030.2  409.58  5055.4  408.52  5100.2  408.72    5139  410.27  5240.3  410.15
  5270.3  408.76  5336.2  410.12  5390.3  409.21  5434.9  409.72  5490.4  410.42
  5590.4  415.53    5757  429.22  5770.5  429.31  5840.5  433.91  5881.2   438.9
#Mann= 13 ,-1 , 0
  4500.4     .05       0  4534.2    .035       0    4636     .05       0
  4737.8     .07       0    4817     .05       0  4839.6     .12       0
  4986.9     .05       0  5013.4     .12       0  5055.4     .05       0
    5139     .07       0  5336.2    .035       0  5434.9     .05       0
    5757     .07       0
Bank Sta=4986.9,5013.4
XS Rating Curve= 0 ,0
Exp/Cntr=0.3,0.1

Type RM Length L Ch R = 1 ,71587   ,720,720,720
BEGIN DESCRIPTION:
X18527
END DESCRIPTION:
XS GIS Cut Line= 4
      2494808.18     13835989.96      2494553.87     13835705.38
      2494045.26     13835584.28      2493354.97     13835687.21
#Sta/Elev= 30
  4041.8  427.73  4182.5  423.71  4323.8  421.73    4409  418.55  4504.5  411.84
  4537.9  411.25  4638.5  409.44  4709.3     409  4739.1  408.85  4831.8  409.41
    4854  408.12  4948.9  408.95  4956.7   408.4  4966.8  405.99  4970.3  403.52
  4970.8  403.02  4996.8  403.52  4997.1   407.4  5007.2  408.17  5027.4  407.17
  5067.9  409.64  5100.8  409.72  5158.9  410.53  5238.7  414.04  5255.6  415.87
  5324.9  419.19  5467.5   431.7  5514.1  435.58  5573.4   440.3  5644.2  443.74
#Mann= 11 ,-1 , 0
  4041.8     .05       0  4537.9    .035       0  4638.5     .07       0
  4709.3    .035       0  4739.1     .07       0  4970.3     .05       0
  4996.8     .07       0  5100.8    .035       0  5238.7     .05       0
  5467.5     .07       0  5514.1     .05       0
Bank Sta=4970.3,4996.8
XS Rating Curve= 0 ,0
Exp/Cntr=0.3,0.1

Type RM Length L Ch R = 1 ,70867   ,549,549,549
BEGIN DESCRIPTION:
Cooperas Creek 78.0
END DESCRIPTION:
XS GIS Cut Line= 3
      2494775.01     13835925.02        2494325.       13835175.
      2494074.98     13834774.97
#Sta/Elev= 30
  4133.4  425.64  4236.4  423.09  4358.9   421.7    4425  419.83  4455.8  417.83
  4580.5  411.43  4634.9  409.75  4689.2  409.55  4763.4  408.89  4809.8  409.07
  4899.2  406.48  4939.2  406.56  4949.8  406.06  4957.5  402.39  4963.4  403.83
  4971.2  400.02  4971.7  399.52  4998.2  400.02  5005.1  407.49  5106.4  408.44
  5161.4  410.25  5189.1  412.95  5204.4  412.62  5247.1  416.58  5298.7  420.53
  5335.3  424.73  5385.4  433.97    5399  439.85  5420.8  445.47  5479.8  451.52
#Mann= 10 ,-1 , 0
  4133.4     .05       0  4455.8     .07       0  4580.5     .05       0
  4689.2      .1       0  4763.4     .07       0  4939.2      .1       0
  4971.2     .05       0  4998.2      .1       0  5106.4     .07       0
  5247.1     .05       0
Bank Sta=4971.2,4998.2
XS Rating Curve= 0 ,0
Exp/Cntr=0.3,0.1