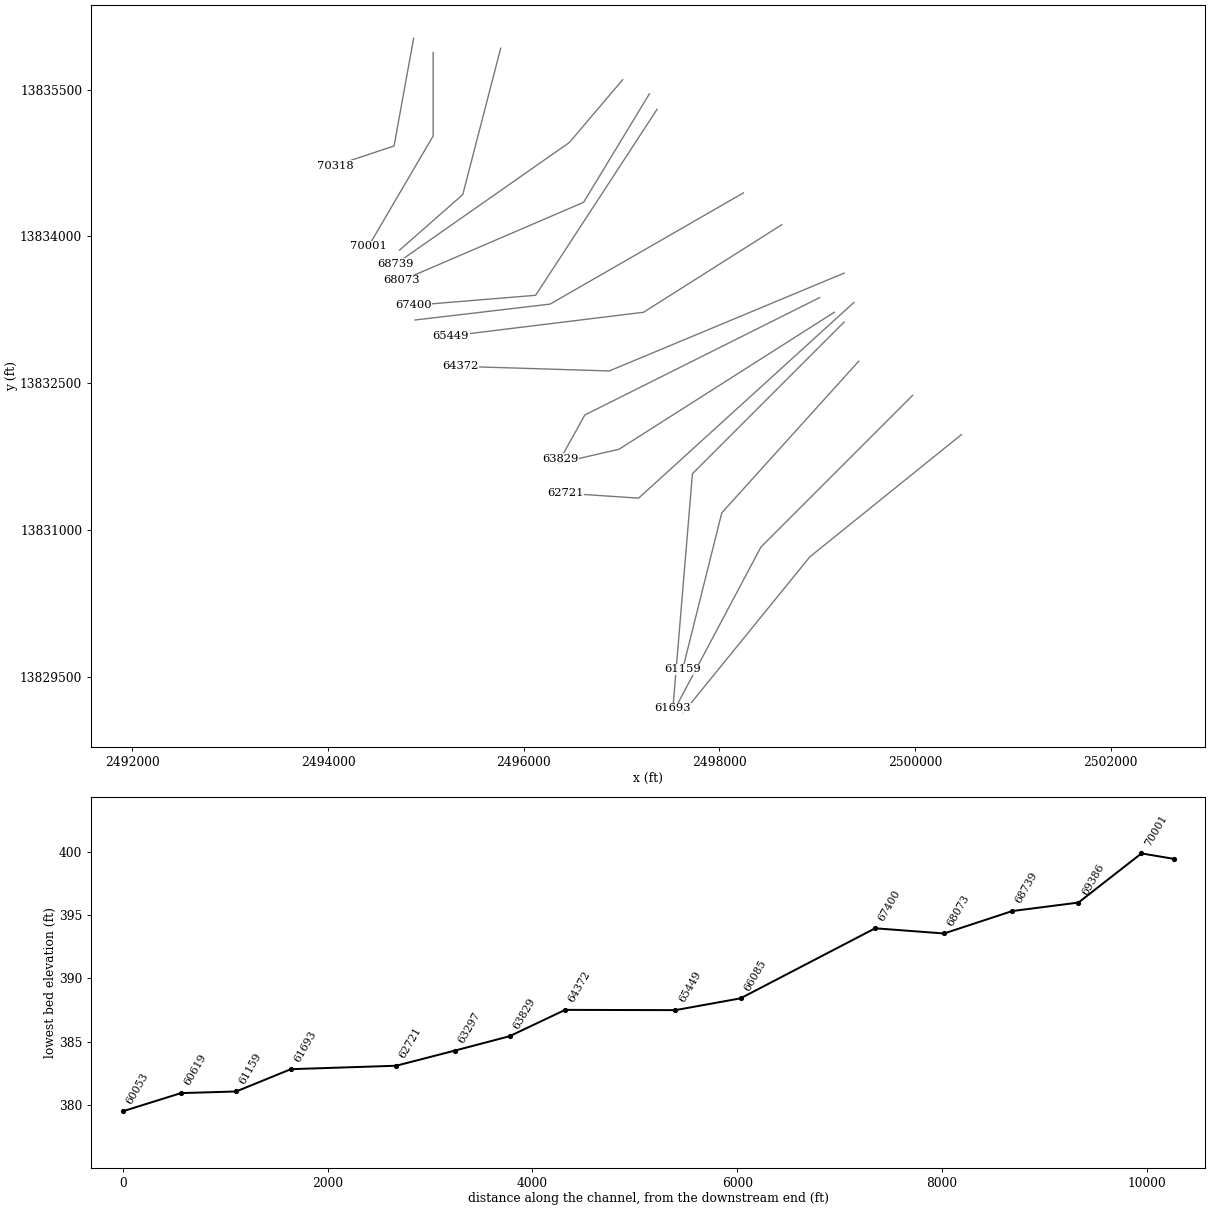
HEC-RAS study Copperas Creek.prj: Copperas Creek Base Level Engineering

--- Copperas Creek.g01 (geometry) --- (continued)

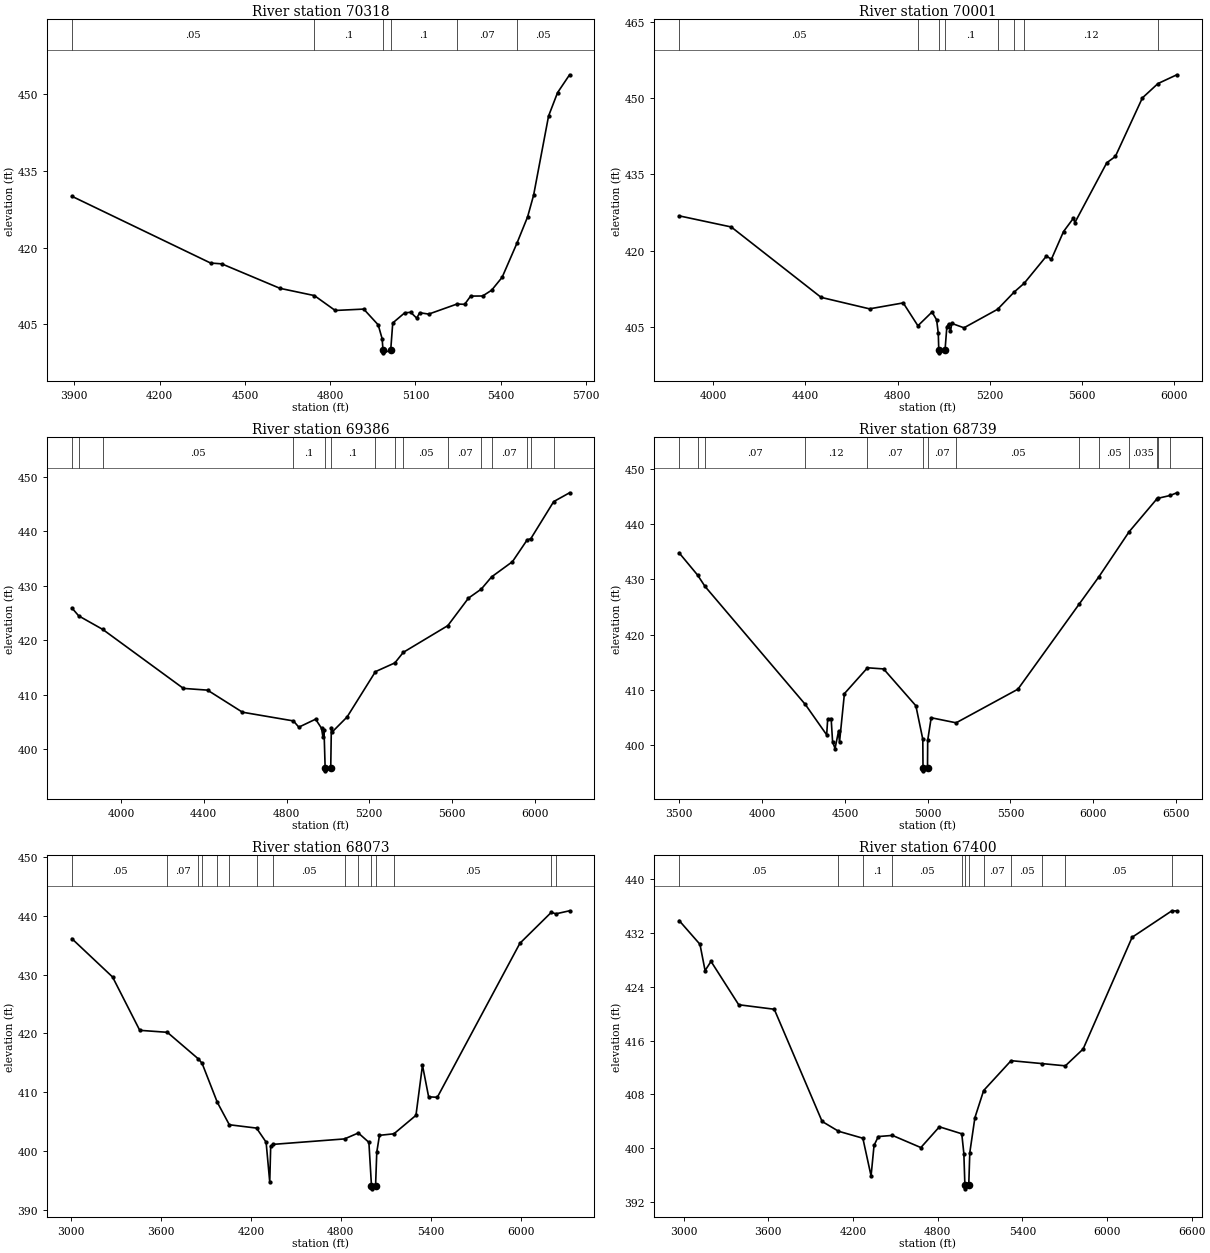
Type RM Length L Ch R = 1 ,70318   ,317,317,317
BEGIN DESCRIPTION:
Cooperas Creek 77.0
END DESCRIPTION:
XS GIS Cut Line= 3
        2494875.     13836024.99        2494675.       13834925.
      2494074.98     13834724.99
#Sta/Elev= 30
  3891.4  430.04  4379.3  416.99  4418.6  416.83  4623.2  412.05  4744.3  410.63
  4817.6  407.72  4917.9  407.99  4968.8  404.91  4982.7   402.2  4985.8  399.94
  4986.3  399.44  5012.8  399.94    5020  405.28  5062.1  407.26  5083.2  407.36
  5104.3  406.22  5114.8  407.28  5146.5  407.01  5246.1  408.98  5272.9  408.92
    5294  410.53  5336.2  410.55  5367.8  411.68  5404.7   414.2  5456.8  420.86
  5494.3  426.01  5515.4  430.24  5568.1  445.73  5599.7  450.29  5641.9  453.78
#Mann= 6 ,-1 , 0
  3891.4     .05       0  4744.3      .1       0  4985.8     .05       0
  5012.8      .1       0  5246.1     .07       0  5456.8     .05       0
Bank Sta=4985.8,5012.8
XS Rating Curve= 0 ,0
Exp/Cntr=0.3,0.1

Type RM Length L Ch R = 1 ,70001   ,615,615,615
BEGIN DESCRIPTION:
X18526
END DESCRIPTION:
XS GIS Cut Line= 3
       2495074.6     13835880.98       2495074.6     13835027.22
      2494414.62     13833901.01
#Sta/Elev= 30
  3852.6  426.84  4078.6  424.65  4468.6  410.79  4678.6  408.53  4824.8   409.7
  4888.5   405.2  4949.7   407.9  4969.7  406.37  4976.9  403.72  4979.1  400.37
  4979.6  399.87  5006.1  400.37  5014.1  405.02  5021.9  405.56  5029.8  404.11
  5035.6  405.66  5088.4   404.8  5234.1  408.44  5306.4  411.85  5350.1  413.59
  5446.1  418.92  5467.6  418.29  5520.3  423.75  5563.4  426.39  5569.2  425.49
  5707.9  437.29  5745.1  438.53  5862.4  450.06  5929.9  452.88  6011.7  454.61
#Mann= 8 ,-1 , 0
  3852.6     .05       0  4888.5      .1       0  4979.1     .05       0
  5006.1      .1       0  5234.1     .12       0  5306.4      .1       0
  5350.1     .12       0  5929.9    .035       0
Bank Sta=4979.1,5006.1
XS Rating Curve= 0 ,0
Exp/Cntr=0.3,0.1

Type RM Length L Ch R = 1 ,69386   ,647,647,647
BEGIN DESCRIPTION:
X18525
END DESCRIPTION:
XS GIS Cut Line= 3
      2495764.86     13835923.34      2495377.35     13834427.78
      2494730.54     13833859.55
#Sta/Elev= 30
  3762.3  425.95  3795.5  424.48  3911.8  421.99  4301.4  411.15  4418.1  410.83
    4587  406.77  4833.3  405.17  4859.4  404.02  4940.6  405.49  4969.2  403.81
  4976.1  402.17  4981.2  403.53  4986.7  396.49  4987.2  395.99  5013.7  396.49
  5016.7  403.95  5021.8  403.18  5092.7  405.89  5229.8  414.23  5323.8  415.84
  5364.5  417.78  5579.7  422.69  5679.5  427.75  5741.4  429.41  5791.5  431.66
  5892.1  434.45  5963.5  438.47  5980.7  438.67  6091.5   445.5  6168.2  447.12
#Mann= 15 ,-1 , 0
  3762.3     .05       0  3795.5     .07       0  3911.8     .05       0
  4833.3      .1       0  4986.7     .05       0  5013.7      .1       0
  5229.8     .05       0  5323.8     .07       0  5364.5     .05       0
  5579.7     .07       0  5741.4    .035       0  5791.5     .07       0
  5963.5     .12       0  5980.7    .035       0  6091.5     .12       0
Bank Sta=4986.7,5013.7
XS Rating Curve= 0 ,0
Exp/Cntr=0.3,0.1

Type RM Length L Ch R = 1 ,68739   ,666,666,666
BEGIN DESCRIPTION:
Cooperas Creek 76.0
END DESCRIPTION:
XS GIS Cut Line= 3
      2497012.17     13835602.42      2496467.25     13834960.61
       2494693.6     13833719.67
#Sta/Elev= 30
  3498.6  434.81  3609.7   430.8    3655  428.73  4261.1  407.34    4390  401.84
  4396.1  404.69    4417  404.79  4425.7  400.59  4440.5  399.36  4461.5  402.47
  4467.6  400.53  4497.2  409.31  4636.6  413.99  4733.8  413.78  4928.8  407.11
  4970.7  401.04    4972  395.82  4972.5  395.32  4999.1  395.82  5000.3  400.85
  5021.3  404.94    5172  404.02  5545.3  410.11    5914  425.47  6035.1   430.5
  6216.8  438.62  6385.5  444.61  6392.8   444.7  6466.1  445.21  6505.2  445.69
#Mann= 14 ,-1 , 0
  3498.6     .05       0  3609.7    .035       0    3655     .07       0
  4261.1     .12       0  4636.6     .07       0    4972     .05       0
  4999.1     .07       0    5172     .05       0    5914     .07       0
  6035.1     .05       0  6216.8    .035       0  6385.5     .12       0
  6392.8    .035       0  6466.1     .05       0
Bank Sta=4972,4999.1
XS Rating Curve= 0 ,0
Exp/Cntr=0.3,0.1

Type RM Length L Ch R = 1 ,68073   ,673,673,673
BEGIN DESCRIPTION:
Cooperas Creek 75.0
END DESCRIPTION:
XS GIS Cut Line= 3
      2497284.68     13835457.15      2496612.57     13834349.06
      2494753.88     13833549.89
#Sta/Elev= 30
  3006.2   436.1  3277.7  429.58  3458.9  420.51  3642.9  420.17  3850.7  415.63
  3874.8  414.89  3976.3  408.26  4056.3  404.45  4237.8  403.88  4301.6  401.49
  4325.9  394.71  4332.2  400.78  4346.7  401.11  4824.5  402.04  4916.7  403.05
  4987.1  401.46  5004.4  394.05  5004.9  393.55  5031.6  394.05  5039.7  399.79
  5057.7  402.65  5154.1  402.91    5301  406.05  5344.5  414.56  5385.5   409.2
  5443.5  409.12  5994.1  435.31  6203.9  440.58  6234.2  440.32  6325.4  440.84
#Mann= 15 ,-1 , 0
  3006.2     .05       0  3642.9     .07       0  3850.7     .05       0
  3874.8    .035       0  3976.3     .05       0  4056.3    .035       0
  4237.8      .1       0  4346.7     .05       0  4824.5     .07       0
  4916.7      .1       0  5004.4     .05       0  5031.6      .1       0
  5154.1     .05       0  6203.9    .035       0  6234.2     .05       0
Bank Sta=5004.4,5031.6
XS Rating Curve= 0 ,0
Exp/Cntr=0.3,0.1

Type RM Length L Ch R = 1 ,67400   ,1315,1315,1315
BEGIN DESCRIPTION:
Cooperas Creek 74.0
END DESCRIPTION:
XS GIS Cut Line= 3
      2497363.39     13835299.71      2496122.11     13833398.43
      2494869.34     13833295.55
#Sta/Elev= 30
  2967.4  433.88  3115.2  430.34  3151.4  426.43  3193.5   427.8  3389.7  421.35
  3641.8  420.68  3980.9  403.99    4097  402.53  4269.7  401.49  4327.9  395.88
    4349  400.42  4379.2  401.74  4479.3  401.91  4680.8   400.1  4812.2  403.19
  4970.8  402.15  4985.6  399.21    4993  394.46  4993.5  393.96  5020.2  394.46
  5027.7  399.35  5063.9  404.55  5125.9  408.59  5320.3  413.03  5537.3   412.6
    5705  412.26  5830.9  414.76  6178.3  431.39  6460.2  435.33    6495   435.3
#Mann= 12 ,-1 , 0
  2967.4     .05       0    4097    .035       0  4269.7      .1       0
  4479.3     .05       0  4970.8      .1       0    4993     .05       0
  5020.2      .1       0  5125.9     .07       0  5320.3     .05       0
  5537.3     .07       0    5705     .05       0  6460.2    .035       0
Bank Sta=4993,5020.2
XS Rating Curve= 0 ,0
Exp/Cntr=0.3,0.1

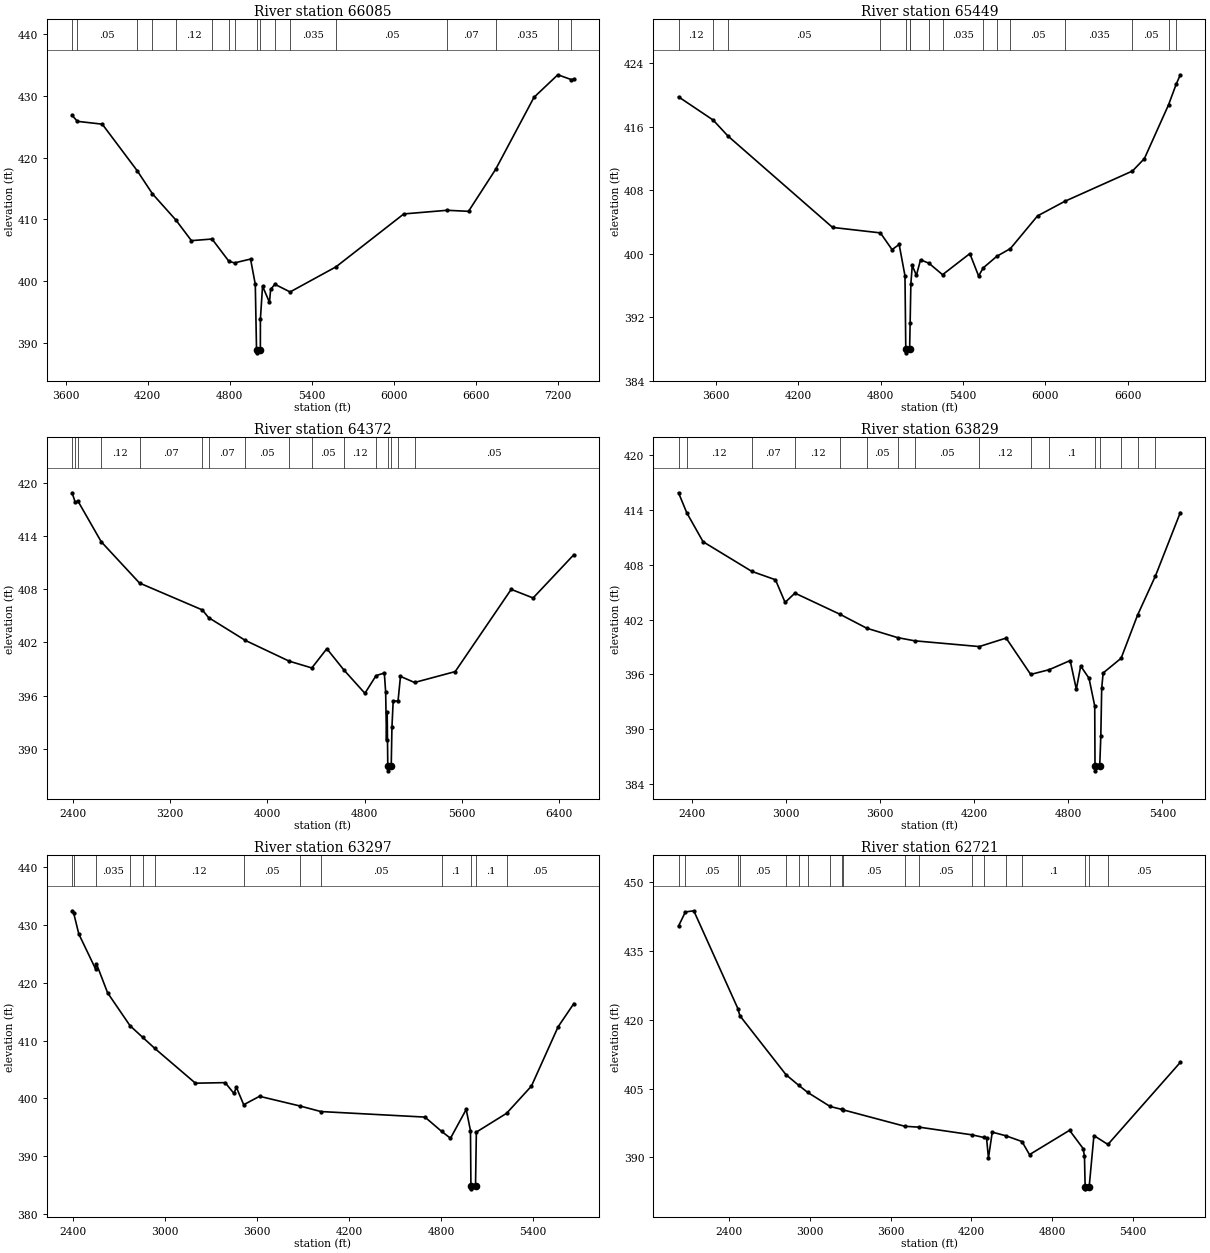
Type RM Length L Ch R = 1 ,66085   ,636,636,636
BEGIN DESCRIPTION:
X18524
END DESCRIPTION:
XS GIS Cut Line= 3
      2498246.49     13834445.36      2496270.31     13833308.38
      2494889.85     13833145.97
#Sta/Elev= 30
  3646.1  426.86  3684.7  425.88    3867  425.42  4122.4  417.89  4234.2  414.15
  4405.5  409.91    4519  406.58  4669.8  406.84  4793.4  403.23  4834.2  402.98
  4951.5   403.6  4986.1  399.51  4995.1  388.93  4995.6  388.43  5023.2  388.93
  5023.5   393.9  5039.2  399.21  5089.9   396.6  5098.2  398.68  5128.9  399.52
  5240.7  398.28  5576.2  402.34  6072.3   410.9  6389.2  411.49  6545.6  411.32
  6744.6  418.14  7024.3  429.76  7198.6  433.41  7297.4  432.63    7316   432.7
#Mann= 17 ,-1 , 0
  3646.1    .035       0  3684.7     .05       0  4122.4    .035       0
  4234.2     .05       0  4405.5     .12       0  4669.8     .07       0
  4793.4    .035       0  4834.2      .1       0  4995.1     .05       0
  5023.2      .1       0  5128.9      .1       0  5240.7    .035       0
  5576.2     .05       0  6389.2     .07       0  6744.6    .035       0
  7198.6     .05       0  7297.4    .035       0
Bank Sta=4995.1,5023.2
XS Rating Curve= 0 ,0
Exp/Cntr=0.3,0.1

Type RM Length L Ch R = 1 ,65449   ,1077,1077,1077
BEGIN DESCRIPTION:
Cooperas Creek 73.0
END DESCRIPTION:
XS GIS Cut Line= 3
      2498639.05     13834120.52        2497225.       13833225.
      2495255.11     13832983.52
#Sta/Elev= 30
  3326.7  419.77  3579.2  416.84  3687.6  414.82  4449.6  403.31  4798.4  402.62
  4883.5  400.51  4935.2  401.16  4977.6  397.21  4983.5     388    4984   387.5
  5011.6     388  5015.2  391.28  5020.6   396.2  5030.7  398.51  5060.9  397.27
  5091.1  399.23  5152.7  398.79  5251.6  397.35  5450.6  400.01  5514.3  397.19
  5548.3  398.21  5647.2  399.67  5746.1  400.64    5944  404.76  6141.8  406.59
  6636.3  410.42  6723.3  411.99  6898.9  418.75  6955.3  421.38  6985.1  422.55
#Mann= 16 ,-1 , 0
  3326.7     .12       0  3579.2     .07       0  3687.6     .05       0
  4798.4      .1       0  4983.5     .05       0  5011.6      .1       0
  5015.2     .07       0  5152.7     .05       0  5251.6    .035       0
  5548.3     .05       0  5647.2    .035       0  5746.1     .05       0
  6141.8    .035       0  6636.3     .05       0  6898.9    .035       0
  6955.3     .05       0
Bank Sta=4983.5,5011.6
XS Rating Curve= 0 ,0
Exp/Cntr=0.3,0.1

Type RM Length L Ch R = 1 ,64372   ,543,543,543
BEGIN DESCRIPTION:
Cooperas Creek 72.0
END DESCRIPTION:
XS GIS Cut Line= 3
      2499275.04     13833625.02        2496875.       13832625.
      2495349.98      13832672.2
#Sta/Elev= 30
  2395.3  418.87  2420.9  417.82  2444.2  417.92  2634.9  413.35  2950.2  408.69
  3466.5  405.66  3517.4   404.8  3819.4  402.23  4179.8  399.89  4366.6  399.12
    4490  401.29  4629.8   398.9  4803.1  396.26  4894.9  398.26  4962.8  398.55
  4973.7  396.39  4980.7     391  4986.1  394.19  4991.3  388.02  4991.8  387.52
  5019.4  388.02  5025.4  392.45  5035.4  395.38  5075.6   395.4  5095.4  398.17
  5211.2  397.48  5545.6  398.71  6005.8  407.98  6185.9  407.01  6521.1  411.89
#Mann= 16 ,-1 , 0
  2395.3     .05       0  2420.9     .07       0  2444.2     .05       0
  2634.9     .12       0  2950.2     .07       0  3466.5     .12       0
  3517.4     .07       0  3819.4     .05       0  4179.8     .07       0
  4366.6     .05       0  4629.8     .12       0  4894.9      .1       0
  4991.3     .05       0  5019.4      .1       0  5075.6     .07       0
  5211.2     .05       0
Bank Sta=4991.3,5019.4
XS Rating Curve= 0 ,0
Exp/Cntr=0.3,0.1

Type RM Length L Ch R = 1 ,63829   ,532,532,532
BEGIN DESCRIPTION:
Cooperas Creek 71.0
END DESCRIPTION:
XS GIS Cut Line= 3
      2499025.02     13833375.01        2496625.       13832175.
      2496374.99     13831724.98
#Sta/Elev= 30
  2316.7  415.87  2369.4  413.67  2473.2  410.51  2783.5  407.27  2934.4  406.35
  2995.9  403.87  3058.5  404.89  3346.1  402.57    3516  401.05  3712.7  400.02
  3821.3  399.67  4233.3  399.04  4404.6  399.97  4561.1  395.99    4679  396.51
  4812.7  397.51  4851.9  394.37  4879.8  396.91  4932.9  395.57  4969.3  392.53
    4971  385.94  4971.5  385.44    5001  385.94    5008   389.2  5013.7  394.48
  5022.9  396.15  5137.4  397.76  5242.2  402.48  5356.5  406.78  5514.8  413.71
#Mann= 16 ,-1 , 0
  2316.7    .035       0  2369.4     .12       0  2783.5     .07       0
  3058.5     .12       0  3346.1     .07       0    3516     .05       0
  3712.7     .07       0  3821.3     .05       0  4233.3     .12       0
  4561.1    .035       0    4679      .1       0    4971     .05       0
    5001      .1       0  5137.4     .05       0  5242.2     .07       0
  5356.5     .05       0
Bank Sta=4971,5001
XS Rating Curve= 0 ,0
Exp/Cntr=0.3,0.1

Type RM Length L Ch R = 1 ,63297   ,576,576,576
BEGIN DESCRIPTION:
Cooperas Creek 70.0
END DESCRIPTION:
XS GIS Cut Line= 3
      2499175.02     13833225.01        2496975.       13831825.
      2496324.99       13831675.
#Sta/Elev= 30
  2392.8  432.48  2403.7  432.04  2436.9  428.45  2545.8  422.42    2552  423.29
  2624.8  418.26  2771.4  412.56  2853.5  410.56  2932.5  408.64    3198  402.61
  3391.9  402.71  3449.4  400.83  3464.7  401.92    3513  398.88  3616.2  400.34
  3881.9  398.65  4016.5   397.7  4695.7  396.74  4804.6  394.26  4862.5  393.07
  4964.9  398.06  4992.9   394.4  4995.8  384.81  4996.3  384.31  5025.8  384.81
  5031.3  394.14  5228.4  397.39  5390.5   402.1    5565  412.39  5667.6  416.41
#Mann= 13 ,-1 , 0
  2392.8     .07       0  2403.7     .05       0  2545.8    .035       0
  2771.4     .12       0  2853.5     .05       0  2932.5     .12       0
    3513     .05       0  3881.9     .07       0  4016.5     .05       0
  4804.6      .1       0  4995.8     .05       0  5025.8      .1       0
  5228.4     .05       0
Bank Sta=4995.8,5025.8
XS Rating Curve= 0 ,0
Exp/Cntr=0.3,0.1

Type RM Length L Ch R = 1 ,62721   ,1028,1028,1028
BEGIN DESCRIPTION:
Cooperas Creek 69.0
END DESCRIPTION:
XS GIS Cut Line= 3
        2499375.       13833325.        2497175.       13831325.
      2496424.97       13831375.
#Sta/Elev= 30
  2026.4  440.49  2077.3  443.56  2139.6  443.82  2466.7  422.48  2481.6  420.91
  2824.1  408.03  2917.4  405.74  2985.9  404.15  3151.9  401.09  3236.5  400.47
  3243.9  400.39  3706.2  396.77  3814.5  396.57  4207.1  394.89  4293.3  394.32
  4312.7  394.23  4326.9  389.84  4355.3  395.49  4455.7   394.7  4575.8  393.44
  4631.7  390.58    4929  395.89  5029.7  391.91  5039.7  390.24  5044.7  383.61
  5045.2  383.11  5074.8  383.61  5109.9  394.74  5213.8   392.8  5751.3  410.73
#Mann= 19 ,-1 , 0
  2026.4     .07       0  2077.3     .05       0  2466.7    .035       0
  2481.6     .05       0  2824.1    .035       0  2917.4     .05       0
  2985.9    .035       0  3151.9     .12       0  3236.5    .035       0
  3243.9     .05       0  3706.2     .07       0  3814.5     .05       0
  4207.1     .07       0  4293.3      .1       0  4455.7     .07       0
  4575.8      .1       0  5044.7     .05       0  5074.8      .1       0
  5213.8     .05       0
Bank Sta=5044.7,5074.8
XS Rating Curve= 0 ,0
Exp/Cntr=0.3,0.1

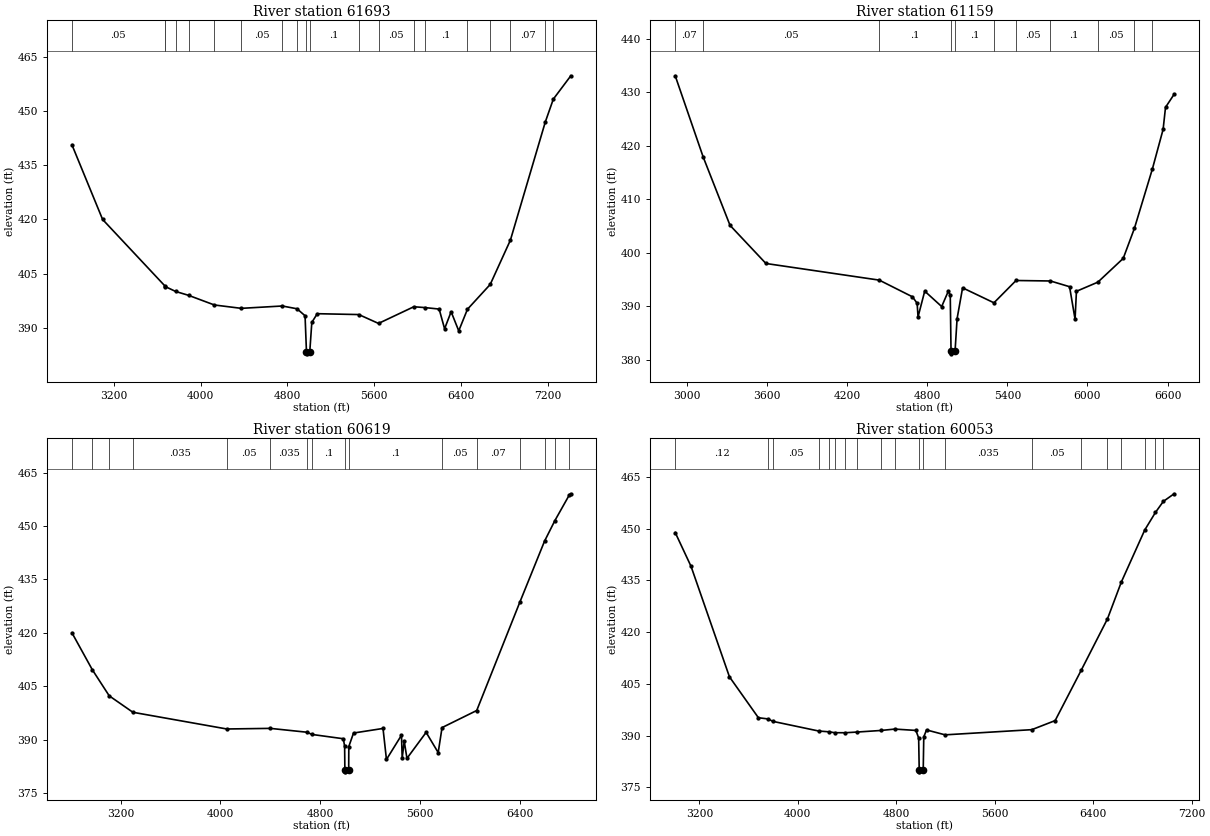
Type RM Length L Ch R = 1 ,61693   ,534,534,534
BEGIN DESCRIPTION:
Cooperas Creek 68.0
END DESCRIPTION:
XS GIS Cut Line= 3
      2499275.03     13833125.03        2497725.       13831575.
        2497525.       13829175.
#Sta/Elev= 30
    2813  440.65  3095.9     420  3669.3  401.65  3673.9  401.44  3769.5  400.09
  3888.2  399.02  4126.5  396.35  4374.2  395.42  4753.1  396.07  4888.6   395.3
  4962.7  393.37  4975.8  383.34  4976.3  382.84    5006  383.34  5025.1  391.53
  5075.3  393.94  5458.3   393.7    5640  391.25  5965.5  395.86  6064.5  395.64
  6199.2  395.22  6249.4  389.77  6309.6  394.48  6379.8   389.2  6460.3  395.17
  6670.1  402.03  6856.2  414.28  7178.2  446.97  7252.1  453.28  7413.4  459.73
#Mann= 20 ,-1 , 0
    2813     .05       0  3669.3    .035       0  3673.9     .05       0
  3769.5    .035       0  3888.2     .05       0  4126.5     .07       0
  4374.2     .05       0  4753.1     .07       0  4888.6      .1       0
  4975.8     .05       0    5006      .1       0  5458.3     .07       0
    5640     .05       0  5965.5     .07       0  6064.5      .1       0
  6460.3     .05       0  6670.1    .035       0  6856.2     .07       0
  7178.2     .12       0  7252.1     .07       0
Bank Sta=4975.8,5006
XS Rating Curve= 0 ,0
Exp/Cntr=0.3,0.1

Type RM Length L Ch R = 1 ,61159   ,540,540,540
BEGIN DESCRIPTION:
Cooperas Creek 67.0
END DESCRIPTION:
XS GIS Cut Line= 3
      2499425.03     13832725.03        2498025.       13831175.
      2497625.01     13829575.05
#Sta/Elev= 30
  2911.5  433.06    3121  417.88  3322.2   405.1  3591.2  397.97  4440.3  394.86
    4689  391.74  4724.1  390.53  4730.8  387.99  4780.9   392.8  4907.9  389.92
    4958  392.81  4972.2  392.05    4978  381.58  4978.5  381.08  5008.2  381.58
  5023.4  387.66  5064.6  393.42  5299.6  390.62  5465.2  394.79  5722.7   394.7
  5866.1  393.63  5907.3  387.55  5917.6  392.77  6078.1  394.48  6268.1  398.92
  6351.8  404.53  6486.7  415.65    6567  423.04    6585  427.16  6649.4   429.6
#Mann= 11 ,-1 , 0
  2911.5     .07       0    3121     .05       0  4440.3      .1       0
    4978     .05       0  5008.2      .1       0  5299.6     .07       0
  5465.2     .05       0  5722.7      .1       0  6078.1     .05       0
  6351.8    .035       0  6486.7     .07       0
Bank Sta=4978,5008.2
XS Rating Curve= 0 ,0
Exp/Cntr=0.3,0.1

Type RM Length L Ch R = 1 ,60619   ,566,566,566
BEGIN DESCRIPTION:
Cooperas Creek 66.0
END DESCRIPTION:
XS GIS Cut Line= 3
      2499974.98     13832374.98        2498425.       13830825.
      2497574.99     13829224.98
#Sta/Elev= 30
    2808  420.02  2971.9  409.62  3107.4   402.3  3297.5  397.68    4051  392.99
  4400.1  393.16  4696.5  392.07  4733.2  391.46  4985.9  390.25  4996.5  388.17
  4998.5  381.45    4999  380.95  5029.1  381.45  5030.1  388.06  5067.9  391.85
  5304.6  393.14  5332.2  384.42  5452.8  391.24  5458.4  384.81  5474.8  389.55
  5496.7  384.73  5650.6  392.04  5747.4  386.36  5778.3  393.38  6056.6  398.18
  6401.6  428.53    6601  445.77  6683.3   451.5  6800.3  458.78  6811.8  459.07
#Mann= 16 ,-1 , 0
    2808     .07       0  2971.9     .05       0  3107.4     .12       0
  3297.5    .035       0    4051     .05       0  4400.1    .035       0
  4696.5     .05       0  4733.2      .1       0  4998.5     .05       0
  5029.1      .1       0  5778.3     .05       0  6056.6     .07       0
  6401.6    .035       0    6601     .07       0  6683.3    .035       0
  6800.3     .07       0
Bank Sta=4998.5,5029.1
XS Rating Curve= 0 ,0
Exp/Cntr=0.3,0.1

Type RM Length L Ch R = 1 ,60053   ,569,569,569
BEGIN DESCRIPTION:
Cooperas Creek 65.0
END DESCRIPTION:
XS GIS Cut Line= 3
      2500475.01     13831975.01        2498925.       13830725.
        2497625.     13829124.99
#Sta/Elev= 30
  3004.2  448.86  3132.7  439.07  3444.9  407.04  3679.9   395.2  3759.5  394.84
  3796.9  394.15  4169.3  391.35  4252.4  391.12  4300.3  390.86  4386.4  390.85
  4477.9  391.04  4676.1  391.51  4787.6  391.91  4959.5  391.52  4981.8  389.33
  4986.4  380.02  4986.9  379.52  5018.9  380.02  5023.4  389.66  5045.7  391.66
  5196.5  390.24  5901.2  391.74  6090.6  394.37  6302.1  408.94  6515.4  423.83
  6628.5  434.54  6818.7  449.61  6905.6   454.7  6969.7  457.89    7057  460.09
#Mann= 20 ,-1 , 0
  3004.2     .12       0  3759.5    .035       0  3796.9     .05       0
  4169.3    .035       0  4252.4     .05       0  4300.3    .035       0
  4386.4     .05       0  4477.9    .035       0  4676.1     .05       0
  4787.6      .1       0  4986.4     .05       0  5018.9      .1       0
  5196.5    .035       0  5901.2     .05       0  6302.1     .07       0
  6515.4     .05       0  6628.5     .07       0  6818.7    .035       0
  6905.6     .05       0  6969.7    .035       0
Bank Sta=4986.4,5018.9
XS Rating Curve= 0 ,0
Exp/Cntr=0.3,0.1