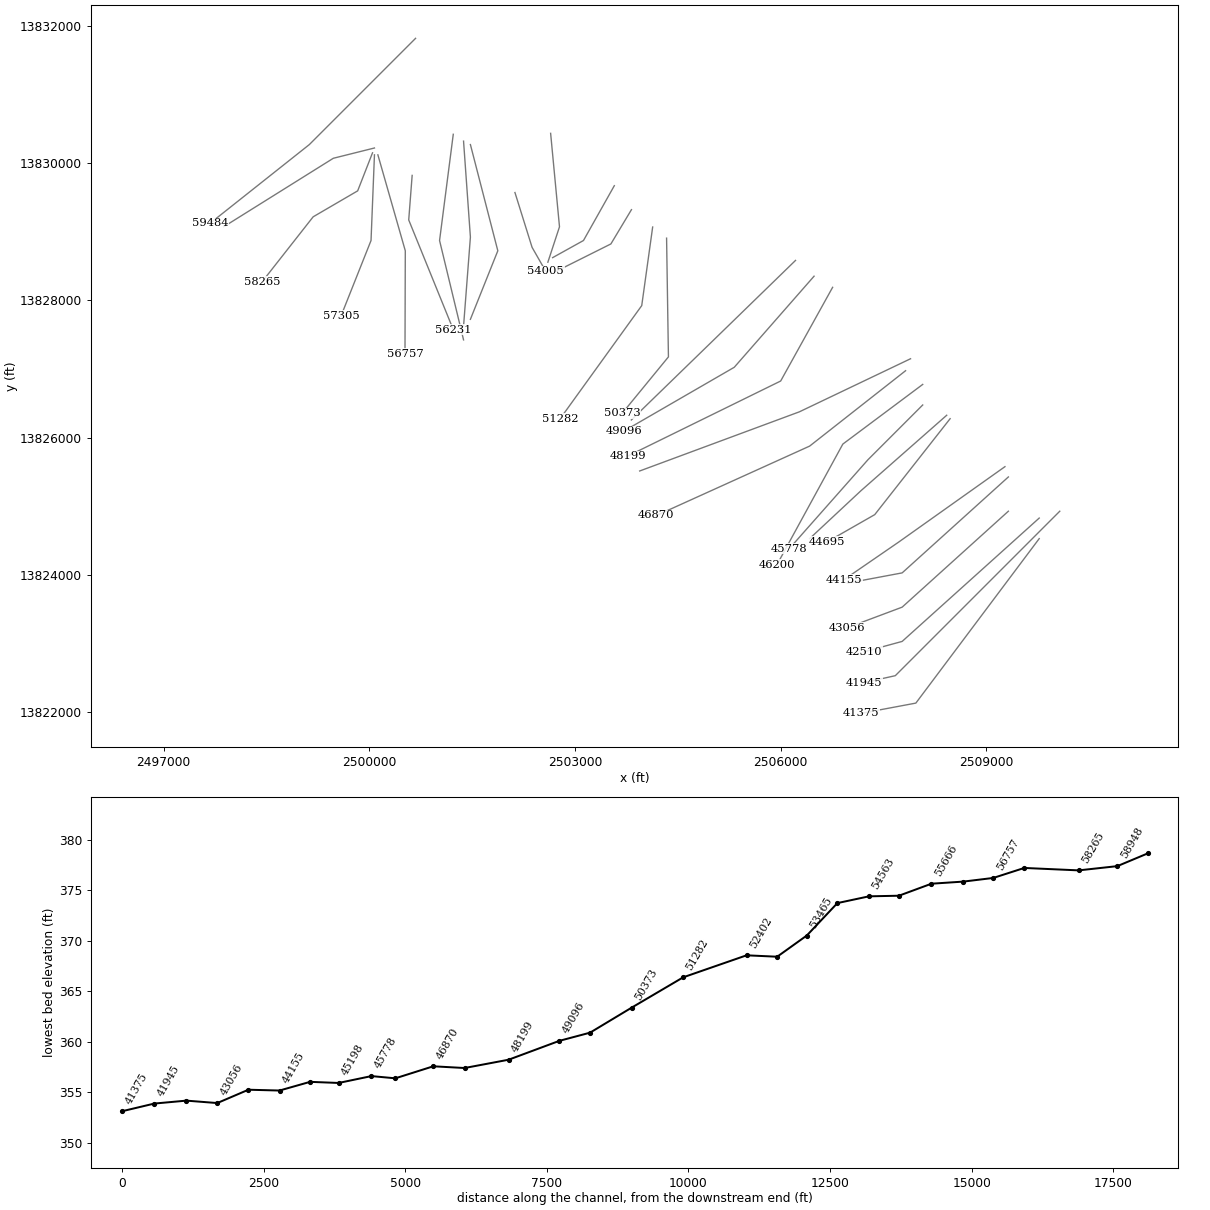
HEC-RAS study Copperas Creek.prj: Copperas Creek Base Level Engineering

--- Copperas Creek.g01 (geometry) --- (continued)

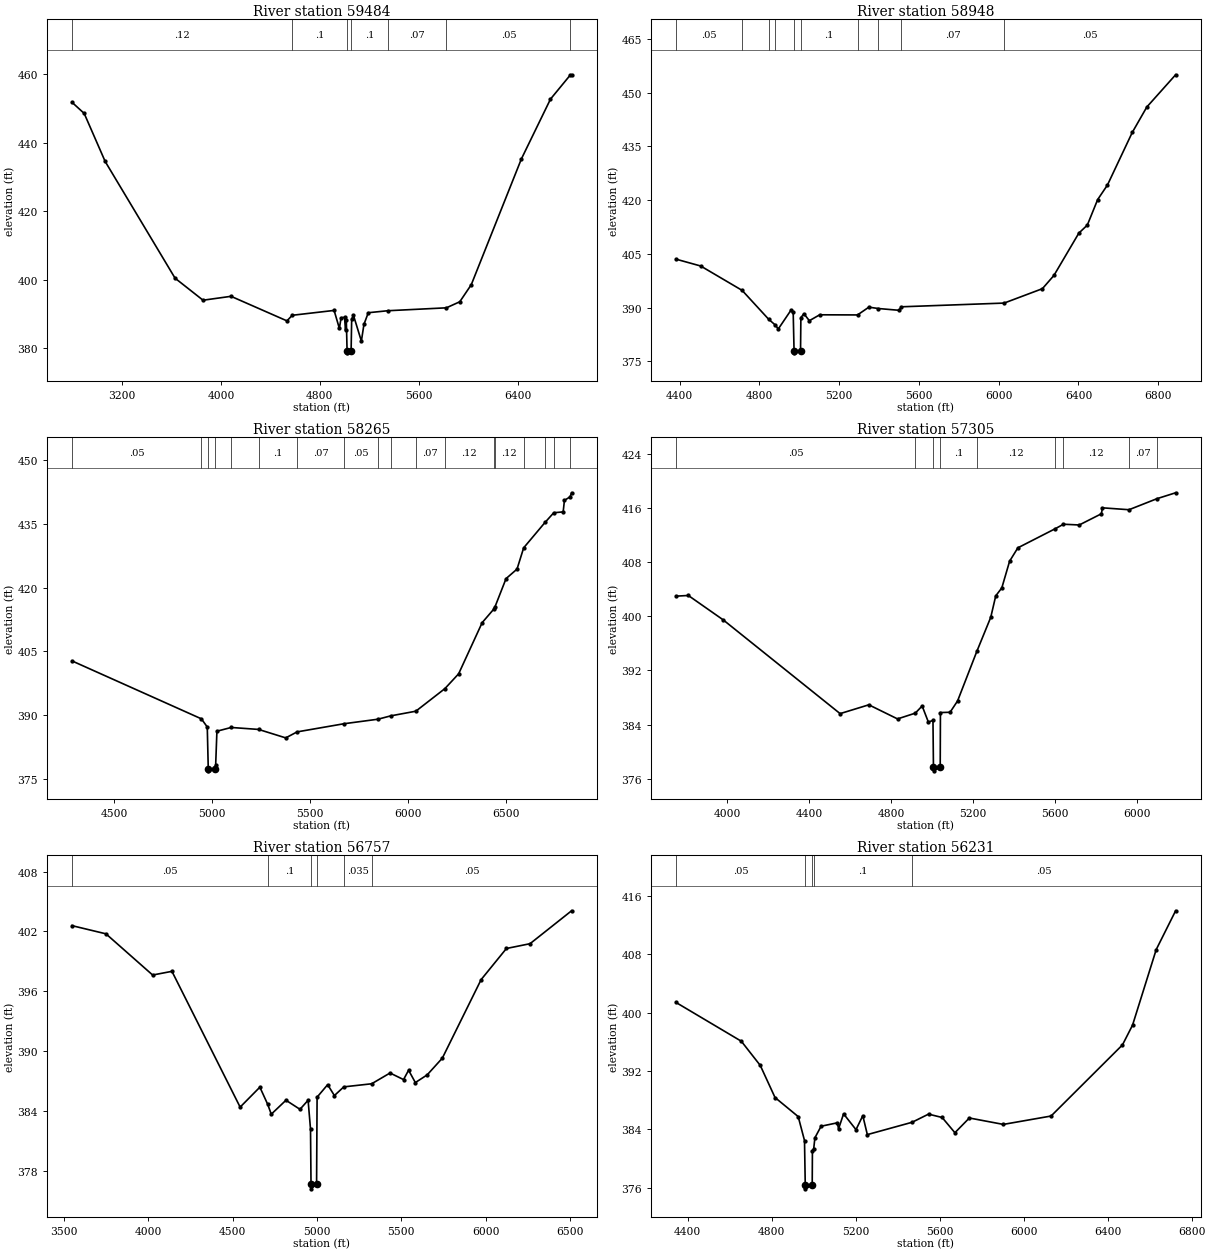
Type RM Length L Ch R = 1 ,59484   ,536,536,536
BEGIN DESCRIPTION:
Cooperas Creek 64.0
END DESCRIPTION:
XS GIS Cut Line= 3
      2500675.01     13831825.01        2499125.       13830275.
      2497675.02     13829125.02
#Sta/Elev= 30
  2794.6  451.82  2893.6  448.56  3063.3  434.53    3629  400.43  3855.3     394
  4081.6  395.14  4534.1  387.97  4577.3   389.6  4915.9  391.02  4958.4  385.77
  4972.5  388.86  5000.2  389.01  5008.3  385.18  5014.7  388.15  5020.9  379.13
  5021.4  378.63  5053.4  379.13    5058  388.47  5072.4  389.59  5136.5  382.06
  5157.3  386.95  5192.5  390.35  5350.9  390.93  5824.5  391.78  5932.8  393.55
  6025.7  398.53  6431.1  435.26  6666.7  452.74  6828.6  459.85  6837.3  459.77
#Mann= 7 ,-1 , 0
  2794.6     .12       0  4577.3      .1       0  5020.9     .05       0
  5053.4      .1       0  5350.9     .07       0  5824.5     .05       0
  6828.6    .035       0
Bank Sta=5020.9,5053.4
XS Rating Curve= 0 ,0
Exp/Cntr=0.3,0.1

Type RM Length L Ch R = 1 ,58948   ,683,683,683
BEGIN DESCRIPTION:
Cooperas Creek 63.0
END DESCRIPTION:
XS GIS Cut Line= 3
      2500075.02       13830225.        2499475.       13830075.
      2497874.98     13829074.99
#Sta/Elev= 30
  4381.9  403.52  4505.6  401.61  4713.5   394.8  4846.5  386.74    4879  385.17
  4894.7  384.03  4959.2  389.35  4969.5  388.66  4973.8  377.87  4974.4  377.37
  5006.3  377.87    5008  387.21  5023.4  388.28  5050.5  386.34  5102.4  387.99
    5292  387.95  5348.9  390.12    5397  389.74    5501  389.24  5511.1  390.22
  6027.2  391.26  6219.1  395.28  6276.9  398.97  6401.9  410.79  6444.4  413.03
  6496.3  420.16  6545.2   424.2  6669.6  438.88  6742.7  445.99  6887.2  454.99
#Mann= 10 ,-1 , 0
  4381.9     .05       0  4713.5    .035       0  4846.5     .05       0
    4879      .1       0  4973.8     .05       0  5006.3      .1       0
    5292     .07       0    5397      .1       0  5511.1     .07       0
  6027.2     .05       0
Bank Sta=4973.8,5006.3
XS Rating Curve= 0 ,0
Exp/Cntr=0.3,0.1

Type RM Length L Ch R = 1 ,58265   ,960,960,960
BEGIN DESCRIPTION:
X18523
END DESCRIPTION:
XS GIS Cut Line= 4
      2500046.76     13830154.59      2499830.18     13829599.61
      2499180.47     13829220.62        2498436.     13828273.11
#Sta/Elev= 30
  4283.3  402.78  4944.6  389.17  4974.7  387.25  4979.8  377.45  4980.3  376.95
  5012.6  377.45  5017.7  378.42    5024  386.26    5097  387.14  5236.9  386.68
  5375.7  384.69  5433.6   386.1  5673.9  388.02  5846.9  389.08  5912.5  389.87
  6040.3  390.96    6189  396.27  6259.2  399.75  6379.4  411.77  6437.5  414.88
  6444.9  415.48  6501.4  422.11  6557.5  424.35  6591.4  429.34  6700.9  435.33
  6745.3  437.59  6793.3  437.79  6799.7  440.49  6828.9  441.34  6836.2  442.28
#Mann= 18 ,-1 , 0
  4283.3     .05       0  4944.6      .1       0  4979.8     .05       0
  5012.6      .1       0    5097    .035       0  5236.9      .1       0
  5433.6     .07       0  5673.9     .05       0  5846.9     .07       0
  5912.5     .05       0  6040.3     .07       0    6189     .12       0
  6437.5    .035       0  6444.9     .12       0  6591.4    .035       0
  6700.9     .12       0  6745.3    .035       0  6828.9     .12       0
Bank Sta=4979.8,5012.6
XS Rating Curve= 0 ,0
Exp/Cntr=0.3,0.1

Type RM Length L Ch R = 1 ,57305   ,548,548,548
BEGIN DESCRIPTION:
Cooperas Creek 62.0
END DESCRIPTION:
XS GIS Cut Line= 3
        2500075.     13830124.97        2500025.       13828875.
      2499586.55     13827772.34
#Sta/Elev= 30
  3749.8  402.96  3809.8  403.06    3980  399.46  4550.4  385.63  4690.5  386.93
  4830.6  384.85  4917.2   385.7  4950.7  386.76  4980.8   384.4  5003.5  384.62
  5005.8  377.69  5006.4  377.19  5038.8  377.69  5039.9  385.79  5086.9  385.83
  5123.5   387.5  5217.7  394.83  5285.4  399.84  5309.7     403  5339.4  404.18
  5377.4  408.12  5417.7  410.09  5600.8  412.92  5640.2  413.57  5717.2  413.46
  5825.1  415.11  5830.5  415.99  5959.8  415.71  6096.5  417.34  6187.4  418.21
#Mann= 9 ,-1 , 0
  3749.8     .05       0  4917.2      .1       0  5005.8     .05       0
  5038.8      .1       0  5217.7     .12       0  5600.8     .07       0
  5640.2     .12       0  5959.8     .07       0  6096.5     .12       0
Bank Sta=5005.8,5038.8
XS Rating Curve= 0 ,0
Exp/Cntr=0.3,0.1

Type RM Length L Ch R = 1 ,56757   ,526,526,526
BEGIN DESCRIPTION:
Cooperas Creek 61.0
END DESCRIPTION:
XS GIS Cut Line= 3
      2500124.99     13830125.03        2500525.       13828725.
       2500520.5     13827218.66
#Sta/Elev= 30
  3547.6  402.58  3749.1  401.76    4026  397.63  4140.4     398  4544.8  384.39
  4661.8  386.39  4708.5  384.66  4729.4  383.68  4816.5  385.08  4899.7  384.17
  4947.8  385.08  4962.1  382.19  4965.1   376.7  4965.6   376.2  4998.1   376.7
  5001.1  385.39  5063.7  386.64  5103.7  385.55  5159.5  386.42  5324.6  386.73
  5433.7  387.81  5513.7  387.15  5543.7  388.09  5583.7  386.85  5653.7  387.62
  5743.7   389.3  5973.7  397.17  6123.7  400.29  6263.7  400.77    6510  404.07
#Mann= 6 ,-1 , 0
  3547.6     .05       0  4708.5      .1       0  4965.1     .05       0
  4998.1      .1       0  5159.5    .035       0  5324.6     .05       0
Bank Sta=4965.1,4998.1
XS Rating Curve= 0 ,0
Exp/Cntr=0.3,0.1

Type RM Length L Ch R = 1 ,56231   ,565,565,565
BEGIN DESCRIPTION:
Cooperas Creek 60.0
END DESCRIPTION:
XS GIS Cut Line= 3
        2500625.     13829825.05        2500575.       13829175.
      2501225.02     13827574.96
#Sta/Elev= 30
  4344.7  401.41  4655.7  396.09  4745.9  392.77  4816.1  388.37  4926.5  385.75
  4956.5  382.47  4960.1  376.34  4960.7  375.84  4993.2  376.34  4994.2   381.1
  5000.4  381.36    5006  382.84  5035.5  384.43  5113.1   384.9  5118.5  384.06
  5142.6  386.13  5201.7  383.96  5234.1  385.88  5255.7  383.28  5468.6  384.97
  5547.1  386.09  5611.9  385.63  5672.7  383.54  5741.4  385.56  5903.3  384.68
  6130.6  385.83  6470.6  395.59  6518.6   398.3  6631.3  408.67  6723.7  413.99
#Mann= 5 ,-1 , 0
  4344.7     .05       0  4960.1     .05       0  4993.2     .05       0
  5000.4      .1       0  5468.6     .05       0
Bank Sta=4960.1,4993.2
XS Rating Curve= 0 ,0
Exp/Cntr=0.3,0.1

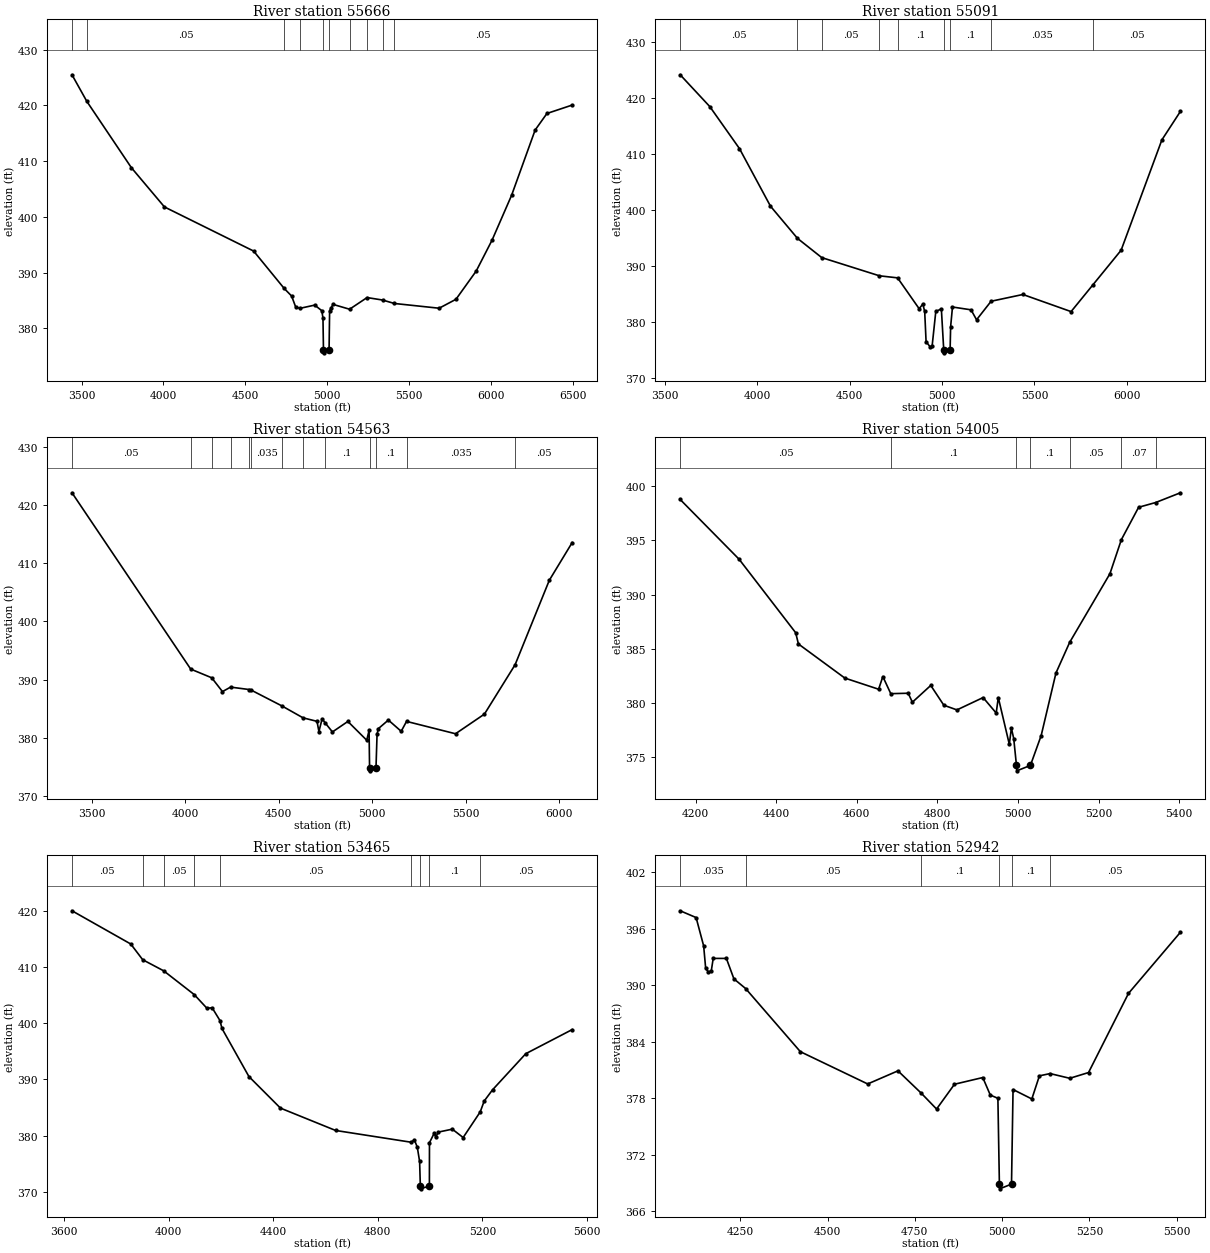
Type RM Length L Ch R = 1 ,55666   ,575,575,575
BEGIN DESCRIPTION:
Cooperas Creek 59.0
END DESCRIPTION:
XS GIS Cut Line= 3
        2501225.     13830424.97        2501025.       13828875.
      2501375.01     13827424.96
#Sta/Elev= 30
  3441.3  425.49  3532.1  420.71  3804.2  408.82  4005.9  401.79  4550.4  393.88
  4736.9  387.18  4782.3  385.82  4808.1  383.78  4836.5  383.63  4923.5  384.19
  4966.9  383.18  4973.9  381.84  4976.9  376.13  4977.6  375.63  5011.1  376.13
  5014.4  383.08  5022.5  383.61    5035  384.32  5136.4  383.45  5243.1  385.54
  5337.5   385.1  5410.2  384.48  5683.1  383.63  5785.9  385.23  5909.4  390.29
  6006.4  395.84  6125.4  403.86  6269.4  415.58  6341.4  418.55  6495.8  420.06
#Mann= 10 ,-1 , 0
  3441.3     .07       0  3532.1     .05       0  4736.9    .035       0
  4836.5      .1       0  4976.9     .05       0  5011.1      .1       0
  5136.4    .035       0  5243.1     .05       0  5337.5    .035       0
  5410.2     .05       0
Bank Sta=4976.9,5011.1
XS Rating Curve= 0 ,0
Exp/Cntr=0.3,0.1

Type RM Length L Ch R = 1 ,55091   ,528,528,528
BEGIN DESCRIPTION:
Cooperas Creek 58.0
END DESCRIPTION:
XS GIS Cut Line= 3
        2501375.     13830325.02        2501475.       13828925.
        2501375.     13827625.03
#Sta/Elev= 30
  3582.8  424.14  3743.2  418.45  3903.6  410.95  4071.6  400.65  4217.7   394.9
  4349.1  391.46    4661  388.21  4759.5  387.84  4876.1  382.33  4896.2  383.15
  4906.2  381.83  4913.7  376.44  4936.3  375.48  4946.3  375.62  4966.3  381.84
  4996.4  382.29  5009.3  374.94    5010  374.44  5043.7  374.94  5046.6  379.13
  5056.6  382.63  5156.9  382.13    5187  380.35  5265.6  383.66  5437.7  384.87
  5698.5  381.81  5816.5  386.59  5969.3  392.78  6189.9   412.5  6290.2  417.59
#Mann= 9 ,-1 , 0
  3582.8     .05       0  4217.7     .07       0  4349.1     .05       0
    4661    .035       0  4759.5      .1       0  5009.3     .05       0
  5043.7      .1       0  5265.6    .035       0  5816.5     .05       0
Bank Sta=5009.3,5043.7
XS Rating Curve= 0 ,0
Exp/Cntr=0.3,0.1

Type RM Length L Ch R = 1 ,54563   ,558,558,558
BEGIN DESCRIPTION:
Cooperas Creek 57.0
END DESCRIPTION:
XS GIS Cut Line= 3
      2501475.01     13830274.96        2501875.       13828725.
      2501474.99     13827724.98
#Sta/Elev= 30
  3393.1  422.07  4028.6  391.83  4141.1  390.34  4198.6  387.97    4242  388.74
  4342.9  388.32  4352.1  388.23  4517.6   385.5    4630  383.47  4704.7  382.87
    4715  381.12  4732.1  383.31  4747.3  382.65  4787.3  381.05  4869.9  382.85
  4970.9  379.63  4983.5  381.31  4986.1  374.88  4986.8  374.38  5020.5  374.88
  5026.2  380.66  5032.9  381.61  5086.7  383.09  5155.4  381.16    5184  382.86
  5446.2  380.74    5601  384.11  5765.2  392.58  5948.4  407.07  6070.9  413.54
#Mann= 13 ,-1 , 0
  3393.1     .05       0  4028.6    .035       0  4141.1     .07       0
    4242    .035       0  4342.9      .1       0  4352.1    .035       0
  4517.6     .05       0    4630    .035       0  4747.3      .1       0
  4986.1     .05       0  5020.5      .1       0    5184    .035       0
  5765.2     .05       0
Bank Sta=4986.1,5020.5
XS Rating Curve= 0 ,0
Exp/Cntr=0.3,0.1

Type RM Length L Ch R = 1 ,54005   ,540,540,540
BEGIN DESCRIPTION:
Cooperas Creek 56.0
END DESCRIPTION:
XS GIS Cut Line= 3
        2502125.     13829575.01        2502375.       13828775.
      2502575.01     13828424.98
#Sta/Elev= 30
  4161.6  398.78  4307.8  393.26  4448.2  386.47    4455  385.43  4570.2  382.28
    4654  381.25  4664.5  382.42  4684.2  380.84  4727.4  380.88  4737.8  380.05
  4783.4   381.6  4815.9  379.77  4848.4  379.34  4913.3  380.48  4945.8  379.05
    4951  380.48  4978.3  376.17  4983.5  377.65  4989.3  376.69  4996.1  374.21
  4996.8  373.71  5030.7  374.21  5057.4  376.97  5094.1  382.75  5128.1  385.58
    5228  391.92  5256.4  395.07  5299.2  398.06  5341.5   398.5  5402.9   399.4
#Mann= 7 ,-1 , 0
  4161.6     .05       0  4684.2      .1       0  4996.1     .05       0
  5030.7      .1       0  5128.1     .05       0  5256.4     .07       0
  5341.5     .05       0
Bank Sta=4996.1,5030.7
XS Rating Curve= 0 ,0
Exp/Cntr=0.3,0.1

Type RM Length L Ch R = 1 ,53465   ,523,523,523
BEGIN DESCRIPTION:
Cooperas Creek 55.0
END DESCRIPTION:
XS GIS Cut Line= 3
       2502645.6     13830438.79        2502775.       13829075.
      2502605.41     13828558.65
#Sta/Elev= 30
  3630.4  420.03  3855.2  414.11  3900.9  411.31  3981.3  409.33    4098   405.1
  4146.5  402.67  4166.6  402.75  4196.6  400.46    4204  399.07  4307.2   390.5
  4427.8  384.88  4638.7   380.9  4928.1   378.8    4940  379.22  4951.2  377.93
  4960.1  375.37  4962.9     371  4963.6   370.5  4997.5     371  4997.8  378.72
  5016.2  380.44  5021.5   379.7  5031.9  380.61  5085.1  381.13  5126.6  379.64
    5192  384.21  5207.1  386.14  5238.9  388.13  5366.1  394.57  5543.8  398.87
#Mann= 9 ,-1 , 0
  3630.4     .05       0  3900.9    .035       0  3981.3     .05       0
    4098    .035       0  4196.6     .05       0  4928.1      .1       0
  4962.9     .05       0  4997.5      .1       0    5192     .05       0
Bank Sta=4962.9,4997.5
XS Rating Curve= 0 ,0
Exp/Cntr=0.3,0.1

Type RM Length L Ch R = 1 ,52942   ,540,540,540
BEGIN DESCRIPTION:
Cooperas Creek 54.0
END DESCRIPTION:
XS GIS Cut Line= 3
      2503574.99     13829674.99        2503125.       13828875.
      2502675.04     13828625.02
#Sta/Elev= 30
  4077.9  397.88  4123.5  397.16  4145.1  394.16  4150.9  391.78  4158.2  391.41
  4166.8  391.47  4172.5  392.83  4210.2  392.83  4231.8  390.66  4265.2  389.64
  4422.1  382.94  4614.9  379.52  4701.6  380.91  4767.8  378.56  4812.2  376.86
  4863.5  379.49  4944.5   380.2  4966.1  378.34  4987.8     378  4992.1   368.9
  4992.8   368.4  5026.8   368.9  5031.2  378.93    5085  377.93  5106.7  380.38
  5137.3  380.62  5193.7  380.12  5247.4  380.73  5361.8  389.12  5510.5   395.6
#Mann= 6 ,-1 , 0
  4077.9    .035       0  4265.2     .05       0  4767.8      .1       0
  4992.1     .05       0  5026.8      .1       0  5137.3     .05       0
Bank Sta=4992.1,5026.8
XS Rating Curve= 0 ,0
Exp/Cntr=0.3,0.1

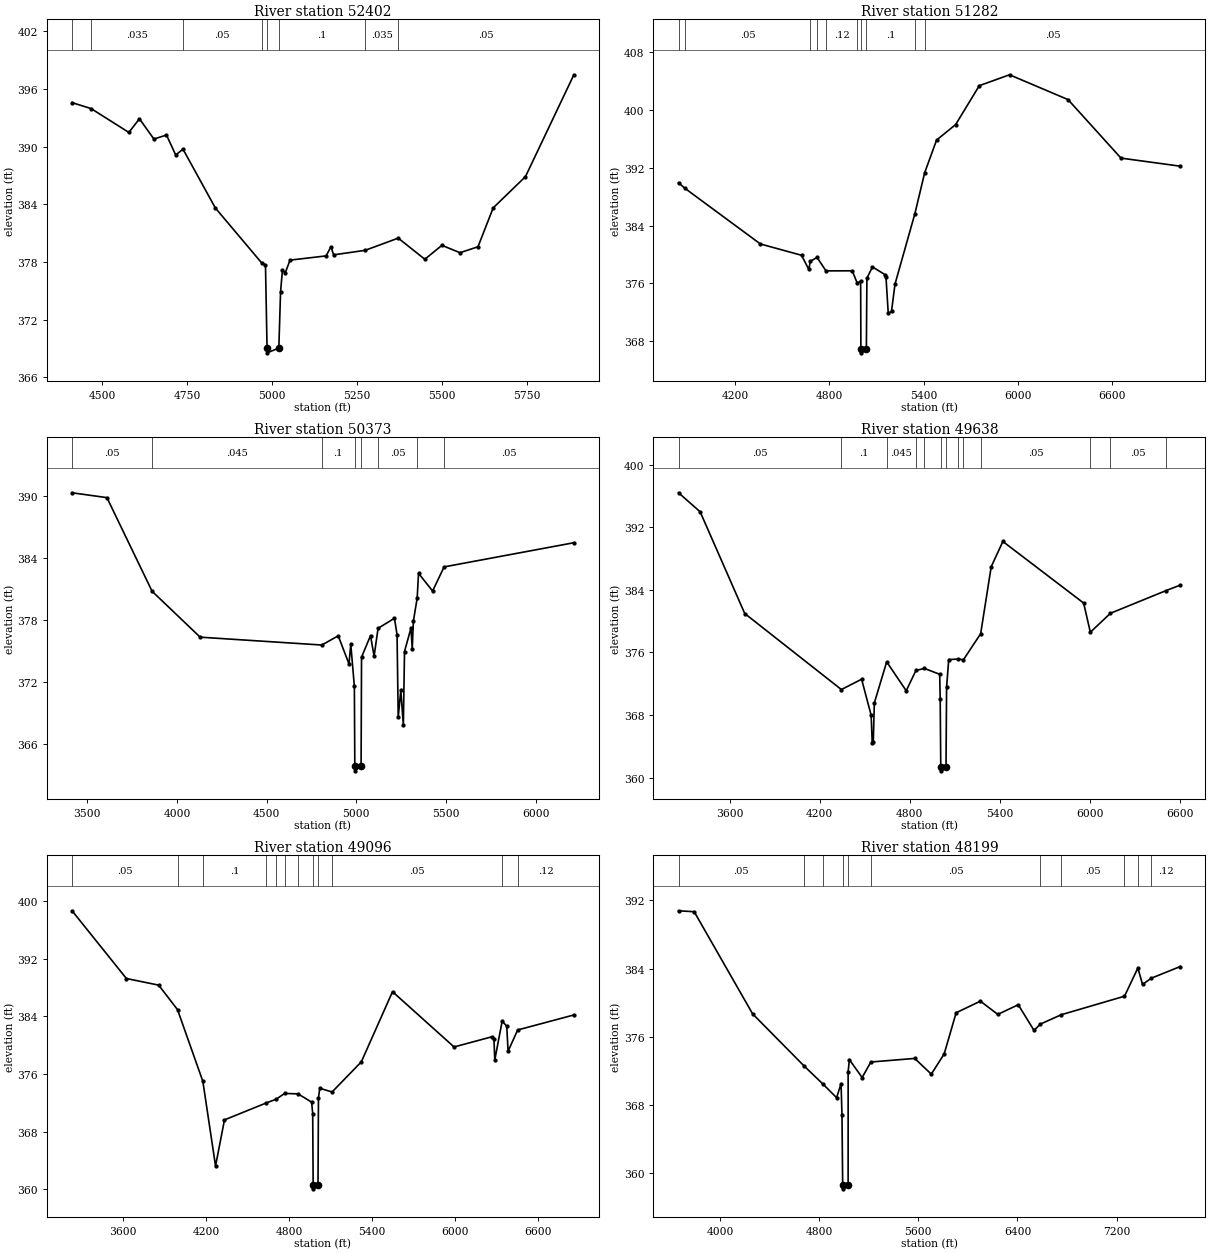
Type RM Length L Ch R = 1 ,52402   ,1120,1120,1120
BEGIN DESCRIPTION:
Cooperas Creek 53.0
END DESCRIPTION:
XS GIS Cut Line= 3
      2503825.01     13829325.01        2503525.       13828825.
      2502725.03     13828425.02
#Sta/Elev= 30
  4411.8  394.58  4467.9  393.96    4579  391.48  4610.1   392.9  4652.8  390.79
  4689.8  391.21    4717  389.13  4738.4  389.74  4833.6  383.62  4969.8  377.91
  4981.3  377.68  4985.9  369.04  4986.6  368.54  5020.6  369.04  5025.7  374.88
  5031.2  377.15  5039.6  376.87  5053.6  378.19  5159.8  378.63  5173.8  379.57
  5182.2  378.74  5274.9  379.21  5372.2  380.48  5450.5  378.28  5500.8  379.73
  5553.9  378.96    5607  379.58  5651.8  383.63  5746.8  386.88  5889.3  397.48
#Mann= 8 ,-1 , 0
  4411.8     .05       0  4467.9    .035       0  4738.4     .05       0
  4969.8      .1       0  4985.9     .05       0  5020.6      .1       0
  5274.9    .035       0  5372.2     .05       0
Bank Sta=4985.9,5020.6
XS Rating Curve= 0 ,0
Exp/Cntr=0.3,0.1

Type RM Length L Ch R = 1 ,51282   ,909,909,909
BEGIN DESCRIPTION:
Cooperas Creek 52.0
END DESCRIPTION:
XS GIS Cut Line= 3
      2504134.51     13829071.68        2503975.       13827925.
      2502781.02     13826269.94
#Sta/Elev= 30
  3838.2  389.94  3880.3  389.14  4359.9  381.45  4622.4  379.88  4668.5  377.92
  4678.2  379.03  4721.1  379.59    4778  377.72  4945.4  377.73  4977.4  376.02
    4999  376.29  5000.6  366.86  5001.3  366.36  5035.4  366.86  5038.9  376.71
  5074.4  378.27  5154.2   377.2  5160.3  376.93    5175  371.82  5195.9  372.13
  5217.9  375.88  5344.5  385.63  5407.1  391.32    5483  395.85  5604.5     398
  5755.4  403.39    5948   404.9    6321  401.46  6658.4  393.35  7036.7  392.23
#Mann= 10 ,-1 , 0
  3838.2    .035       0  3880.3     .05       0  4678.2    .035       0
  4721.1     .05       0    4778     .12       0  4977.4      .1       0
  5000.6     .05       0  5035.4      .1       0  5344.5     .07       0
  5407.1     .05       0
Bank Sta=5000.6,5035.4
XS Rating Curve= 0 ,0
Exp/Cntr=0.3,0.1

Type RM Length L Ch R = 1 ,50373   ,735,735,735
BEGIN DESCRIPTION:
Cooperas Creek 51.0
END DESCRIPTION:
XS GIS Cut Line= 3
      2504337.55     13828909.34      2504364.62     13827176.73
      2503688.93     13826352.39
#Sta/Elev= 30
    3415   390.3  3609.4  389.83  3861.2  380.76  4129.4  376.31  4807.8  375.55
  4899.5  376.44  4959.5  373.72  4969.5  375.62  4989.5  371.54    4992  363.86
  4992.8  363.36    5027  363.86  5029.5  374.37  5079.5  376.46  5099.5  374.47
  5121.8  377.17  5213.2  378.14  5227.6  376.54    5234  368.55  5248.4  371.15
  5262.7   367.8  5269.2  374.92  5305.2  377.19  5312.3   375.2  5318.7  377.86
  5339.8   380.1  5347.4   382.5  5425.7  380.78    5490  383.12  6213.7  385.46
#Mann= 8 ,-1 , 0
    3415     .05       0  3861.2    .045       0  4807.8      .1       0
    4992     .05       0    5027      .1       0  5121.8     .05       0
  5339.8    .035       0    5490     .05       0
Bank Sta=4992,5027
XS Rating Curve= 0 ,0
Exp/Cntr=0.3,0.1

Type RM Length L Ch R = 1 ,49638   ,542,542,542
BEGIN DESCRIPTION:
Cooperas Creek 50.0
END DESCRIPTION:
XS GIS Cut Line= 3
      2506218.97     13828584.41        2504975.       13827375.
      2503823.21     13826256.33
#Sta/Elev= 30
  3260.7  396.39  3404.6  393.96  3701.5  380.97  4344.9  371.26  4479.5  372.58
  4543.1  367.97  4550.1  364.46  4557.2  364.57  4564.2  369.55  4646.4   374.8
  4776.4  371.11  4841.3   373.7  4897.4  373.96  4999.2  373.21  5002.7  370.02
  5006.4  361.38  5007.1  360.88  5041.4  361.38  5045.2  371.53  5059.3  375.08
  5122.4  375.17  5157.1  375.06    5272  378.39  5342.3  386.95    5420  390.17
  5957.5  382.31  6002.3  378.58  6135.9     381  6507.9  383.91  6601.3   384.6
#Mann= 13 ,-1 , 0
  3260.7     .05       0  4344.9      .1       0  4646.4    .045       0
  4841.3     .05       0  4897.4      .1       0  5006.4     .05       0
  5041.4      .1       0  5122.4     .12       0  5157.1      .1       0
    5272     .05       0  6002.3    .035       0  6135.9     .05       0
  6507.9     .12       0
Bank Sta=5006.4,5041.4
XS Rating Curve= 0 ,0
Exp/Cntr=0.3,0.1

Type RM Length L Ch R = 1 ,49096   ,897,897,897
BEGIN DESCRIPTION:
Cooperas Creek 49.0
END DESCRIPTION:
XS GIS Cut Line= 3
      2506489.71     13828354.33        2505325.       13827025.
      2503714.94      13826093.9
#Sta/Elev= 30
  3232.5  398.66  3625.2  389.26  3858.7  388.34  3994.7  384.94  4177.9  374.99
  4269.6  363.24  4334.1  369.64  4635.2  371.98  4707.9  372.51  4769.3  373.31
  4865.9  373.25  4964.3   372.1  4971.9  370.51  4975.3  360.57    4976  360.07
  5010.3  360.57  5013.6  372.67    5023  374.03    5112  373.51  5323.3  377.69
  5548.9  387.43  5993.9  379.76  6266.6  381.17  6282.1  380.87  6288.1  377.96
  6341.7  383.36  6374.6  382.64  6384.3  379.17  6453.6  382.12  6859.8   384.2
#Mann= 12 ,-1 , 0
  3232.5     .05       0  3994.7     .07       0  4177.9      .1       0
  4635.2     .05       0  4707.9    .035       0  4769.3     .05       0
  4865.9      .1       0  4975.3     .05       0  5010.3      .1       0
    5112     .05       0  6341.7    .035       0  6453.6     .12       0
Bank Sta=4975.3,5010.3
XS Rating Curve= 0 ,0
Exp/Cntr=0.3,0.1

Type RM Length L Ch R = 1 ,48199   ,777,777,777
BEGIN DESCRIPTION:
X18522
END DESCRIPTION:
XS GIS Cut Line= 3
      2506760.44     13828191.93      2506002.43     13826824.81
       2503771.1     13825729.43
#Sta/Elev= 30
  3665.2  390.78  3791.5  390.67  4263.1   378.7    4678   372.6  4832.3  370.45
  4940.7  368.88  4976.6  370.53  4984.1  366.81  4989.6   358.7  4990.6   358.2
  5033.6   358.7  5033.8  371.94  5043.7  373.34  5146.7  371.24  5216.8  373.06
  5570.9  373.48  5704.6  371.64  5808.5     374  5905.1  378.83  6100.8  380.19
  6241.3  378.64  6406.4  379.77  6533.6  376.76  6584.7   377.5  6753.4   378.6
  7263.6  380.77  7371.8  384.08    7409  382.15  7480.1  382.88  7714.1  384.25
#Mann= 11 ,-1 , 0
  3665.2     .05       0    4678     .07       0  4832.3      .1       0
  4989.6     .05       0  5033.6      .1       0  5216.8     .05       0
  6584.7     .12       0  6753.4     .05       0  7263.6     .12       0
  7371.8    .035       0  7480.1     .12       0
Bank Sta=4989.6,5033.6
XS Rating Curve= 0 ,0
Exp/Cntr=0.3,0.1

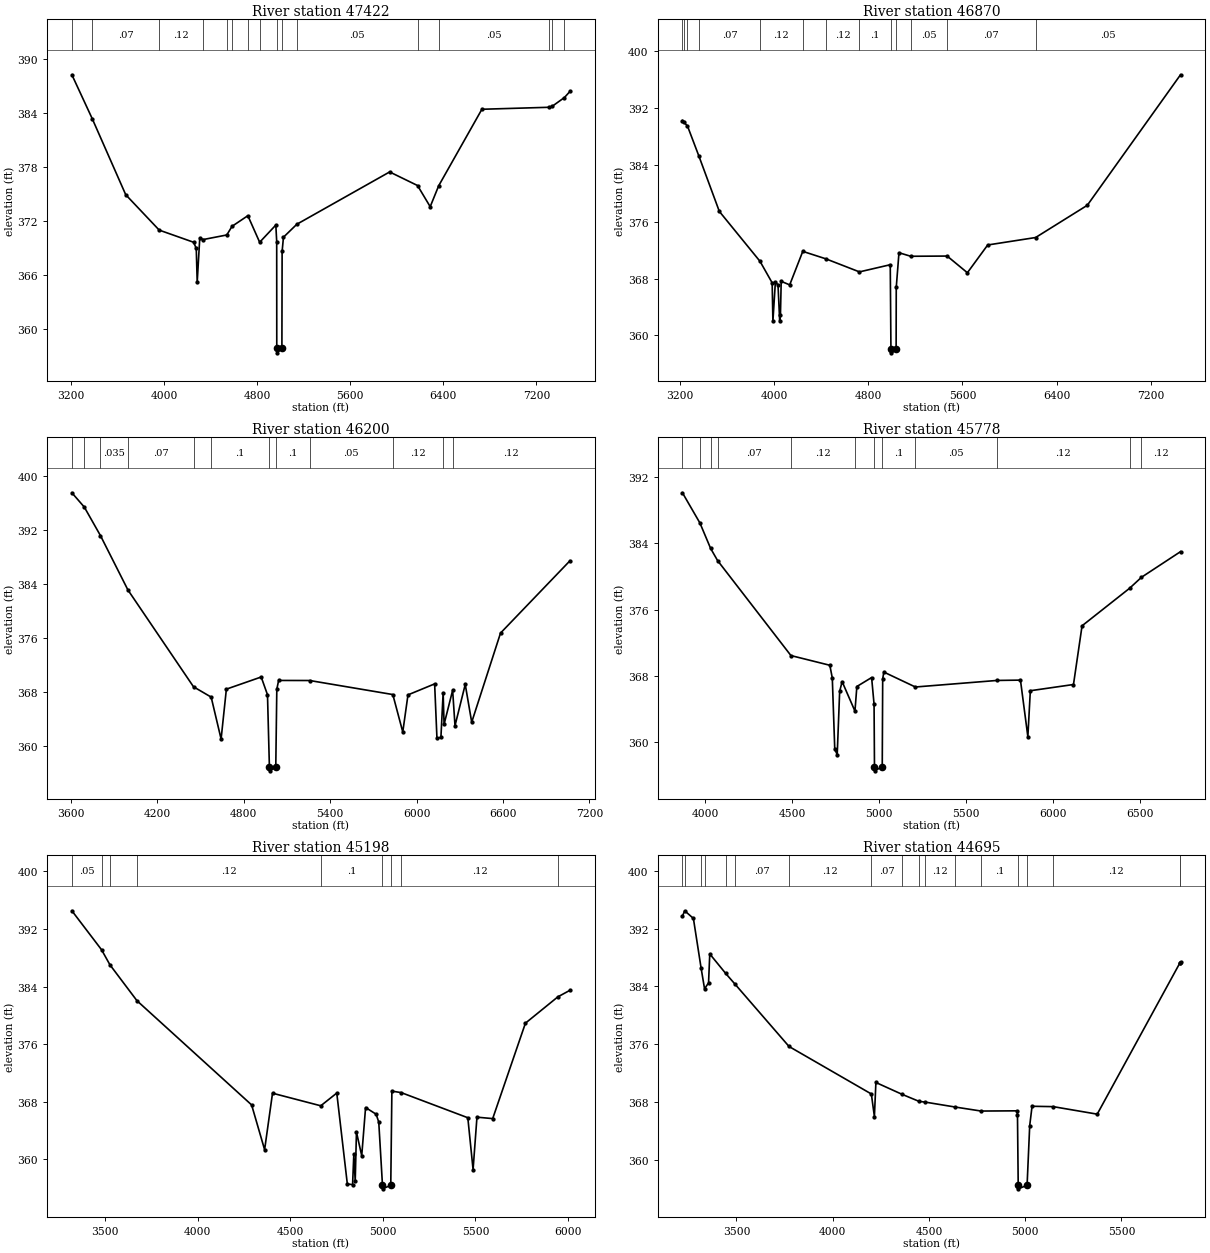
Type RM Length L Ch R = 1 ,47422   ,552,552,552
BEGIN DESCRIPTION:
Cooperas Creek 48.0
END DESCRIPTION:
XS GIS Cut Line= 3
      2507897.42     13827149.66        2506275.       13826375.
      2503945.02     13825511.85
#Sta/Elev= 30
  3206.2  388.26  3381.3  383.38  3669.2  374.94  3957.1  371.01  4252.9  369.66
  4275.6  368.98  4283.8  365.25  4305.9  370.15  4334.5  369.96  4538.3  370.47
  4583.1  371.43  4719.3  372.61  4820.8  369.66  4959.8  371.57  4967.3  369.74
  4967.9  357.88  4968.9  357.38    5012  357.88  5013.9  368.64  5025.4  370.22
  5140.4  371.66  5938.4  377.47  6178.4  375.96  6287.1  373.61  6360.4  375.94
  6731.7  384.43  7307.7  384.65  7337.1  384.77  7441.1  385.73  7488.8  386.41
#Mann= 16 ,-1 , 0
  3206.2     .12       0  3381.3     .07       0  3957.1     .12       0
  4334.5     .07       0  4538.3     .05       0  4583.1     .07       0
  4719.3     .12       0  4820.8      .1       0  4967.9     .05       0
    5012      .1       0  5140.4     .05       0  6178.4     .12       0
  6360.4     .05       0  7307.7     .07       0  7337.1    .035       0
  7441.1     .12       0
Bank Sta=4967.9,5012
XS Rating Curve= 0 ,0
Exp/Cntr=0.3,0.1

Type RM Length L Ch R = 1 ,46870   ,670,670,670
BEGIN DESCRIPTION:
Cooperas Creek 47.0
END DESCRIPTION:
XS GIS Cut Line= 3
      2507825.02     13826975.01        2506425.       13825875.
      2504189.28     13824862.42
#Sta/Elev= 30
    3219  390.26  3228.3  390.08  3261.7   389.5    3360  385.21  3532.6  377.47
  3878.4  370.44  3981.8  367.41  3988.1  361.98    4009  367.48  4031.5  367.13
  4045.7  362.08  4052.3  362.93  4058.7  367.62  4130.9  367.12  4242.1  371.84
  4436.5   370.8  4723.9  368.95  4985.9  369.96  4991.7  358.05  4992.7  357.55
  5035.8  358.05  5036.9  366.76    5060  371.65    5160  371.15  5469.6  371.18
  5641.7  368.83  5814.4  372.74  6221.7  373.79  6661.2  378.33  7453.8  396.71
#Mann= 13 ,-1 , 0
    3219     .12       0  3228.3    .035       0  3261.7     .12       0
    3360     .07       0  3878.4     .12       0  4242.1     .07       0
  4436.5     .12       0  4723.9      .1       0  4991.7     .05       0
  5035.8      .1       0    5160     .05       0  5469.6     .07       0
  6221.7     .05       0
Bank Sta=4991.7,5035.8
XS Rating Curve= 0 ,0
Exp/Cntr=0.3,0.1

Type RM Length L Ch R = 1 ,46200   ,422,422,422
BEGIN DESCRIPTION:
Cooperas Creek 46.0
END DESCRIPTION:
XS GIS Cut Line= 3
      2508075.04     13826775.03      2506909.32     13825904.38
      2505949.17     13824146.36
#Sta/Elev= 30
  3607.2  397.58  3693.4  395.46  3805.6  391.23  3996.4  383.17  4451.7  368.82
  4574.3  367.29  4643.2  361.07  4679.8  368.47  4921.6  370.27  4965.3  367.64
  4978.7  356.86  4979.7  356.36  5022.8  356.86    5030  368.45  5042.6  369.76
  5258.2  369.75  5835.5  367.67  5904.6  362.12  5940.7  367.62  6125.8  369.25
  6141.9  361.19  6169.4  361.32  6184.9  367.95  6191.3  363.25  6250.8   368.3
  6267.2  363.05  6338.3  369.17  6383.2  363.57  6583.2  376.78  7065.3   387.5
#Mann= 12 ,-1 , 0
  3607.2    .035       0  3693.4     .07       0  3805.6    .035       0
  3996.4     .07       0  4451.7     .12       0  4574.3      .1       0
  4978.7     .05       0  5022.8      .1       0  5258.2     .05       0
  5835.5     .12       0  6184.9     .07       0  6250.8     .12       0
Bank Sta=4978.7,5022.8
XS Rating Curve= 0 ,0
Exp/Cntr=0.3,0.1

Type RM Length L Ch R = 1 ,45778   ,580,580,580
BEGIN DESCRIPTION:
Cooperas Creek 45.0
END DESCRIPTION:
XS GIS Cut Line= 3
      2508074.97     13826474.97        2507275.       13825675.
      2506124.99     13824374.98
#Sta/Elev= 30
  3868.7  390.11  3969.2  386.47  4030.9   383.4  4071.1  381.93  4493.2  370.48
  4717.2  369.31  4731.3  367.77  4745.5  359.17  4759.6  358.54  4773.7  366.17
  4787.9  367.34  4861.7  363.78  4872.7  366.75  4957.6  367.83  4971.7  364.62
  4974.1  357.08  4975.1  356.58  5018.8  357.08  5021.4  367.67    5028  368.49
  5209.5  366.69  5679.6  367.48  5814.4  367.52    5857   360.7  5871.2  366.24
  6119.6  366.99    6169  374.07  6442.3  378.59    6511  379.92  6735.7  383.01
#Mann= 12 ,-1 , 0
  3868.7    .035       0  3969.2     .07       0  4030.9     .12       0
  4071.1     .07       0  4493.2     .12       0  4861.7      .1       0
  4974.1     .05       0  5018.8      .1       0  5209.5     .05       0
  5679.6     .12       0  6442.3    .035       0    6511     .12       0
Bank Sta=4974.1,5018.8
XS Rating Curve= 0 ,0
Exp/Cntr=0.3,0.1

Type RM Length L Ch R = 1 ,45198   ,503,503,503
BEGIN DESCRIPTION:
Cooperas Creek 44.0
END DESCRIPTION:
XS GIS Cut Line= 3
      2508425.02     13826325.02        2507175.       13825225.
      2506425.02     13824525.02
#Sta/Elev= 30
  3319.4  394.54  3479.8  389.12    3525  387.03  3671.1  382.04  4290.5  367.56
  4360.7  361.34  4403.4  369.19  4664.1  367.44  4750.6  369.21  4807.6  356.57
    4836  356.49  4842.7   360.7  4850.2  356.94  4856.9  363.79  4885.4   360.5
  4906.2   367.2  4963.2  366.27  4977.4  365.18  4997.5   356.4  4998.5   355.9
  5042.3   356.4  5048.3  369.48    5099  369.27  5458.6  365.78    5487  358.58
    5508  365.86    5593  365.66  5769.8  378.92  5945.1  382.58  6010.4  383.49
#Mann= 9 ,-1 , 0
  3319.4     .05       0  3479.8     .12       0    3525     .07       0
  3671.1     .12       0  4664.1      .1       0  4997.5     .05       0
  5042.3      .1       0    5099     .12       0  5945.1    .035       0
Bank Sta=4997.5,5042.3
XS Rating Curve= 0 ,0
Exp/Cntr=0.3,0.1

Type RM Length L Ch R = 1 ,44695   ,540,540,540
BEGIN DESCRIPTION:
Cooperas Creek 43.0
END DESCRIPTION:
XS GIS Cut Line= 3
      2508475.01     13826275.01        2507375.       13824875.
      2506674.99     13824474.99
#Sta/Elev= 30
  3219.8  393.73  3231.5  394.47  3276.7  393.41  3316.5  386.58  3334.6  383.68
  3355.4   384.5  3361.7   388.5  3444.5   385.8  3492.9  384.32  3773.4   375.7
  4200.9  369.13  4216.7  366.01  4224.5  370.72  4361.4  369.07  4448.5  368.11
    4482     368    4635  367.33  4770.7  366.77  4957.8   366.8  4959.8  366.18
  4963.6  356.51  4964.6  356.01  5009.7  356.51  5023.3  364.76  5035.5  367.43
  5145.1  367.38  5373.9  366.34  5801.8  387.18  5802.3  387.23  5806.5  387.35
#Mann= 18 ,-1 , 0
  3219.8     .07       0  3231.5     .05       0  3316.5     .07       0
  3334.6     .05       0  3444.5     .12       0  3492.9     .07       0
  3773.4     .12       0  4200.9     .07       0  4361.4     .12       0
  4448.5     .07       0    4482     .12       0    4635     .07       0
  4770.7      .1       0  4963.6     .05       0  5009.7      .1       0
  5145.1     .12       0  5801.8    .035       0  5802.3     .05       0
Bank Sta=4963.6,5009.7
XS Rating Curve= 0 ,0
Exp/Cntr=0.3,0.1

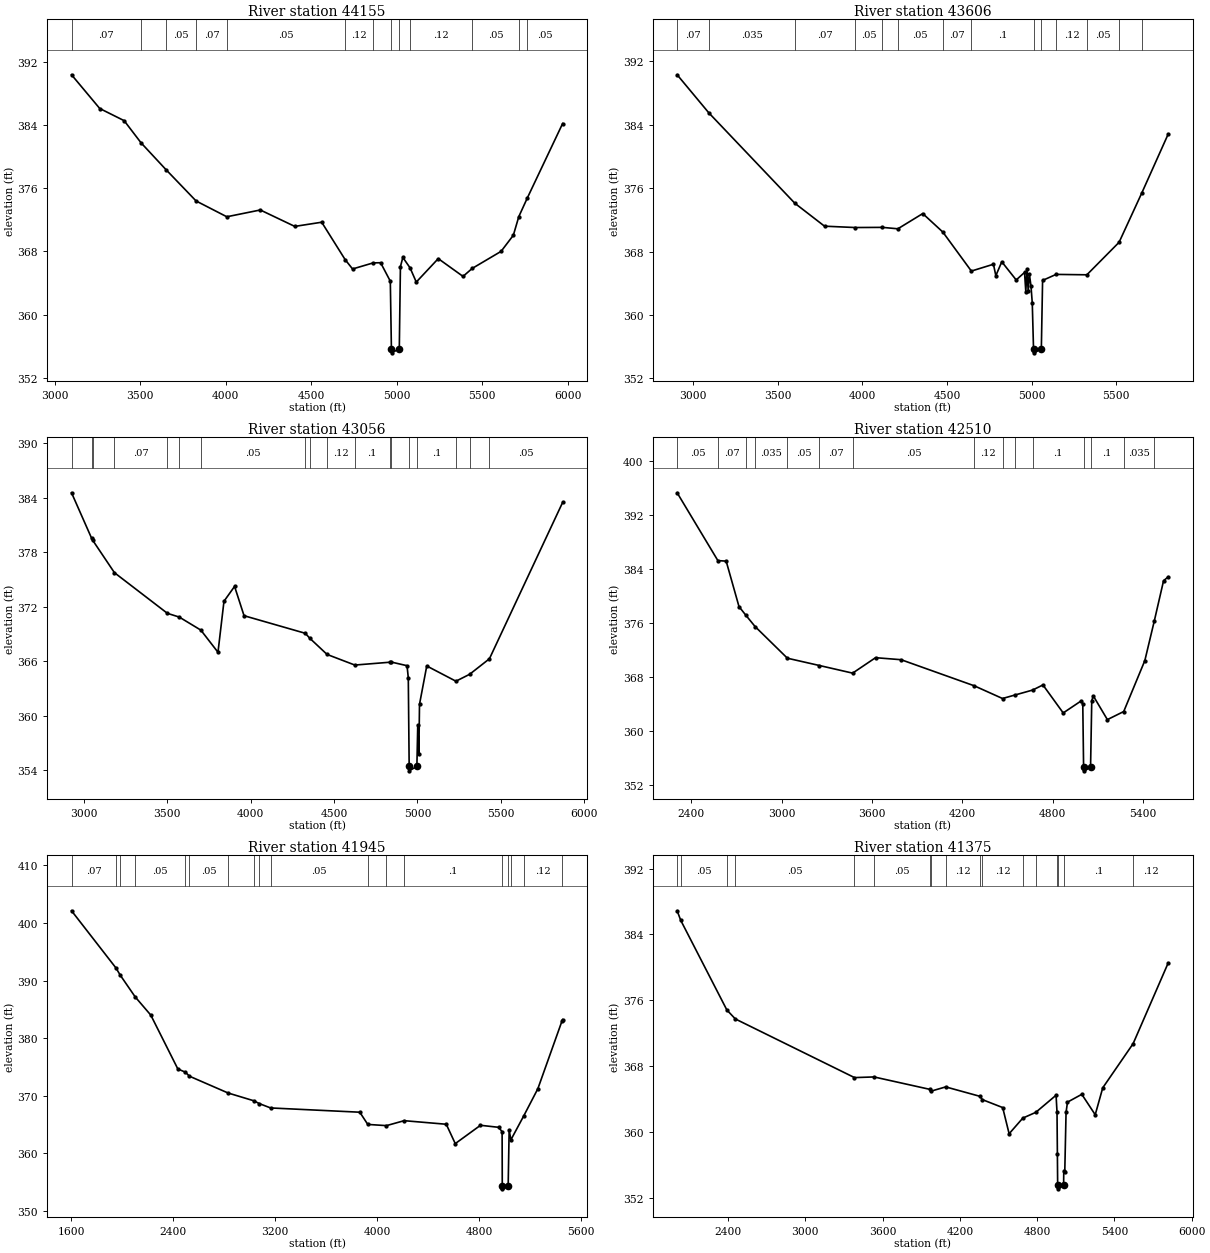
Type RM Length L Ch R = 1 ,44155   ,549,549,549
BEGIN DESCRIPTION:
Cooperas Creek 42.0
END DESCRIPTION:
XS GIS Cut Line= 3
      2509275.04     13825575.03        2507725.       13824475.
      2506925.02     13823925.02
#Sta/Elev= 30
  3099.3  390.36  3264.2  386.09  3406.9  384.55  3505.9  381.74  3651.9  378.34
  3827.6  374.38  4007.2  372.38    4203  373.24  4404.6  371.16    4562  371.69
  4699.5  366.94  4742.5  365.77  4863.1  366.54  4906.5  366.56  4963.2  364.22
  4969.6  355.65  4970.6  355.15  5015.7  355.65  5022.3  366.06  5036.4  367.23
  5078.7  365.91    5115  364.11  5243.5  367.08  5388.3  364.83  5442.1  365.84
  5610.9     368  5682.6  370.04  5714.3  372.39  5763.2  374.71  5970.8  384.19
#Mann= 13 ,-1 , 0
  3099.3     .07       0  3505.9    .035       0  3651.9     .05       0
  3827.6     .07       0  4007.2     .05       0  4699.5     .12       0
  4863.1      .1       0  4969.6     .05       0  5015.7      .1       0
  5078.7     .12       0  5442.1     .05       0  5714.3    .035       0
  5763.2     .05       0
Bank Sta=4969.6,5015.7
XS Rating Curve= 0 ,0
Exp/Cntr=0.3,0.1

Type RM Length L Ch R = 1 ,43606   ,550,550,550
BEGIN DESCRIPTION:
Cooperas Creek 41.0
END DESCRIPTION:
XS GIS Cut Line= 3
      2509325.04     13825425.03        2507775.       13824025.
      2506975.05     13823875.01
#Sta/Elev= 30
  2905.6  390.29  3092.8  385.49  3601.3  374.09  3776.6   371.2  3958.1  371.03
    4119  371.05  4210.1  370.87  4357.2  372.79  4475.9  370.46  4644.5  365.54
    4775   366.4  4789.2  364.96  4824.3  366.71  4909.5  364.42  4958.8  365.37
  4966.3  362.94    4973  365.75  4980.5  362.97  4987.2  365.17  4996.9  363.67
  5004.5  361.51  5011.9  355.73  5012.9  355.23  5058.1  355.73  5065.5  364.36
  5145.1  365.12  5327.2  365.07  5517.6  369.17  5652.3  375.41  5808.2  382.83
#Mann= 14 ,-1 , 0
  2905.6     .07       0  3092.8    .035       0  3601.3     .07       0
  3958.1     .05       0    4119     .12       0  4210.1     .05       0
  4475.9     .07       0  4644.5      .1       0  5011.9     .05       0
  5058.1      .1       0  5145.1     .12       0  5327.2     .05       0
  5517.6    .035       0  5652.3     .05       0
Bank Sta=5011.9,5058.1
XS Rating Curve= 0 ,0
Exp/Cntr=0.3,0.1

Type RM Length L Ch R = 1 ,43056   ,546,546,546
BEGIN DESCRIPTION:
Cooperas Creek 40.0
END DESCRIPTION:
XS GIS Cut Line= 3
      2509324.96     13824924.97        2507775.       13823525.
      2506975.01       13823225.
#Sta/Elev= 30
    2927  384.56    3047  379.56    3054  379.32  3184.2  375.75  3501.6  371.27
  3572.5  370.86    3702  369.42  3804.6  366.98  3840.5   372.6    3904  374.24
  3960.8  371.01  4328.1  369.07  4353.8  368.54  4458.4  366.74  4624.8  365.57
  4833.1  365.88  4838.5  365.92  4937.5   365.5    4945  364.18  4950.3  354.41
  4951.3  353.91  4996.5  354.41  5001.8  358.99  5008.5  355.82  5012.2  361.24
  5055.7  365.47  5230.5  363.79  5312.4  364.55  5431.1  366.26    5870   383.5
#Mann= 18 ,-1 , 0
    2927    .035       0    3047     .05       0    3054    .035       0
  3184.2     .07       0  3501.6     .12       0  3572.5     .07       0
    3702     .05       0  4328.1     .07       0  4353.8     .05       0
  4458.4     .12       0  4624.8      .1       0  4833.1     .12       0
  4838.5      .1       0  4950.3     .05       0  4996.5      .1       0
  5230.5     .12       0  5312.4    .035       0  5431.1     .05       0
Bank Sta=4950.3,4996.5
XS Rating Curve= 0 ,0
Exp/Cntr=0.3,0.1

Type RM Length L Ch R = 1 ,42510   ,565,565,565
BEGIN DESCRIPTION:
Cooperas Creek 39.0
END DESCRIPTION:
XS GIS Cut Line= 3
        2509775.       13824825.        2507775.       13823025.
      2507225.01       13822875.
#Sta/Elev= 30
  2305.4  395.36  2575.8  385.31  2630.9  385.23  2716.1  378.49  2761.3  377.22
  2822.7  375.54  3037.5  370.84  3250.1  369.76  3470.5  368.63  3622.7  370.92
  3792.4  370.62  4277.3  366.76  4465.7  364.87  4550.3   365.4  4665.3  366.12
  4734.2  366.88  4868.7  362.73    4989  364.53  4998.7     364  5004.1  354.65
  5005.1  354.15  5050.3  354.65  5058.3  364.56  5068.7  365.25    5162  361.74
  5270.5  362.94  5410.7  370.49  5473.2  376.33  5535.1  382.33  5566.2   382.9
#Mann= 15 ,-1 , 0
  2305.4     .05       0  2575.8     .07       0  2761.3     .05       0
  2822.7    .035       0  3037.5     .05       0  3250.1     .07       0
  3470.5     .05       0  4277.3     .12       0  4465.7      .1       0
  4550.3     .12       0  4665.3      .1       0  5004.1     .05       0
  5050.3      .1       0  5270.5    .035       0  5473.2     .07       0
Bank Sta=5004.1,5050.3
XS Rating Curve= 0 ,0
Exp/Cntr=0.3,0.1

Type RM Length L Ch R = 1 ,41945   ,570,570,570
BEGIN DESCRIPTION:
Cooperas Creek 38.0
END DESCRIPTION:
XS GIS Cut Line= 3
      2510074.98     13824924.98        2507675.       13822525.
      2507224.96     13822424.99
#Sta/Elev= 30
  1601.6  402.12  1950.1   392.2  1984.4  390.93  2101.4  387.17  2223.8  384.01
    2436  374.67  2495.9   374.1  2527.1  373.41    2831  370.49  3031.6  369.15
  3076.1  368.65  3164.2   367.9  3864.3  367.16    3927  365.04  4073.6  364.83
  4212.6  365.69  4543.1  365.07  4613.8  361.71  4811.8  364.89  4953.3  364.54
  4981.5  363.79  4982.8  354.36  4983.8  353.86  5029.1  354.36  5036.7  364.01
  5050.8  362.38  5151.1  366.51    5262  371.23  5451.9  383.01  5456.7  383.24
#Mann= 18 ,-1 , 0
  1601.6     .07       0  1950.1     .05       0  1984.4     .07       0
  2101.4     .05       0  2495.9    .035       0  2527.1     .05       0
    2831     .07       0  3031.6     .05       0  3076.1     .07       0
  3164.2     .05       0    3927    .035       0  4073.6     .12       0
  4212.6      .1       0  4982.8     .05       0  5029.1      .1       0
  5050.8     .07       0  5151.1     .12       0  5451.9     .07       0
Bank Sta=4982.8,5029.1
XS Rating Curve= 0 ,0
Exp/Cntr=0.3,0.1

Type RM Length L Ch R = 1 ,41375   ,554,554,554
BEGIN DESCRIPTION:
Cooperas Creek 37.0
END DESCRIPTION:
XS GIS Cut Line= 3
      2509774.99     13824524.99        2507975.       13822125.
      2507175.03       13821975.
#Sta/Elev= 30
  2004.3  386.87  2032.5   385.7  2390.5  374.82  2456.5  373.73  3381.6  366.61
  3533.2  366.69  3964.4  365.19  3972.7  364.95    4090  365.48  4357.1  364.33
  4373.9  363.94  4532.4  362.97  4582.4  359.79  4688.6  361.69  4789.5  362.39
    4947  364.47  4954.3  362.42  4957.2   357.3  4959.3   353.6  4960.3   353.1
  5005.6   353.6  5006.8  355.32  5014.5   355.1  5024.6  362.39  5035.7  363.63
  5146.7  364.58    5251   362.1  5309.5  365.37  5545.3  370.73  5818.2  380.55
#Mann= 17 ,-1 , 0
  2004.3     .07       0  2032.5     .05       0  2390.5    .035       0
  2456.5     .05       0  3381.6     .07       0  3533.2     .05       0
  3964.4     .12       0  3972.7    .035       0    4090     .12       0
  4357.1      .1       0  4373.9     .12       0  4688.6      .1       0
  4789.5     .12       0  4957.2      .1       0  4959.3     .05       0
  5005.6      .1       0  5545.3     .12       0
Bank Sta=4959.3,5005.6
XS Rating Curve= 0 ,0
Exp/Cntr=0.3,0.1