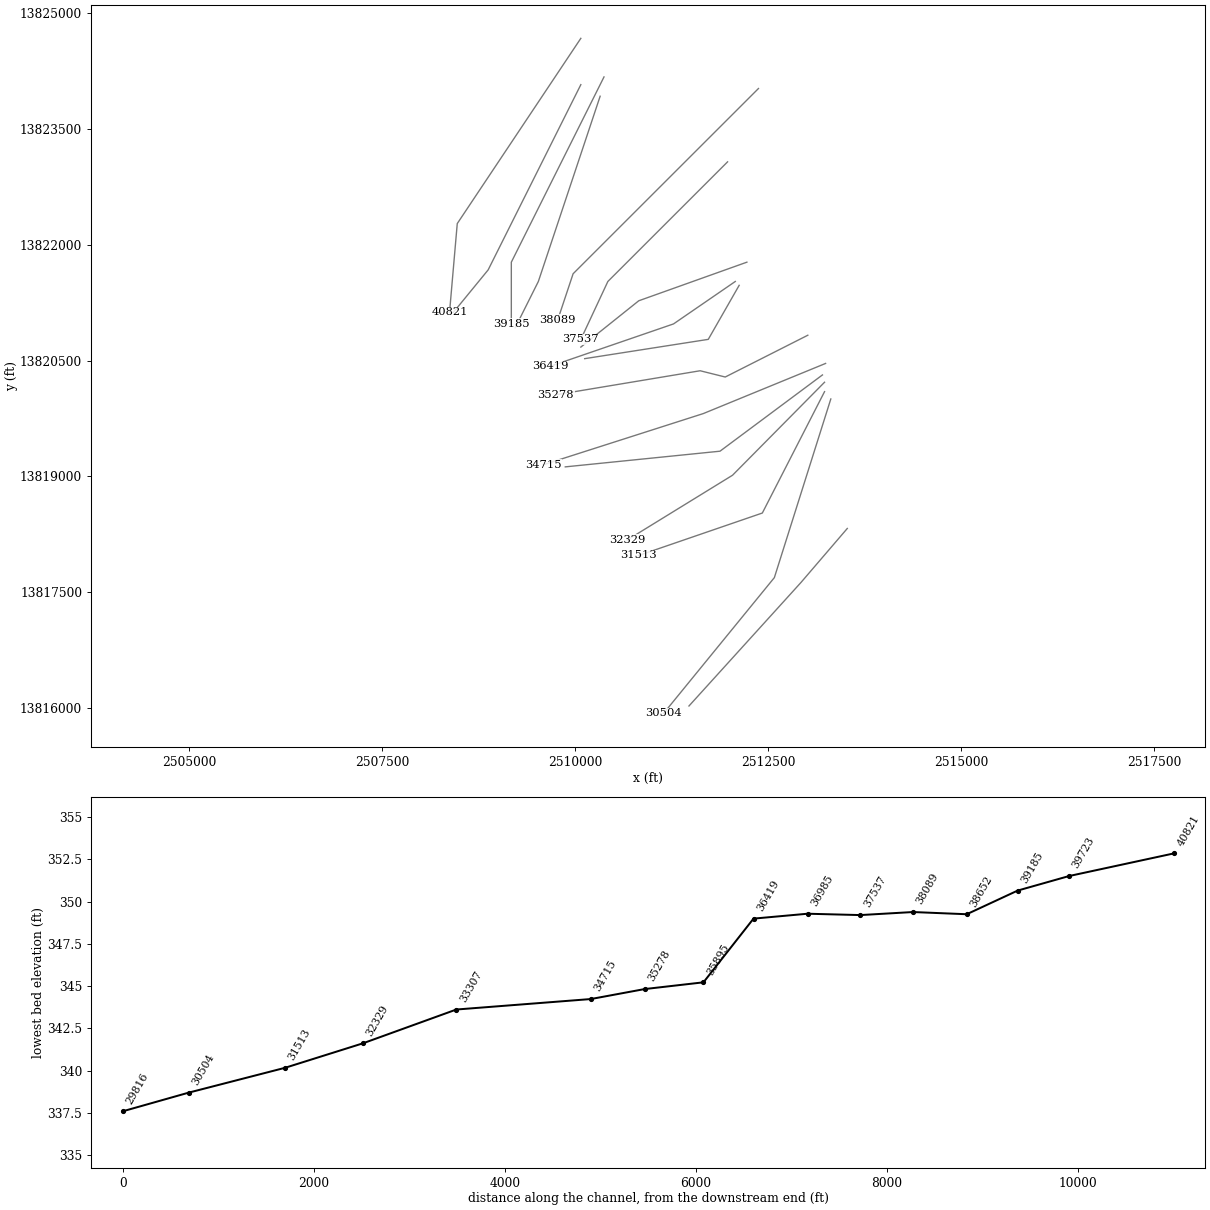
HEC-RAS study Copperas Creek.prj: Copperas Creek Base Level Engineering

--- Copperas Creek.g01 (geometry) --- (continued)

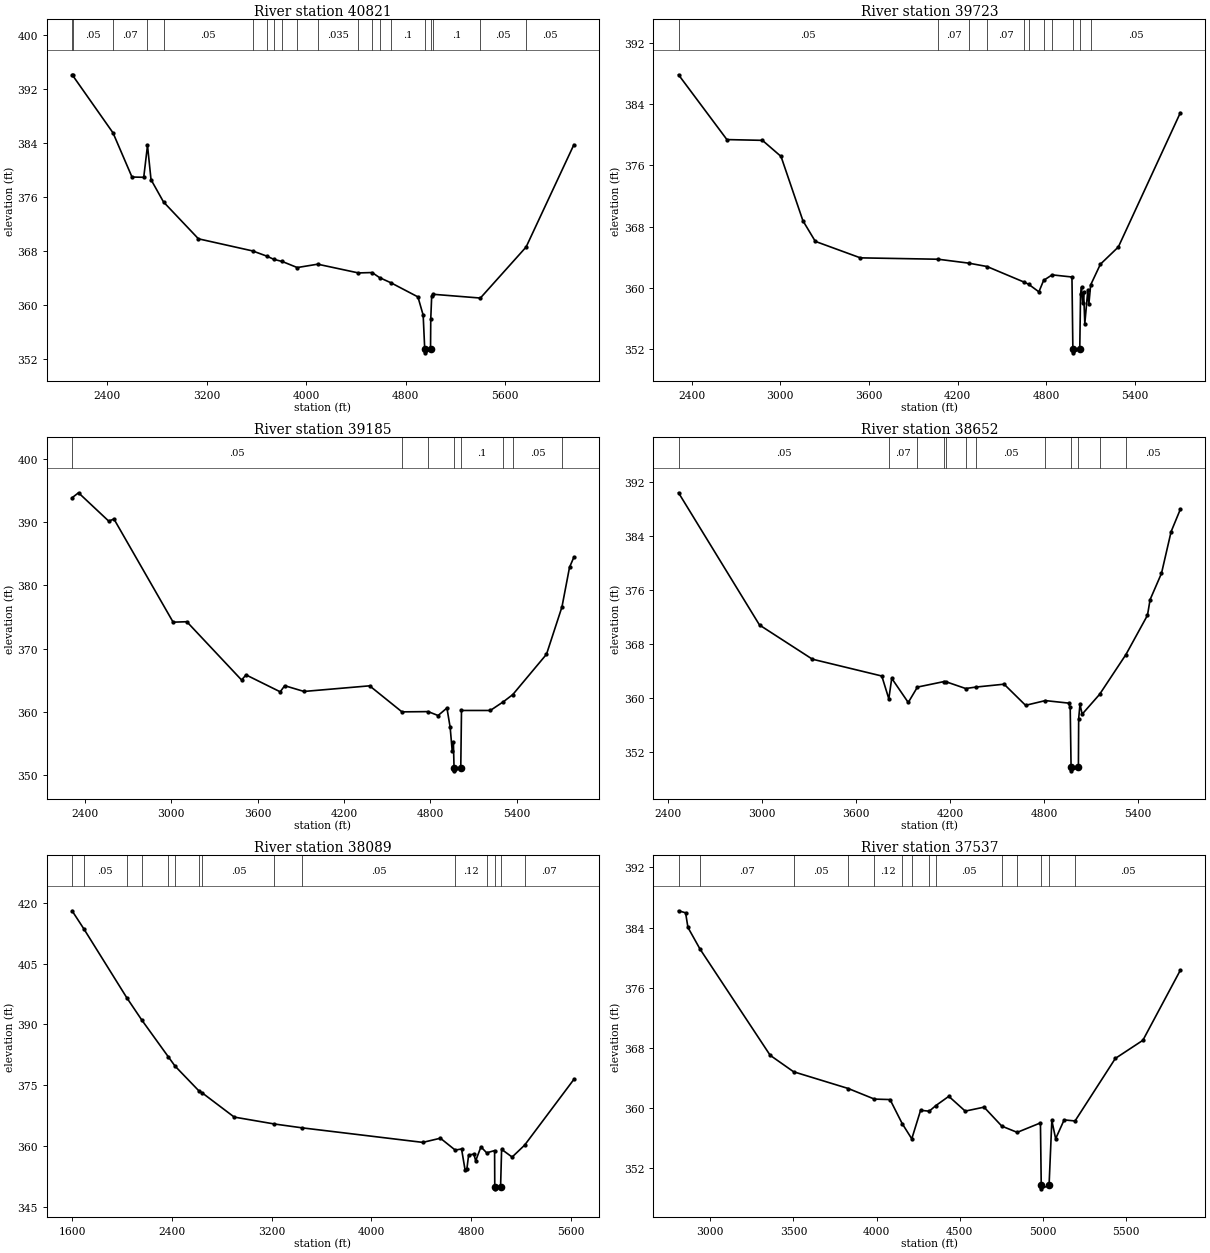
Type RM Length L Ch R = 1 ,40821   ,1098,1098,1098
BEGIN DESCRIPTION:
Cooperas Creek 36.0
END DESCRIPTION:
XS GIS Cut Line= 3
      2510075.01     13824675.01        2508475.       13822275.
        2508375.       13821125.
#Sta/Elev= 30
  2115.5  394.16    2120  394.07  2445.1  385.53  2597.8  378.97  2692.4  378.93
  2722.6  383.66    2751  378.58  2851.7  375.26  3132.6  369.79  3568.7  367.99
  3686.8  367.19  3739.1  366.74  3807.3  366.42  3927.9  365.52  4092.4  366.02
  4420.6  364.72  4530.5  364.78  4590.9  364.02    4684  363.24  4899.3  361.16
  4941.4  358.45  4954.1  353.35  4955.1  352.85  5000.7  353.35  5002.5  357.87
    5010  361.31  5020.9  361.55  5401.9  360.99  5769.9  368.57  6154.3  383.76
#Mann= 20 ,-1 , 0
  2115.5     .07       0    2120     .05       0  2445.1     .07       0
  2722.6    .035       0  2851.7     .05       0  3568.7     .05       0
  3686.8    .035       0  3739.1     .05       0  3807.3    .035       0
  3927.9    .035       0  4092.4    .035       0  4420.6    .035       0
  4530.5      .1       0  4590.9    .035       0    4684      .1       0
  4954.1    .035       0  5000.7      .1       0  5020.9      .1       0
  5401.9     .05       0  5769.9     .05       0
Bank Sta=4954.1,5000.7
XS Rating Curve= 0 ,0
Exp/Cntr=0.3,0.1

Type RM Length L Ch R = 1 ,39723   ,538,538,538
BEGIN DESCRIPTION:
Cooperas Creek 35.0
END DESCRIPTION:
XS GIS Cut Line= 3
      2510075.02     13824075.04        2508875.       13821675.
      2508424.98     13821124.97
#Sta/Elev= 30
  2311.8  387.81  2638.9  379.35  2879.2  379.25    3005  377.15  3153.2  368.75
    3237  366.06  3541.7  363.91  4067.9  363.73  4274.5  363.22  4398.2  362.78
  4648.4  360.75  4679.9  360.46  4749.2  359.47  4781.2  360.97  4838.5  361.69
  4972.8  361.41    4979  352.01    4980  351.51  5025.6  352.01    5031  359.21
  5037.5  360.06  5045.4  357.97  5051.8  359.39  5059.7  355.32  5080.5  359.76
    5087  357.83  5099.4  360.38  5165.2  363.08  5286.6  365.33  5705.8  382.85
#Mann= 11 ,-1 , 0
  2311.8     .05       0  4067.9     .07       0  4274.5     .05       0
  4398.2     .07       0  4648.4     .05       0  4679.9      .1       0
  4781.2     .05       0  4838.5      .1       0    4979     .05       0
  5025.6      .1       0  5099.4     .05       0
Bank Sta=4979,5025.6
XS Rating Curve= 0 ,0
Exp/Cntr=0.3,0.1

Type RM Length L Ch R = 1 ,39185   ,533,533,533
BEGIN DESCRIPTION:
Cooperas Creek 34.0
END DESCRIPTION:
XS GIS Cut Line= 3
      2510374.99     13824174.97        2509175.       13821775.
        2509175.     13820975.05
#Sta/Elev= 30
  2312.7  393.85  2357.4  394.64    2567  390.16  2603.4  390.49  3014.2  374.17
  3109.3  374.24  3489.4  365.02  3520.1  365.83  3757.7  363.15  3788.5  364.12
  3922.6  363.21  4378.2   364.1  4602.6  359.98  4784.9  360.02  4853.4   359.4
  4914.9  360.59  4937.3  357.52  4951.2  353.86  4959.6  355.26  4964.2  351.15
  4965.2  350.65  5010.9  351.15  5015.9   360.2  5215.9   360.2  5307.3  361.59
  5372.2  362.72  5605.9  369.09  5713.3  376.58  5765.9  382.86  5795.9  384.44
#Mann= 8 ,-1 , 0
  2312.7     .05       0  4602.6     .07       0  4784.9      .1       0
  4964.2     .05       0  5010.9      .1       0  5307.3     .07       0
  5372.2     .05       0  5713.3     .07       0
Bank Sta=4964.2,5010.9
XS Rating Curve= 0 ,0
Exp/Cntr=0.3,0.1

Type RM Length L Ch R = 1 ,38652   ,563,563,563
BEGIN DESCRIPTION:
Cooperas Creek 33.0
END DESCRIPTION:
XS GIS Cut Line= 3
      2510324.99     13823924.98        2509525.       13821525.
      2509225.01     13820925.01
#Sta/Elev= 30
  2469.7  390.42  2986.2  370.84  3323.5  365.78  3766.2  363.29    3811  359.91
  3829.5  362.95  3934.9  359.37  3993.4  361.65  4163.7  362.47  4178.1  362.42
  4301.1  361.44  4369.3  361.66  4546.2  362.08  4683.3  358.95  4809.2  359.65
  4957.3  359.28  4967.9  358.63  4973.5  349.75  4974.5  349.25  5020.2  349.75
  5021.9  356.96  5030.2  359.11  5044.2  357.64  5155.2  360.57  5323.1  366.46
  5460.7  372.28  5477.5   374.6  5550.1  378.49  5611.6  384.67  5670.3  387.97
#Mann= 12 ,-1 , 0
  2469.7     .05       0    3811     .07       0  3993.4     .05       0
  4163.7     .07       0  4178.1     .05       0  4301.1     .07       0
  4369.3     .05       0  4809.2      .1       0  4973.5     .05       0
  5020.2      .1       0  5155.2     .07       0  5323.1     .05       0
Bank Sta=4973.5,5020.2
XS Rating Curve= 0 ,0
Exp/Cntr=0.3,0.1

Type RM Length L Ch R = 1 ,38089   ,552,552,552
BEGIN DESCRIPTION:
Cooperas Creek 32.0
END DESCRIPTION:
XS GIS Cut Line= 3
      2512375.02     13824025.02        2509975.       13821625.
        2509775.       13821025.
#Sta/Elev= 30
  1599.5  418.04  1693.3  413.61  2038.5  396.57  2157.9  391.11  2370.7  382.03
  2426.1  379.68  2614.8  373.65  2645.2  373.04  2900.6   367.1  3223.3  365.39
  3443.3  364.45  4413.8  360.85  4555.2  361.88    4674  358.95  4724.9  359.22
  4753.2  354.05  4767.4  354.24  4781.5  357.69  4823.9  357.98  4838.1  356.29
  4880.5  359.75  4926.6  358.27  4990.1  358.83  4991.4  349.88  4992.4  349.38
  5038.1  349.88  5046.3  359.13  5130.7  357.23  5230.7  360.16  5626.1   376.4
#Mann= 15 ,-1 , 0
  1599.5    .035       0  1693.3     .05       0  2038.5    .035       0
  2157.9     .05       0  2370.7    .035       0  2426.1     .05       0
  2614.8    .035       0  2645.2     .05       0  3223.3     .07       0
  3443.3     .05       0    4674     .12       0  4926.6      .1       0
  4991.4     .05       0  5038.1      .1       0  5230.7     .07       0
Bank Sta=4991.4,5038.1
XS Rating Curve= 0 ,0
Exp/Cntr=0.3,0.1

Type RM Length L Ch R = 1 ,37537   ,552,552,552
BEGIN DESCRIPTION:
Cooperas Creek 31.0
END DESCRIPTION:
XS GIS Cut Line= 3
      2511975.02     13823075.02        2510425.       13821525.
      2510075.01     13820775.01
#Sta/Elev= 30
  2808.4  386.23  2850.9  385.96    2865  384.01    2938  381.12    3360  366.98
  3500.9  364.79    3830  362.56  3987.3  361.15  4081.2  361.09  4154.3  357.89
    4212  355.86  4265.1  359.66    4317  359.54    4357  360.29  4434.8  361.52
  4533.8  359.55  4646.9  360.08  4753.9  357.55  4846.5  356.72  4986.3  357.98
  4991.1   349.7  4992.1   349.2  5038.3   349.7  5054.9  358.31  5077.7  355.87
  5128.9  358.38  5194.5  358.24  5437.1  366.57  5602.7  368.98  5828.1  378.31
#Mann= 14 ,-1 , 0
  2808.4     .05       0    2938     .07       0  3500.9     .05       0
    3830     .07       0  3987.3     .12       0  4154.3     .07       0
    4212     .05       0    4317     .12       0    4357     .05       0
  4753.9     .12       0  4846.5      .1       0  4991.1     .05       0
  5038.3      .1       0  5194.5     .05       0
Bank Sta=4991.1,5038.3
XS Rating Curve= 0 ,0
Exp/Cntr=0.3,0.1

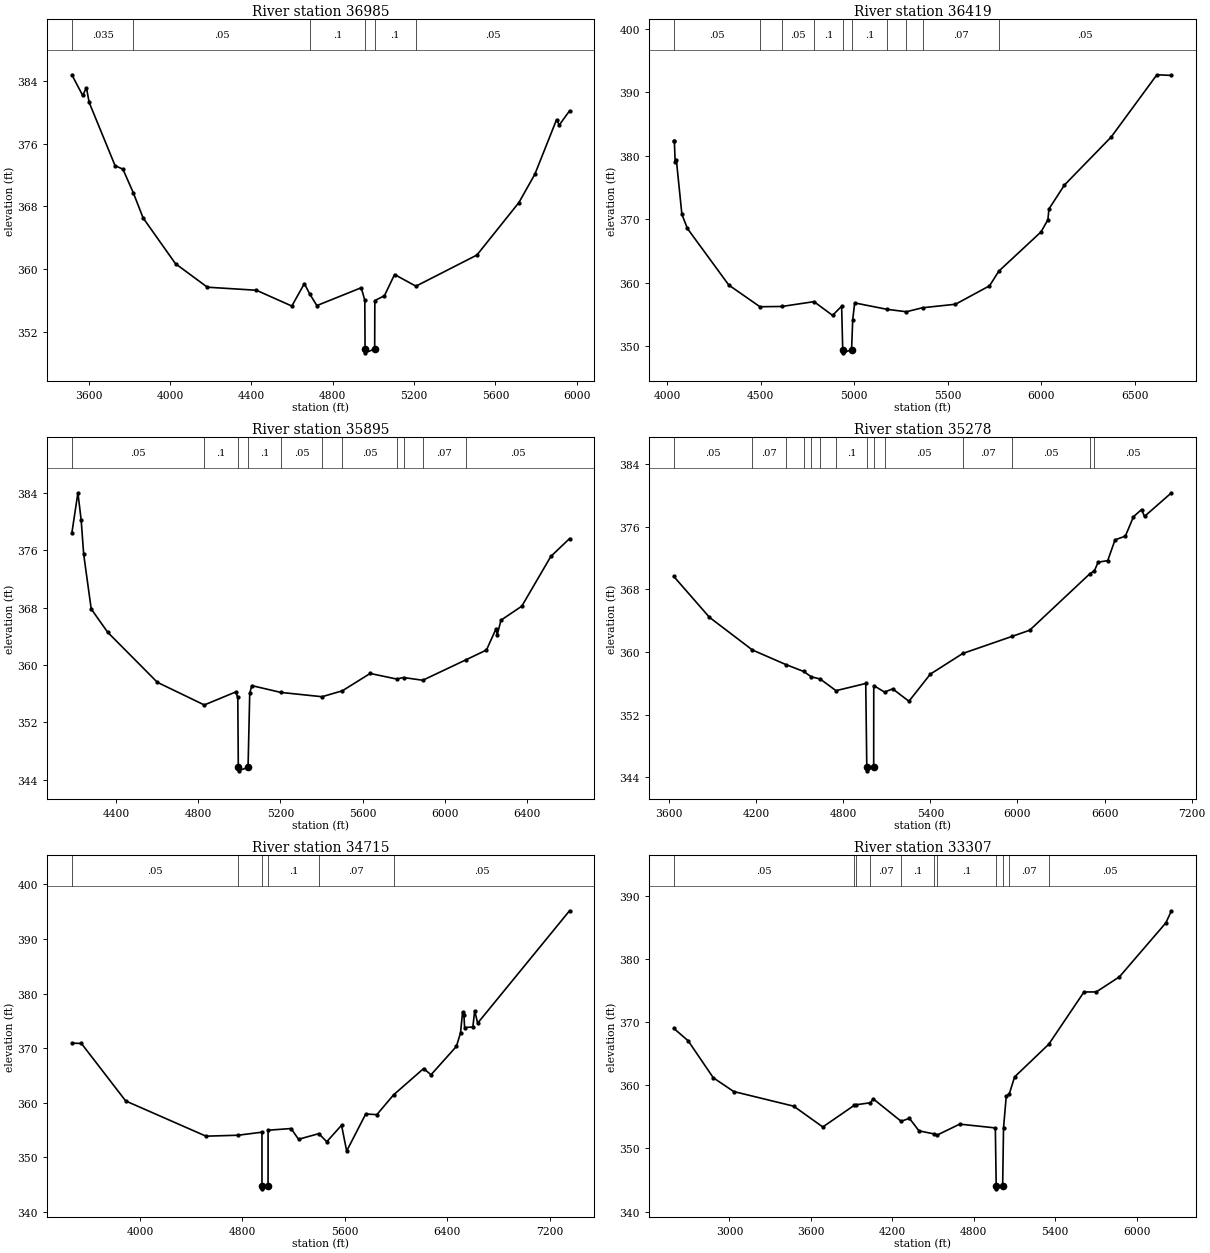
Type RM Length L Ch R = 1 ,36985   ,566,566,566
BEGIN DESCRIPTION:
Cooperas Creek 30.0
END DESCRIPTION:
XS GIS Cut Line= 3
      2512225.01       13821775.        2510825.       13821275.
      2510074.99     13820674.99
#Sta/Elev= 30
  3517.3  384.82  3570.4  382.18    3589  383.16  3602.3  381.29  3729.7  373.21
  3768.4  372.75  3818.9  369.77  3867.7  366.52    4027  360.67  4183.6  357.67
  4424.7  357.28  4598.8  355.26  4660.4  358.12  4687.9  356.76    4722  355.32
  4940.2   357.6  4957.7     356    4959  349.78    4960  349.28  5006.3  349.78
  5007.1  355.96  5054.3  356.58    5104  359.29  5209.1   357.8    5509  361.78
  5715.5  368.49  5793.9  372.11  5900.4  379.07    5914   378.4  5964.4  380.21
#Mann= 6 ,-1 , 0
  3517.3    .035       0  3818.9     .05       0  4687.9      .1       0
    4959     .05       0  5006.3      .1       0  5209.1     .05       0
Bank Sta=4959,5006.3
XS Rating Curve= 0 ,0
Exp/Cntr=0.3,0.1

Type RM Length L Ch R = 1 ,36419   ,524,524,524
BEGIN DESCRIPTION:
Cooperas Creek 29.0
END DESCRIPTION:
XS GIS Cut Line= 3
      2512074.99     13821524.99        2511275.       13820975.
        2509675.       13820425.
#Sta/Elev= 30
  4034.8  382.35  4037.8  382.35  4042.2  379.02  4048.3  379.42  4078.1   370.8
  4107.6  368.57  4329.1  359.66  4495.7  356.25    4613  356.29  4784.8  357.05
  4884.3  354.89  4932.8  356.33  4938.6  349.49  4939.6  348.99    4986  349.49
  4992.1  354.21  5002.6  356.85    5176  355.84  5279.1  355.46  5365.6  356.09
  5541.8  356.64  5723.9  359.54    5774  361.86  5999.6  368.03  6036.4  369.94
  6041.9  371.64  6124.8  375.41  6374.7  382.96  6619.4  392.77  6697.5  392.67
#Mann= 10 ,-1 , 0
  4034.8     .05       0  4495.7     .07       0    4613     .05       0
  4784.8      .1       0  4938.6     .05       0    4986      .1       0
    5176     .05       0  5279.1      .1       0  5365.6     .07       0
    5774     .05       0
Bank Sta=4938.6,4986
XS Rating Curve= 0 ,0
Exp/Cntr=0.3,0.1

Type RM Length L Ch R = 1 ,35895   ,617,617,617
BEGIN DESCRIPTION:
Cooperas Creek 28.0
END DESCRIPTION:
XS GIS Cut Line= 3
      2512125.01     13821475.02        2511725.       13820775.
      2510124.97     13820524.99
#Sta/Elev= 30
  4183.4  378.43  4212.9  384.05  4228.8  380.23    4241  375.46  4277.7  367.83
  4358.3  364.56  4600.2  357.58  4828.9  354.42  4981.7  356.23  4992.2  355.49
  4994.7  345.72  4995.7  345.22  5042.2  345.72  5050.4  356.06  5060.5  357.12
  5202.3  356.17  5402.8  355.57  5502.1   356.4  5637.4  358.82  5766.3  358.04
  5799.9  358.25  5893.7  357.87  6103.9  360.72  6204.2  362.09  6251.3  365.08
  6256.3  364.18  6275.1  366.26  6376.3  368.21    6518  375.16  6609.1  377.65
#Mann= 11 ,-1 , 0
  4183.4     .05       0  4828.9      .1       0  4994.7     .05       0
  5042.2      .1       0  5202.3     .05       0  5402.8     .07       0
  5502.1     .05       0  5766.3     .07       0  5799.9     .05       0
  5893.7     .07       0  6103.9     .05       0
Bank Sta=4994.7,5042.2
XS Rating Curve= 0 ,0
Exp/Cntr=0.3,0.1

Type RM Length L Ch R = 1 ,35278   ,563,563,563
BEGIN DESCRIPTION:
X18521
END DESCRIPTION:
XS GIS Cut Line= 4
      2513013.86      13820828.5      2511944.58     13820287.09
      2511619.72     13820368.31      2509751.78     13820056.98
#Sta/Elev= 30
  3633.4  369.65    3879  364.43  4174.6  360.26    4406  358.39  4528.5  357.51
  4580.3  356.83  4641.6  356.55  4750.5  355.06  4955.2  355.98  4962.4  345.32
  4963.4  344.82  5009.9  345.32  5010.4  355.71  5084.7  354.88  5140.7  355.29
  5252.7  353.71  5399.7  357.17    5623  359.81  5963.6     362    6084  362.78
  6498.2  369.99    6530  370.38  6555.5  371.48  6621.4  371.67    6672  374.33
    6743   374.8  6798.8  377.28  6854.5   378.2  6874.8  377.32  7060.5  380.34
#Mann= 14 ,-1 , 0
  3633.4     .05       0  4174.6     .07       0    4406     .05       0
  4528.5     .07       0  4580.3     .05       0  4641.6     .07       0
  4750.5      .1       0  4962.4     .05       0  5009.9      .1       0
  5084.7     .05       0    5623     .07       0  5963.6     .05       0
  6498.2     .07       0    6530     .05       0
Bank Sta=4962.4,5009.9
XS Rating Curve= 0 ,0
Exp/Cntr=0.3,0.1

Type RM Length L Ch R = 1 ,34715   ,1408,1408,1408
BEGIN DESCRIPTION:
X18520
END DESCRIPTION:
XS GIS Cut Line= 3
      2513243.98     13820463.05      2511660.33     13819813.35
      2509589.67     13819150.19
#Sta/Elev= 30
  3468.6  370.93  3543.2  370.86    3889  360.33    4516  353.88    4766  354.05
  4952.9  354.61  4953.1  344.73  4954.1  344.23  5000.6  344.73  5000.8  354.97
  5180.3  355.28  5238.4  353.31  5396.9  354.34  5458.9  352.86  5574.4  355.88
  5614.4  351.16  5763.5  357.95  5849.9  357.82  5981.2  361.46    6215  366.26
    6273  365.13  6471.1  370.32  6503.3  372.78  6519.5  376.62    6530  376.01
  6535.4  373.78  6599.7  373.88    6614  376.87  6637.1  374.58  7354.6  395.17
#Mann= 6 ,-1 , 0
  3468.6     .05       0    4766      .1       0  4953.1     .05       0
  5000.6      .1       0  5396.9     .07       0  5981.2     .05       0
Bank Sta=4953.1,5000.6
XS Rating Curve= 0 ,0
Exp/Cntr=0.3,0.1

Type RM Length L Ch R = 1 ,33307   ,978,978,978
BEGIN DESCRIPTION:
X18519
END DESCRIPTION:
XS GIS Cut Line= 3
      2513203.37     13820314.15       2511876.9     13819326.06
       2509873.6     13819123.03
#Sta/Elev= 30
  2589.8     369  2695.5  367.04  2881.1  361.18  3031.2  359.01  3473.3  356.69
  3688.1   353.4  3917.8   356.8  3929.2   356.9  4038.1  357.23  4059.3  357.85
  4265.1   354.3  4326.2  354.77  4396.5  352.79  4507.2   352.3    4532  352.13
  4696.8  353.85  4959.4  353.25  4965.7  344.11  4966.7  343.61  5013.4  344.11
  5019.7  353.22  5039.8  358.25  5062.2  358.63  5101.2  361.32  5353.1  366.49
  5612.7  374.76  5703.2  374.77    5874  377.16  6215.8  385.69  6257.4  387.61
#Mann= 11 ,-1 , 0
  2589.8     .05       0  3917.8     .07       0  3929.2     .05       0
  4038.1     .07       0  4265.1      .1       0  4507.2     .05       0
    4532      .1       0  4965.7     .05       0  5013.4      .1       0
  5062.2     .07       0  5353.1     .05       0
Bank Sta=4965.7,5013.4
XS Rating Curve= 0 ,0
Exp/Cntr=0.3,0.1

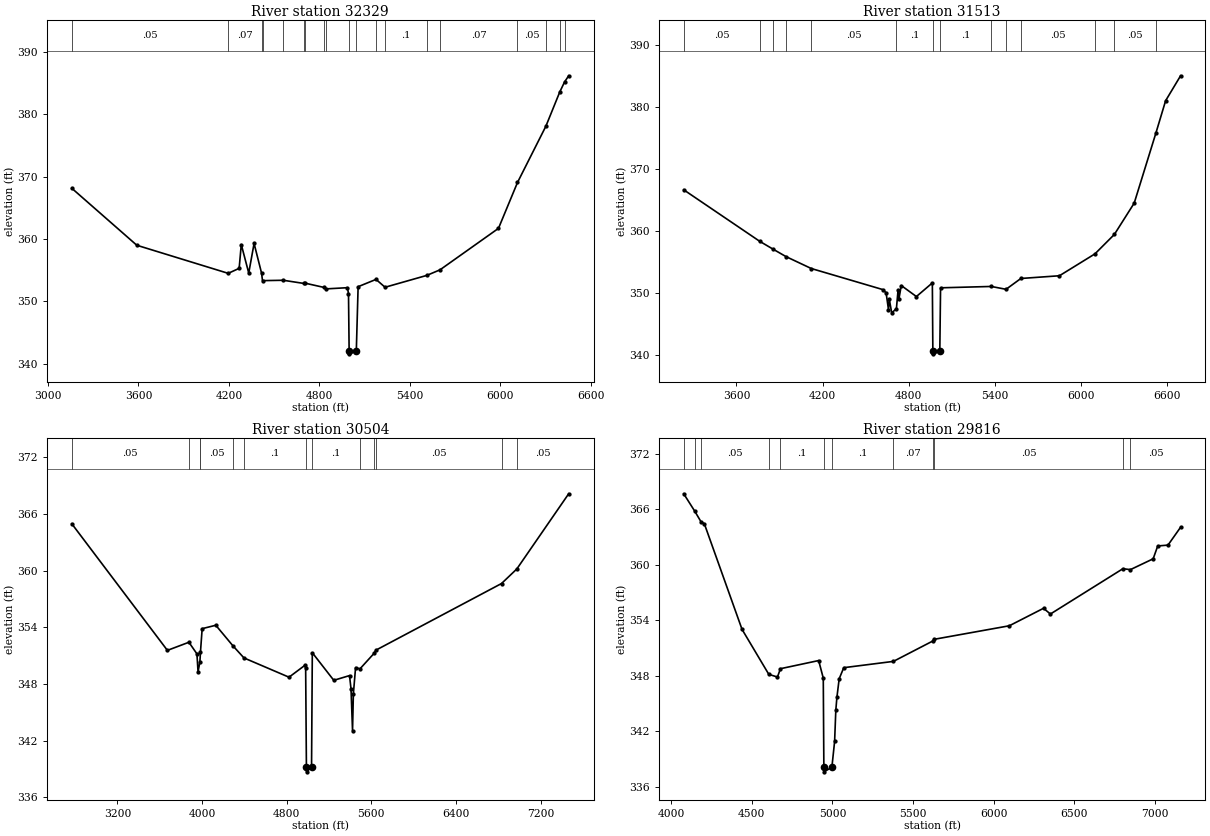
Type RM Length L Ch R = 1 ,32329   ,816,816,816
BEGIN DESCRIPTION:
Cooperas Creek 27.0
END DESCRIPTION:
XS GIS Cut Line= 3
      2513230.46     13820219.41      2512039.33     13819014.74
      2510674.96     13818174.98
#Sta/Elev= 30
  3158.2  368.14  3589.4  359.01  4195.7  354.51  4268.3  355.31  4282.4  359.13
  4331.9  354.56  4367.3   359.3  4416.9  354.55  4423.2  353.34  4560.8   353.4
  4695.6   352.9  4703.1  352.95  4831.8  352.25  4845.5  352.02  4986.6  352.21
  4993.7  351.26  4997.9  342.11  4998.9  341.61  5045.6  342.11  5057.5  352.37
  5176.3  353.54  5236.3  352.28  5513.1  354.18  5600.6  355.07  5988.7  361.72
  6114.8  369.07  6303.4   378.1  6395.7   383.6  6426.9  385.17  6454.4  386.17
#Mann= 19 ,-1 , 0
  3158.2     .05       0  4195.7     .07       0  4416.9     .05       0
  4423.2     .07       0  4560.8     .05       0  4695.6     .07       0
  4703.1    .035       0  4831.8     .05       0  4845.5      .1       0
  4997.9     .05       0  5045.6      .1       0  5176.3    .035       0
  5236.3      .1       0  5513.1     .05       0  5600.6     .07       0
  6114.8     .05       0  6303.4     .07       0  6395.7     .05       0
  6426.9     .07       0
Bank Sta=4997.9,5045.6
XS Rating Curve= 0 ,0
Exp/Cntr=0.3,0.1

Type RM Length L Ch R = 1 ,31513   ,1009,1009,1009
BEGIN DESCRIPTION:
Cooperas Creek 26.0
END DESCRIPTION:
XS GIS Cut Line= 3
      2513230.47     13820097.61        2512425.       13818525.
      2510824.98     13817974.99
#Sta/Elev= 30
  3233.4  366.67  3762.9  358.34  3856.7  357.06    3946  355.87  4121.4  353.95
  4620.2  350.54  4642.4  350.02  4658.9   347.3  4664.6  348.98  4681.1  346.79
    4714  347.44  4725.6  350.47  4731.2  348.99  4747.8   351.2  4853.2  349.42
  4964.2  351.62  4967.7  340.66  4968.7  340.16  5016.2  340.66  5021.4  350.83
  5374.2  351.05  5477.3  350.59  5580.5  352.34  5848.9  352.78  6096.3  356.32
  6231.4  359.46  6369.4  364.52  6519.6  375.78  6588.1  381.07  6692.2   385.1
#Mann= 14 ,-1 , 0
  3233.4     .05       0  3762.9     .07       0  3856.7     .05       0
    3946     .07       0  4121.4     .05       0    4714      .1       0
  4967.7     .05       0  5016.2      .1       0  5374.2     .05       0
  5477.3      .1       0  5580.5     .05       0  6096.3     .07       0
  6231.4     .05       0  6519.6     .07       0
Bank Sta=4967.7,5016.2
XS Rating Curve= 0 ,0
Exp/Cntr=0.3,0.1

Type RM Length L Ch R = 1 ,30504   ,688,688,688
BEGIN DESCRIPTION:
Cooperas Creek 25.0
END DESCRIPTION:
XS GIS Cut Line= 3
      2513311.67     13820002.83      2512580.75     13817688.25
      2511146.54     13815929.31
#Sta/Elev= 30
  2768.5  364.95    3672  351.55  3875.2  352.41  3951.2  351.18  3961.7  349.28
  3979.3  350.33  3984.4  351.34  4000.6  353.85  4129.5  354.21  4291.6  352.03
  4395.8  350.75  4821.6  348.71  4969.7  349.95  4978.9   349.7  4986.1  339.19
  4987.1  338.69  5034.6  339.19  5041.9   351.3  5244.8  348.38  5393.5  348.88
  5407.7  347.49  5422.1  343.05    5430  346.94  5450.8  349.73    5492  349.59
  5626.8  351.25  5642.6  351.57  6830.7  358.63  6975.1  360.17  7465.3  368.13
#Mann= 13 ,-1 , 0
  2768.5     .05       0  3875.2     .12       0  3979.3    .035       0
  3984.4     .05       0  4291.6     .12       0  4395.8      .1       0
  4986.1     .05       0  5034.6      .1       0    5492     .05       0
  5626.8    .035       0  5642.6     .05       0  6830.7     .07       0
  6975.1     .05       0
Bank Sta=4986.1,5034.6
XS Rating Curve= 0 ,0
Exp/Cntr=0.3,0.1

Type RM Length L Ch R = 1 ,29816   ,561,561,561
BEGIN DESCRIPTION:
Cooperas Creek 24.0
END DESCRIPTION:
XS GIS Cut Line= 3
      2513525.03     13818325.03        2512925.       13817625.
      2511474.99     13816024.99
#Sta/Elev= 30
    4078  367.65  4146.7  365.76  4185.7  364.61  4205.9  364.41  4439.7  352.99
  4605.7  348.13  4659.2  347.84    4678  348.74  4914.9  349.62  4943.5  347.72
  4947.1  338.09  4948.1  337.59  4996.9  338.09  5013.8  340.88  5021.3  344.26
    5028  345.64  5042.2  347.66  5070.6  348.85  5378.3  349.53  5623.5  351.74
    5632  351.92  6097.2  353.38  6309.4  355.27    6352  354.65  6801.8  359.55
  6848.2  359.45  6989.3  360.62  7017.7  362.01  7081.2   362.1  7159.3  364.03
#Mann= 12 ,-1 , 0
    4078     .05       0  4146.7    .035       0  4185.7     .05       0
  4605.7     .07       0    4678      .1       0  4947.1     .05       0
  4996.9      .1       0  5378.3     .07       0  5623.5    .035       0
    5632     .05       0  6801.8     .07       0  6848.2     .05       0
Bank Sta=4947.1,4996.9
XS Rating Curve= 0 ,0
Exp/Cntr=0.3,0.1