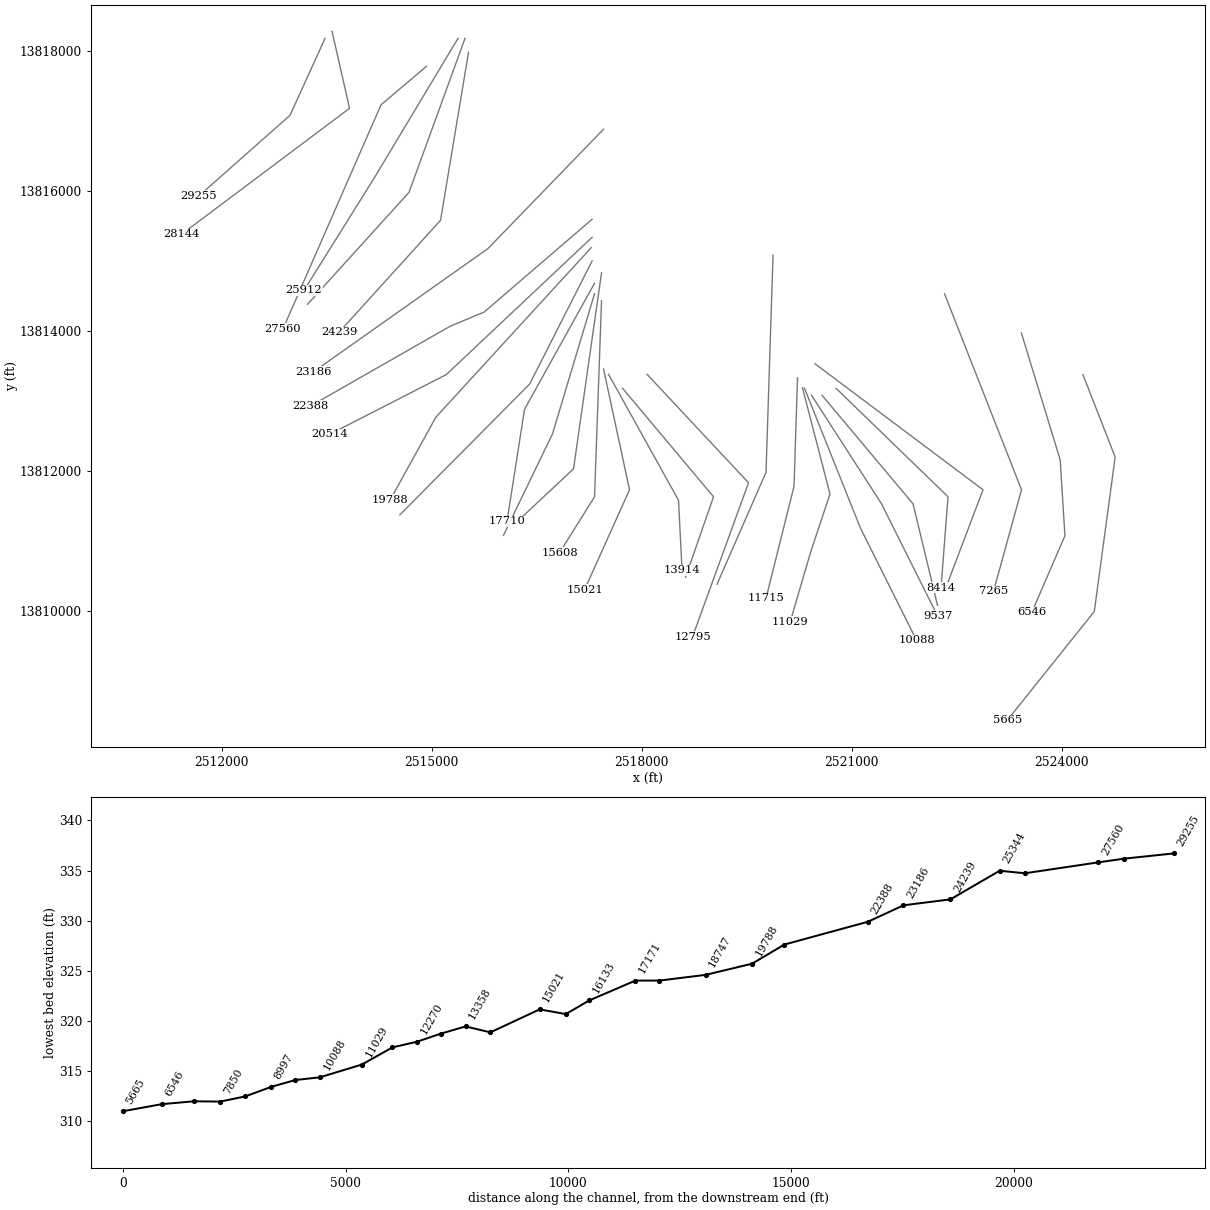
HEC-RAS study Copperas Creek.prj: Copperas Creek Base Level Engineering

--- Copperas Creek.g01 (geometry) --- (continued)

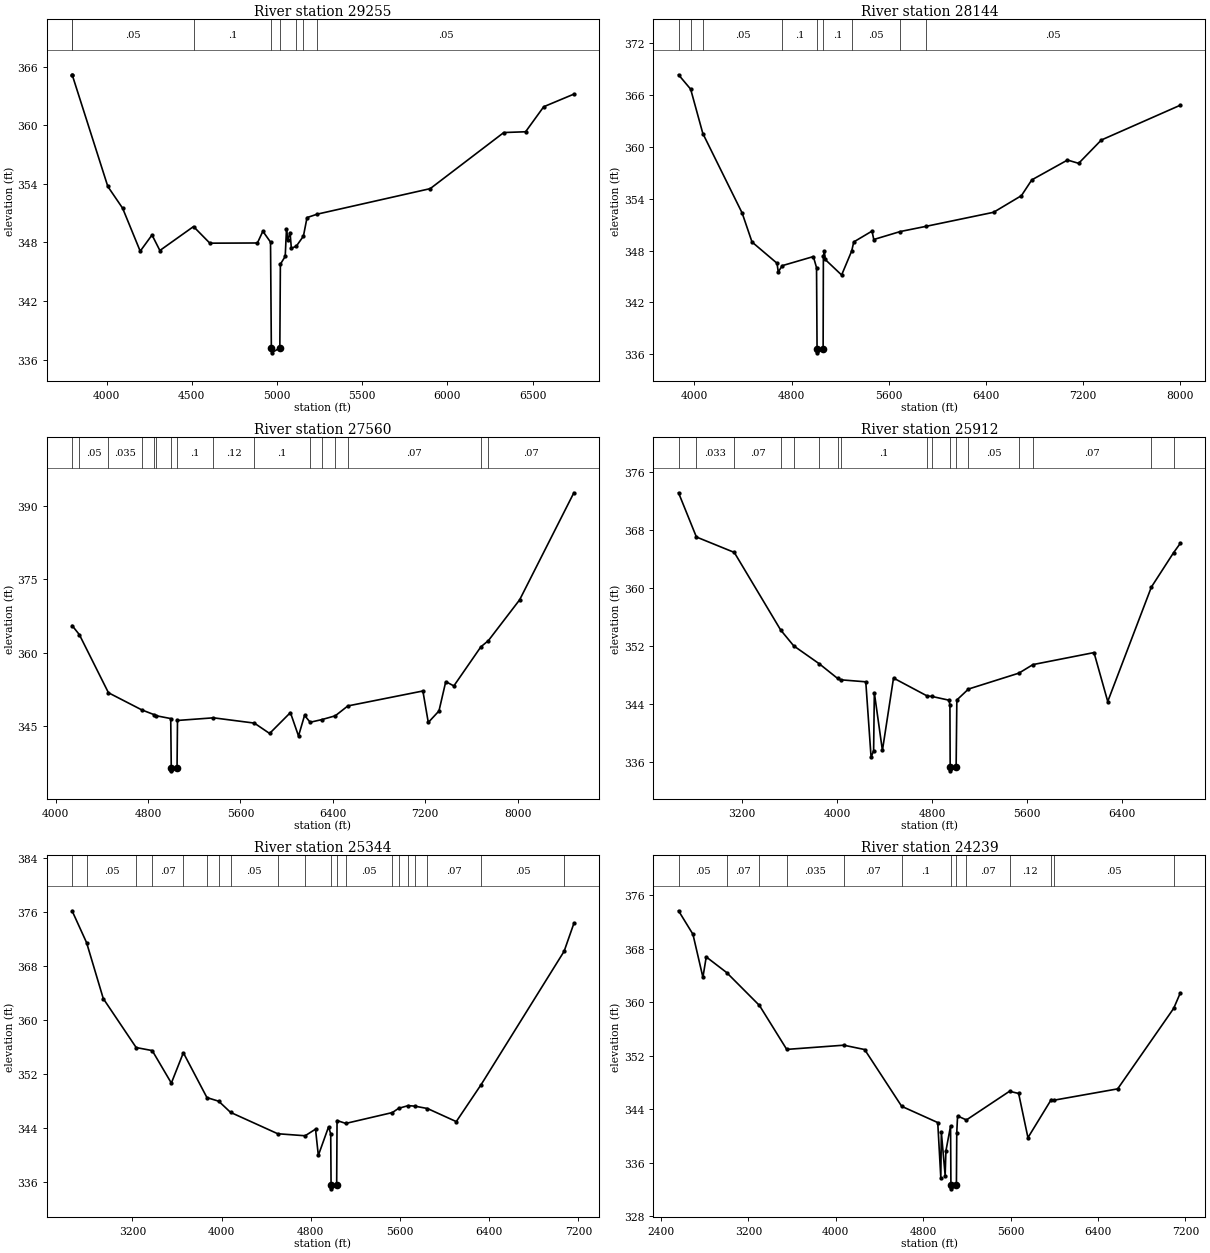
Type RM Length L Ch R = 1 ,29255   ,1111,1111,1111
BEGIN DESCRIPTION:
Cooperas Creek 23.0
END DESCRIPTION:
XS GIS Cut Line= 3
      2513474.98     13818174.97        2512975.       13817075.
      2511675.02     13815925.01
#Sta/Elev= 30
  3797.8  365.16  3798.5  365.16  4007.6  353.73  4094.3  351.51  4197.6  347.11
  4266.8  348.77  4312.9  347.18  4510.3  349.63  4606.2  347.93  4885.2  347.95
  4917.1  349.15  4962.1  348.04  4966.9  337.21  4967.9  336.71  5016.7  337.21
  5019.9  345.78  5048.3  346.58  5055.8  349.39  5062.5  348.25  5076.7  349.01
  5084.3  347.41  5113.3  347.62  5155.1  348.65  5176.3  350.55  5236.1   350.9
    5899  353.51  6330.6  359.25  6458.6  359.33  6564.8  361.89  6741.7  363.18
#Mann= 8 ,-1 , 0
  3797.8    .035       0  3798.5     .05       0  4510.3      .1       0
  4966.9     .05       0  5016.7      .1       0  5113.3     .07       0
  5155.1    .035       0  5236.1     .05       0
Bank Sta=4966.9,5016.7
XS Rating Curve= 0 ,0
Exp/Cntr=0.3,0.1

Type RM Length L Ch R = 1 ,28144   ,584,584,584
BEGIN DESCRIPTION:
Cooperas Creek 22.0
END DESCRIPTION:
XS GIS Cut Line= 3
        2513575.     13818275.01        2513825.       13817175.
      2511424.97     13815374.97
#Sta/Elev= 30
  3870.5  368.28  3970.2  366.62  4070.5   361.5    4394  352.32    4475  348.98
  4680.7  346.53  4690.9  345.52  4723.5  346.25  4979.6   347.3  5005.8  346.02
  5010.1  336.69  5011.1  336.19    5060  336.69  5062.1  347.35  5070.4  347.89
  5076.7  346.97  5212.1  345.17  5295.2  347.95  5312.1  348.99  5462.1  350.24
  5476.7  349.27  5695.1  350.19    5907  350.79  6462.1  352.41  6691.3  354.33
  6776.7  356.15  7070.4  358.44  7162.1  358.06  7348.6  360.75  7998.6  364.77
#Mann= 9 ,-1 , 0
  3870.5     .05       0  3970.2    .035       0  4070.5     .05       0
  4723.5      .1       0  5010.1     .05       0    5060      .1       0
  5295.2     .05       0  5695.1    .035       0    5907     .05       0
Bank Sta=5010.1,5060
XS Rating Curve= 0 ,0
Exp/Cntr=0.3,0.1

Type RM Length L Ch R = 1 ,27560   ,1648,1648,1648
BEGIN DESCRIPTION:
Cooperas Creek 21.0
END DESCRIPTION:
XS GIS Cut Line= 3
      2514924.99     13817774.99        2514275.       13817225.
        2512875.     13814025.01
#Sta/Elev= 30
  4142.1  365.56  4205.2  363.69    4457   351.8  4745.7  348.29  4855.5  347.29
  4867.1  347.11  4996.3  346.52  5000.9  336.32  5001.9  335.82  5050.9  336.32
  5054.8  346.13  5366.4  346.67  5719.9  345.59  5852.3  343.47  6032.4  347.74
  6102.6  342.95  6154.9  347.17  6203.3  345.76  6303.5   346.3  6420.8  347.08
  6529.5   349.1  7179.3  352.16  7226.1  345.72  7318.5  348.07  7377.3  354.07
  7447.5   353.2  7681.2  361.19  7746.5  362.47  8017.1  370.82  8486.4  392.72
#Mann= 16 ,-1 , 0
  4142.1     .07       0  4205.2     .05       0    4457    .035       0
  4745.7     .05       0  4855.5     .07       0  4867.1      .1       0
  5000.9     .05       0  5050.9      .1       0  5366.4     .12       0
  5719.9      .1       0  6203.3     .12       0  6303.5     .05       0
  6420.8    .035       0  6529.5     .07       0  7681.2     .05       0
  7746.5     .07       0
Bank Sta=5000.9,5050.9
XS Rating Curve= 0 ,0
Exp/Cntr=0.3,0.1

Type RM Length L Ch R = 1 ,25912   ,568,568,568
BEGIN DESCRIPTION:
Cooperas Creek 20.0
END DESCRIPTION:
XS GIS Cut Line= 3
        2515375.     13818175.01        2514175.       13816175.
      2513174.99     13814574.99
#Sta/Elev= 30
  2667.7  373.15  2817.9  367.04  3136.4  364.91  3526.4  354.19  3636.2     352
  3851.3  349.52  4005.8  347.49  4029.9  347.31  4242.1  347.03  4286.8  336.58
  4308.1  337.53    4314  345.53    4382  337.55  4475.3  347.55  4757.6  345.08
  4798.5  345.01  4941.8  344.49  4949.6  343.82  4951.7  335.23  4952.7  334.73
  5001.8  335.23  5007.8  344.52  5105.4  346.03  5529.5  348.23  5647.6  349.41
  6161.1  351.07  6276.6  344.31  6643.4  360.12  6829.6  364.86  6886.9  366.17
#Mann= 17 ,-1 , 0
  2667.7     .05       0  2817.9    .033       0  3136.4     .07       0
  3526.4    .035       0  3636.2     .05       0  3851.3    .035       0
  4005.8     .05       0  4029.9      .1       0  4757.6     .12       0
  4798.5      .1       0  4951.7     .05       0  5001.8      .1       0
  5105.4     .05       0  5529.5    .035       0  5647.6     .07       0
  6643.4     .05       0  6829.6     .07       0
Bank Sta=4951.7,5001.8
XS Rating Curve= 0 ,0
Exp/Cntr=0.3,0.1

Type RM Length L Ch R = 1 ,25344   ,1105,1105,1105
BEGIN DESCRIPTION:
Cooperas Creek 19.0
END DESCRIPTION:
XS GIS Cut Line= 3
      2515474.98     13818174.96        2514675.       13815975.
      2513224.99     13814374.98
#Sta/Elev= 30
  2658.5  376.21  2788.8  371.48  2938.4  363.19  3233.4  355.93  3377.4  355.48
  3548.9  350.66  3656.5  355.16  3868.1  348.51  3973.9  347.97  4079.7  346.32
  4502.9  343.15  4748.9  342.85  4841.8  343.83  4867.1  339.94  4958.8  344.17
  4978.1  343.14  4981.4  335.48  4982.4  334.98  5031.5  335.48  5034.9  345.11
  5113.1  344.68  5530.9  346.29  5586.3  346.91  5673.2  347.32    5733  347.24
  5845.8  346.89  6104.1  344.95  6327.7  350.45  7071.2   370.2  7158.7  374.33
#Mann= 20 ,-1 , 0
  2658.5     .07       0  2788.8     .05       0  3233.4     .07       0
  3377.4     .07       0  3656.5     .05       0  3868.1     .05       0
  3973.9    .035       0  4079.7     .05       0  4502.9     .12       0
  4748.9      .1       0  4981.4     .05       0  5031.5      .1       0
  5113.1     .05       0  5530.9     .07       0  5586.3    .035       0
  5673.2     .07       0    5733     .12       0  5845.8     .07       0
  6327.7     .05       0  7071.2     .07       0
Bank Sta=4981.4,5031.5
XS Rating Curve= 0 ,0
Exp/Cntr=0.3,0.1

Type RM Length L Ch R = 1 ,24239   ,1053,1053,1053
BEGIN DESCRIPTION:
Cooperas Creek 18.0
END DESCRIPTION:
XS GIS Cut Line= 3
      2515525.01     13817975.04        2515125.       13815575.
      2513675.02     13813975.02
#Sta/Elev= 30
  2560.4  373.71  2692.2   370.2  2783.5  363.76  2813.9  366.81  3000.2  364.48
  3300.9  359.55  3550.6  352.98  4072.6  353.61  4263.6  352.96  4602.7  344.47
  4932.7  342.04  4960.6  333.82  4965.7  340.57  5000.6  334.12  5007.4  337.79
    5050  341.53  5053.3  332.63  5054.3  332.13  5103.5  332.63  5106.7  340.52
  5114.2  343.03    5195  342.43  5589.7  346.72  5673.1  346.39  5758.2  339.78
  5971.6  345.48  5994.7  345.38  6579.4  347.08  7092.1  359.12  7152.8  361.43
#Mann= 13 ,-1 , 0
  2560.4     .05       0  3000.2     .07       0  3300.9     .05       0
  3550.6    .035       0  4072.6     .07       0  4602.7      .1       0
  5053.3     .05       0  5103.5      .1       0    5195     .07       0
  5589.7     .12       0  5971.6     .07       0  5994.7     .05       0
  7092.1     .07       0
Bank Sta=5053.3,5103.5
XS Rating Curve= 0 ,0
Exp/Cntr=0.3,0.1

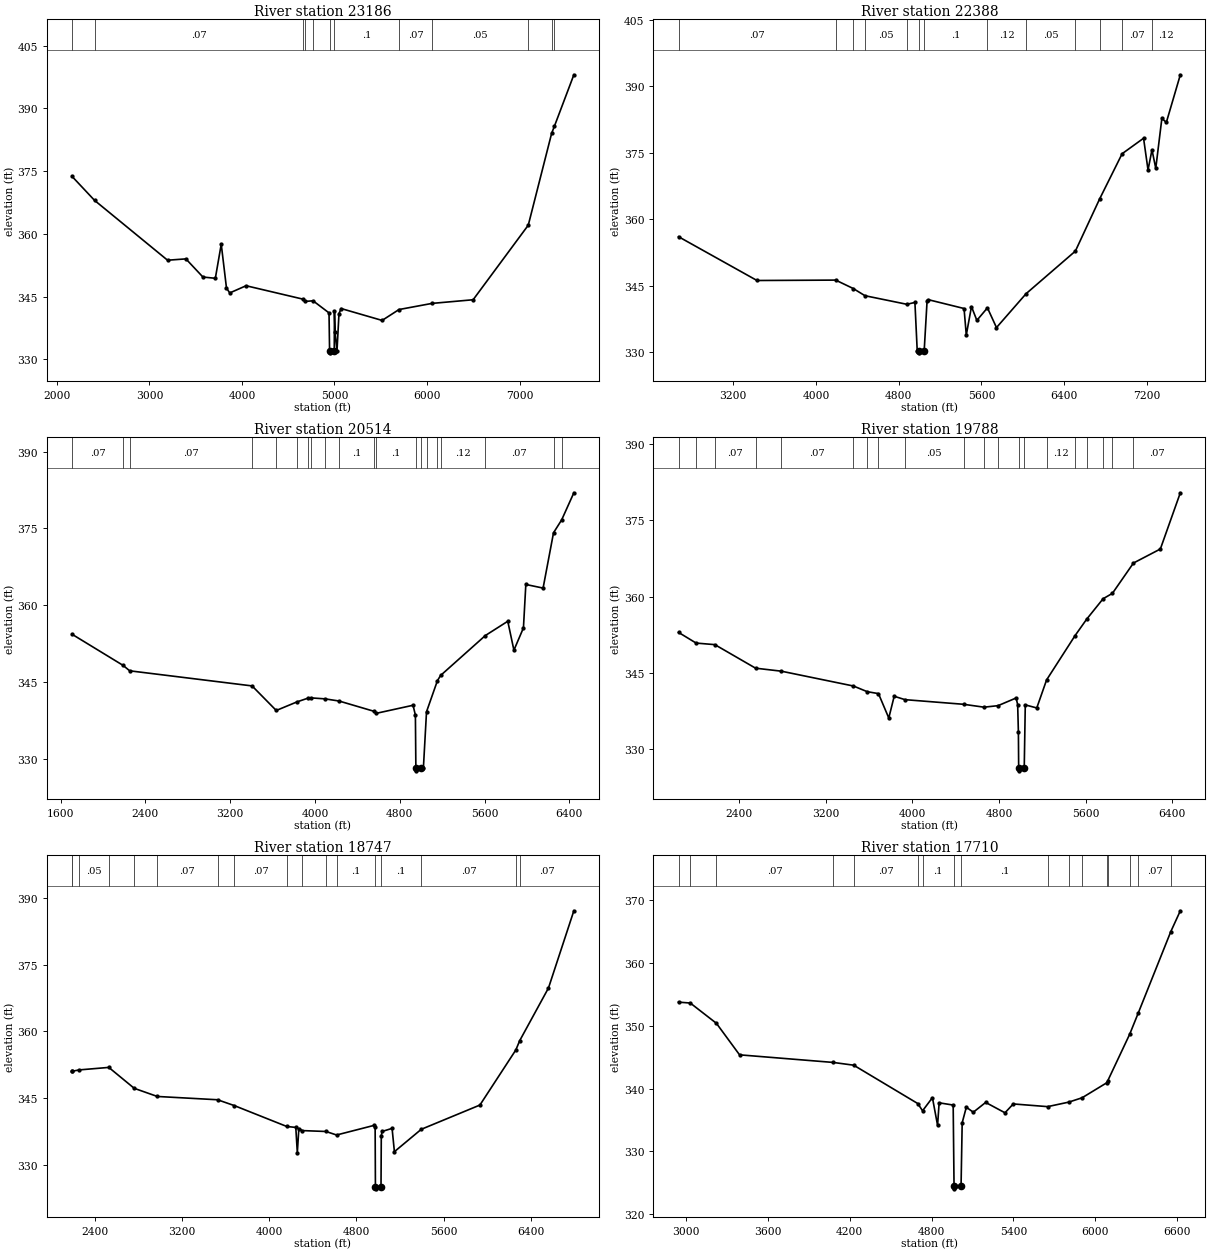
Type RM Length L Ch R = 1 ,23186   ,798,798,798
BEGIN DESCRIPTION:
X18518
END DESCRIPTION:
XS GIS Cut Line= 3
       2517453.6     13816876.14      2515802.23     13815170.62
      2513311.71     13813411.01
#Sta/Elev= 30
  2164.1  373.71    2407  367.99  3196.3  353.68  3394.4     354  3578.3  349.66
  3712.6  349.36  3776.4  357.51    3833  347.03  3868.2  345.86    4045  347.58
  4656.9  344.39  4681.9  343.83  4768.7  343.98  4941.3  341.09  4947.3  332.04
  4948.3  331.54  4997.8  332.04    5000   341.5  5006.6  336.44  5027.5  332.04
  5048.9   340.9  5071.9  342.13    5515  339.29  5697.5  341.89  6054.7  343.36
  6498.7  344.23  7094.9  362.06  7347.2     384  7377.8  385.74  7587.5  398.01
#Mann= 12 ,-1 , 0
  2164.1    .035       0    2407     .07       0  4656.9      .1       0
  4681.9     .07       0  4768.7      .1       0  4947.3     .05       0
  4997.8      .1       0  5697.5     .07       0  6054.7     .05       0
  7094.9     .07       0  7347.2     .12       0  7377.8     .07       0
Bank Sta=4947.3,4997.8
XS Rating Curve= 0 ,0
Exp/Cntr=0.3,0.1

Type RM Length L Ch R = 1 ,22388   ,1874,1874,1874
BEGIN DESCRIPTION:
X18517
END DESCRIPTION:
XS GIS Cut Line= 4
      2517290.43     13815589.61      2515748.09     13814263.73
      2515260.81      13814060.7      2513271.05     13812923.69
#Sta/Elev= 30
  2670.3   356.1  3429.1  346.22  4190.3  346.31  4360.2  344.41  4473.4  342.79
    4879  340.85  4956.7  341.27  4978.9   330.4  4995.9   330.4  4996.9   329.9
  5046.4   330.4  5074.2  341.57  5086.7  341.89  5431.9   339.9  5453.5  333.92
  5503.7  340.33  5555.8  337.22  5658.1  340.05  5745.6   335.6  6032.2  343.25
  6508.7  352.85  6743.5  364.63  6960.9  374.82  7168.2  378.31  7211.4  371.16
  7249.6  375.69  7286.3  371.53  7345.3   382.8  7388.5  381.88  7523.8  392.63
#Mann= 13 ,-1 , 0
  2670.3     .07       0  4190.3     .05       0  4360.2     .07       0
  4473.4     .05       0    4879      .1       0  4995.9     .05       0
  5046.4      .1       0  5658.1     .12       0  6032.2     .05       0
  6508.7     .07       0  6743.5     .12       0  6960.9     .07       0
  7249.6     .12       0
Bank Sta=4995.9,5046.4
XS Rating Curve= 0 ,0
Exp/Cntr=0.3,0.1

Type RM Length L Ch R = 1 ,20514   ,726,726,726
BEGIN DESCRIPTION:
X18516
END DESCRIPTION:
XS GIS Cut Line= 3
      2517290.55     13815332.48      2515206.67     13813370.38
      2513541.79     13812517.64
#Sta/Elev= 30
  1709.1  354.31  2190.3  348.23  2252.6  347.17  3406.9  344.22    3635  339.42
  3831.8  341.11    3933  341.82  3963.6  341.88  4095.4  341.69  4227.2  341.27
  4560.4  339.24  4577.2  338.86  4925.1  340.44  4947.3  338.51  4951.8  328.13
  4952.8  327.63    5003  328.13  5022.6  328.13  5052.2  339.17  5155.2  345.25
  5184.9  346.26    5607  354.06  5818.6  356.85  5876.5   351.2  5966.4  355.56
  5988.9  364.04  6151.7  363.33  6250.1  374.14    6327  376.66  6441.9  381.95
#Mann= 20 ,-1 , 0
  1709.1     .07       0  2190.3     .05       0  2252.6     .07       0
  3406.9     .05       0    3635     .07       0  3831.8     .05       0
    3933     .07       0  3963.6     .05       0  4095.4     .05       0
  4227.2      .1       0  4560.4     .12       0  4577.2      .1       0
  4951.8     .05       0    5003      .1       0  5052.2     .12       0
  5155.2      .1       0  5184.9     .12       0    5607     .07       0
  6250.1     .12       0    6327    .035       0
Bank Sta=4951.8,5003
XS Rating Curve= 0 ,0
Exp/Cntr=0.3,0.1

Type RM Length L Ch R = 1 ,19788   ,1041,1041,1041
BEGIN DESCRIPTION:
X18515
END DESCRIPTION:
XS GIS Cut Line= 3
       2517277.6     13815184.14      2515057.77     13812761.28
      2514408.04     13811583.64
#Sta/Elev= 30
  1842.2  352.95  2004.4  350.85  2177.5  350.54  2553.3  345.91  2791.1  345.32
  3456.9   342.4  3583.4  341.29  3687.3  340.91  3782.6  336.11  3832.5  340.39
  3932.1  339.72  4472.2  338.81  4661.8  338.24    4791  338.54  4957.9  340.05
    4972  338.73  4978.8  333.28  4981.3  326.22  4982.3  325.72  5032.6  326.22
  5042.3  338.69  5148.4  338.09  5238.9   343.6  5501.8  352.32  5608.6  355.54
  5760.6  359.57  5846.5  360.63  6040.5  366.59  6288.9  369.35  6473.2  380.41
#Mann= 20 ,-1 , 0
  1842.2     .07       0  2004.4     .07       0  2177.5     .07       0
  2553.3     .05       0  2791.1     .07       0  3456.9     .05       0
  3583.4     .05       0  3687.3     .07       0  3932.1     .05       0
  4472.2     .07       0  4661.8     .07       0    4791      .1       0
  4981.3     .05       0  5032.6      .1       0  5238.9     .12       0
  5501.8     .07       0  5608.6     .12       0  5760.6     .07       0
  5846.5    .035       0  6040.5     .07       0
Bank Sta=4981.3,5032.6
XS Rating Curve= 0 ,0
Exp/Cntr=0.3,0.1

Type RM Length L Ch R = 1 ,18747   ,1037,1037,1037
BEGIN DESCRIPTION:
Cooperas Creek 17.0
END DESCRIPTION:
XS GIS Cut Line= 3
      2517291.17      13814994.7       2516397.8     13813235.03
      2514543.45     13811367.14
#Sta/Elev= 30
  2190.6  350.99  2193.8  351.05  2257.3  351.34  2527.7   351.9  2761.1   347.2
    2973  345.37  3525.9  344.63  3679.4  343.32  4160.7  338.63  4243.9  338.41
    4258  332.73  4272.1  338.17  4302.4   337.7  4520.8   337.5  4618.4  336.71
  4965.1  338.89  4972.2  338.41  4974.8  325.11  4975.8  324.61  5026.1  325.11
  5028.7  336.53  5035.8   337.5  5127.7   338.2    5149  332.96  5395.6  337.99
  5933.8  343.44  6263.5  355.82  6299.5  357.93  6563.2  369.75  6796.1   387.1
#Mann= 17 ,-1 , 0
  2190.6     .05       0  2193.8     .07       0  2257.3     .05       0
  2527.7     .07       0  2761.1     .05       0    2973     .07       0
  3525.9     .05       0  3679.4     .07       0  4160.7     .12       0
  4302.4      .1       0  4520.8     .12       0  4618.4      .1       0
  4974.8     .05       0  5026.1      .1       0  5395.6     .07       0
  6263.5    .035       0  6299.5     .07       0
Bank Sta=4974.8,5026.1
XS Rating Curve= 0 ,0
Exp/Cntr=0.3,0.1

Type RM Length L Ch R = 1 ,17710   ,539,539,539
BEGIN DESCRIPTION:
Cooperas Creek 16.0
END DESCRIPTION:
XS GIS Cut Line= 3
      2517325.02     13814675.03        2516325.       13812875.
        2516075.     13811274.97
#Sta/Elev= 30
  2945.5  353.77  3031.5  353.63  3223.2   350.4  3392.8  345.38    4079  344.17
  4229.6  343.73  4699.5  337.62  4734.5  336.47  4806.8  338.56  4844.5  334.15
  4855.9  337.74  4958.9  337.38  4965.2  324.54  4966.2  324.04  5016.7  324.54
  5024.9  334.56  5055.3  337.04  5106.4  336.24    5197   337.8  5338.7  336.15
  5399.4  337.56  5651.4  337.13  5806.3  337.85  5903.9  338.54  6084.8  340.93
    6093  341.29  6253.1  348.67  6315.2  352.01  6554.4  365.01  6624.1  368.32
#Mann= 17 ,-1 , 0
  2945.5     .07       0  3031.5     .05       0  3223.2     .07       0
    4079     .05       0  4229.6     .07       0  4699.5     .12       0
  4734.5      .1       0  4965.2     .05       0  5016.7      .1       0
  5651.4     .07       0  5806.3      .1       0  5903.9     .07       0
  6084.8     .05       0    6093     .07       0  6253.1     .12       0
  6315.2     .07       0  6554.4     .12       0
Bank Sta=4965.2,5016.7
XS Rating Curve= 0 ,0
Exp/Cntr=0.3,0.1

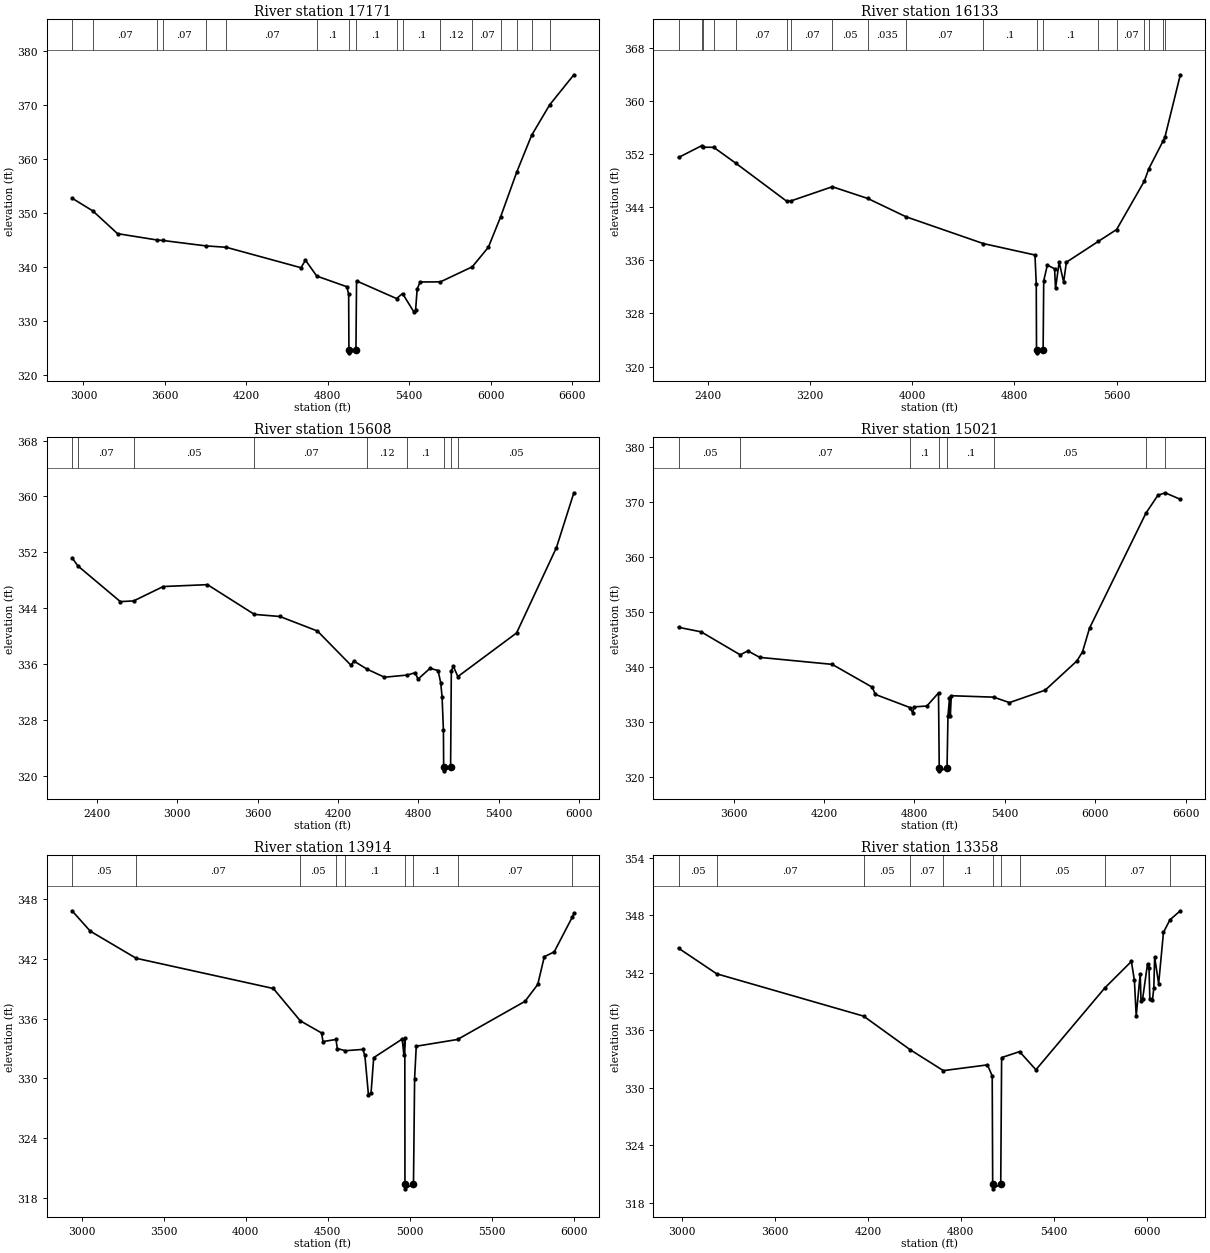
Type RM Length L Ch R = 1 ,17171   ,1038,1038,1038
BEGIN DESCRIPTION:
Cooperas Creek 15.0
END DESCRIPTION:
XS GIS Cut Line= 3
      2517325.01     13814525.02        2516725.       13812525.
        2516025.       13811075.
#Sta/Elev= 30
  2915.8  352.73    3069  350.36  3250.8  346.15  3540.5  344.98  3585.4  344.88
  3902.2  343.88  4052.1  343.62  4602.8  339.83  4635.9  341.23  4719.2  338.28
  4941.2   336.3  4954.3  334.91  4956.3  324.54  4957.3  324.04  5007.9  324.54
  5012.4  337.38  5307.3  334.11  5351.4  335.04  5436.9  331.55  5447.5  331.93
  5459.2   335.9  5481.4  337.18    5631  337.21  5865.3     340    5984  343.63
  6074.1  349.26  6194.4  357.66  6302.7  364.39  6435.5  370.04    6614  375.62
#Mann= 17 ,-1 , 0
  2915.8     .05       0    3069     .07       0  3540.5     .05       0
  3585.4     .07       0  3902.2     .05       0  4052.1     .07       0
  4719.2      .1       0  4956.3     .05       0  5007.9      .1       0
  5307.3     .12       0  5351.4      .1       0    5631     .12       0
  5865.3     .07       0  6074.1     .12       0  6194.4     .07       0
  6302.7     .12       0  6435.5     .07       0
Bank Sta=4956.3,5007.9
XS Rating Curve= 0 ,0
Exp/Cntr=0.3,0.1

Type RM Length L Ch R = 1 ,16133   ,525,525,525
BEGIN DESCRIPTION:
Cooperas Creek 14.0
END DESCRIPTION:
XS GIS Cut Line= 3
        2517425.       13814825.        2517025.       13812025.
      2516225.01     13811275.01
#Sta/Elev= 30
  2172.2  351.51  2355.2  353.31  2361.7  353.07  2447.6  353.04  2621.4  350.63
  3020.1  344.89  3053.8  344.98    3375   347.1  3652.6  345.33    3952  342.57
  4554.8  338.54  4960.2  336.81  4970.3  332.46  4972.3  322.56  4973.3  322.06
    5024  322.56  5028.7  332.92  5057.1  335.29  5113.7  334.73    5121  331.76
  5149.4  335.74  5184.5  332.73    5206  335.72  5456.3  338.87  5598.8  340.65
  5815.6  347.95  5850.9  349.82  5963.9  354.05  5977.7  354.65  6097.2  363.98
#Mann= 19 ,-1 , 0
  2172.2     .07       0  2355.2     .05       0  2361.7     .07       0
  2447.6     .05       0  2621.4     .07       0  3020.1     .05       0
  3053.8     .07       0    3375     .05       0  3652.6    .035       0
    3952     .07       0  4554.8      .1       0  4972.3     .05       0
    5024      .1       0  5456.3     .12       0  5598.8     .07       0
  5815.6     .12       0  5850.9     .07       0  5963.9     .12       0
  5977.7     .07       0
Bank Sta=4972.3,5024
XS Rating Curve= 0 ,0
Exp/Cntr=0.3,0.1

Type RM Length L Ch R = 1 ,15608   ,587,587,587
BEGIN DESCRIPTION:
Cooperas Creek 13.0
END DESCRIPTION:
XS GIS Cut Line= 3
        2517425.     13814424.97        2517325.       13811625.
      2516824.98     13810824.96
#Sta/Elev= 30
  2215.5  351.22  2258.6  350.06  2575.7  344.94  2675.2  345.04  2895.9   347.1
  3226.1  347.37  3576.3  343.11  3766.5  342.81  4046.6  340.73  4296.8  335.83
  4319.3  336.42  4417.6  335.26    4547  334.11  4716.7  334.42  4777.1  334.76
  4797.1  333.83  4887.2  335.38  4947.2  335.07  4967.2  333.28  4977.2  331.26
  4987.2  326.51  4988.9   321.2  4989.9   320.7  5040.7   321.2  5046.1  335.03
  5061.5  335.67  5094.8   334.2  5533.2  340.45  5830.9  352.69  5960.7  360.53
#Mann= 9 ,-1 , 0
  2215.5     .05       0  2258.6     .07       0  2675.2     .05       0
  3576.3     .07       0  4417.6     .12       0  4716.7      .1       0
  4988.9     .05       0  5040.7      .1       0  5094.8     .05       0
Bank Sta=4988.9,5040.7
XS Rating Curve= 0 ,0
Exp/Cntr=0.3,0.1

Type RM Length L Ch R = 1 ,15021   ,1107,1107,1107
BEGIN DESCRIPTION:
Cooperas Creek 12.0
END DESCRIPTION:
XS GIS Cut Line= 3
      2517453.58     13813451.61        2517825.       13811725.
      2517183.37      13810298.9
#Sta/Elev= 30
  3234.4  347.25  3384.4  346.43    3644  342.25  3694.6  342.97  3773.1  341.79
  4253.8  340.52  4519.8  336.37  4540.2  335.06  4769.1  332.68  4788.7  331.68
  4795.9  332.79  4882.3  332.95  4959.6  335.33  4964.4  321.67  4965.4  321.17
  5016.2  321.67  5022.4  331.17  5032.5  334.33    5038  331.13  5044.4  334.82
  5325.8  334.56  5430.3  333.57  5667.3  335.83  5877.7  341.13  5915.3   342.8
  5961.6  347.09  6335.7  367.98  6415.1  371.23  6463.5   371.7  6564.3  370.51
#Mann= 8 ,-1 , 0
  3234.4     .05       0    3644     .07       0  4769.1      .1       0
  4964.4     .05       0  5016.2      .1       0  5325.8     .05       0
  6335.7    .035       0  6463.5     .05       0
Bank Sta=4964.4,5016.2
XS Rating Curve= 0 ,0
Exp/Cntr=0.3,0.1

Type RM Length L Ch R = 1 ,13914   ,556,556,556
BEGIN DESCRIPTION:
Cooperas Creek 11.0
END DESCRIPTION:
XS GIS Cut Line= 3
      2517525.02     13813374.97        2518525.       13811575.
        2518575.     13810575.04
#Sta/Elev= 30
  2941.5  346.86  3052.4  344.81  3332.6  342.08  4168.9  339.04  4333.9  335.78
  4462.9  334.57  4472.1   333.7  4551.1  333.91    4559     333    4608  332.78
  4714.6  332.91  4727.2   332.3  4748.9  328.36  4764.9  328.51    4781  332.08
  4954.8  333.95  4965.1  332.37  4970.8  334.07  4971.7  319.38  4972.7  318.88
  5023.7  319.38  5030.6  329.98  5040.6  333.23  5292.3  333.91    5704  337.75
  5781.6  339.45  5821.6  342.24  5881.7  342.72  5992.1  346.22  6001.8  346.59
#Mann= 9 ,-1 , 0
  2941.5     .05       0  3332.6     .07       0  4333.9     .05       0
  4551.1     .07       0    4608      .1       0  4971.7     .05       0
  5023.7      .1       0  5292.3     .07       0  5992.1     .05       0
Bank Sta=4971.7,5023.7
XS Rating Curve= 0 ,0
Exp/Cntr=0.3,0.1

Type RM Length L Ch R = 1 ,13358   ,563,563,563
BEGIN DESCRIPTION:
Cooperas Creek 10.0
END DESCRIPTION:
XS GIS Cut Line= 3
      2517724.99     13813175.02        2519025.       13811625.
        2518625.       13810475.
#Sta/Elev= 30
  2977.2  344.55  3223.9  341.88  4172.4  337.47  4472.1  333.98  4687.4  331.79
  4972.2  332.39  5002.9  331.24    5006  319.97    5007  319.47    5058  319.97
  5063.7  333.15  5179.6  333.77  5285.1  331.88  5730.2  340.41  5901.8  343.17
  5921.3  341.19  5932.9  337.48  5958.7  341.89    5964  339.07  5974.3  339.26
    6006  342.93  6015.6  342.53  6020.9  339.26  6037.8  339.12  6046.7  340.44
    6052  343.64  6077.8  340.84  6108.9   346.2  6150.8  347.51  6217.8  348.45
#Mann= 10 ,-1 , 0
  2977.2     .05       0  3223.9     .07       0  4172.4     .05       0
  4472.1     .07       0  4687.4      .1       0    5006     .05       0
    5058      .1       0  5179.6     .05       0  5730.2     .07       0
  6150.8     .05       0
Bank Sta=5006,5058
XS Rating Curve= 0 ,0
Exp/Cntr=0.3,0.1

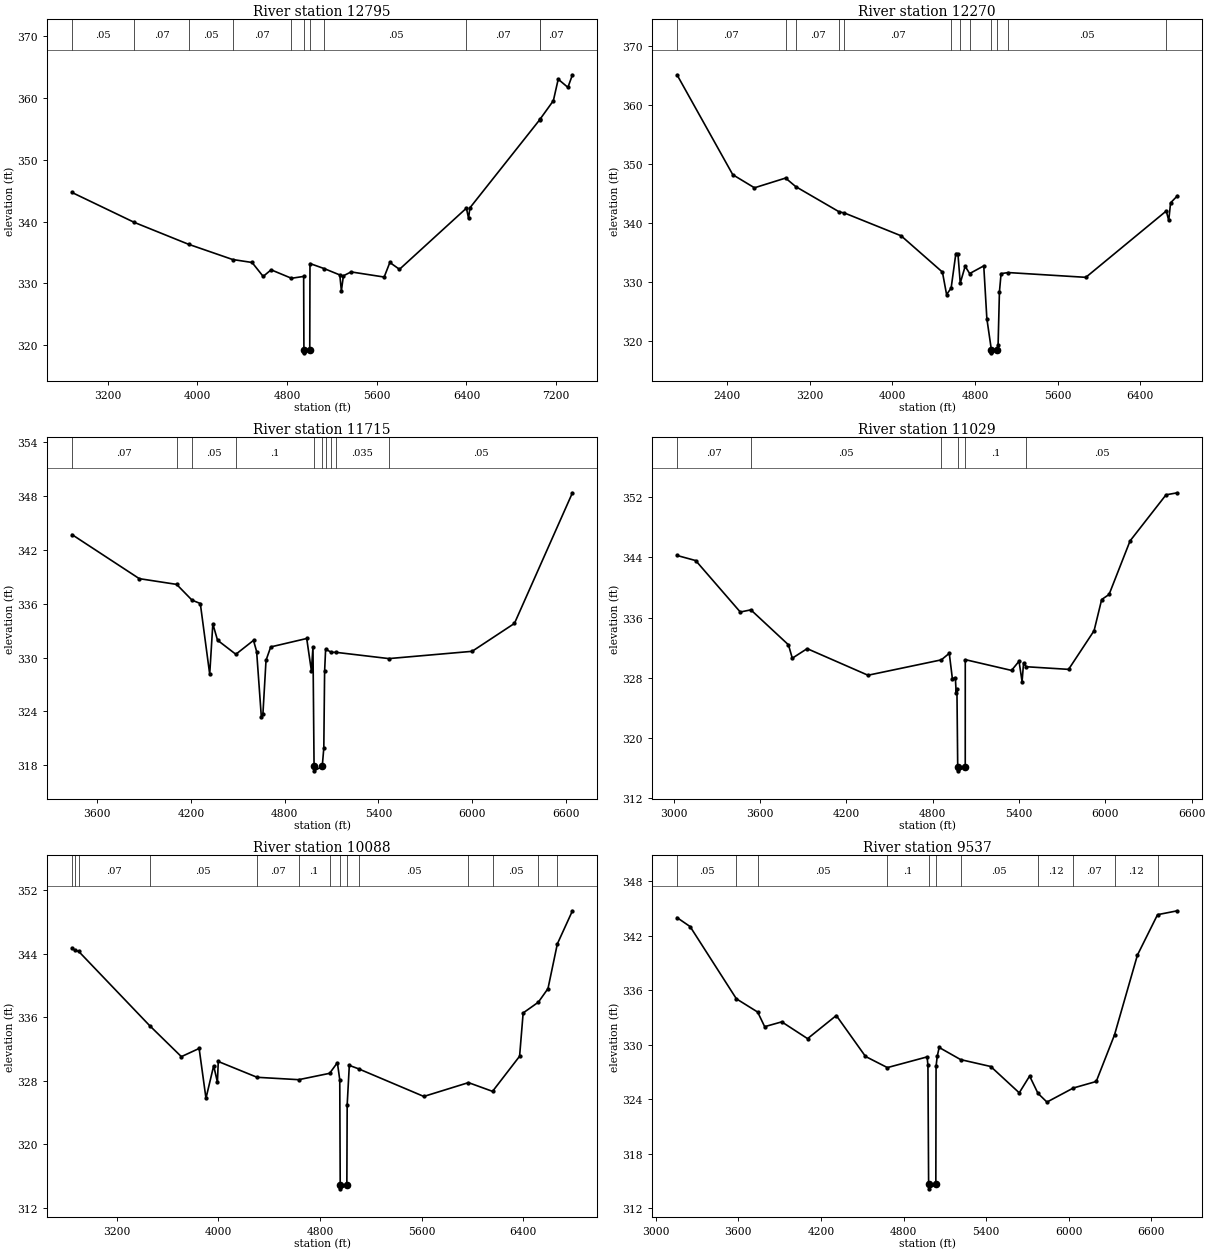
Type RM Length L Ch R = 1 ,12795   ,525,525,525
BEGIN DESCRIPTION:
Cooperas Creek 9.0
END DESCRIPTION:
XS GIS Cut Line= 3
      2518074.99     13813375.01        2519525.       13811825.
      2518724.98     13809624.96
#Sta/Elev= 30
  2881.6  344.72  3437.9  339.87  3920.8  336.33  4314.3  333.86  4487.5  333.38
  4586.7  331.12  4657.5  332.19  4839.2  330.82  4947.7  331.12  4949.9  319.24
  4950.9  318.74  5002.1  319.24  5004.1  333.21  5133.5  332.37  5270.1  331.36
  5284.1  328.77  5302.1  331.22  5370.6  331.85  5665.8  331.02  5716.4  333.38
  5802.2  332.27  6399.2  342.18  6418.7  340.52    6430  342.22  7052.4  356.49
  7055.5  356.58  7174.8  359.59    7218  363.07  7304.5  361.75  7345.1  363.79
#Mann= 11 ,-1 , 0
  2881.6     .05       0  3437.9     .07       0  3920.8     .05       0
  4314.3     .07       0  4839.2      .1       0  4949.9     .05       0
  5002.1      .1       0  5133.5     .05       0  6399.2     .07       0
  7052.4     .05       0  7055.5     .07       0
Bank Sta=4949.9,5002.1
XS Rating Curve= 0 ,0
Exp/Cntr=0.3,0.1

Type RM Length L Ch R = 1 ,12270   ,555,555,555
BEGIN DESCRIPTION:
Cooperas Creek 8.0
END DESCRIPTION:
XS GIS Cut Line= 3
        2519875.     13815075.01        2519775.       13811975.
      2519075.02     13810375.04
#Sta/Elev= 30
  1913.9  365.09  2454.2  348.15  2664.3  345.93  2965.7  347.58  3064.2  346.13
  3486.3  341.84  3534.1  341.67    4085  337.79  4485.2  331.64  4525.3  327.84
  4569.4  328.92  4615.3  334.79  4635.3  334.74  4657.8  329.78  4705.4  332.63
  4748.8  331.39  4885.5  332.69  4915.5  323.75  4959.4  318.45  4960.4  317.95
  5011.6  318.45  5024.5  319.34  5037.3  328.26  5053.3  331.38  5122.2  331.56
  5874.3  330.75  6653.6     342  6677.4  340.39  6695.3  343.38  6761.9  344.58
#Mann= 12 ,-1 , 0
  1913.9     .07       0  2965.7    .035       0  3064.2     .07       0
  3486.3     .12       0  3534.1     .07       0  4569.4     .05       0
  4657.8     .07       0  4748.8      .1       0  4959.4     .05       0
  5011.6      .1       0  5122.2     .05       0  6653.6     .07       0
Bank Sta=4959.4,5011.6
XS Rating Curve= 0 ,0
Exp/Cntr=0.3,0.1

Type RM Length L Ch R = 1 ,11715   ,686,686,686
BEGIN DESCRIPTION:
Cooperas Creek 7.0
END DESCRIPTION:
XS GIS Cut Line= 3
        2520225.     13813324.99        2520175.       13811775.
      2519775.01     13810175.04
#Sta/Elev= 30
  3440.3  343.71  3870.5   338.8  4109.3  338.16  4207.9   336.4  4260.7  336.03
  4320.8  328.15  4340.8  333.76  4370.8  331.94  4487.9  330.37  4600.9  331.92
  4620.9  330.67  4650.9   323.4  4660.9  323.68  4680.9   329.7    4711  331.19
  4941.1  332.13  4971.1  328.52  4981.1  331.19  4988.1  317.88  4989.1  317.38
  5040.4  317.88  5050.4  319.92  5055.5  328.46    5062  330.94  5098.6  330.59
    5127  330.59  5466.4  329.89  5998.7   330.7  6269.3  333.81  6640.3  348.37
#Mann= 10 ,-1 , 0
  3440.3     .07       0  4109.3    .035       0  4207.9     .05       0
  4487.9      .1       0  4988.1     .05       0  5040.4      .1       0
    5062    .035       0  5098.6      .1       0    5127    .035       0
  5466.4     .05       0
Bank Sta=4988.1,5040.4
XS Rating Curve= 0 ,0
Exp/Cntr=0.3,0.1

Type RM Length L Ch R = 1 ,11029   ,941,941,941
BEGIN DESCRIPTION:
X18514
END DESCRIPTION:
XS GIS Cut Line= 4
      2520296.08     13813180.84       2520688.6     13811664.89
      2520417.89     13810852.75      2520120.46     13809838.79
#Sta/Elev= 30
  3022.7  344.26  3152.7  343.58  3462.6  336.75  3536.1  337.04  3797.3   332.4
  3824.1  330.62  3927.4  331.89  4350.3  328.36  4859.8   330.4  4915.3  331.27
  4936.9  327.89  4957.5  328.05  4963.2  326.06  4968.5  326.53    4974  316.17
    4975  315.67  5026.3  316.17  5026.5  330.43    5348     329  5400.2  330.22
  5421.3  327.51  5431.8  330.01  5449.5  329.49  5744.6  329.14  5921.8  334.27
  5974.6  338.41    6026  339.08  6171.9  346.19    6422  352.31  6501.4  352.58
#Mann= 6 ,-1 , 0
  3022.7     .07       0  3536.1     .05       0  4859.8      .1       0
    4974     .05       0  5026.3      .1       0  5449.5     .05       0
Bank Sta=4974,5026.3
XS Rating Curve= 0 ,0
Exp/Cntr=0.3,0.1

Type RM Length L Ch R = 1 ,10088   ,551,551,551
BEGIN DESCRIPTION:
Cooperas Creek 6.0
END DESCRIPTION:
XS GIS Cut Line= 3
        2520325.     13813174.99        2521125.       13811175.
        2521925.     13809575.01
#Sta/Elev= 30
  2846.3  344.73  2867.8  344.45  2898.8  344.29  3457.6  334.95  3707.9  331.04
  3847.9  332.07  3901.8   325.8  3962.4  329.89    3992  327.83  3998.7  330.43
  4304.6  328.44  4632.5  328.14  4875.9  328.94  4937.1  330.28  4955.9  328.13
  4959.4   314.9  4960.4   314.4  5011.7   314.9  5014.3  324.98  5031.1  329.94
  5103.6  329.51  5618.1  326.03  5969.9  327.77  6159.5  326.67  6372.7  331.09
  6400.7  336.54  6520.2  337.89  6596.3   339.6  6670.1  345.23  6789.2   349.4
#Mann= 14 ,-1 , 0
  2846.3     .07       0  2867.8     .05       0  2898.8     .07       0
  3457.6     .05       0  4304.6     .07       0  4632.5      .1       0
  4875.9     .07       0  4959.4     .05       0  5011.7     .07       0
  5103.6     .05       0  5969.9     .07       0  6159.5     .05       0
  6520.2    .035       0  6670.1     .05       0
Bank Sta=4959.4,5011.7
XS Rating Curve= 0 ,0
Exp/Cntr=0.3,0.1

Type RM Length L Ch R = 1 ,9537    ,540,540,540
BEGIN DESCRIPTION:
Cooperas Creek 5.0
END DESCRIPTION:
XS GIS Cut Line= 3
        2520425.       13813075.        2521425.       13811525.
      2522224.98     13809925.04
#Sta/Elev= 30
  3155.4  344.02  3250.6  343.03  3586.5  335.07    3741  333.61  3791.9     332
    3916  332.53  4103.4  330.68    4312  333.23  4523.8  328.72  4682.8  327.49
  4971.3  328.67  4977.2  327.74  4982.2  314.63  4983.2  314.13  5034.6  314.63
  5036.3  327.64  5044.7  328.72  5058.7  329.71  5214.7  328.37  5433.2  327.61
  5640.1  324.71  5715.5  326.56  5776.2  324.65  5841.3  323.69  6032.7  325.24
  6199.1  325.96  6331.9   331.1  6498.2  339.89  6644.2  344.34  6788.8  344.77
#Mann= 11 ,-1 , 0
  3155.4     .05       0  3586.5     .07       0    3741     .05       0
  4682.8      .1       0  4982.2     .05       0  5034.6      .1       0
  5214.7     .05       0  5776.2     .12       0  6032.7     .07       0
  6331.9     .12       0  6644.2     .05       0
Bank Sta=4982.2,5034.6
XS Rating Curve= 0 ,0
Exp/Cntr=0.3,0.1

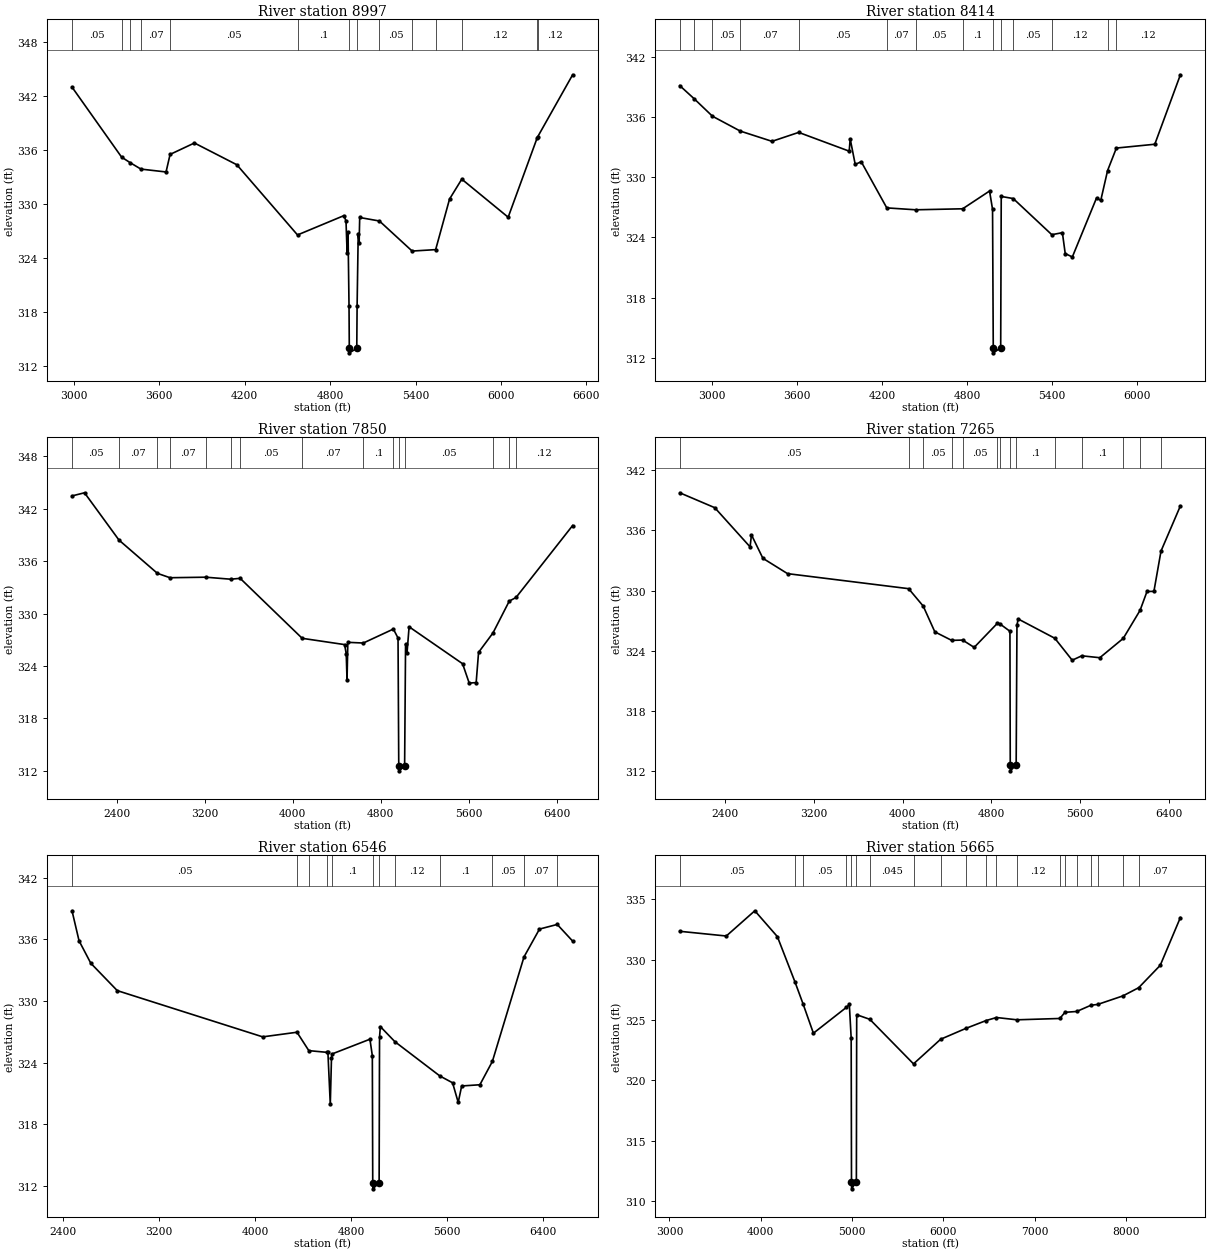
Type RM Length L Ch R = 1 ,8997    ,583,583,583
BEGIN DESCRIPTION:
Cooperas Creek 4.0
END DESCRIPTION:
XS GIS Cut Line= 3
        2520575.       13813075.        2521875.       13811525.
      2522224.99     13810075.04
#Sta/Elev= 30
  2988.4  342.98  3336.5   335.2  3396.9  334.58  3472.1  333.87  3648.6  333.55
  3676.9   335.5  3847.7  336.77  4145.6  334.35  4571.5  326.55  4897.6   328.7
  4911.9   328.1  4919.7  324.57  4926.2  326.86  4933.1  318.68  4935.1  313.95
  4936.2  313.45  4987.5  313.95  4989.9  318.69  4997.7  326.71  5004.2  325.71
  5008.1  328.49  5146.6   328.1  5376.2  324.76  5541.3  324.92  5638.9  330.54
  5724.7  332.75  6050.4  328.52  6253.8  337.33  6258.5  337.48    6503  344.35
#Mann= 14 ,-1 , 0
  2988.4     .05       0  3336.5     .07       0  3396.9     .05       0
  3472.1     .07       0  3676.9     .05       0  4571.5      .1       0
  4935.1     .05       0  4987.5      .1       0  5146.6     .05       0
  5376.2     .12       0  5541.3      .1       0  5724.7     .12       0
  6253.8     .07       0  6258.5     .12       0
Bank Sta=4935.1,4987.5
XS Rating Curve= 0 ,0
Exp/Cntr=0.3,0.1

Type RM Length L Ch R = 1 ,8414    ,564,564,564
BEGIN DESCRIPTION:
Cooperas Creek 3.0
END DESCRIPTION:
XS GIS Cut Line= 3
      2520774.99     13813175.01        2522375.       13811625.
        2522275.     13810325.03
#Sta/Elev= 30
  2772.5  339.12  2874.2  337.81  3003.3  336.07  3199.6  334.59  3423.2  333.57
  3611.4  334.46  3967.8  332.59  3974.7  333.82  4010.2  331.27  4052.6  331.54
  4232.9  326.94  4436.6  326.75  4768.1  326.85  4957.9  328.62    4979  326.79
    4984     313  4985.1   312.5  5036.4     313  5040.3  328.08  5124.8  327.87
    5397  324.27  5471.6  324.47  5491.6  322.39  5541.8  322.05  5712.3  327.92
  5742.4  327.69  5790.5  330.66  5852.5   332.9  6123.5  333.28    6304   340.2
#Mann= 14 ,-1 , 0
  2772.5     .05       0  2874.2     .07       0  3003.3     .05       0
  3199.6     .07       0  3611.4     .05       0  4232.9     .07       0
  4436.6     .05       0  4768.1      .1       0    4984     .05       0
  5036.4      .1       0  5124.8     .05       0    5397     .12       0
  5790.5      .1       0  5852.5     .12       0
Bank Sta=4984,5036.4
XS Rating Curve= 0 ,0
Exp/Cntr=0.3,0.1

Type RM Length L Ch R = 1 ,7850    ,585,585,585
BEGIN DESCRIPTION:
Cooperas Creek 2.0
END DESCRIPTION:
XS GIS Cut Line= 3
      2520474.99     13813525.01        2522875.       13811725.
      2522325.01     13810275.02
#Sta/Elev= 30
  1993.9  343.47  2107.5  343.83  2421.1  338.41  2770.3   334.6  2884.7   334.1
  3209.6  334.16  3436.7  333.93  3522.4  334.03  4086.2  327.16    4472  326.44
  4486.6  325.38  4493.9  322.35  4501.2   326.7  4641.8  326.62  4915.2  328.22
  4957.5  327.19  4964.1  312.58  4965.2  311.98  5017.4  312.58    5026  326.51
  5039.1  325.45  5058.1  328.48  5544.2  324.25  5604.5  322.03  5667.7  322.09
  5689.6  325.55  5820.8  327.78  5968.5  331.42  6030.3  331.84  6544.7  340.08
#Mann= 15 ,-1 , 0
  1993.9     .05       0  2421.1     .07       0  2770.3     .12       0
  2884.7     .07       0  3209.6     .05       0  3436.7     .07       0
  3522.4     .05       0  4086.2     .07       0  4641.8      .1       0
  4915.2     .05       0  4964.1     .05       0  5017.4     .05       0
  5820.8     .07       0  5968.5      .1       0  6030.3     .12       0
Bank Sta=4964.1,5017.4
XS Rating Curve= 0 ,0
Exp/Cntr=0.3,0.1

Type RM Length L Ch R = 1 ,7265    ,719,719,719
BEGIN DESCRIPTION:
Cooperas Creek 1.0
END DESCRIPTION:
XS GIS Cut Line= 3
        2522325.     13814524.99        2523425.       13811725.
      2523024.99     13810274.97
#Sta/Elev= 30
  1991.6  339.76  2307.3  338.27  2625.5  334.36  2637.9  335.56    2741  333.22
  2963.2  331.69  4054.4  330.19  4186.1  328.45  4290.8  325.88  4442.5  325.03
  4541.4  325.06  4645.4  324.33  4855.1  326.74  4875.4  326.69  4967.7  325.94
  4970.6  312.61  4971.7  312.01  5023.9  312.61    5031  326.52  5041.4  327.17
  5372.4  325.24    5529  323.05  5615.1  323.49  5777.9   323.3  5989.2  325.23
  6140.9  328.03  6203.2  329.91  6265.5  329.92  6329.4  333.94  6504.1  338.45
#Mann= 14 ,-1 , 0
  1991.6     .05       0  4054.4    .035       0  4186.1     .05       0
  4442.5    .035       0  4541.4     .05       0  4855.1     .07       0
  4875.4      .1       0  4970.6     .05       0  5023.9      .1       0
  5372.4     .12       0  5615.1      .1       0  5989.2     .05       0
  6140.9     .07       0  6329.4     .05       0
Bank Sta=4970.6,5023.9
XS Rating Curve= 0 ,0
Exp/Cntr=0.3,0.1

Type RM Length L Ch R = 1 ,6546    ,881,881,881
BEGIN DESCRIPTION:
X18513
END DESCRIPTION:
XS GIS Cut Line= 4
      2523422.79     13813965.99      2523977.76     13812152.18
      2524045.44     13811069.32      2523571.71     13809972.98
#Sta/Elev= 30
  2472.4  338.79  2531.1  335.87  2629.4  333.68  2849.9  331.02    4063  326.52
  4349.1  326.97  4447.8  325.18  4602.2  325.01  4606.9  325.04  4626.9  319.95
  4636.9  324.48  4644.7  324.87  4957.5  326.29  4977.6  324.69    4981  312.33
  4982.1  311.73  5034.3  312.33  5037.7  326.48  5044.5  327.52  5165.9  326.05
  5541.3  322.71    5647  322.05    5694  320.14  5722.9  321.74  5874.8  321.86
    5979  324.13  6242.8   334.3    6372  337.01    6520  337.46  6648.5  335.84
#Mann= 12 ,-1 , 0
  2472.4     .05       0  4349.1    .035       0  4447.8     .05       0
  4602.2     .07       0  4644.7      .1       0    4981     .05       0
  5034.3      .1       0  5165.9     .12       0  5541.3      .1       0
    5979     .05       0  6242.8     .07       0    6520     .05       0
Bank Sta=4981,5034.3
XS Rating Curve= 0 ,0
Exp/Cntr=0.3,0.1

Type RM Length L Ch R = 1 ,5665    ,963,963,963
BEGIN DESCRIPTION:
X18512
END DESCRIPTION:
XS GIS Cut Line= 4
      2524302.61     13813370.41      2524762.83     13812192.78
      2524465.04     13809986.47      2523219.94      13808430.1
#Sta/Elev= 30
  3112.7  332.35  3622.6  331.96  3934.8  334.05  4181.9  331.91  4374.6  328.16
  4463.2  326.34  4576.6  323.91    4938  326.05  4970.2  326.29  4990.4  323.51
  4993.9  311.62    4995  311.02  5047.3  311.62  5050.9  325.44  5194.6  325.06
  5673.2  321.37  5970.6  323.41  6247.3  324.31    6469  324.96  6582.2  325.21
  6806.1  325.02    7276  325.13    7332  325.64  7460.9  325.71  7618.1  326.23
  7689.6  326.29  7966.9     327  8139.9  327.68  8375.6  329.53  8596.5  333.49
#Mann= 20 ,-1 , 0
  3112.7     .05       0  4374.6    .035       0  4463.2     .05       0
    4938      .1       0  4993.9     .05       0  5047.3      .1       0
  5194.6    .045       0  5673.2      .1       0  5970.6     .07       0
  6247.3     .12       0    6469     .05       0  6582.2     .07       0
  6806.1     .12       0    7276     .07       0    7332     .12       0
  7460.9     .07       0  7618.1     .12       0  7689.6     .07       0
  7966.9     .12       0  8139.9     .07       0
Bank Sta=4993.9,5047.3
XS Rating Curve= 0 ,0
Exp/Cntr=0.3,0.1