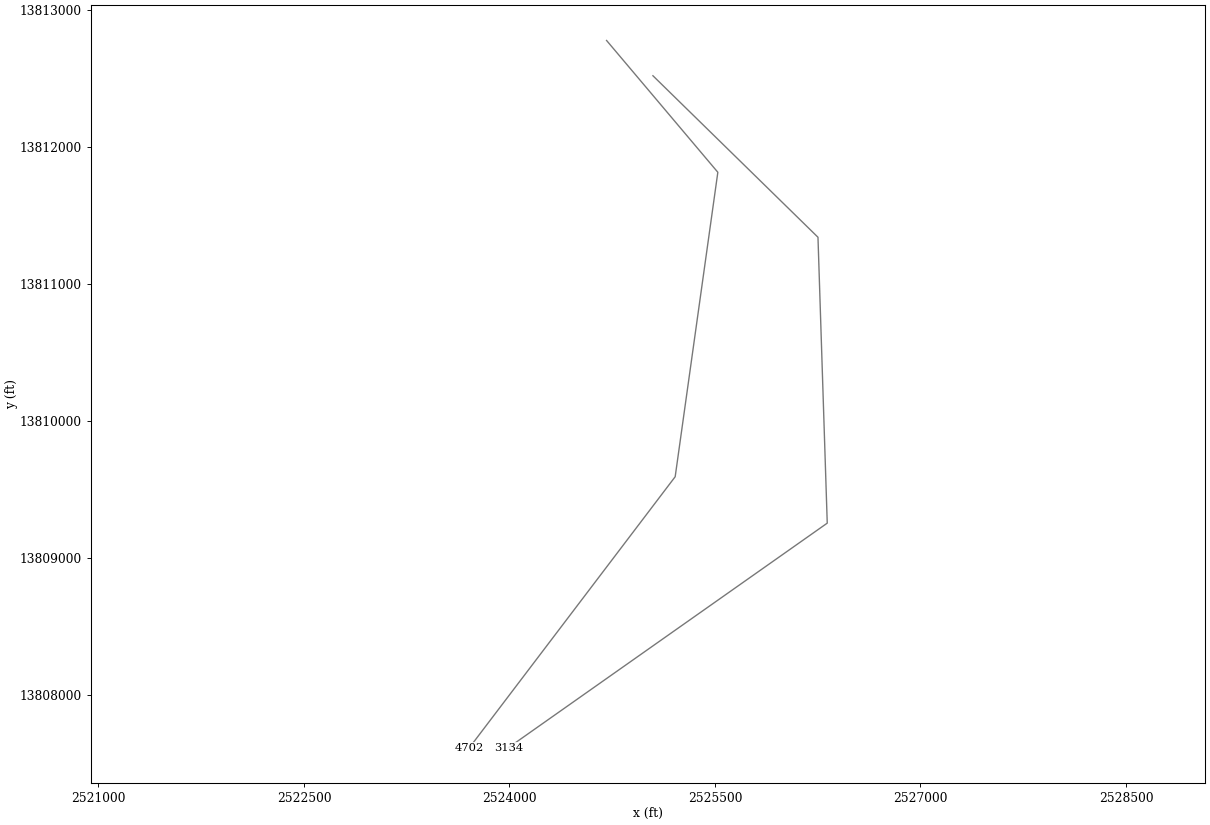
HEC-RAS study Copperas Creek.prj: Copperas Creek Base Level Engineering

--- Copperas Creek.g01 (geometry) --- (continued)

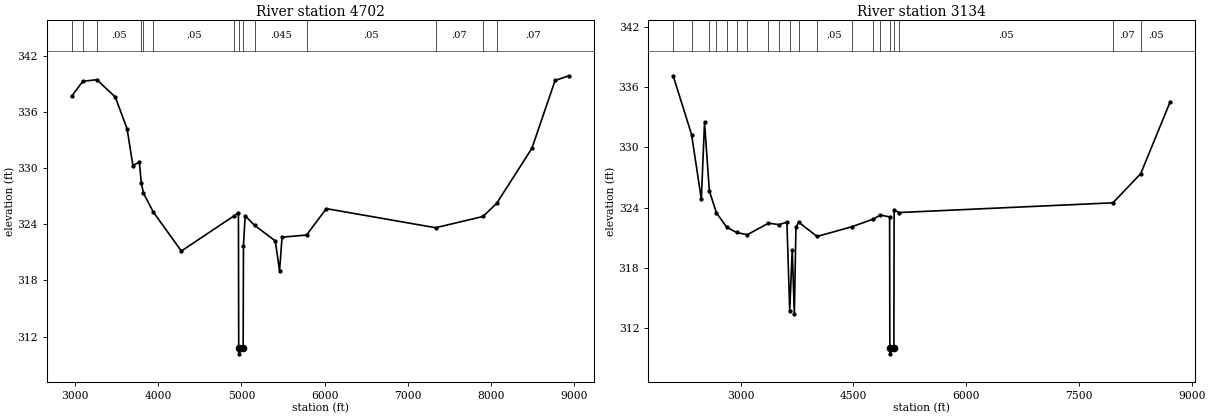
Type RM Length L Ch R = 1 ,4702    ,1568,1568,1568
BEGIN DESCRIPTION:
X18511
END DESCRIPTION:
XS GIS Cut Line= 4
      2524708.71     13812774.79      2525520.82     13811813.78
       2525209.5     13809593.94      2523707.93      13807618.9
#Sta/Elev= 30
  2958.8   337.7  3091.1  339.27  3259.7  339.44  3481.6  337.59  3623.3   334.2
  3693.6  330.27  3771.6  330.65  3793.6  328.45  3820.3  327.33  3938.6  325.31
  4276.4  321.14  4907.3  324.88    4963  325.22  4966.6  310.76  4967.7  310.16
    5020  310.76  5023.6  321.68  5043.8   324.9  5158.2  323.88  5407.3  322.22
  5457.8  319.02  5488.1  322.62  5782.8  322.85  6020.6  325.67  7335.1  323.63
  7904.9  324.83  8069.1  326.22  8494.3  332.12  8772.9  339.36  8939.6  339.86
#Mann= 14 ,-1 , 0
  2958.8     .05       0  3091.1    .035       0  3259.7     .05       0
  3793.6     .12       0  3820.3    .035       0  3938.6     .05       0
  4907.3     .12       0  4966.6     .05       0    5020     .12       0
  5158.2    .045       0  5782.8     .05       0  7335.1     .07       0
  7904.9     .12       0  8069.1     .07       0
Bank Sta=4966.6,5020
XS Rating Curve= 0 ,0
Exp/Cntr=0.3,0.1

Type RM Length L Ch R = 1 ,3134    ,0,0,0
BEGIN DESCRIPTION:
X18510
END DESCRIPTION:
XS GIS Cut Line= 4
      2525047.06     13812517.65      2526251.75     13811340.04
      2526319.42     13809255.55      2523992.89     13807618.86
#Sta/Elev= 30
  2100.4  337.14  2345.6  331.29  2475.5  324.84    2518  332.52  2582.1  325.67
  2676.1   323.5  2812.9  322.06  2943.5  321.54  3086.6  321.31  3368.4  322.46
    3510  322.32  3614.1  322.56  3651.7  313.74  3684.8  319.81  3713.1  313.44
  3734.3  322.07  3770.8  322.56  4015.6  321.14  4475.3   322.1  4758.5  322.85
  4856.9  323.27  4980.7  323.09  4983.8  310.05  4984.9  309.45  5037.6  310.05
  5040.8  323.78  5103.7  323.52  7952.2  324.49    8322  327.39  8715.2  334.57
#Mann= 20 ,-1 , 0
  2100.4     .05       0  2345.6     .12       0  2582.1    .035       0
  2676.1     .05       0  2812.9    .035       0  2943.5     .05       0
  3086.6    .035       0  3368.4     .05       0    3510     .12       0
  3651.7     .12       0  3770.8    .035       0  4015.6     .05       0
  4475.3     .05       0  4758.5     .12       0  4856.9      .1       0
  4983.8     .05       0  5037.6      .1       0  5103.7     .05       0
  7952.2     .07       0    8322     .05       0
Bank Sta=4983.8,5037.6
XS Rating Curve= 0 ,0
Exp/Cntr=0.3,0.1

Chan Stop Cuts=-1
Use User Specified Reach Order=0
Composite Channel Slope=5