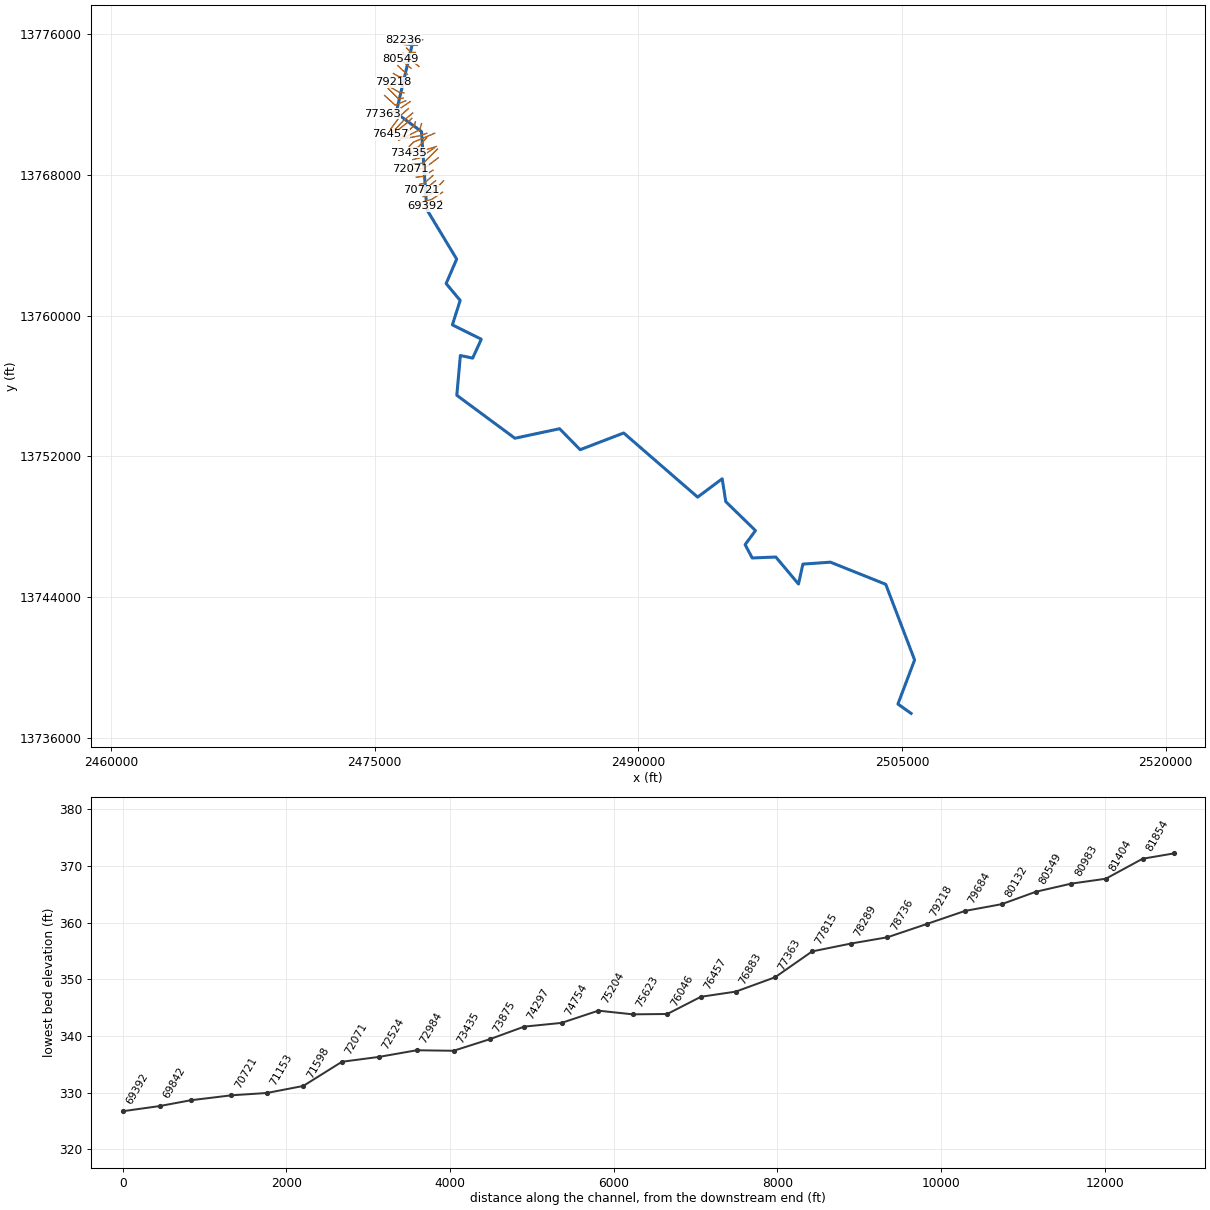
--- DENTON CREEK 2.prj (project) ---

Proj Title=DENTON CREEK 2 Base Level Engineering
Current Plan=p01
Default Exp/Contr=0.3,0.1
English Units
Geom File=g01
Flow File=f01
Plan File=p01
Y Axis Title=Elevation
X Axis Title(PF)=Main Channel Distance
X Axis Title(XS)=Station
BEGIN DESCRIPTION:
DENTON CREEK 2
END DESCRIPTION:
DSS Export Rating Curves= 0
DSS Export Rating Curve Sorted= 0
DSS Export Volume Flow Curves= 0
DXF OffsetX= 0
DXF OffsetY= 0
DXF ScaleX= 1
DXF ScaleY= 10

--- DENTON CREEK 2.p01 (plan) ---

Plan Title=Multiple Run
Program Version=4.10
Short Identifier=Multiple
Geom File=g01
Flow File=f01
Subcritical Flow
K Sum by GR= 0
Std Step Tol= 0.01
Critical Tol= 0.01
Num of Std Step Trials= 20
Max Error Tol= 0.3
Flow Tol Ratio= 0.001
Split Flow NTrial= 30
Split Flow Tol= 0.02
Split Flow Ratio= 0.02
Log Output Level= 0
Friction Slope Method= 1
Unsteady Friction Slope Method= 2
Unsteady Bridges Friction Slope Method= 1
Parabolic Critical Depth
Global Vel Dist= 1 , 1 , 1
Global Log Level= 0
CheckData=True
Encroach Param=-1 ,0,0, 0
BEGIN DESCRIPTION:
Multiple Run
END DESCRIPTION:
Computation Interval=1HOUR
Output Interval=1HOUR
Run HTab= 0
Run UNet= 0
Run PostProcess= 0
Run WQNet= 0
UNET Theta= 1
UNET Theta Warmup= 1
UNET ZTol= 0.02
UNET ZSATol= 0.05
UNET MxIter= 20
UNET MaxInSteps= 0
UNET DtIC= 0
UNET DtMin= 0
UNET MaxCRTS= 20
UNET WFStab= 2
UNET SFStab= 1
UNET WFX= 1
UNET SFX= 1
UNET DSS MLevel= 4
UNET DZMax Abort= 100
UNET Convert EG Bridges= 0
UNET Use Existing IB Tables=-1
UNET Froude Reduction=False
UNET Froude Limit= 1
UNET Froude Power= 10
UNET Time Slicing=0,0, 5
UNET Junction Losses=0
Instantaneous Interval=1HOUR
Write IC File= 0
Write IC File at Sim End=0
Echo Input=False
Echo Parameters=False
Echo Output=False
Write Detailed= 0
WQ AD Non Conservative
WQ ULTIMATE=-1
WQ Max Comp Step=1HOUR
WQ Output Interval=15MIN
WQ Output Selected Increments= 0
WQ Output face flow=0
WQ Output face velocity=0
WQ Output face area=0
WQ Output face dispersion=0
WQ Output cell volume=0
WQ Output cell surface area=0
WQ Output cell continuity=0
WQ Output cumulative cell continuity=0
WQ Output face conc=0
WQ Output face dconc_dx=0
WQ Output face courant=0
WQ Output face peclet=0
WQ Output face adv mass=0
WQ Output face disp mass=0
WQ Output cell mass=0
WQ Output cell source sink temp=0
WQ Output cell source sink nsm=0
WQ Output MaxMinRange=-1
WQ Daily Max Min Mean=-1
WQ Daily Range=0
WQ Daily Time=0
WQ Create Restart=0
WQ Fixed Restart=0
WQ System Summary=0
WQ Use Fixed Temperature=0
Sorting and Armoring Iterations= 10
XS Update Threshold= 0.02
Hydraulics Update Threshold= 0.02
Energy Slope Method= 1
Volume Change Method= 0
XS Weighting Method= 0
Number of US Weighted Cross Sections= 1
Number of DS Weighted Cross Sections= 1
Upstream XS Weight=0.25
Main XS Weight=0.5
Downstream XS Weight=0.25
Number of DS XS's Weighted with US Boundary= 1
Upstream Boundary Weight= 1
Weight of XSs Associated with US Boundary= 0
Number of US XS's Weighted with DS Boundary= 1
Downstream Boundary Weight= 0.5
Weight of XSs Associated with DS Boundary= 0.5
Sediment Output Level= 4
Mass or Volume Output= 0
Output Increment Type= 1
Profile and TS Output Increment= 10
XS Output Flag= 0
XS Output Increment= 10
Disregard all LS=0
Disregard all Conn=0
Disregard all Breaches=0
Disregard all Pumps=0

--- DENTON CREEK 2.f01 (steady flow) ---

Flow Title=Multiple
Number of Profiles=7
Profile Names=10-year,25-year,50-year,1pct_min,100-year,1pct_plu,500-year
River Rch & RM= DENTON CREEK 2,Reach-1,82236
     586     930    1235     795    1586    3164    2587
River Rch & RM= DENTON CREEK 2,Reach-1,77363
    1404    2330    3188    2106    4203    8386    7237
River Rch & RM= DENTON CREEK 2,Reach-1,69842
    1460    2418    3303    2177    4344    8667    7446
River Rch & RM= DENTON CREEK 2,Reach-1,61772
    2473    4191    5816    3888    7758   15479   13686
River Rch & RM= DENTON CREEK 2,Reach-1,52803
    2887    4922    6858    4601    9181   18319   16313
River Rch & RM= DENTON CREEK 2,Reach-1,51256
    3753    6428    8985    6043   12057   24056   21516
River Rch & RM= DENTON CREEK 2,Reach-1,36577
    4792    8248   11566    7797   15557   31041   27896
River Rch & RM= DENTON CREEK 2,Reach-1,23802
    5464    9375   13119    8820   17598   35112   31374
Boundary for River Rch & Prof#=DENTON CREEK 2,Reach-1,1
Up Type=0
Dn Type=3
Dn Slope=0.005
Boundary for River Rch & Prof#=DENTON CREEK 2,Reach-1,2
Up Type=0
Dn Type=3
Dn Slope=0.005
Boundary for River Rch & Prof#=DENTON CREEK 2,Reach-1,3
Up Type=0
Dn Type=3
Dn Slope=0.005
Boundary for River Rch & Prof#=DENTON CREEK 2,Reach-1,4
Up Type=0
Dn Type=3
Dn Slope=0.005
Boundary for River Rch & Prof#=DENTON CREEK 2,Reach-1,5
Up Type=0
Dn Type=3
Dn Slope=0.005
Boundary for River Rch & Prof#=DENTON CREEK 2,Reach-1,6
Up Type=0
Dn Type=3
Dn Slope=0.005
Boundary for River Rch & Prof#=DENTON CREEK 2,Reach-1,7
Up Type=0
Dn Type=3
Dn Slope=0.005

--- DENTON CREEK 2.g01 (geometry) ---

Geom Title=Existing Conditions
Program Version=4.10

River Reach=DENTON CREEK 2  ,Reach-1
Reach XY= 30
        2477225.       13775775.      2476226.96     13771530.88
       2477671.9     13770473.35      2477976.97     13766030.89
      2479673.05     13763219.11        2479075.       13761825.
      2479873.96     13760864.57      2479428.74     13759476.56
      2481074.77     13758659.78       2480584.7     13757585.77
      2479883.88     13757731.53      2479682.48     13755468.93
       2482985.5     13753026.22      2485528.21     13753567.13
        2486700.      13752374.6        2489175.       13753325.
      2493380.67     13749676.98      2494777.55     13750720.02
      2494982.76     13749418.83      2496671.47     13747773.55
       2496082.2      13746974.7      2496485.75     13746215.29
      2497827.51     13746270.05      2499118.33     13744733.96
      2499368.93     13745866.87      2500935.21      13745975.5
      2504081.17     13744717.14      2505723.78      13740414.5
      2504774.53     13737904.83        2505525.       13737375.

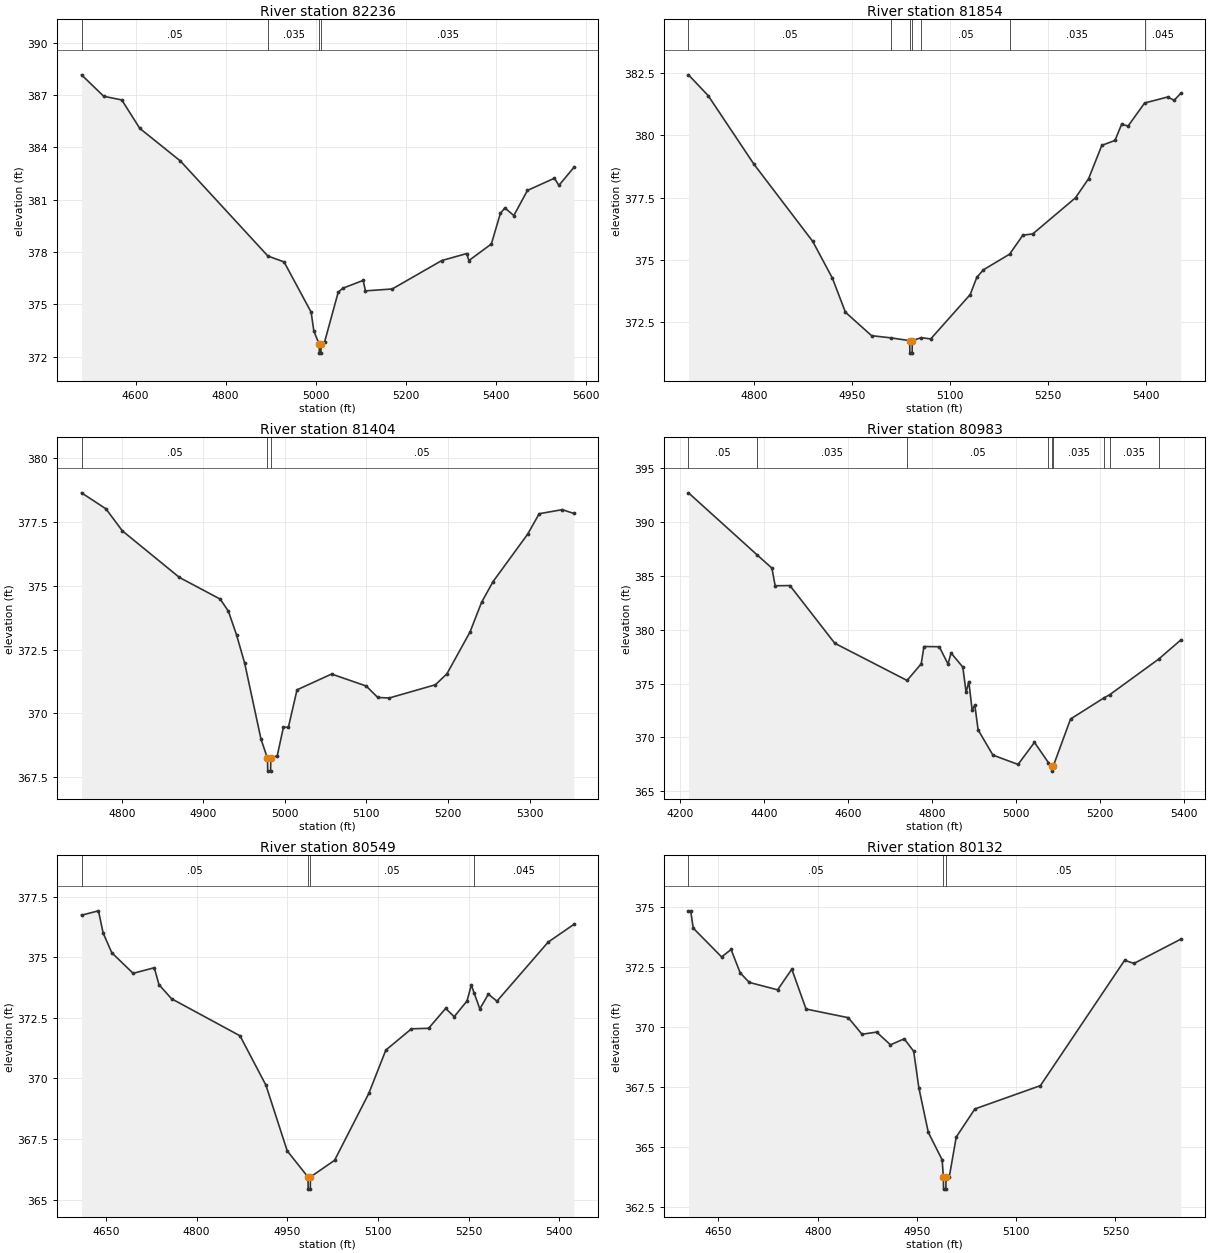
Type RM Length L Ch R = 1 ,82236   ,382,382,382
BEGIN DESCRIPTION:
DEN7
END DESCRIPTION:
XS GIS Cut Line= 3
      2477744.23     13775694.47      2477227.94     13775724.75
      2476651.86     13775699.64
#Sta/Elev= 30
    4480  388.16  4529.3  386.93  4569.4  386.72  4609.4  385.09  4699.6  383.22
    4894  377.77    4930  377.43  4990.1  374.55  4996.1  373.47  5008.1   372.7
  5008.4   372.2  5011.9   372.2  5012.1   372.7  5020.1  372.85  5050.2  375.69
  5060.2  375.92  5105.7  376.37  5110.8  375.77  5170.3  375.88  5280.4  377.51
  5335.7  377.91  5340.7  377.51  5390.5  378.46  5410.5  380.21  5420.5  380.53
  5440.5  380.09  5470.6  381.53  5530.6  382.23  5540.6  381.82  5573.8  382.85
#Mann= 4 ,-1 , 0
    4480     .05       0    4894    .035       0  5008.1    .035       0
  5012.1    .035       0
Bank Sta=5008.1,5012.1
XS Rating Curve= 0 ,0
Exp/Cntr=0.3,0.1

Type RM Length L Ch R = 1 ,81854   ,450,450,450
BEGIN DESCRIPTION:
DENTON CREEK 2 110.0
END DESCRIPTION:
XS GIS Cut Line= 3
        2477425.       13775375.        2477125.       13775375.
      2476674.97       13775425.
#Sta/Elev= 30
    4700  382.42    4730  381.59    4800  378.84    4890  375.74    4920  374.27
    4940   372.9    4980  371.96  5010.2  371.87  5038.2  371.76  5038.5  371.26
    5042  371.26  5042.2  371.76  5055.8  371.88  5070.4  371.83  5130.8  373.61
  5140.9   374.3  5150.9   374.6  5191.1  375.23  5211.3  375.99  5226.4  376.04
  5291.8  377.49  5311.9  378.26    5332  379.59  5352.2  379.79  5362.2  380.43
  5372.3  380.37  5397.5  381.29  5432.6  381.53  5442.7   381.4  5452.8  381.68
#Mann= 7 ,-1 , 0
    4700     .05       0  5010.2    .035       0  5038.2     .05       0
  5042.2    .035       0  5055.8     .05       0  5191.1    .035       0
  5397.5    .045       0
Bank Sta=5038.2,5042.2
XS Rating Curve= 0 ,0
Exp/Cntr=0.3,0.1

Type RM Length L Ch R = 1 ,81404   ,421,421,421
BEGIN DESCRIPTION:
DENTON CREEK 2 109.0
END DESCRIPTION:
XS GIS Cut Line= 3
      2477325.02       13774975.        2477075.       13774975.
      2476824.98     13775225.02
#Sta/Elev= 30
  4750.7  378.65  4780.7  378.02  4800.7  377.16  4870.7  375.33  4920.7  374.48
  4930.7  374.01  4940.7  373.08  4950.7  371.97  4970.7  368.99  4978.7  368.23
    4979  367.73  4982.5  367.73  4982.7  368.23  4990.7  368.34  4998.2  369.45
  5004.3  369.45  5014.9  370.92  5057.3  371.54  5099.7  371.07  5113.9  370.62
    5128   370.6  5184.6  371.12  5198.7  371.55    5227  373.19  5241.1  374.35
  5255.3  375.17  5297.7  377.03  5311.8  377.83  5340.1  377.99  5354.3  377.84
#Mann= 3 ,-1 , 0
  4750.7     .05       0  4978.7     .05       0  4982.7     .05       0
Bank Sta=4978.7,4982.7
XS Rating Curve= 0 ,0
Exp/Cntr=0.3,0.1

Type RM Length L Ch R = 1 ,80983   ,434,434,434
BEGIN DESCRIPTION:
DENTON CREEK 2 108.0
END DESCRIPTION:
XS GIS Cut Line= 3
      2477524.97     13774175.02        2476925.       13774675.
        2476625.       13774925.
#Sta/Elev= 30
  4220.3  392.71  4383.3  386.96  4418.8  385.72  4426.6  384.08  4461.7   384.1
  4568.5  378.74  4740.4  375.29  4774.1  376.83  4780.6  378.44  4817.1  378.42
  4837.9  376.81  4845.1  377.84  4873.1  376.53  4880.9  374.18  4887.4  375.19
  4895.2  372.57  4901.7  372.99  4909.5   370.7  4944.7  368.36  5004.5  367.49
  5043.6  369.54  5076.8  367.66  5084.6  367.37  5084.8  366.87  5088.6  367.37
  5129.5  371.71  5208.1  373.65  5222.8  373.97  5339.4  377.28  5391.8  379.05
#Mann= 9 ,-1 , 0
  4220.3     .05       0  4383.3    .035       0  4740.4     .05       0
  5076.8    .035       0  5084.6     .05       0  5088.6    .035       0
  5208.1    .045       0  5222.8    .035       0  5339.4    .045       0
Bank Sta=5084.6,5088.6
XS Rating Curve= 0 ,0
Exp/Cntr=0.3,0.1

Type RM Length L Ch R = 1 ,80549   ,417,417,417
BEGIN DESCRIPTION:
DENTON CREEK 2 107.0
END DESCRIPTION:
XS GIS Cut Line= 3
      2477074.99     13774075.01        2476775.       13774325.
      2476474.98     13774625.02
#Sta/Elev= 30
  4609.5  376.74  4637.5  376.92  4645.3     376  4659.6  375.19  4694.8  374.34
  4729.9  374.57  4737.7  373.87  4758.5  373.29  4871.8  371.76  4914.7  369.72
  4949.9  367.01  4984.3  365.93  4984.6  365.43  4988.1  365.43  4988.3  365.93
  5028.3  366.62  5084.9  369.38  5113.1  371.17  5155.6  372.05  5183.9  372.07
  5212.1  372.89  5226.3  372.55  5247.5   373.2  5254.6  373.86  5259.1  373.54
  5268.7  372.87  5282.8  373.48    5297  373.19  5381.8  375.63  5424.3  376.36
#Mann= 4 ,-1 , 0
  4609.5     .05       0  4984.3     .05       0  4988.3     .05       0
  5259.1    .045       0
Bank Sta=4984.3,4988.3
XS Rating Curve= 0 ,0
Exp/Cntr=0.3,0.1

Type RM Length L Ch R = 1 ,80132   ,448,448,448
BEGIN DESCRIPTION:
DENTON CREEK 2 106.0
END DESCRIPTION:
XS GIS Cut Line= 3
        2476875.       13773725.        2476575.       13773975.
      2476324.98     13774225.02
#Sta/Elev= 30
  4604.7  374.83    4608  374.83  4611.9  374.11  4654.8  372.91  4669.1  373.22
  4682.8  372.25  4696.5  371.85  4739.4  371.54  4760.9   372.4  4782.4  370.74
  4846.2  370.38    4867  369.69  4889.1  369.78    4910  369.25  4930.8   369.5
  4945.1  368.98  4952.9  367.46  4967.2   365.6  4988.1  364.46    4990  363.74
  4990.2  363.24  4993.7  363.24    4994  363.74  4998.8  363.74  5009.4  365.41
  5037.6  366.58  5136.6  367.55  5263.9  372.77  5278.1  372.64  5348.8  373.65
#Mann= 3 ,-1 , 0
  4604.7     .05       0    4990     .05       0    4994     .05       0
Bank Sta=4990,4994
XS Rating Curve= 0 ,0
Exp/Cntr=0.3,0.1

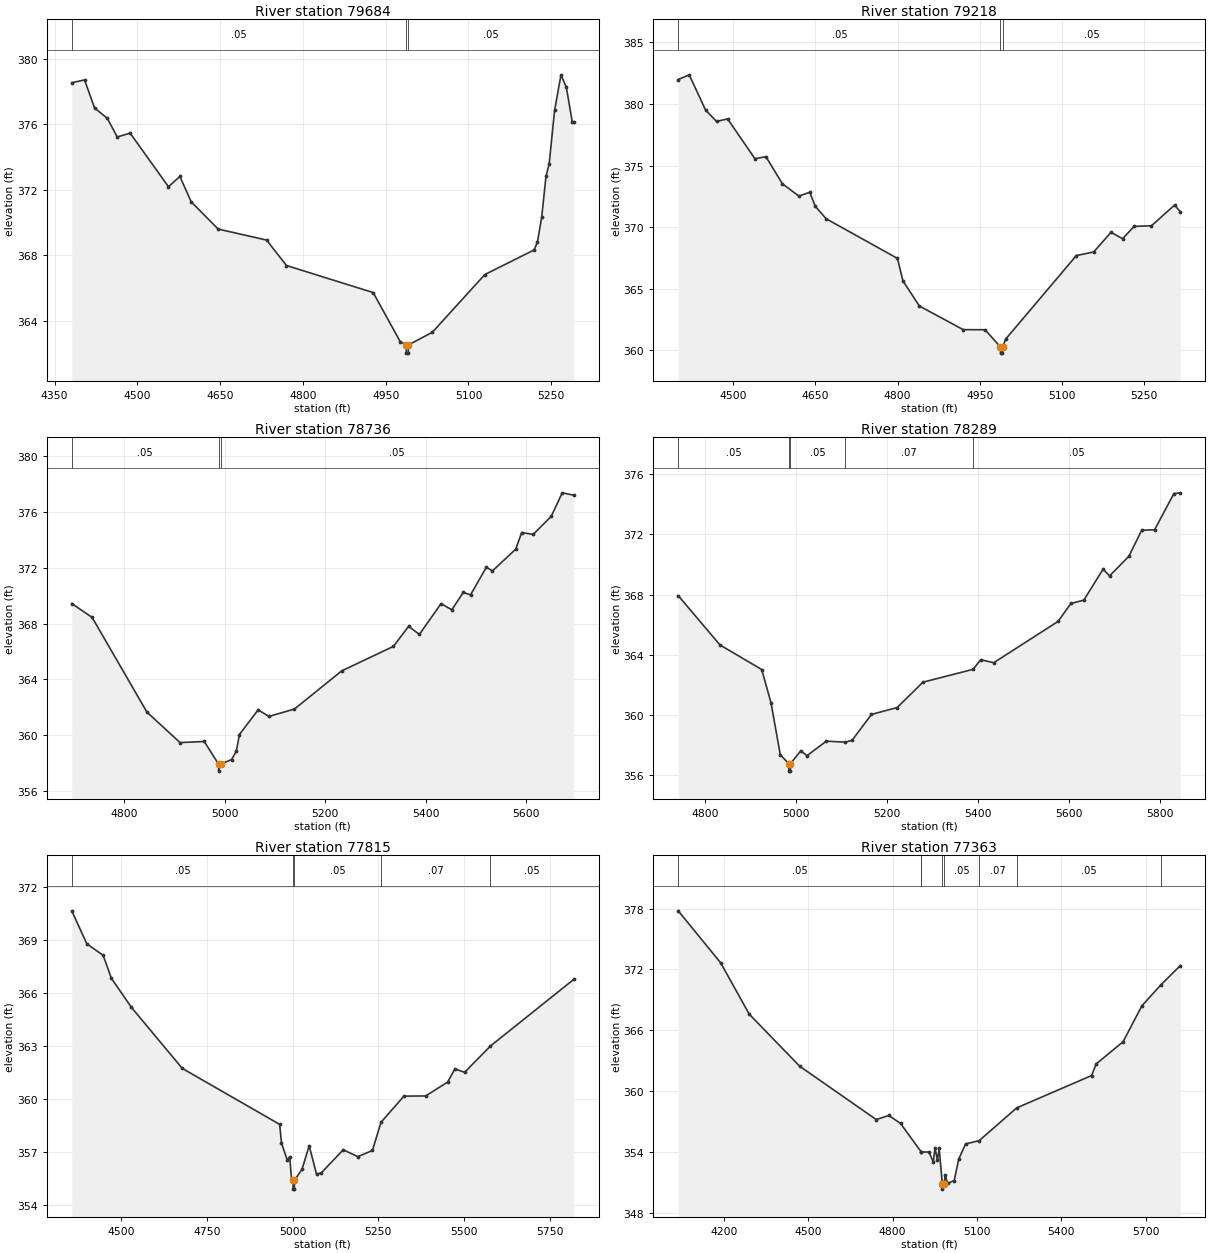
Type RM Length L Ch R = 1 ,79684   ,466,466,466
BEGIN DESCRIPTION:
DENTON CREEK 2 105.0
END DESCRIPTION:
XS GIS Cut Line= 3
      2476925.02     13773474.99        2476325.       13773625.
      2476075.03     13773774.98
#Sta/Elev= 30
    4381  378.53  4404.2   378.7  4422.3  376.99  4445.4  376.36  4463.5  375.22
  4486.7  375.46  4556.3  372.19  4576.9  372.82  4597.5  371.27  4646.4  369.61
  4734.1  368.94  4770.1  367.39  4927.3  365.74  4976.3  362.75  4987.2  362.55
  4987.4  362.05  4990.9  362.05  4991.2  362.55  5034.5  363.32  5129.7  366.84
  5219.1  368.34    5225  368.82  5232.7  370.32  5240.5  372.82  5246.3  373.59
  5256.1  376.84  5267.7  379.01  5277.4  378.25  5288.1  376.15    5291  376.15
#Mann= 3 ,-1 , 0
    4381     .05       0  4987.2     .05       0  4991.2     .05       0
Bank Sta=4987.2,4991.2
XS Rating Curve= 0 ,0
Exp/Cntr=0.3,0.1

Type RM Length L Ch R = 1 ,79218   ,482,482,482
BEGIN DESCRIPTION:
DENTON CREEK 2 104.0
END DESCRIPTION:
XS GIS Cut Line= 3
        2476975.       13773175.        2476375.       13773175.
      2476075.03     13773274.99
#Sta/Elev= 30
  4399.6  381.99  4419.6  382.37  4449.6   379.5  4469.6  378.58  4489.6  378.79
  4539.6  375.55  4559.6  375.72  4589.6  373.52  4619.6  372.52  4639.6  372.82
  4649.6  371.69  4669.6  370.67  4799.6  367.45  4809.6  365.63  4839.6  363.58
  4919.6  361.66  4959.6  361.65  4987.6  360.25  4987.8  359.75  4991.3  359.75
  4991.6  360.25  4997.1  360.89  5126.1  367.68  5157.7  367.97  5189.3  369.57
  5210.4  369.05  5231.5  370.05  5263.1   370.1  5305.3  371.78  5315.8  371.24
#Mann= 3 ,-1 , 0
  4399.6     .05       0  4987.6     .05       0  4991.6     .05       0
Bank Sta=4987.6,4991.6
XS Rating Curve= 0 ,0
Exp/Cntr=0.3,0.1

Type RM Length L Ch R = 1 ,78736   ,447,447,447
BEGIN DESCRIPTION:
DENTON CREEK 2 103.0
END DESCRIPTION:
XS GIS Cut Line= 3
      2476674.97       13772675.        2476375.       13772725.
      2475775.03     13773074.98
#Sta/Elev= 30
  4695.9  369.44  4736.4  368.44  4845.4  361.64  4911.3  359.45  4959.5  359.53
  4987.9   357.9  4988.1   357.4  4991.9   357.9  5013.7  358.23  5023.2  358.83
  5029.4  360.03  5066.6   361.8  5088.1  361.33  5138.9  361.86  5232.8   364.6
  5335.7  366.36  5365.9   367.8  5387.4  367.22  5430.4  369.43  5451.9  368.99
  5474.7  370.24  5489.1  370.06  5520.6  372.05  5532.6  371.78  5578.9  373.34
  5590.9  374.54  5613.6   374.4  5649.6   375.7  5671.5  377.39  5694.6  377.22
#Mann= 3 ,-1 , 0
  4695.9     .05       0  4987.9     .05       0  4991.9     .05       0
Bank Sta=4987.9,4991.9
XS Rating Curve= 0 ,0
Exp/Cntr=0.3,0.1

Type RM Length L Ch R = 1 ,78289   ,474,474,474
BEGIN DESCRIPTION:
DENTON CREEK 2 102.0
END DESCRIPTION:
XS GIS Cut Line= 3
      2476624.97     13772374.99        2476375.       13772325.
      2475775.03     13772924.97
#Sta/Elev= 30
  4741.2  367.93  4832.9  364.66  4924.7  363.03  4945.1  360.82  4965.5  357.38
  4983.9  356.79  4984.2  356.29  4987.7  356.29  4987.9  356.79  5010.3  357.63
  5024.4  357.32  5066.8  358.28  5108.6  358.21  5123.4  358.34  5165.8  360.05
  5222.4  360.51    5279  362.19  5388.9  363.04  5406.2  363.68  5434.5  363.48
  5575.9  366.22  5604.2  367.41  5632.5  367.63  5674.9  369.69  5689.1  369.24
  5731.5  370.54  5759.8  372.27  5788.1   372.3  5830.5   374.7  5844.6  374.75
#Mann= 5 ,-1 , 0
  4741.2     .05       0  4983.9     .05       0  4987.9     .05       0
  5108.6     .07       0  5388.9     .05       0
Bank Sta=4983.9,4987.9
XS Rating Curve= 0 ,0
Exp/Cntr=0.3,0.1

Type RM Length L Ch R = 1 ,77815   ,452,452,452
BEGIN DESCRIPTION:
DENTON CREEK 2 101.0
END DESCRIPTION:
XS GIS Cut Line= 3
      2476774.99       13772225.        2476175.       13771975.
      2475575.02     13772524.98
#Sta/Elev= 30
  4356.4  370.67  4400.3   368.8  4447.9  368.15  4471.8  366.85  4530.3   365.2
  4678.7  361.74  4962.5  358.57  4967.9  357.52  4984.7  356.54  4991.8  356.74
  4997.2  355.46  5001.7   355.4  5001.9   354.9  5005.4   354.9  5005.7   355.4
  5027.7  356.02  5048.6  357.36  5070.2  355.74  5084.4  355.83  5147.9  357.13
  5190.5  356.74    5233  357.09  5258.1  358.69  5324.9  360.17  5388.4  360.18
  5452.5  360.97  5473.5  361.71  5501.8  361.52  5577.2  363.01  5820.3  366.79
#Mann= 5 ,-1 , 0
  4356.4     .05       0  5001.7     .05       0  5005.7     .05       0
  5258.1     .07       0  5577.2     .05       0
Bank Sta=5001.7,5005.7
XS Rating Curve= 0 ,0
Exp/Cntr=0.3,0.1

Type RM Length L Ch R = 1 ,77363   ,480,480,480
BEGIN DESCRIPTION:
DENTON CREEK 2 100.0
END DESCRIPTION:
XS GIS Cut Line= 3
      2477025.02     13772175.01        2476225.       13771625.
      2475424.99       13771475.
#Sta/Elev= 30
  4038.3  377.78  4189.2  372.65  4290.7  367.59    4470  362.46  4742.2   357.2
  4786.6   357.6  4828.5  356.82  4901.8  354.02  4902.3     354    4930     354
  4944.9  353.01    4951  354.39  4959.8   353.2  4965.8  354.36  4977.2  350.84
  4977.7  350.34  4984.2  350.84  4986.8  351.76  4995.6  350.92  5019.3  351.17
  5035.4  353.31    5060   354.8  5108.1  355.12  5241.4  358.35  5507.7  361.54
  5523.8  362.68  5619.6  364.87  5686.6  368.42    5755  370.51  5823.1  372.38
#Mann= 8 ,-1 , 0
  4038.3     .05       0  4901.8     .07       0  4902.3     .05       0
  4977.2     .05       0  4984.2     .05       0  5108.1     .07       0
  5241.4     .05       0    5755     .07       0
Bank Sta=4977.2,4984.2
XS Rating Curve= 0 ,0
Exp/Cntr=0.3,0.1

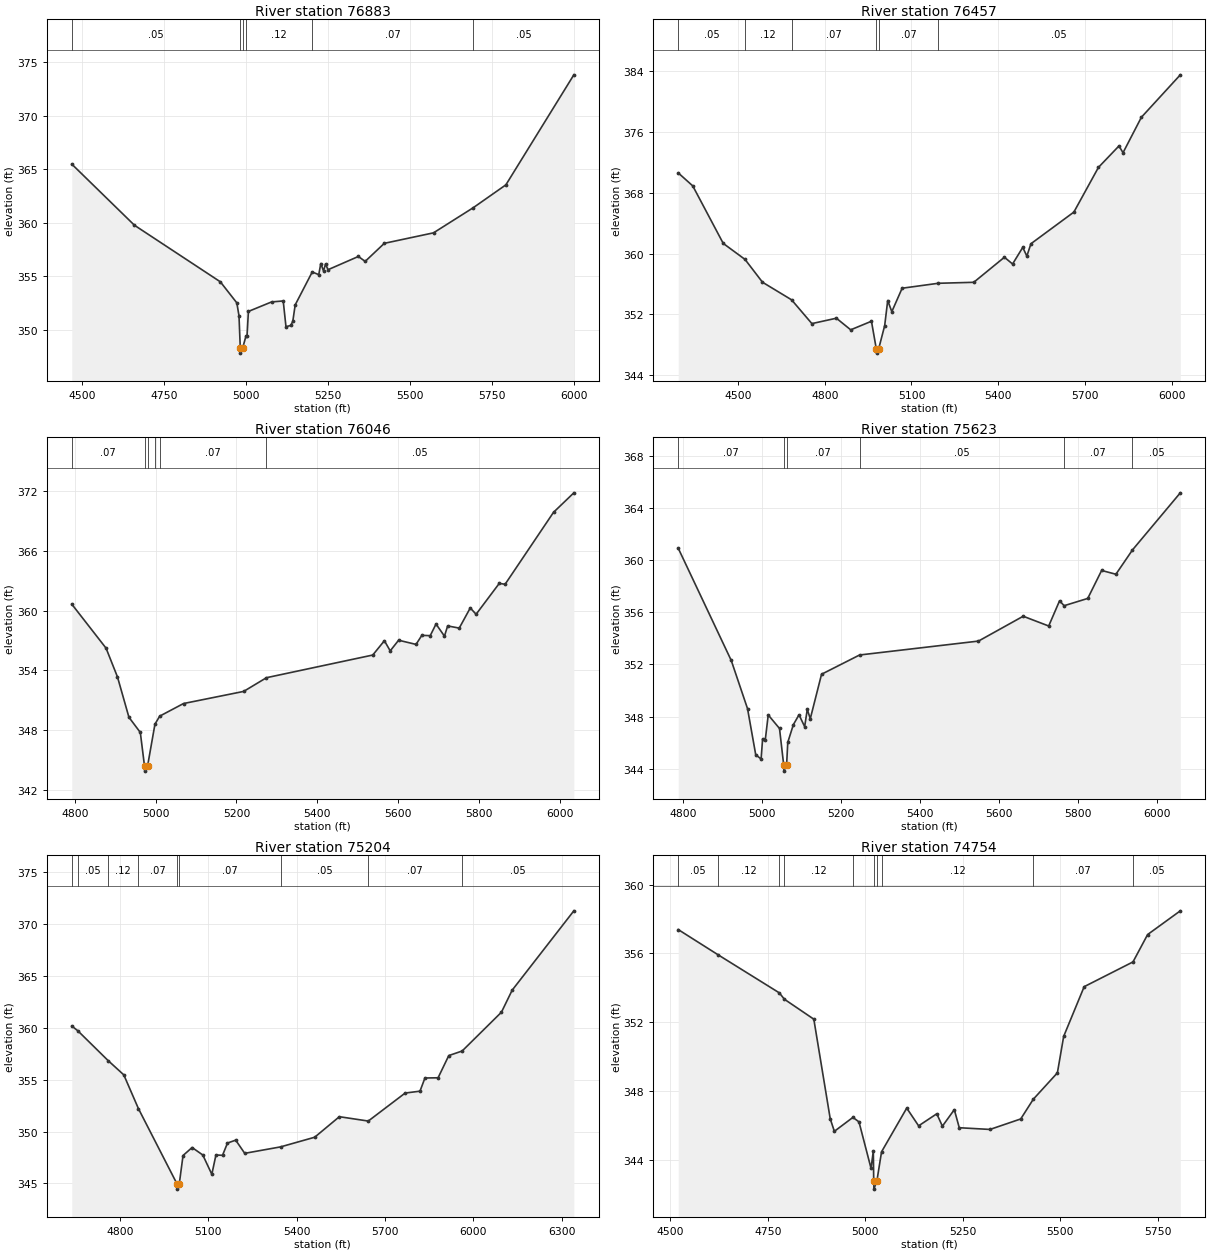
Type RM Length L Ch R = 1 ,76883   ,426,426,426
BEGIN DESCRIPTION:
DENTON CREEK 2 99.0
END DESCRIPTION:
XS GIS Cut Line= 3
      2476924.98     13771774.99        2476525.       13771425.
      2475924.99     13770624.99
#Sta/Elev= 30
  4468.8  365.49    4660  359.77    4922  354.48  4972.3  352.51  4978.9   351.3
  4982.8  348.31  4983.3  347.81  4990.2  348.31  5000.3  349.41  5003.4  349.41
  5007.6  351.71  5078.4   352.6  5113.8  352.69  5122.2  350.28  5136.7   350.4
    5143  350.78  5150.3  352.32  5202.3   355.4  5222.2  355.15  5228.4  356.19
  5236.7   355.5    5243  356.16  5250.3  355.61    5343  356.85  5363.8  356.39
  5422.2  358.08  5572.2  359.06  5693.4  361.41    5793  363.55  6000.3  373.84
#Mann= 6 ,-1 , 0
  4468.8     .05       0  4982.8     .05       0  4990.2     .05       0
  5000.3     .12       0  5202.3     .07       0  5693.4     .05       0
Bank Sta=4982.8,4990.2
XS Rating Curve= 0 ,0
Exp/Cntr=0.3,0.1

Type RM Length L Ch R = 1 ,76457   ,411,411,411
BEGIN DESCRIPTION:
DENTON CREEK 2 98.0
END DESCRIPTION:
XS GIS Cut Line= 3
      2477174.98     13771524.99        2476625.       13771075.
      2475925.02     13770325.02
#Sta/Elev= 30
  4293.3  370.64  4343.5  368.93    4449  361.35  4524.4  359.24  4584.7  356.24
  4685.4  353.92  4755.5  350.79  4840.3   351.5  4889.8  349.97  4961.6   351.1
  4978.6   347.4  4979.1   346.9  4986.1   347.4  5007.3  350.52  5017.8  353.83
    5032  352.36  5067.7  355.45  5192.4   356.1  5315.4  356.23  5421.4  359.53
  5449.7  358.64  5484.9  360.83    5499  359.68  5513.2  361.31  5661.7  365.48
  5746.7  371.37  5817.6  374.19  5831.7   373.3  5895.2  377.97  6029.8  383.56
#Mann= 6 ,-1 , 0
  4293.3     .05       0  4524.4     .12       0  4685.4     .07       0
  4978.6     .05       0  4986.1     .07       0  5192.4     .05       0
Bank Sta=4978.6,4986.1
XS Rating Curve= 0 ,0
Exp/Cntr=0.3,0.1

Type RM Length L Ch R = 1 ,76046   ,423,423,423
BEGIN DESCRIPTION:
DENTON CREEK 2 97.0
END DESCRIPTION:
XS GIS Cut Line= 3
      2477125.02     13771225.02        2476975.       13771075.
      2476175.03     13770425.03
#Sta/Elev= 30
  4792.5  360.66  4877.4  356.23  4905.7  353.33    4934  349.28  4962.2  347.75
  4972.6  344.36  4973.1  343.86  4980.1  344.36  4998.4  348.58  5010.1  349.39
  5069.1  350.66    5218  351.88  5274.5  353.26  5537.6  355.54  5566.4  356.98
  5580.8  355.96  5601.6  357.03  5644.7  356.61  5659.1  357.52  5679.9  357.49
  5694.2  358.66  5715.1  357.44    5723  358.47  5751.7  358.25    5779  360.28
  5793.4  359.64  5850.8  362.75  5865.2  362.66  5985.1   369.9  6035.4  371.86
#Mann= 6 ,-1 , 0
  4792.5     .07       0  4972.6     .05       0  4980.1     .07       0
  4998.4     .05       0  5010.1     .07       0  5274.5     .05       0
Bank Sta=4972.6,4980.1
XS Rating Curve= 0 ,0
Exp/Cntr=0.3,0.1

Type RM Length L Ch R = 1 ,75623   ,419,419,419
BEGIN DESCRIPTION:
DENTON CREEK 2 96.0
END DESCRIPTION:
XS GIS Cut Line= 3
        2477325.       13771025.        2477275.       13770825.
      2476474.98     13770124.98
#Sta/Elev= 30
  4788.6  360.94  4922.6  352.31  4963.8   348.6  4984.5  345.06  4998.1  344.73
  5001.9  346.29  5008.5  346.17  5016.1  348.12  5044.6  347.08  5055.1   344.3
  5055.6   343.8  5062.6   344.3  5065.5  346.01  5079.7  347.38  5093.9  348.13
  5108.2  347.22  5114.8  348.55  5122.4  347.83  5150.9  351.25    5247  352.73
  5547.6   353.8  5660.6  355.71  5725.1  354.96  5752.6   356.9  5764.1  356.52
  5823.8  357.08  5858.9  359.23    5895  358.94  5936.9  360.81  6057.8   365.2
#Mann= 6 ,-1 , 0
  4788.6     .07       0  5055.1     .05       0  5062.6     .07       0
    5247     .05       0  5764.1     .07       0  5936.9     .05       0
Bank Sta=5055.1,5062.6
XS Rating Curve= 0 ,0
Exp/Cntr=0.3,0.1

Type RM Length L Ch R = 1 ,75204   ,450,450,450
BEGIN DESCRIPTION:
DENTON CREEK 2 95.0
END DESCRIPTION:
XS GIS Cut Line= 3
      2477675.01     13770925.04        2477575.       13770575.
      2476374.99     13769974.99
#Sta/Elev= 30
    4636  360.17  4656.2  359.72  4759.4  356.84  4812.8  355.46  4862.6   352.2
  4993.6  344.95  4994.1  344.45  5001.2  344.95    5014  347.69  5044.8  348.46
  5081.1  347.74  5111.8  345.88  5125.8  347.74  5148.2  347.71    5165  348.89
  5192.9  349.17  5223.6   347.9  5345.2  348.52  5461.2  349.45  5545.1  351.43
  5643.3  351.01  5768.7  353.71    5819  353.89  5835.8  355.16  5880.5  355.18
  5916.8  357.32  5962.2  357.76  6095.7   361.5  6132.1  363.62  6341.7  371.27
#Mann= 9 ,-1 , 0
    4636     .07       0  4656.2     .05       0  4759.4     .12       0
  4862.6     .07       0  4993.6     .05       0  5001.2     .07       0
  5345.2     .05       0  5643.3     .07       0  5962.2     .05       0
Bank Sta=4993.6,5001.2
XS Rating Curve= 0 ,0
Exp/Cntr=0.3,0.1

Type RM Length L Ch R = 1 ,74754   ,457,457,457
BEGIN DESCRIPTION:
DENTON CREEK 2 94.0
END DESCRIPTION:
XS GIS Cut Line= 3
      2477975.02     13770375.01        2477525.       13770225.
        2476725.       13770075.
#Sta/Elev= 30
    4520  357.38  4622.5  355.91  4779.4   353.7  4792.4  353.33  4867.9  352.17
    4910  346.38  4920.6  345.65  4968.2  346.46  4983.8   346.2  5014.7   343.5
  5020.6  344.51  5021.6  342.79  5022.1  342.29  5029.9  342.79  5041.7  344.46
  5106.3     347  5136.8  345.97  5183.4  346.67  5197.8  345.95  5228.4  346.91
  5241.1  345.86  5319.9  345.76  5398.8  346.37  5431.2  347.52  5492.9  349.05
    5509  351.17  5561.6  354.06  5686.9   355.5  5724.4  357.09  5808.3  358.47
#Mann= 10 ,-1 , 0
    4520     .05       0  4622.5     .12       0  4779.4     .07       0
  4792.4     .12       0  4968.2     .07       0  5021.6     .05       0
  5029.9     .07       0  5041.7     .12       0  5431.2     .07       0
  5686.9     .05       0
Bank Sta=5021.6,5029.9
XS Rating Curve= 0 ,0
Exp/Cntr=0.3,0.1

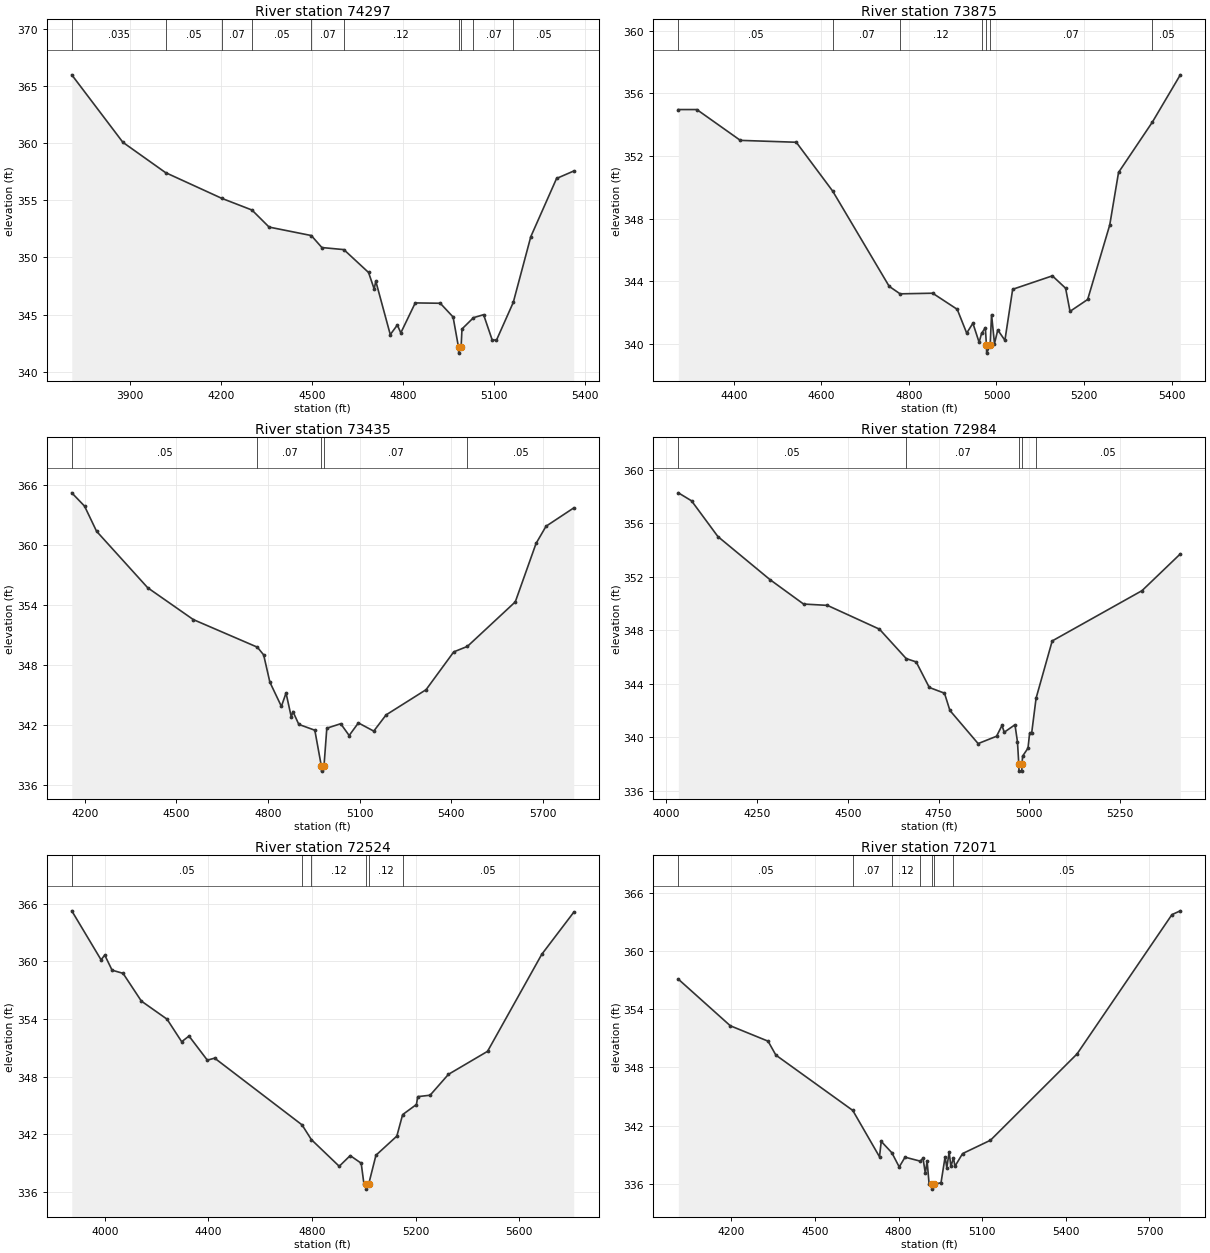
Type RM Length L Ch R = 1 ,74297   ,422,422,422
BEGIN DESCRIPTION:
DENTON CREEK 2 93.0
END DESCRIPTION:
XS GIS Cut Line= 3
      2478424.99       13770375.        2477225.       13769875.
      2476975.03     13769625.03
#Sta/Elev= 30
  3708.4  365.96  3876.8  360.06  4017.4  357.41  4202.7  355.16    4302  354.14
  4358.4  352.65  4497.4  351.91  4532.3  350.86  4604.7  350.68  4686.1  348.68
  4704.5  347.24  4709.9  347.92  4757.6  343.25  4780.9  344.09  4792.3   343.4
  4839.9  346.02  4922.3  345.99  4964.5  344.79  4982.5  342.13    4983  341.63
  4990.9  342.13  4993.8  343.74  5031.7  344.73    5065  344.99  5093.2  342.79
  5107.4  342.76  5162.7  346.06  5220.5  351.81  5305.4   356.9  5361.9  357.55
#Mann= 10 ,-1 , 0
  3708.4    .035       0  4017.4     .05       0  4202.7     .07       0
    4302     .05       0  4497.4     .07       0  4604.7     .12       0
  4982.5     .05       0  4990.9     .12       0  5031.7     .07       0
  5162.7     .05       0
Bank Sta=4982.5,4990.9
XS Rating Curve= 0 ,0
Exp/Cntr=0.3,0.1

Type RM Length L Ch R = 1 ,73875   ,440,440,440
BEGIN DESCRIPTION:
DENTON CREEK 2 92.0
END DESCRIPTION:
XS GIS Cut Line= 3
      2477975.01     13770125.01        2477475.       13769575.
      2477075.03       13769525.
#Sta/Elev= 30
  4273.5  354.97  4315.7  354.97  4415.1     353  4542.8  352.88  4625.9  349.76
    4755  343.67  4779.9  343.19  4854.3  343.23  4910.4   342.2    4932  340.68
  4946.2  341.31  4960.4  340.09    4966  340.66  4974.6  341.03  4977.1   339.9
  4977.6   339.4  4985.6   339.9  4988.8  341.86  4995.5  340.01    5003  340.88
  5019.3  340.22    5037  343.48  5127.7  344.34  5157.9  343.55    5168  342.07
  5208.3  342.83  5258.7  347.59  5278.8  350.95  5356.1  354.17  5419.9  357.19
#Mann= 7 ,-1 , 0
  4273.5     .05       0  4625.9     .07       0  4779.9     .12       0
    4966     .07       0  4977.1     .05       0  4985.6     .07       0
  5356.1     .05       0
Bank Sta=4977.1,4985.6
XS Rating Curve= 0 ,0
Exp/Cntr=0.3,0.1

Type RM Length L Ch R = 1 ,73435   ,451,451,451
BEGIN DESCRIPTION:
DENTON CREEK 2 91.0
END DESCRIPTION:
XS GIS Cut Line= 3
      2478524.97     13769624.99        2477725.       13769375.
      2476925.05     13769275.01
#Sta/Elev= 30
  4157.3  365.19  4199.2  363.86  4238.5  361.35  4406.1   355.7  4555.4  352.52
  4765.3  349.76  4785.9  348.99  4806.3  346.26    4844  343.84  4859.2  345.18
  4876.5  342.77  4881.7  343.33  4901.1  342.04  4953.5  341.46  4974.9  337.87
  4975.4  337.37  4983.5  337.87  4992.8  341.66  5038.3  342.11    5066  340.93
  5096.2  342.19  5146.6  341.37  5186.9  342.99  5317.9  345.51  5408.6  349.29
  5453.4  349.84  5610.2  354.29  5678.2  360.13  5710.9  361.85  5801.6  363.68
#Mann= 5 ,-1 , 0
  4157.3     .05       0  4765.3     .07       0  4974.9     .05       0
  4983.5     .07       0  5453.4     .05       0
Bank Sta=4974.9,4983.5
XS Rating Curve= 0 ,0
Exp/Cntr=0.3,0.1

Type RM Length L Ch R = 1 ,72984   ,460,460,460
BEGIN DESCRIPTION:
DENTON CREEK 2 90.0
END DESCRIPTION:
XS GIS Cut Line= 3
      2478374.99     13769524.99        2477575.       13768975.
      2477175.02       13768875.
#Sta/Elev= 30
    4033  358.28  4069.4  357.68  4141.9  355.01  4285.3  351.79    4378  349.96
  4443.7  349.86  4587.1  348.08  4660.8  345.88  4688.3  345.63  4724.4  343.72
  4766.3  343.29  4781.2     342    4859  339.52  4909.8  340.07  4924.7  340.88
    4931  340.37  4960.5  340.93  4967.4  339.65  4971.1  337.96  4971.6  337.46
  4979.3  337.46  4979.8  337.96  4981.5  338.58  4996.4  339.18  5000.8  340.28
  5006.4  340.28  5018.7  342.92  5063.1   347.2  5310.5  350.96  5416.1  353.71
#Mann= 5 ,-1 , 0
    4033     .05       0  4660.8     .07       0  4971.1     .05       0
  4979.8     .07       0  5018.7     .05       0
Bank Sta=4971.1,4979.8
XS Rating Curve= 0 ,0
Exp/Cntr=0.3,0.1

Type RM Length L Ch R = 1 ,72524   ,453,453,453
BEGIN DESCRIPTION:
DENTON CREEK 2 89.0
END DESCRIPTION:
XS GIS Cut Line= 3
      2478575.01     13769475.01        2477775.       13768675.
      2476975.01       13768575.
#Sta/Elev= 30
  3872.8  365.27  3985.9  360.17  4000.1  360.66  4028.4  359.09  4070.8  358.76
  4141.5  355.87  4240.5  353.99  4297.1  351.64  4325.4  352.23  4396.1  349.72
  4424.4  349.93  4761.7  342.98  4797.6  341.45  4905.2  338.67  4947.6  339.78
    4990  338.99  5000.6  336.83  5009.9  336.79  5010.4  336.29  5018.7  336.79
    5047  339.82  5127.6  341.81    5150  344.05  5203.2   345.1  5208.3  345.92
  5256.1  346.07  5326.7  348.24  5477.8  350.64    5687  360.74  5810.4  365.12
#Mann= 6 ,-1 , 0
  3872.8     .05       0  4761.7     .07       0  4797.6     .12       0
  5009.9     .05       0  5018.7     .12       0    5150     .05       0
Bank Sta=5009.9,5018.7
XS Rating Curve= 0 ,0
Exp/Cntr=0.3,0.1

Type RM Length L Ch R = 1 ,72071   ,473,473,473
BEGIN DESCRIPTION:
DENTON CREEK 2 88.0
END DESCRIPTION:
XS GIS Cut Line= 3
      2478624.99     13768974.99        2477825.       13768375.
      2477025.04       13768325.
#Sta/Elev= 30
  4009.3  357.11  4195.7   352.3  4331.2  350.71  4359.3  349.27  4635.2  343.56
  4731.2  338.77  4737.4  340.36  4775.4  339.19    4802  337.72  4822.8  338.73
  4877.3  338.32  4887.4  338.61  4895.7  337.05    4902  338.35  4909.3  335.93
  4918.3  335.93  4918.8  335.43  4927.3  335.93    4952  336.09  4966.6  338.76
  4972.8  337.65  4981.2  339.27  4987.4  337.77  4996.7  338.66    5002  337.79
  5029.3   339.1  5129.5  340.48  5440.1  349.39  5780.8  363.78  5810.8  364.17
#Mann= 7 ,-1 , 0
  4009.3     .05       0  4635.2     .07       0  4775.4     .12       0
  4877.3     .07       0  4918.3     .05       0  4927.3     .07       0
  4996.7     .05       0
Bank Sta=4918.3,4927.3
XS Rating Curve= 0 ,0
Exp/Cntr=0.3,0.1

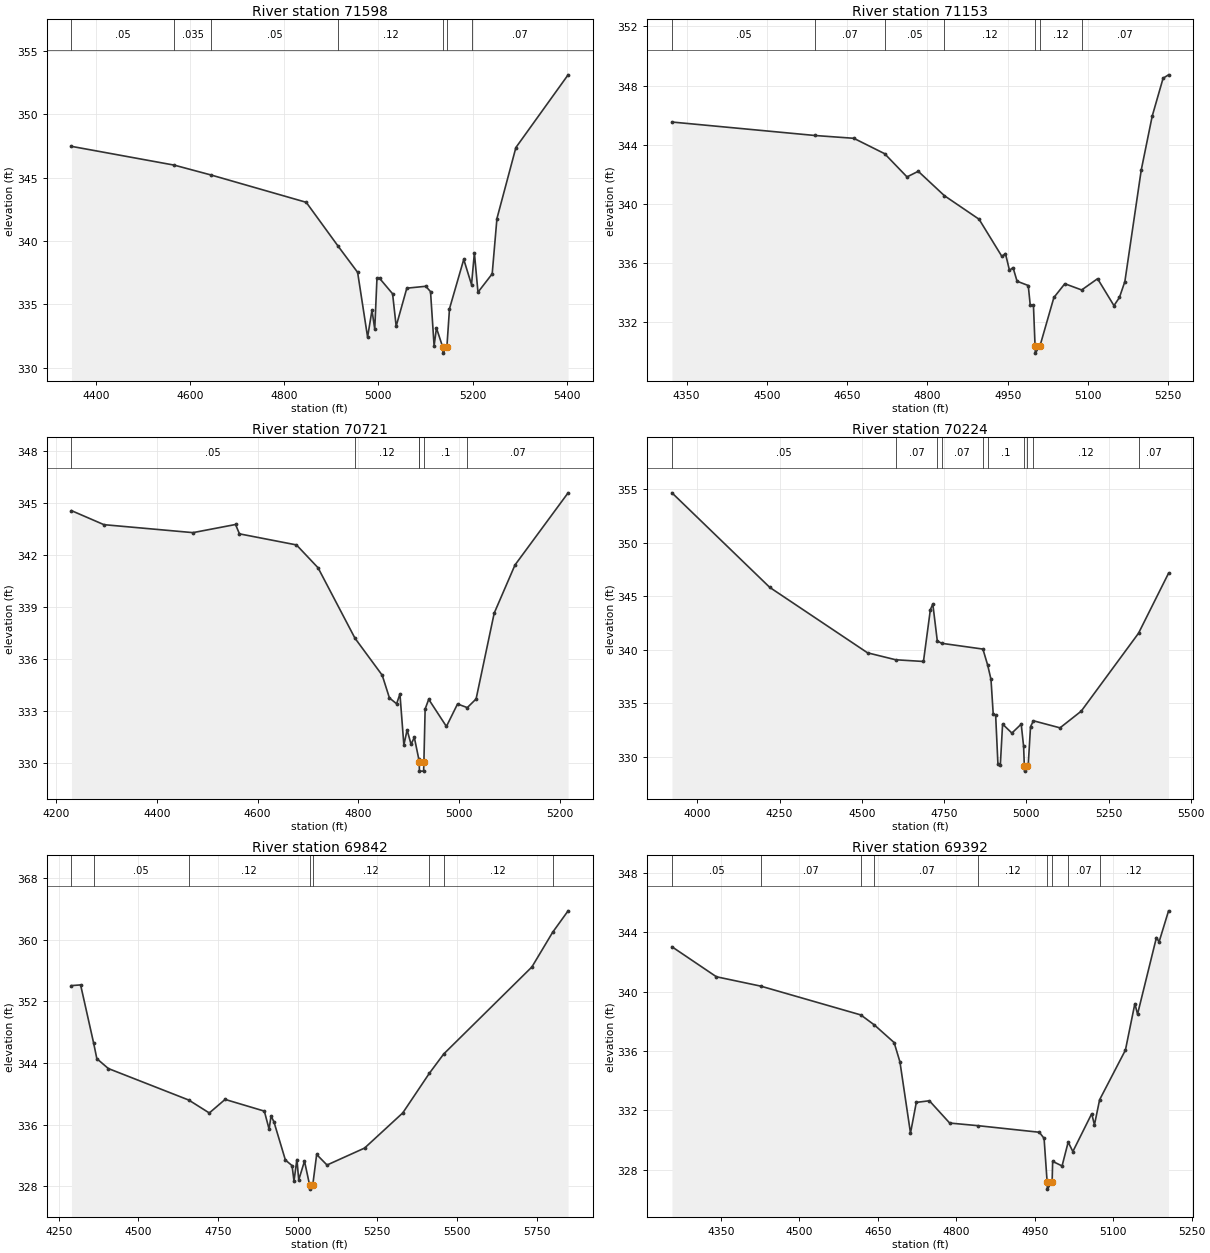
Type RM Length L Ch R = 1 ,71598   ,445,445,445
BEGIN DESCRIPTION:
DENTON CREEK 2 87.0
END DESCRIPTION:
XS GIS Cut Line= 3
      2478325.04     13768275.02        2477775.       13767925.
      2477374.98       13767875.
#Sta/Elev= 30
    4348  347.46  4566.4  345.98  4644.8   345.2  4846.7  343.05  4914.9  339.57
  4955.9  337.53  4977.1  332.42  4986.4  334.54  4992.3  333.06    4997  337.06
  5002.5  337.06  5030.2  335.84  5037.8  333.28  5060.4  336.28  5100.7  336.43
  5110.8  336.01  5118.4  331.73  5123.4  333.14  5136.5  331.66    5137  331.16
  5145.6  331.66  5151.1  334.66  5181.4  338.55  5197.9  336.56    5204  339.06
  5211.6  335.96  5241.8  337.41  5251.9  341.77  5292.2  347.37  5403.1   353.1
#Mann= 7 ,-1 , 0
    4348     .05       0  4566.4    .035       0  4644.8     .05       0
  4914.9     .12       0  5136.5     .05       0  5145.6     .12       0
  5197.9     .07       0
Bank Sta=5136.5,5145.6
XS Rating Curve= 0 ,0
Exp/Cntr=0.3,0.1

Type RM Length L Ch R = 1 ,71153   ,432,432,432
BEGIN DESCRIPTION:
DENTON CREEK 2 86.0
END DESCRIPTION:
XS GIS Cut Line= 3
      2478325.02     13767975.02        2477825.       13767525.
      2477574.96     13767474.99
#Sta/Elev= 30
  4322.8  345.54  4589.8  344.63  4662.5  344.44  4720.1   343.4  4761.9  341.83
  4782.9  342.21  4831.8  340.56  4896.5  338.97  4939.1  336.46  4945.8  336.65
  4953.3  335.52    4960   335.7  4967.5  334.78  4988.4  334.49  4992.1  333.17
  4998.1  333.17  5001.1  330.42  5001.6  329.92  5010.4  330.42  5036.3  333.68
  5056.7  334.61  5088.2  334.19  5117.9  334.95  5148.5  333.13  5158.7  333.68
  5168.9  334.76  5199.5   342.3  5219.9  345.93  5240.3   348.5  5250.5  348.73
#Mann= 7 ,-1 , 0
  4322.8     .05       0  4589.8     .07       0  4720.1     .05       0
  4831.8     .12       0  5001.1     .05       0  5010.4     .12       0
  5088.2     .07       0
Bank Sta=5001.1,5010.4
XS Rating Curve= 0 ,0
Exp/Cntr=0.3,0.1

Type RM Length L Ch R = 1 ,70721   ,497,497,497
BEGIN DESCRIPTION:
DENTON CREEK 2 85.0
END DESCRIPTION:
XS GIS Cut Line= 3
      2478475.04     13767675.03        2477875.       13767175.
      2477675.03     13767125.01
#Sta/Elev= 30
  4229.9  344.56  4294.4  343.75  4471.4  343.29    4556  343.76  4563.8  343.22
  4677.1  342.58    4720  341.26  4793.4  337.19  4847.6  335.05  4861.9  333.74
  4876.2   333.4  4882.8  333.97  4890.6  331.02  4897.1  331.89  4904.9  331.06
  4911.4  331.46  4920.3   330.2  4921.1  330.01  4921.6  329.51  4929.9  329.51
  4930.4  330.01  4932.9   333.1    4940  333.66  4975.2  332.09  4997.3  333.39
  5016.7  333.18  5034.2  333.68  5070.2  338.64  5111.5  341.42  5217.1  345.59
#Mann= 6 ,-1 , 0
  4229.9     .05       0  4793.4     .12       0  4920.3      .1       0
  4921.1     .05       0  4930.4      .1       0  5016.7     .07       0
Bank Sta=4921.1,4930.4
XS Rating Curve= 0 ,0
Exp/Cntr=0.3,0.1

Type RM Length L Ch R = 1 ,70224   ,382,382,382
BEGIN DESCRIPTION:
DENTON CREEK 2 84.0
END DESCRIPTION:
XS GIS Cut Line= 3
      2478925.03     13767675.03        2478175.       13766875.
      2477775.04     13766775.01
#Sta/Elev= 30
    3923  354.68  4220.3  345.83  4517.3  339.71  4602.8  339.06  4687.2   338.9
  4708.2  343.75  4715.6  344.28  4729.2  340.83  4742.5   340.6  4867.8  340.06
  4882.3  338.56  4892.4  337.22  4899.2  333.95  4906.5   333.9  4913.4  329.34
  4920.7  329.18  4927.6  333.04  4955.9   332.2  4984.2  333.04  4991.5  330.95
  4993.7  329.14  4994.2  328.64  5003.1  329.14  5005.7  329.31  5012.5   332.8
  5021.4  333.35  5102.1  332.69  5166.5  334.25  5340.6  341.54  5431.9  347.16
#Mann= 10 ,-1 , 0
    3923     .05       0  4602.8     .07       0  4729.2     .05       0
  4742.5     .07       0  4867.8     .12       0  4882.3      .1       0
  4993.7     .05       0  5003.1      .1       0  5021.4     .12       0
  5340.6     .07       0
Bank Sta=4993.7,5003.1
XS Rating Curve= 0 ,0
Exp/Cntr=0.3,0.1

Type RM Length L Ch R = 1 ,69842   ,450,450,450
BEGIN DESCRIPTION:
DENTON CREEK 2 83.0
END DESCRIPTION:
XS GIS Cut Line= 3
      2478875.02     13767025.01        2478275.       13766625.
      2477474.98     13766374.99
#Sta/Elev= 30
  4289.8  354.04  4318.4  354.13  4359.2   346.6  4369.4  344.55  4405.5  343.27
  4657.9  339.18  4722.5   337.5  4772.1  339.26  4895.3  337.74  4910.3  335.39
  4916.3   337.1  4925.3  336.37  4961.4  331.39  4982.4  330.66  4988.4  328.65
  4997.4  331.45  5003.4  328.81  5021.4  331.25  5037.6  328.11  5038.1  327.61
  5047.2  328.11  5059.6  332.11  5092.1  330.74    5210  332.94    5330  337.51
  5413.2  342.64  5458.5  345.16  5735.4  356.46  5800.5  360.96  5849.1  363.75
#Mann= 8 ,-1 , 0
  4289.8     .07       0  4359.2     .05       0  4657.9     .12       0
  5037.6     .05       0  5047.2     .12       0  5413.2     .07       0
  5458.5     .12       0  5800.5     .07       0
Bank Sta=5037.6,5047.2
XS Rating Curve= 0 ,0
Exp/Cntr=0.3,0.1

Type RM Length L Ch R = 1 ,69392   ,468,468,468
BEGIN DESCRIPTION:
DENTON CREEK 2 82.0
END DESCRIPTION:
XS GIS Cut Line= 3
      2478775.03     13766525.01        2478075.       13766275.
      2477874.99       13766225.
#Sta/Elev= 30
  4256.2  343.02  4341.2     341  4425.9  340.37  4617.3  338.43  4643.4  337.75
    4681  336.57  4692.1  335.27  4712.3  330.47  4723.4  332.54  4748.4  332.65
  4787.2  331.15  4842.1  330.97  4958.6  330.53  4967.7  330.12  4973.5   327.2
    4974   326.7  4983.1   327.2  4984.1  328.57  5002.1  328.26  5013.8  329.87
  5022.7  329.23  5058.8  331.78    5064  331.03  5073.9  332.72  5123.2  336.06
  5141.3  339.19  5146.4  338.48  5182.5  343.64  5187.6  343.35  5205.7  345.44
#Mann= 9 ,-1 , 0
  4256.2     .05       0  4425.9     .07       0  4617.3     .12       0
  4643.4     .07       0  4842.1     .12       0  4973.5     .05       0
  4983.1     .12       0  5013.8     .07       0  5073.9     .12       0
Bank Sta=4973.5,4983.1
XS Rating Curve= 0 ,0
Exp/Cntr=0.3,0.1