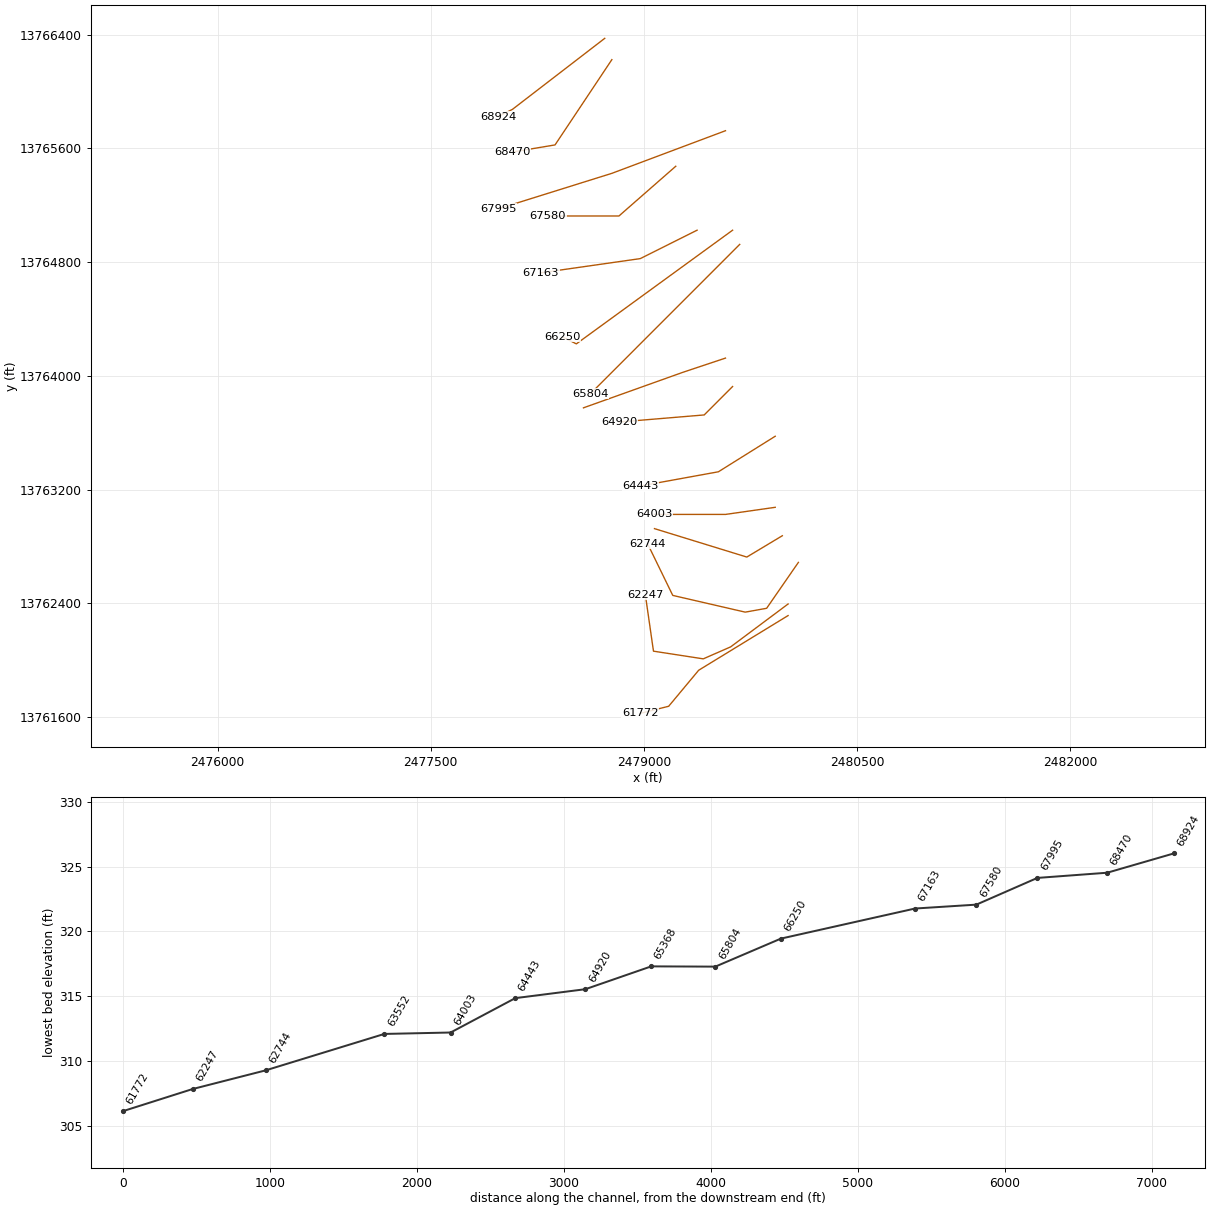
HEC-RAS study DENTON CREEK 2.prj: DENTON CREEK 2 Base Level Engineering

--- DENTON CREEK 2.g01 (geometry) --- (continued)

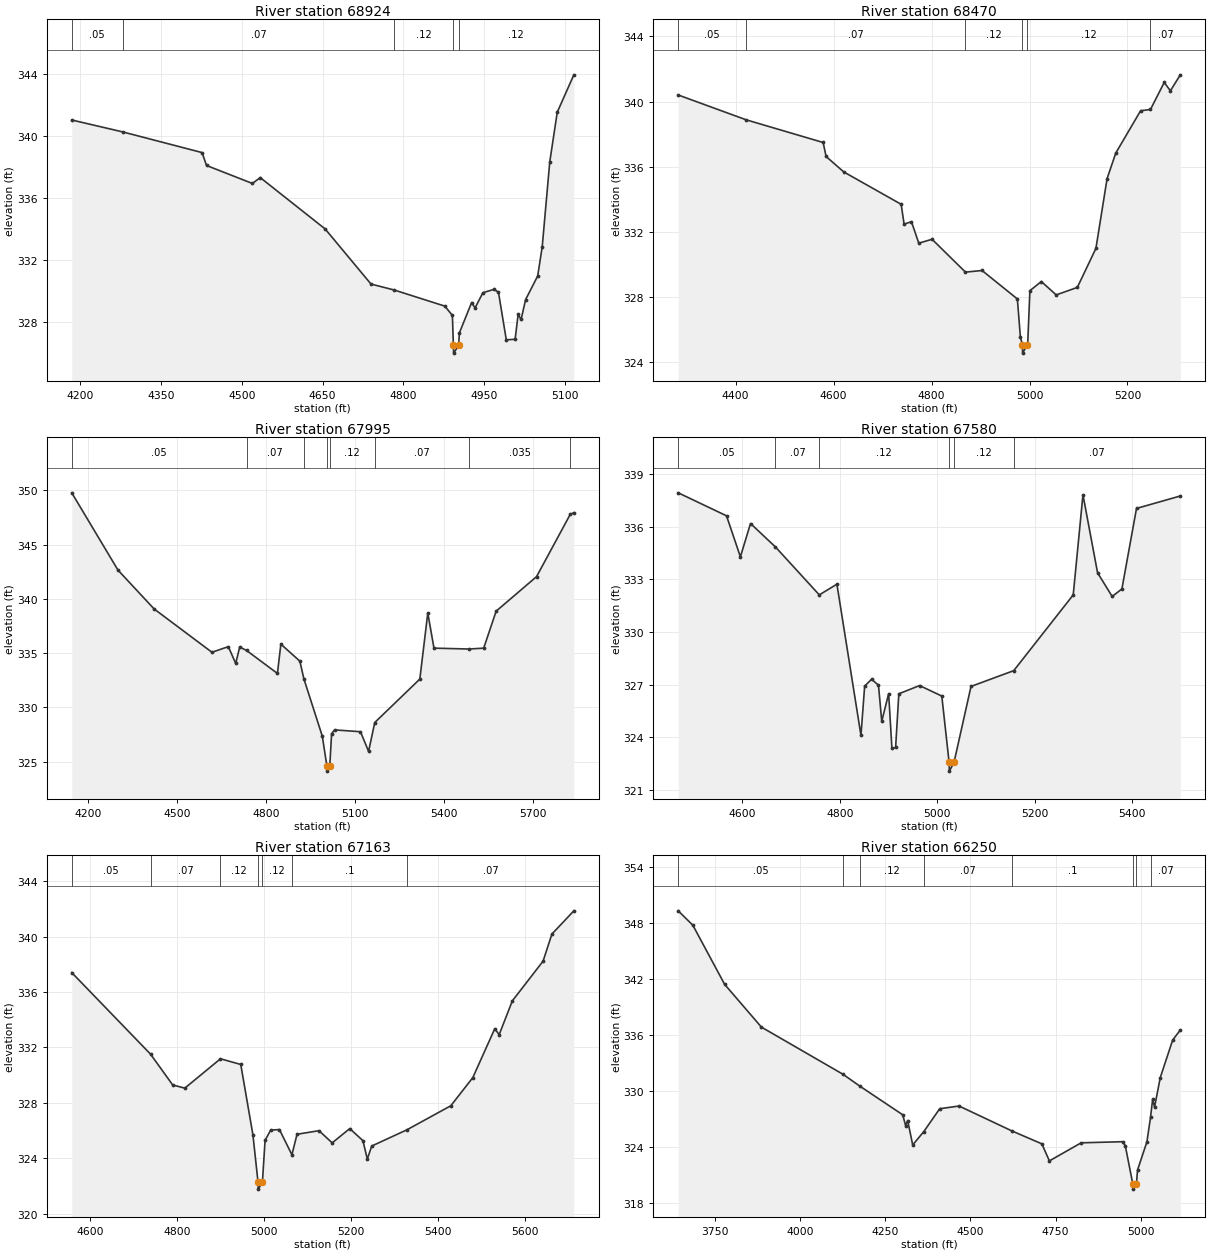
Type RM Length L Ch R = 1 ,68924   ,454,454,454
BEGIN DESCRIPTION:
DENTON CREEK 2 81.0
END DESCRIPTION:
XS GIS Cut Line= 3
      2478725.01     13766375.01        2478075.       13765875.
      2477974.98     13765824.99
#Sta/Elev= 30
  4184.3  341.04  4279.1  340.27  4426.2  338.94  4434.4  338.11  4519.6  336.95
  4534.1  337.33  4654.6  334.02  4739.7  330.47  4782.4  330.09  4876.6  329.05
  4890.8  328.45  4892.6  326.52  4893.1  326.02  4902.3  326.52  4903.8  327.33
  4926.5  329.28  4932.8  328.93  4947.3  329.91  4968.1  330.13  4976.3  329.94
  4990.8  326.88  5007.2  326.91  5012.8  328.51  5018.3  328.19  5026.7  329.47
  5049.1  330.99  5057.5  332.87  5071.5  338.34  5085.4  341.54  5116.2  343.95
#Mann= 5 ,-1 , 0
  4184.3     .05       0  4279.1     .07       0  4782.4     .12       0
  4892.6     .05       0  4902.3     .12       0
Bank Sta=4892.6,4902.3
XS Rating Curve= 0 ,0
Exp/Cntr=0.3,0.1

Type RM Length L Ch R = 1 ,68470   ,475,475,475
BEGIN DESCRIPTION:
DENTON CREEK 2 80.0
END DESCRIPTION:
XS GIS Cut Line= 3
      2478774.99     13766224.98        2478375.       13765625.
      2478075.03       13765575.
#Sta/Elev= 30
  4282.7   340.4  4421.8  338.87  4578.6  337.48  4584.6  336.62  4620.7  335.67
  4737.9  333.68  4743.9  332.46  4758.9  332.61  4773.9  331.29    4801  331.53
  4869.2  329.51  4903.1  329.61  4975.2  327.86  4981.3  325.53  4985.4  325.03
  4985.9  324.53  4995.2  325.03  4996.3  325.12  5000.8  328.37  5024.1  328.93
  5054.5  328.11  5097.6  328.57  5135.6  330.97  5158.4  335.26  5176.1  336.83
  5226.8  339.43    5247  339.51    5275  341.17  5287.7  340.66  5307.9  341.64
#Mann= 6 ,-1 , 0
  4282.7     .05       0  4421.8     .07       0  4869.2     .12       0
  4985.4     .05       0  4995.2     .12       0    5247     .07       0
Bank Sta=4985.4,4995.2
XS Rating Curve= 0 ,0
Exp/Cntr=0.3,0.1

Type RM Length L Ch R = 1 ,67995   ,415,415,415
BEGIN DESCRIPTION:
DENTON CREEK 2 79.0
END DESCRIPTION:
XS GIS Cut Line= 3
      2479575.02     13765725.01        2478775.       13765425.
      2477974.98     13765174.99
#Sta/Elev= 30
    4146  349.77  4301.8  342.65  4423.7  339.07  4618.6  335.08  4673.8   335.6
  4698.7  334.05  4712.1  335.56  4735.1  335.25  4839.3  333.13  4850.9  335.83
    4915  334.26  4928.3  332.65  4990.6  327.35  5005.9  324.63  5006.4  324.13
  5015.9  324.63  5021.9  327.58  5031.9  327.93  5119.3  327.76  5146.6  325.95
  5167.5  328.61  5319.4  332.61  5346.2   338.7  5367.1  335.46  5484.8  335.38
  5534.7  335.46  5576.7  338.87  5712.9  342.05  5826.5  347.79  5838.6  347.94
#Mann= 8 ,-1 , 0
    4146     .05       0  4735.1     .07       0  4928.3     .12       0
  5005.9     .05       0  5015.9     .12       0  5167.5     .07       0
  5484.8    .035       0  5826.5     .07       0
Bank Sta=5005.9,5015.9
XS Rating Curve= 0 ,0
Exp/Cntr=0.3,0.1

Type RM Length L Ch R = 1 ,67580   ,417,417,417
BEGIN DESCRIPTION:
DENTON CREEK 2 78.0
END DESCRIPTION:
XS GIS Cut Line= 3
        2479225.       13765475.        2478825.       13765125.
        2478325.       13765125.
#Sta/Elev= 30
    4468  337.94  4567.2  336.63  4595.7  334.29  4616.5  336.19  4667.5  334.86
  4757.8  332.12    4794  332.73  4843.4  324.11    4851  326.92  4865.2  327.31
  4879.4  326.97  4886.1  324.91  4900.3  326.49    4907  323.37  4914.6  323.42
  4921.2  326.48  4963.9  326.95  5009.5  326.35  5024.5  322.57    5025  322.07
  5034.6  322.57  5069.5   326.9  5157.3   327.8  5279.5  332.12  5299.5  337.83
  5329.5  333.38  5359.5  332.03  5379.5  332.46  5409.5  337.05  5499.5  337.76
#Mann= 6 ,-1 , 0
    4468     .05       0  4667.5     .07       0  4757.8     .12       0
  5024.5     .05       0  5034.6     .12       0  5157.3     .07       0
Bank Sta=5024.5,5034.6
XS Rating Curve= 0 ,0
Exp/Cntr=0.3,0.1

Type RM Length L Ch R = 1 ,67163   ,913,913,913
BEGIN DESCRIPTION:
DENTON CREEK 2 77.0
END DESCRIPTION:
XS GIS Cut Line= 3
      2479374.99       13765025.        2478975.       13764825.
      2478275.01       13764725.
#Sta/Elev= 30
  4557.2   337.4  4738.4  331.51  4789.2  329.29  4817.1  329.06  4899.1  331.18
  4945.7  330.77  4973.7  325.69  4985.4  322.27  4985.9  321.77  4995.5  322.27
  5001.6  325.29  5014.5  326.03  5034.7  326.07  5063.3  324.25  5075.1  325.73
  5125.6  325.99  5155.9  325.11  5196.3  326.14  5226.6  325.27  5236.7  323.94
  5246.8  324.88  5328.2  326.06  5428.7  327.79  5479.2  329.82  5529.7  333.35
  5539.8  332.92  5570.1  335.36  5640.8  338.23    5661  340.18  5711.5  341.86
#Mann= 7 ,-1 , 0
  4557.2     .05       0  4738.4     .07       0  4899.1     .12       0
  4985.4     .05       0  4995.5     .12       0  5063.3      .1       0
  5328.2     .07       0
Bank Sta=4985.4,4995.5
XS Rating Curve= 0 ,0
Exp/Cntr=0.3,0.1

Type RM Length L Ch R = 1 ,66250   ,446,446,446
BEGIN DESCRIPTION:
DENTON CREEK 2 76.0
END DESCRIPTION:
XS GIS Cut Line= 3
      2479625.01     13765025.01        2478525.       13764225.
      2478424.96     13764275.02
#Sta/Elev= 30
  3643.6  349.32  3686.5  347.77  3779.6  341.43  3887.4  336.84  4126.5  331.78
  4175.4  330.52  4301.7  327.43  4310.2  326.27  4316.3  326.81    4331  324.19
  4363.6  325.63  4410.2  328.08    4467  328.37  4622.8  325.68  4709.7  324.31
  4731.7  322.48  4824.9  324.42  4946.2  324.54  4954.3  324.11  4976.6  319.95
  4977.1  319.45  4986.8  319.95  4990.2   321.5  5017.7  324.53  5028.3  327.16
  5034.5   329.1  5040.1  328.26  5056.9  331.43  5093.2  335.45  5115.6  336.53
#Mann= 8 ,-1 , 0
  3643.6     .05       0  4126.5     .07       0  4175.4     .12       0
  4363.6     .07       0  4622.8      .1       0  4976.6     .05       0
  4986.8     .07       0  5028.3     .07       0
Bank Sta=4976.6,4986.8
XS Rating Curve= 0 ,0
Exp/Cntr=0.3,0.1

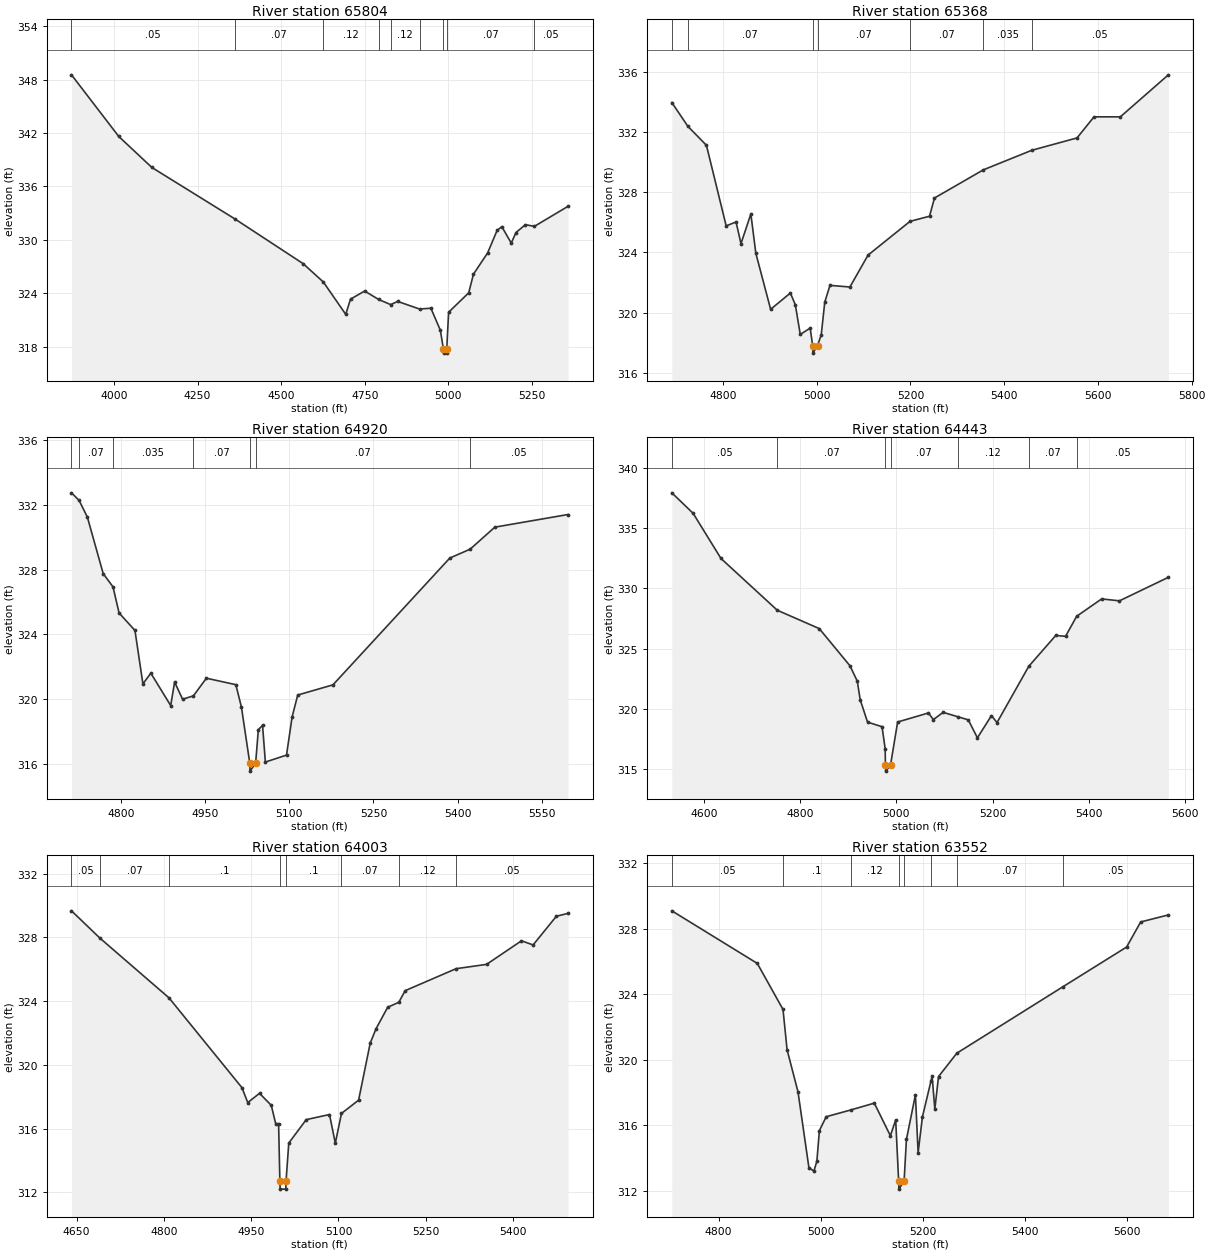
Type RM Length L Ch R = 1 ,65804   ,436,436,436
BEGIN DESCRIPTION:
DENTON CREEK 2 75.0
END DESCRIPTION:
XS GIS Cut Line= 3
      2479674.98     13764924.98        2478875.       13764125.
        2478625.       13763875.
#Sta/Elev= 30
  3872.8  348.53  4014.2  341.61  4113.2  338.13  4362.1  332.34  4565.7  327.33
  4626.1  325.27    4693  321.64  4707.2  323.35  4749.6  324.26  4791.5  323.31
  4827.2  322.74  4848.6  323.09  4913.7  322.24  4947.6  322.33  4975.9  319.86
  4984.9  317.79  4985.4  317.29  4994.6  317.29  4995.1  317.79  5000.6  321.88
  5060.7  324.06  5074.9  326.15  5117.3  328.54  5145.6  331.06  5159.7  331.49
    5188  329.64  5202.1  330.83  5230.4  331.71  5257.1  331.52  5357.7  333.77
#Mann= 9 ,-1 , 0
  3872.8     .05       0  4362.1     .07       0  4626.1     .12       0
  4791.5     .07       0  4827.2     .12       0  4913.7     .07       0
  4984.9     .05       0  4995.1     .07       0  5257.1     .05       0
Bank Sta=4984.9,4995.1
XS Rating Curve= 0 ,0
Exp/Cntr=0.3,0.1

Type RM Length L Ch R = 1 ,65368   ,448,448,448
BEGIN DESCRIPTION:
DENTON CREEK 2 74.0
END DESCRIPTION:
XS GIS Cut Line= 3
      2479574.97     13764124.99        2479275.       13764025.
        2478575.       13763775.
#Sta/Elev= 30
  4690.8  333.95    4725  332.37  4764.6  331.11  4806.7  325.76  4827.8  326.02
  4838.3  324.58  4859.4  326.55    4870  323.94  4901.6  320.22  4943.7   321.3
  4954.3  320.52  4964.8  318.55  4985.9  318.97  4991.3  317.81  4991.8  317.31
  5001.7  317.81  5009.6  318.53  5017.1   320.7  5028.2  321.81  5070.7   321.7
  5109.5  323.82    5199  326.06  5240.6   326.4  5251.2  327.61  5355.4  329.48
  5458.9  330.78  5555.4   331.6  5591.6     333  5647.8     333  5750.3  335.79
#Mann= 7 ,-1 , 0
  4690.8     .05       0    4725     .07       0  4991.3     .05       0
  5001.7     .07       0    5199     .07       0  5355.4    .035       0
  5458.9     .05       0
Bank Sta=4991.3,5001.7
XS Rating Curve= 0 ,0
Exp/Cntr=0.3,0.1

Type RM Length L Ch R = 1 ,64920   ,477,477,477
BEGIN DESCRIPTION:
DENTON CREEK 2 73.0
END DESCRIPTION:
XS GIS Cut Line= 3
      2479624.99     13763924.99        2479425.       13763725.
        2478825.       13763675.
#Sta/Elev= 30
  4711.9  332.74  4725.5  332.27  4740.2  331.24  4768.4  327.75  4785.9  326.93
  4796.7  325.32    4825  324.24  4839.2  320.94  4853.3   321.6  4888.7   319.6
  4895.7  321.05  4909.9  319.99  4929.2   320.2  4952.3  321.29  5004.8  320.89
  5014.8   319.5  5029.6  316.05  5030.1  315.55  5040.1  316.05  5044.9  318.11
  5052.4  318.38  5057.4  316.11  5095.1  316.54  5105.1   318.9  5115.1  320.25
  5177.9  320.88  5386.1  328.71  5422.4  329.26  5466.4  330.62  5596.8   331.4
#Mann= 7 ,-1 , 0
  4711.9     .05       0  4725.5     .07       0  4785.9    .035       0
  4929.2     .07       0  5029.6     .05       0  5040.1     .07       0
  5422.4     .05       0
Bank Sta=5029.6,5040.1
XS Rating Curve= 0 ,0
Exp/Cntr=0.3,0.1

Type RM Length L Ch R = 1 ,64443   ,440,440,440
BEGIN DESCRIPTION:
DENTON CREEK 2 72.0
END DESCRIPTION:
XS GIS Cut Line= 3
      2479924.99       13763575.        2479525.       13763325.
      2478975.01       13763225.
#Sta/Elev= 30
  4533.9  337.92  4578.1  336.22  4635.9  332.48  4752.8  328.19  4839.9  326.67
  4903.6  323.59  4918.9  322.31  4924.8  320.79  4940.1  318.92  4970.2  318.54
  4976.7  316.72  4977.3  315.36  4977.8  314.86  4987.8  315.36  5002.6  318.93
  5066.6  319.68  5076.7  319.13  5097.1  319.73  5127.2  319.37  5149.2  319.11
  5168.2  317.62  5197.4  319.46  5208.9  318.88  5274.7  323.54  5330.8   326.1
  5351.2  326.03  5374.2  327.69  5426.1  329.13    5463  328.97  5564.6  330.92
#Mann= 7 ,-1 , 0
  4533.9     .05       0  4752.8     .07       0  4977.3     .05       0
  4987.8     .07       0  5127.2     .12       0  5274.7     .07       0
  5374.2     .05       0
Bank Sta=4977.3,4987.8
XS Rating Curve= 0 ,0
Exp/Cntr=0.3,0.1

Type RM Length L Ch R = 1 ,64003   ,451,451,451
BEGIN DESCRIPTION:
DENTON CREEK 2 71.0
END DESCRIPTION:
XS GIS Cut Line= 3
      2479924.96     13763074.99        2479575.       13763025.
      2479075.01       13763025.
#Sta/Elev= 30
  4641.1  329.67  4689.9  327.96  4808.7  324.21    4934  318.58  4944.1  317.64
  4964.3  318.22  4984.5  317.47  4992.1  316.32  4997.1  316.32  4999.3  312.71
  4999.8  312.21  5009.4  312.21  5009.9  312.71  5014.6   315.1  5044.6  316.57
  5084.6  316.89  5094.6  315.09  5105.2  316.96  5134.6  317.79  5154.6  321.37
  5164.6  322.27  5184.6  323.62  5203.7  323.93  5214.6  324.66  5302.2  326.04
  5354.6  326.31  5414.6  327.79  5434.6  327.53  5474.6  329.33  5494.6  329.51
#Mann= 8 ,-1 , 0
  4641.1     .05       0  4689.9     .07       0  4808.7      .1       0
  4999.3     .05       0  5009.9      .1       0  5105.2     .07       0
  5203.7     .12       0  5302.2     .05       0
Bank Sta=4999.3,5009.9
XS Rating Curve= 0 ,0
Exp/Cntr=0.3,0.1

Type RM Length L Ch R = 1 ,63552   ,808,808,808
BEGIN DESCRIPTION:
DENTON CREEK 2 70.0
END DESCRIPTION:
XS GIS Cut Line= 3
      2479975.02     13762875.01        2479725.       13762725.
      2479075.04     13762924.99
#Sta/Elev= 30
  4708.7  329.09  4875.9  325.88  4926.2  323.07  4934.2  320.61  4955.6  318.03
  4976.9  313.41  4986.7   313.2  4992.5  313.81  4997.4  315.67  5010.7  316.52
  5058.5  316.93  5104.9  317.35  5136.3  315.36  5146.7  316.32  5152.5   312.6
    5153   312.1  5163.2   312.6  5167.7  315.13  5185.3  317.85  5190.6  314.33
  5199.1  316.52  5215.6  318.68    5218  318.99  5223.3  316.98  5230.5  318.97
  5266.4   320.4  5474.2  324.46  5598.6  326.88  5626.1  328.41  5680.3  328.84
#Mann= 8 ,-1 , 0
  4708.7     .05       0  4926.2      .1       0  5058.5     .12       0
  5152.5     .05       0  5163.2     .12       0  5215.6     .12       0
  5266.4     .07       0  5474.2     .05       0
Bank Sta=5152.5,5163.2
XS Rating Curve= 0 ,0
Exp/Cntr=0.3,0.1

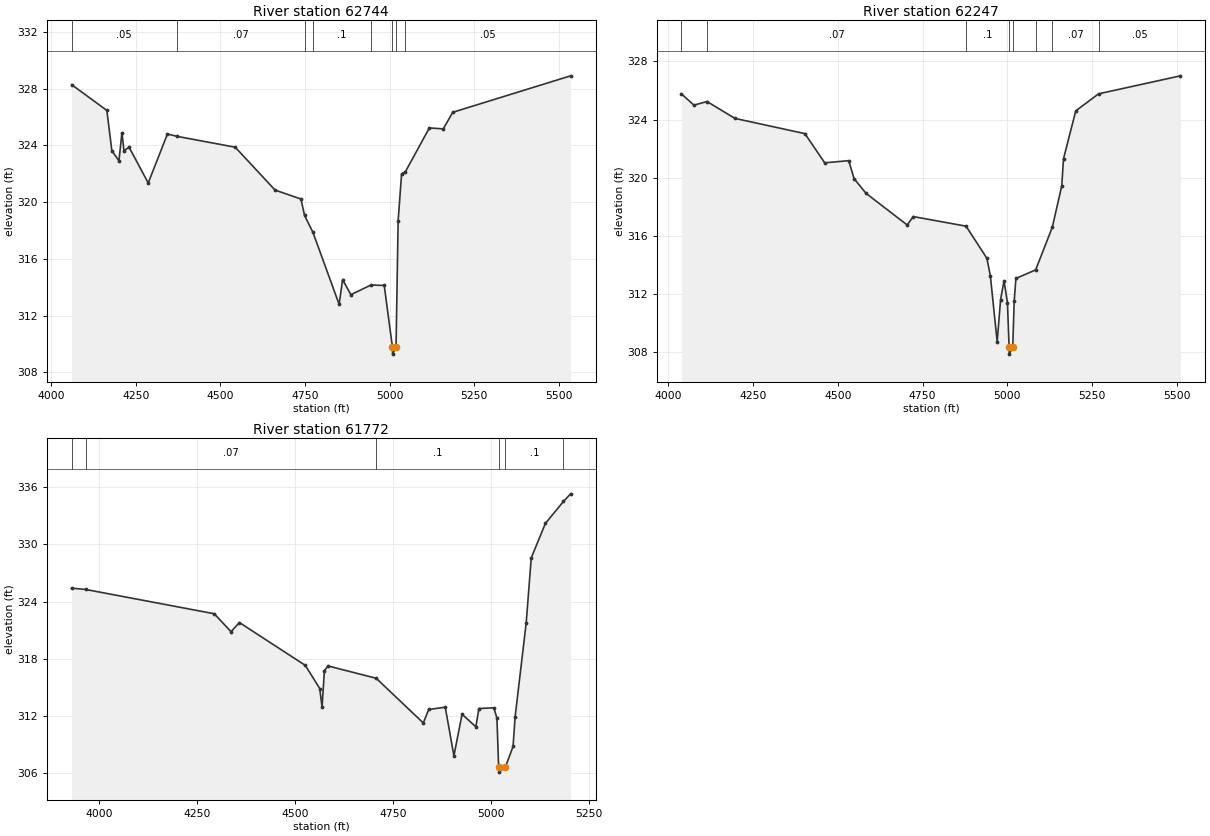
Type RM Length L Ch R = 1 ,62744   ,497,497,497
BEGIN DESCRIPTION:
DEN5
END DESCRIPTION:
XS GIS Cut Line= 5
      2480088.02     13762687.45      2479864.71     13762364.54
      2479713.81     13762337.38      2479203.79     13762455.08
      2479025.78     13762820.14
#Sta/Elev= 30
    4060  328.28  4164.2  326.46    4179  323.62    4200  322.91  4208.8   324.9
  4214.9  323.61  4229.7  323.88  4286.5  321.35  4343.3   324.8  4370.8  324.64
  4543.8  323.87  4661.6  320.85  4738.1  320.22  4748.8  319.06  4773.4  317.88
    4851   312.8  4861.3  314.54  4885.7  313.48  4945.2  314.16  4984.4  314.13
  5008.6  309.79  5009.1  309.29  5019.3  309.79  5025.5  318.68  5035.7  321.99
  5046.9  322.14  5117.8  325.23  5158.9  325.16    5187  326.33  5535.5   328.9
#Mann= 8 ,-1 , 0
    4060     .05       0  4370.8     .07       0  4748.8     .12       0
  4773.4      .1       0  4945.2     .12       0  5008.6     .05       0
  5019.3     .12       0  5046.9     .05       0
Bank Sta=5008.6,5019.3
XS Rating Curve= 0 ,0
Exp/Cntr=0.3,0.1

Type RM Length L Ch R = 1 ,62247   ,475,475,475
BEGIN DESCRIPTION:
DEN4
END DESCRIPTION:
XS GIS Cut Line= 5
      2480015.64     13762394.75       2479611.2     13762092.93
      2479418.56     13762008.67      2479067.98     13762062.75
      2479010.73     13762460.53
#Sta/Elev= 30
  4038.9  325.77  4075.6  324.99  4114.3  325.24  4196.5  324.08  4402.9  323.03
  4461.3  321.02  4532.1  321.17  4547.9  319.93  4583.1  318.92  4704.6  316.74
  4722.5  317.32  4878.1  316.66  4939.5  314.45  4949.7  313.26  4969.9   308.7
    4980  311.61  4990.1   312.9  5000.2  311.39    5005  308.35  5005.5  307.85
  5015.8  308.35  5020.1  311.53  5025.2  313.06  5083.4  313.65  5132.4  316.58
  5160.4  319.44  5165.5   321.3  5201.7   324.6  5268.8  325.77  5510.4  327.01
#Mann= 8 ,-1 , 0
  4038.9     .05       0  4114.3     .07       0  4878.1      .1       0
    5005     .05       0  5015.8      .1       0  5083.4     .12       0
  5132.4     .07       0  5268.8     .05       0
Bank Sta=5005,5015.8
XS Rating Curve= 0 ,0
Exp/Cntr=0.3,0.1

Type RM Length L Ch R = 1 ,61772   ,475,475,475
BEGIN DESCRIPTION:
DENTON CREEK 2 69.0
END DESCRIPTION:
XS GIS Cut Line= 4
      2480015.64     13762313.26       2479386.4     13761928.68
        2479175.       13761675.      2478975.03     13761625.01
#Sta/Elev= 30
  3930.2  325.41  3966.4  325.27  4294.3  322.73  4337.2  320.85  4358.5  321.81
  4526.8  317.32  4563.6  314.89  4569.5  312.95  4575.5  316.78  4584.9  317.26
  4707.7  315.97    4828  311.29  4841.7   312.7    4884  312.94  4906.1  307.85
  4926.9   312.2  4962.1  310.89  4969.9   312.8  5008.2  312.88  5015.9  311.78
  5020.3  306.64  5020.8  306.14  5037.3  306.64  5057.1  308.83  5062.3  311.92
  5090.6  321.77  5103.5  328.58  5139.6  332.19  5185.7  334.49    5204  335.29
#Mann= 6 ,-1 , 0
  3930.2     .05       0  3966.4     .07       0  4707.7      .1       0
  5020.3     .05       0  5037.3      .1       0  5185.7     .12       0
Bank Sta=5020.3,5037.3
XS Rating Curve= 0 ,0
Exp/Cntr=0.3,0.1