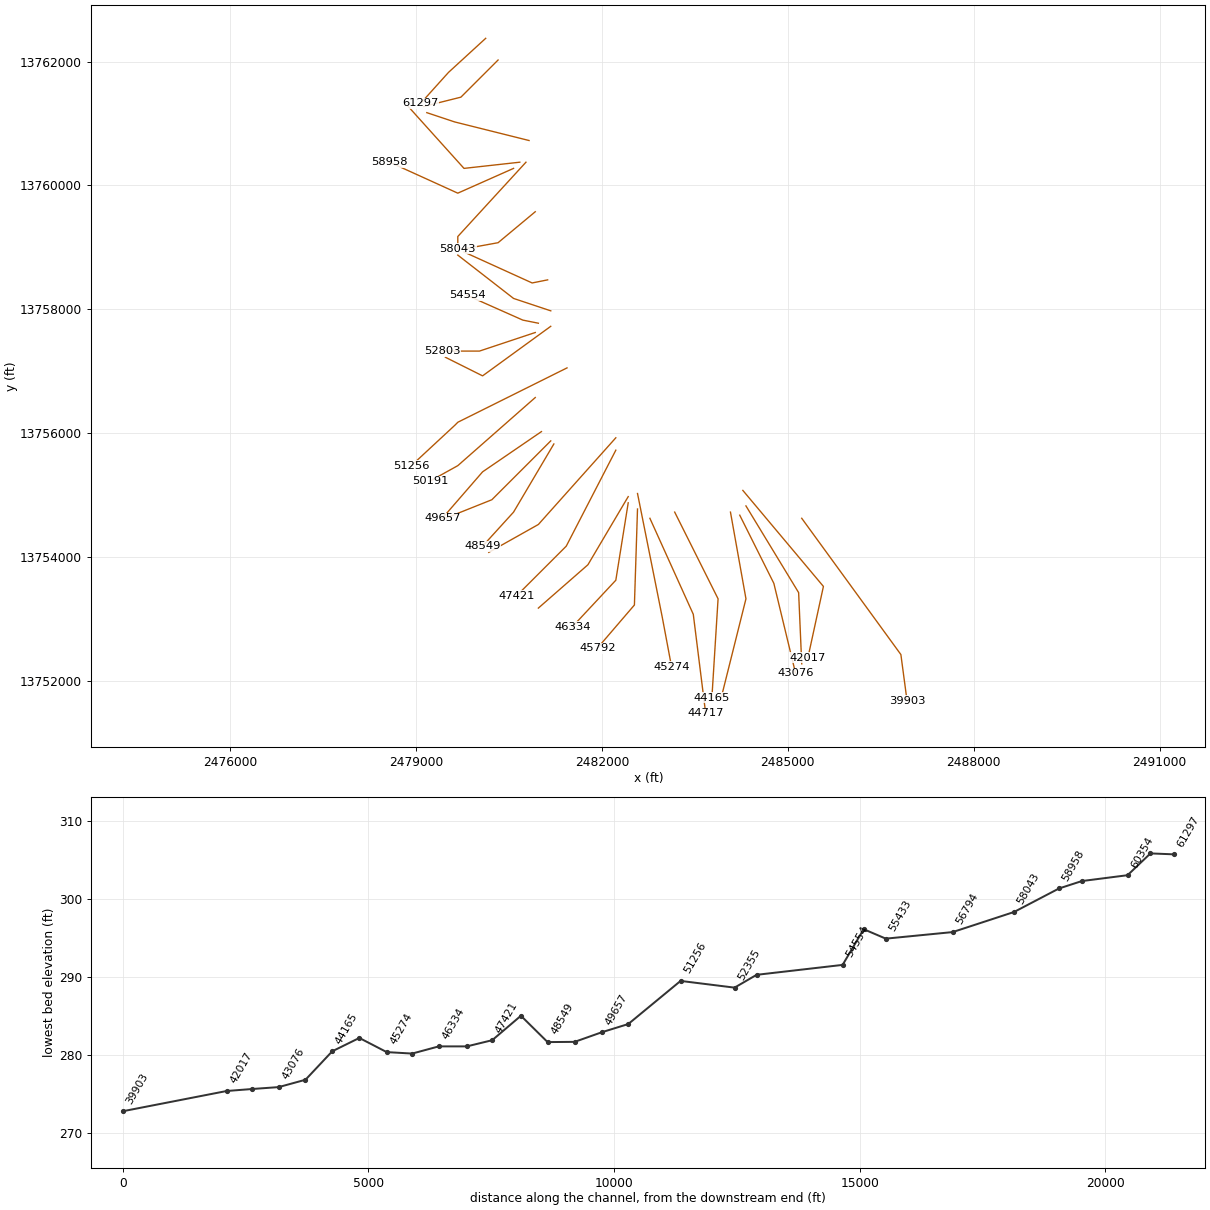
HEC-RAS study DENTON CREEK 2.prj: DENTON CREEK 2 Base Level Engineering

--- DENTON CREEK 2.g01 (geometry) --- (continued)

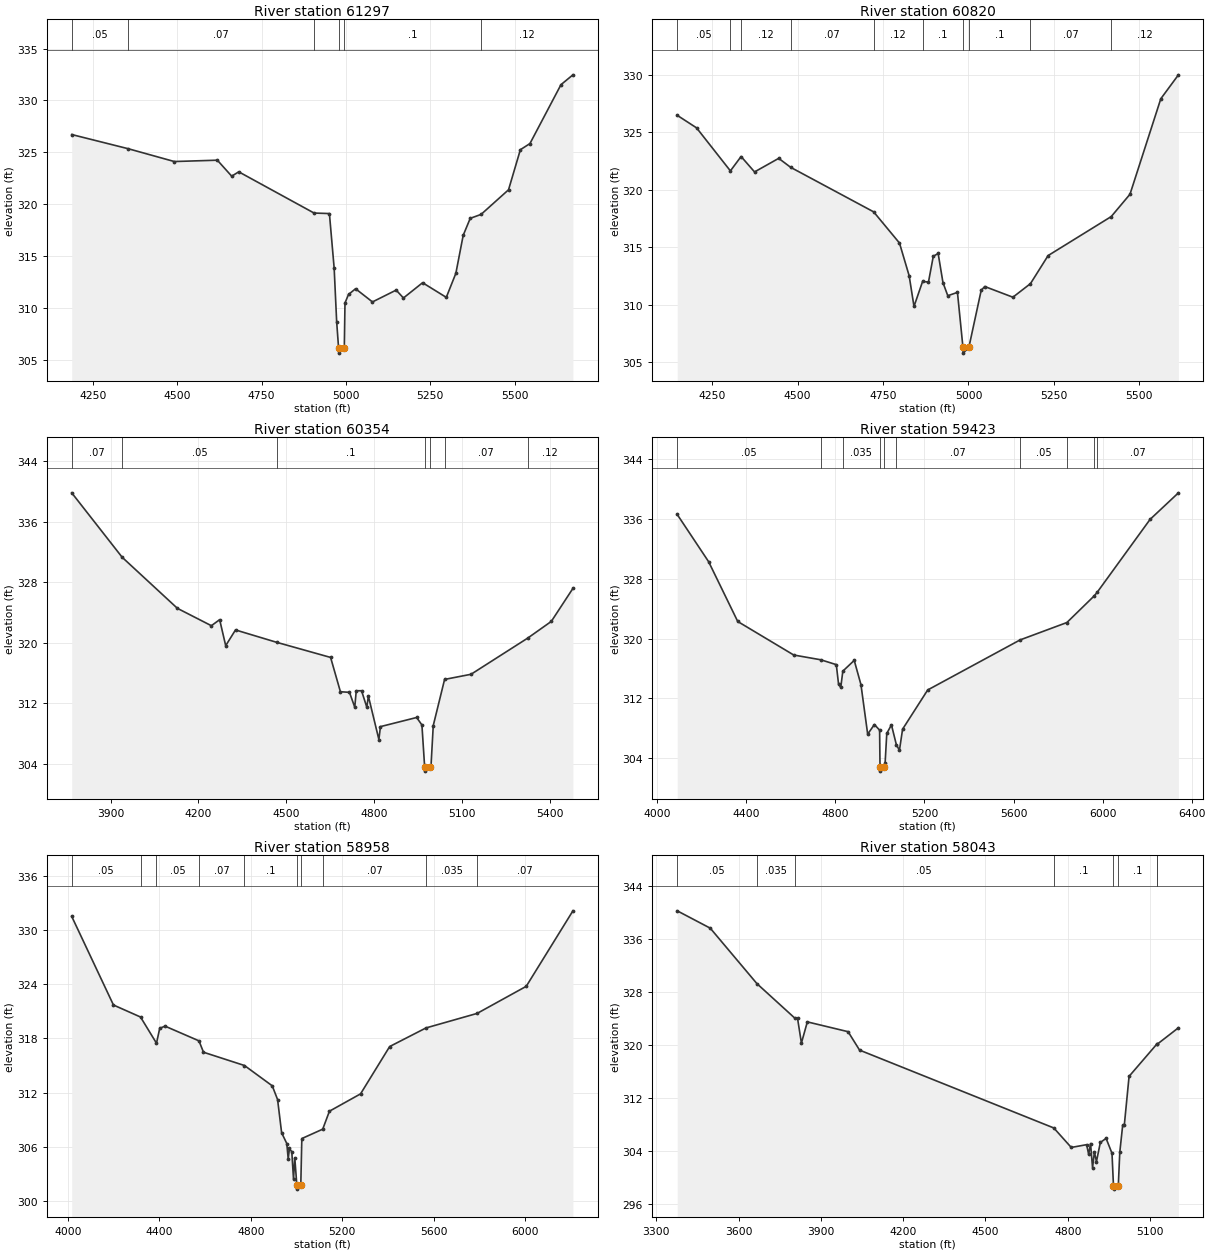
Type RM Length L Ch R = 1 ,61297   ,477,477,477
BEGIN DESCRIPTION:
DENTON CREEK 2 68.0
END DESCRIPTION:
XS GIS Cut Line= 3
      2480124.97     13762374.98        2479525.       13761825.
      2479074.99     13761324.99
#Sta/Elev= 30
  4186.6  326.72  4353.5  325.36  4490.9  324.12  4618.5  324.25  4661.1  322.71
    4682  323.13  4905.4  319.16  4950.9  319.11    4965  313.85  4972.4  308.71
  4978.1  306.17  4978.6  305.67  4995.1  306.17  4997.1   310.5  5007.6  311.32
  5028.5  311.87  5078.6   310.6  5148.9  311.74  5170.5  310.98  5227.3  312.45
  5297.6  311.04    5326  313.36  5347.7  317.01  5368.6  318.65  5400.8  319.03
  5482.2   321.4  5517.3  325.26  5545.7  325.85  5637.7  331.52  5673.2  332.47
#Mann= 6 ,-1 , 0
  4186.6     .05       0  4353.5     .07       0  4905.4      .1       0
  4978.1     .05       0  4995.1      .1       0  5400.8     .12       0
Bank Sta=4978.1,4995.1
XS Rating Curve= 0 ,0
Exp/Cntr=0.3,0.1

Type RM Length L Ch R = 1 ,60820   ,466,466,466
BEGIN DESCRIPTION:
DENTON CREEK 2 67.0
END DESCRIPTION:
XS GIS Cut Line= 3
      2480324.99     13762024.99        2479725.       13761425.
      2479124.98       13761275.
#Sta/Elev= 30
  4147.5  326.46  4204.1  325.37  4303.1  321.63  4334.4  322.88  4373.8  321.54
  4444.5  322.72  4479.5  321.94  4722.4  318.07    4798  315.36  4826.3  312.52
  4840.5  309.85  4865.7  312.02  4882.9  311.97    4897  314.21  4911.2  314.45
  4925.3  311.92  4939.4  310.78  4967.7  311.07  4983.8  306.29  4984.3  305.79
  5001.1  306.29  5037.2  311.25  5047.6  311.58    5130  310.65  5181.4  311.83
  5233.1  314.27  5417.8  317.66  5472.7   319.6  5562.9   327.9  5614.5  329.98
#Mann= 10 ,-1 , 0
  4147.5     .05       0  4303.1     .07       0  4334.4     .12       0
  4479.5     .07       0  4722.4     .12       0  4865.7      .1       0
  4983.8     .05       0  5001.1      .1       0  5181.4     .07       0
  5417.8     .12       0
Bank Sta=4983.8,5001.1
XS Rating Curve= 0 ,0
Exp/Cntr=0.3,0.1

Type RM Length L Ch R = 1 ,60354   ,931,931,931
BEGIN DESCRIPTION:
DENTON CREEK 2 66.0
END DESCRIPTION:
XS GIS Cut Line= 3
      2480825.02     13760724.99        2479625.       13761025.
      2479174.99       13761175.
#Sta/Elev= 30
  3767.4  339.84  3939.6  331.31  4128.2  324.55  4244.2  322.25  4272.5  323.05
  4293.1  319.61  4326.6  321.69  4467.3  320.05  4651.3  318.05  4684.8  313.51
  4715.7  313.43  4733.8  311.46  4738.9  313.64    4757  313.64    4775  311.45
  4780.2  312.94  4816.2  307.18  4821.4  308.89  4945.1   310.1  4963.1  309.11
  4972.5   303.5    4973     303  4989.8   303.5    4994  303.59  5001.8  309.03
  5040.5  315.14  5130.8  315.82  5324.4  320.61  5404.9  322.82  5478.7  327.19
#Mann= 7 ,-1 , 0
  3767.4     .07       0  3939.6     .05       0  4467.3      .1       0
  4972.5     .05       0  4989.8      .1       0  5040.5     .07       0
  5324.4     .12       0
Bank Sta=4972.5,4989.8
XS Rating Curve= 0 ,0
Exp/Cntr=0.3,0.1

Type RM Length L Ch R = 1 ,59423   ,465,465,465
BEGIN DESCRIPTION:
DENTON CREEK 2 65.0
END DESCRIPTION:
XS GIS Cut Line= 3
      2480675.02       13760375.        2479775.       13760275.
      2478875.01     13761274.98
#Sta/Elev= 30
  4089.8  336.62  4230.7   330.3  4361.5  322.29    4613   317.8  4734.7  317.16
  4804.2  316.51  4814.3   313.9  4824.3  313.47  4833.5  315.64  4884.7  317.08
  4914.9  313.83  4945.1   307.2  4975.2  308.49  4998.7  307.74  5000.5  302.75
    5001  302.25  5017.9  302.75  5023.4  303.33  5030.9   307.3  5051.8  308.45
  5073.7  305.81  5087.7  305.03  5101.9  307.87  5214.7  313.12  5629.5  319.82
  5839.8  322.15  5962.2  325.71  5975.6  326.19  6213.3  335.96  6340.7  339.52
#Mann= 10 ,-1 , 0
  4089.8     .05       0  4734.7      .1       0  4833.5    .035       0
  5000.5    .035       0  5017.9    .035       0  5073.7     .07       0
  5629.5     .05       0  5839.8     .07       0  5962.2     .12       0
  5975.6     .07       0
Bank Sta=5000.5,5017.9
XS Rating Curve= 0 ,0
Exp/Cntr=0.3,0.1

Type RM Length L Ch R = 1 ,58958   ,915,915,915
BEGIN DESCRIPTION:
DENTON CREEK 2 64.0
END DESCRIPTION:
XS GIS Cut Line= 3
        2480575.       13760275.        2479675.       13759875.
      2478574.99       13760375.
#Sta/Elev= 30
  4016.1   331.5  4198.7  321.69  4317.1  320.36    4387  317.46  4401.2  319.11
  4424.4  319.35  4572.9  317.72  4592.7  316.46    4772  314.99  4893.6  312.74
  4916.9  311.22  4934.6  307.54  4957.2  306.35  4963.4  304.66  4968.8   305.8
  4979.1  305.43  4986.6  302.42  4992.1  304.78    5001   301.8  5001.5   301.3
  5018.5   301.8    5023   306.9  5114.4  307.94  5143.8  309.93    5280  311.85
  5407.4  317.09  5566.2  319.15  5790.1  320.76    6005  323.76  6209.3  332.12
#Mann= 10 ,-1 , 0
  4016.1     .05       0  4317.1    .035       0    4387     .05       0
  4572.9     .07       0    4772      .1       0    5001     .05       0
  5018.5      .1       0  5114.4     .07       0  5566.2    .035       0
  5790.1     .07       0
Bank Sta=5001,5018.5
XS Rating Curve= 0 ,0
Exp/Cntr=0.3,0.1

Type RM Length L Ch R = 1 ,58043   ,1249,1249,1249
BEGIN DESCRIPTION:
DENTON CREEK 2 63.0
END DESCRIPTION:
XS GIS Cut Line= 3
        2480775.       13760375.        2479675.       13759175.
        2479675.     13758974.98
#Sta/Elev= 30
  3375.9  340.29  3496.4  337.67  3666.6   329.3  3803.8  324.13  3814.6  324.09
  3828.8  320.33  3850.4  323.53    3999  322.05  4040.9  319.27  4749.3  307.52
  4812.9  304.58    4869     305  4876.4  303.54  4883.2  305.17  4890.6  301.53
  4897.4  303.92  4904.8  302.45    4919  305.33    4940  305.95  4961.5   303.7
  4966.9  298.79  4967.4  298.29  4984.5  298.79  4989.9  303.85  5000.4   307.9
  5006.3   307.9  5023.8  315.31  5125.3  320.19  5127.1  320.18  5203.8  322.64
#Mann= 8 ,-1 , 0
  3375.9     .05       0  3666.6    .035       0  3803.8     .05       0
  4749.3      .1       0  4966.9     .05       0  4984.5      .1       0
  5125.3     .07       0  5127.1     .12       0
Bank Sta=4966.9,4984.5
XS Rating Curve= 0 ,0
Exp/Cntr=0.3,0.1

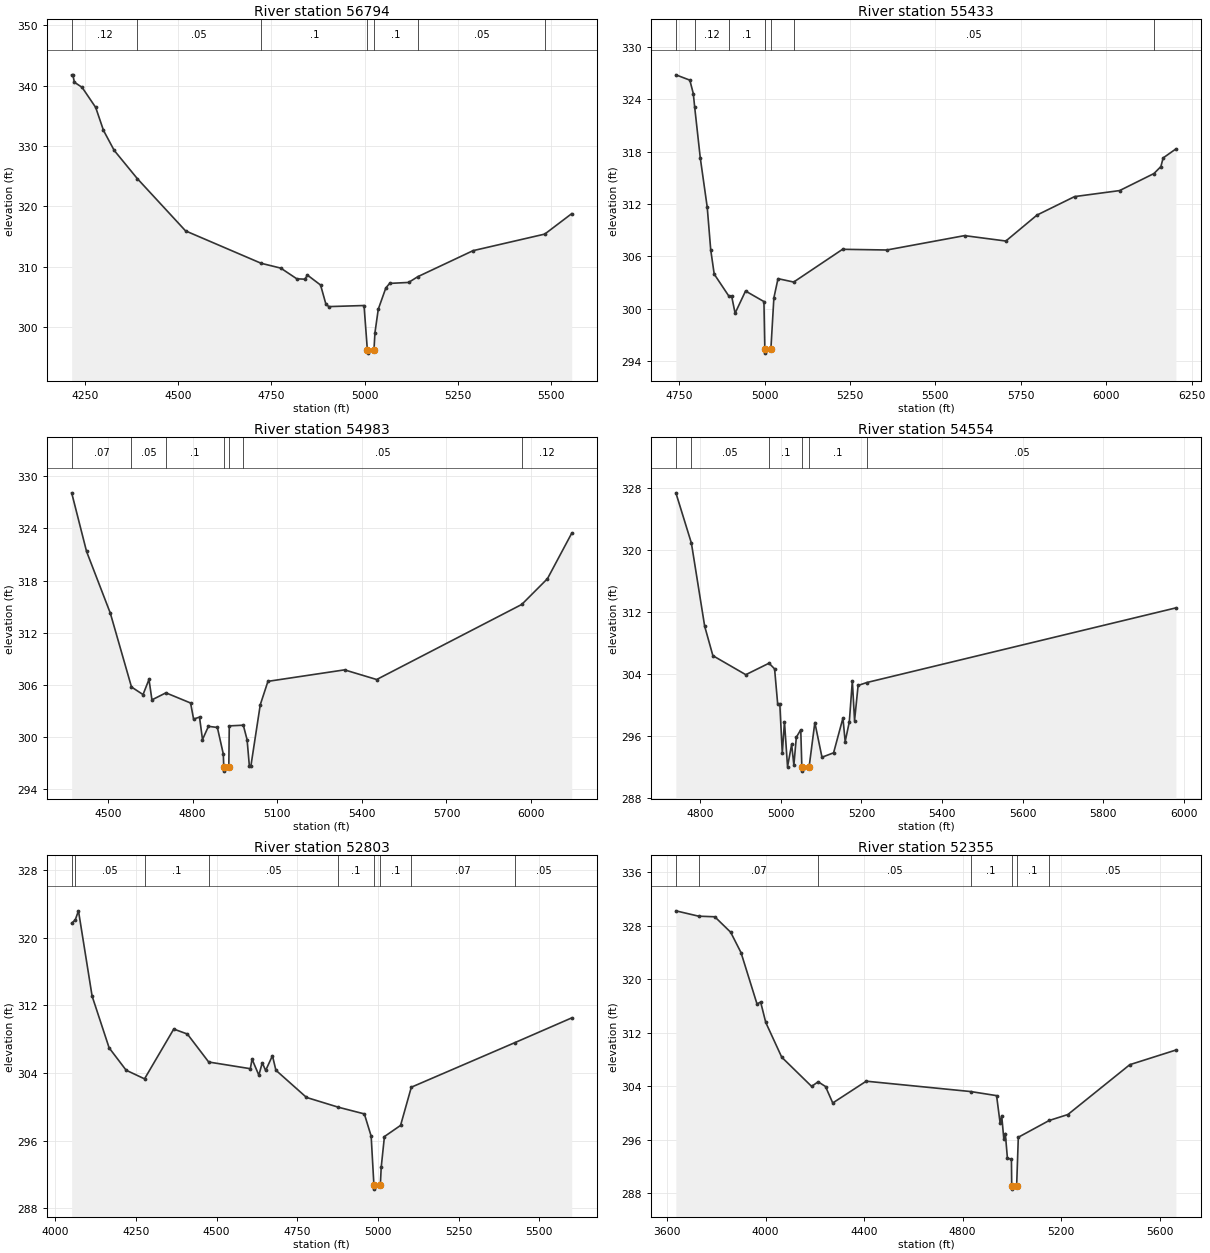
Type RM Length L Ch R = 1 ,56794   ,1361,1361,1361
BEGIN DESCRIPTION:
DENTON CREEK 2 62.0
END DESCRIPTION:
XS GIS Cut Line= 3
      2480925.01     13759575.01        2480325.       13759075.
      2479774.95     13758974.99
#Sta/Elev= 30
  4214.6  341.78  4217.9  341.78  4221.8  340.56  4242.6   339.7    4279  336.38
  4299.9  332.58  4328.5  329.28  4390.3  324.62  4519.9  315.95  4722.4  310.59
    4775  309.79    4818  308.02  4839.4  307.96  4846.6  308.63  4881.7  306.99
  4896.1   303.8  4903.9  303.42  4998.2   303.6  5007.1  296.22  5007.6  295.72
  5024.8  296.22  5027.4  299.08  5036.3  302.98  5056.6  306.51  5066.8  307.26
  5117.6  307.42  5142.5  308.38  5290.4  312.68  5482.5  315.42  5554.7   318.8
#Mann= 7 ,-1 , 0
  4214.6     .12       0  4390.3     .05       0  4722.4      .1       0
  5007.1     .05       0  5024.8      .1       0  5142.5     .05       0
  5482.5     .12       0
Bank Sta=5007.1,5024.8
XS Rating Curve= 0 ,0
Exp/Cntr=0.3,0.1

Type RM Length L Ch R = 1 ,55433   ,450,450,450
BEGIN DESCRIPTION:
DENTON CREEK 2 61.0
END DESCRIPTION:
XS GIS Cut Line= 3
      2481124.98       13758475.        2480875.       13758425.
      2479775.03     13758924.99
#Sta/Elev= 30
  4740.5  326.83  4781.3  326.22  4791.5  324.68  4795.6   323.1  4811.9   317.3
  4832.3  311.62  4842.5  306.73  4852.7  303.95  4895.5  301.43  4903.6  301.45
  4913.8  299.46  4944.4  302.01  4998.2   300.8  5000.8  295.38  5001.3  294.88
  5018.6  295.38  5027.3  301.22  5039.4  303.43  5085.3  303.04  5228.3   306.8
  5357.9  306.72  5585.3  308.37  5706.1  307.75  5797.3  310.73  5907.2  312.85
    6039  313.54  6139.6   315.5  6159.8   316.3  6166.4  317.29  6203.7  318.32
#Mann= 7 ,-1 , 0
  4740.5     .07       0  4795.6     .12       0  4895.5      .1       0
  5000.8     .05       0  5018.6      .1       0  5085.3     .05       0
  6139.6     .12       0
Bank Sta=5000.8,5018.6
XS Rating Curve= 0 ,0
Exp/Cntr=0.3,0.1

Type RM Length L Ch R = 1 ,54983   ,429,429,429
BEGIN DESCRIPTION:
DENTON CREEK 2 60.0
END DESCRIPTION:
XS GIS Cut Line= 3
      2481174.99       13757975.        2480575.       13758175.
      2479675.01     13758874.99
#Sta/Elev= 30
  4371.4  328.08  4424.1  321.35  4508.4  314.25  4583.5  305.76  4624.4  304.89
  4645.5  306.63    4656  304.28  4705.5  305.09    4793  303.92  4803.6  302.07
  4824.6   302.3  4835.2  299.72  4856.3  301.24  4887.9  301.11    4909  298.05
  4910.6  296.59  4911.1  296.09  4928.5  296.59  4930.1  301.29  4979.9  301.37
  4993.3   299.7  5001.2  296.73    5007  296.73    5040  303.72  5067.2  306.41
  5338.7  307.73  5452.7  306.62    5967  315.25  6058.1  318.21    6144  323.43
#Mann= 7 ,-1 , 0
  4371.4     .07       0  4583.5     .05       0  4705.5      .1       0
  4910.6     .05       0  4928.5      .1       0  4979.9     .05       0
    5967     .12       0
Bank Sta=4910.6,4928.5
XS Rating Curve= 0 ,0
Exp/Cntr=0.3,0.1

Type RM Length L Ch R = 1 ,54554   ,1751,1751,1751
BEGIN DESCRIPTION:
DENTON CREEK 2 59.0
END DESCRIPTION:
XS GIS Cut Line= 3
      2480975.02       13757775.        2480725.       13757825.
      2479824.96     13758225.02
#Sta/Elev= 30
  4739.8  327.39  4778.3  320.91  4811.2   310.2  4831.6   306.4  4913.2  303.95
  4970.8  305.43  4984.6   304.7  4992.2   300.2  4997.5   300.2  5003.7  293.85
  5009.1  297.88  5016.7  292.09  5026.9  294.96  5032.4   292.3  5038.5  295.89
  5049.5  296.85  5052.2  292.02  5052.7  291.52  5070.1  292.02  5084.4  297.78
  5102.1  293.31  5130.9  293.88  5154.1  298.36  5159.6  295.32  5169.9  297.87
  5177.4  303.14  5182.9  298.04  5191.7  302.56  5213.3  302.94  5979.7  312.56
#Mann= 6 ,-1 , 0
  4739.8     .07       0  4778.3     .05       0  4970.8      .1       0
  5052.2     .05       0  5070.1      .1       0  5213.3     .05       0
Bank Sta=5052.2,5070.1
XS Rating Curve= 0 ,0
Exp/Cntr=0.3,0.1

Type RM Length L Ch R = 1 ,52803   ,448,448,448
BEGIN DESCRIPTION:
DENTON CREEK 2 58.0
END DESCRIPTION:
XS GIS Cut Line= 3
      2480925.01       13757625.        2480025.       13757325.
      2479424.99       13757325.
#Sta/Elev= 30
  4051.3  321.72  4062.3   322.1  4072.4  323.18  4114.6  313.09  4167.3  306.97
    4220  304.32    4277   303.3  4367.5  309.19  4409.7   308.6  4475.7  305.29
  4604.7   304.5    4610  305.63  4631.1  303.73  4641.6   305.2  4652.1  304.29
  4673.2  306.04  4683.8  304.32  4778.6   301.1  4877.5  299.94  4957.8  299.15
  4978.9  296.52  4987.4  290.75  4987.9  290.25  5007.4  290.75    5010  292.82
    5020  296.47    5070  297.79  5103.3  302.31  5424.4  307.59    5600  310.51
#Mann= 9 ,-1 , 0
  4051.3     .07       0  4062.3     .05       0    4277      .1       0
  4475.7     .05       0  4877.5      .1       0  4987.4     .05       0
  5007.4      .1       0  5103.3     .07       0  5424.4     .05       0
Bank Sta=4987.4,5007.4
XS Rating Curve= 0 ,0
Exp/Cntr=0.3,0.1

Type RM Length L Ch R = 1 ,52355   ,1099,1099,1099
BEGIN DESCRIPTION:
DENTON CREEK 2 57.0
END DESCRIPTION:
XS GIS Cut Line= 3
      2481174.98     13757724.99        2480075.       13756925.
      2479475.04     13757224.98
#Sta/Elev= 30
  3635.6  330.25  3727.9  329.45  3793.6  329.36  3858.1  327.05  3900.3  323.99
  3965.2  316.31  3979.9   316.6  4000.7  313.55  4065.6  308.35    4187  303.98
  4213.4  304.67  4243.4  303.96  4272.8   301.5  4408.8  304.76  4833.1  303.21
  4938.2   302.6  4952.8  298.43    4959   299.6  4967.5  296.16  4973.7  296.93
  4982.2  293.25  4998.5  293.08  4999.7  289.11  5000.2  288.61  5019.7  289.11
  5026.5  296.37  5151.9  298.88  5227.7  299.77  5479.3  307.23  5666.5  309.42
#Mann= 7 ,-1 , 0
  3635.6     .05       0  3727.9     .07       0  4213.4     .05       0
  4833.1      .1       0  4999.7     .05       0  5019.7      .1       0
  5151.9     .05       0
Bank Sta=4999.7,5019.7
XS Rating Curve= 0 ,0
Exp/Cntr=0.3,0.1

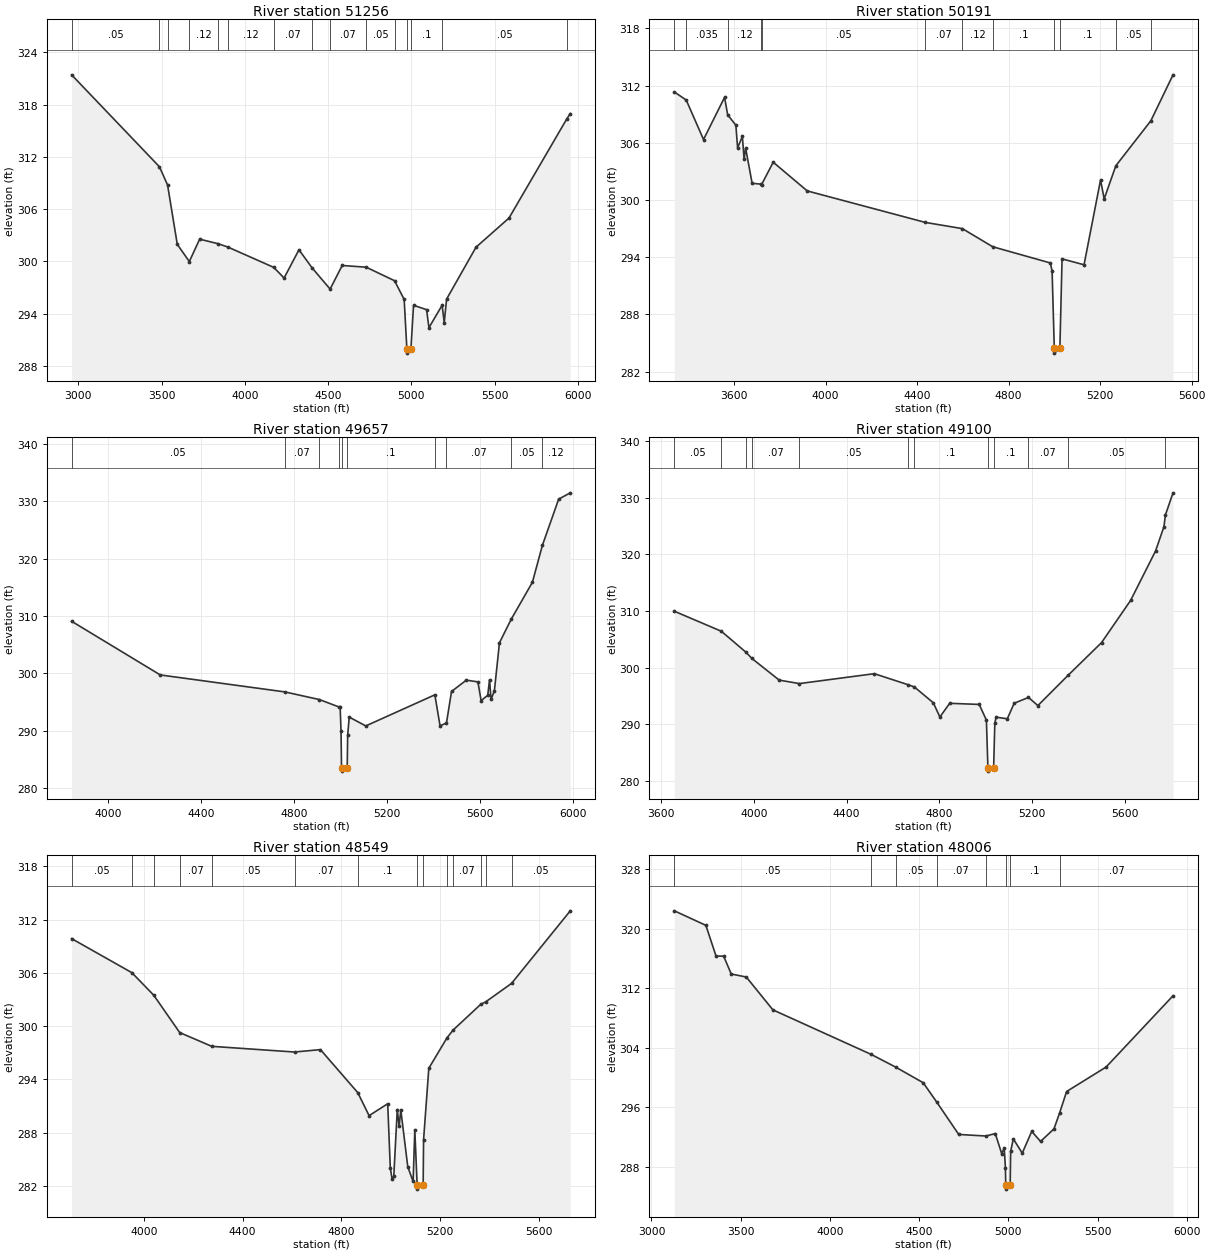
Type RM Length L Ch R = 1 ,51256   ,1065,1065,1065
BEGIN DESCRIPTION:
DENTON CREEK 2 56.0
END DESCRIPTION:
XS GIS Cut Line= 4
      2481437.31     13757053.56      2479676.02     13756176.02
        2479625.       13756125.        2478925.       13755475.
#Sta/Elev= 30
  2959.5  321.41    3487  310.86  3535.9  308.77  3594.3  301.95  3666.6  299.98
  3728.6  302.55    3839  302.03  3898.5  301.64  4173.8  299.31  4235.7  298.09
  4325.1  301.33  4403.7  299.26  4512.2  296.82  4584.8  299.53  4729.2  299.33
  4899.2  297.78    4957  295.63  4973.2  289.97  4973.7  289.47  4997.5  289.97
  5013.4  294.96  5091.6  294.46  5105.7  292.39    5185  294.97  5197.6  292.97
  5211.8  295.67  5388.6  301.63  5586.5  304.97  5933.4  316.34  5954.7  316.96
#Mann= 15 ,-1 , 0
  2959.5     .05       0    3487     .12       0  3535.9    .035       0
  3666.6     .12       0    3839     .07       0  3898.5     .12       0
  4173.8     .07       0  4403.7     .12       0  4512.2     .07       0
  4729.2     .05       0  4899.2      .1       0  4973.2     .05       0
  4997.5      .1       0    5185     .05       0  5933.4     .12       0
Bank Sta=4973.2,4997.5
XS Rating Curve= 0 ,0
Exp/Cntr=0.3,0.1

Type RM Length L Ch R = 1 ,50191   ,534,534,534
BEGIN DESCRIPTION:
DENTON CREEK 2 55.0
END DESCRIPTION:
XS GIS Cut Line= 3
      2480924.99     13756574.99        2479675.       13755475.
      2479225.04     13755225.02
#Sta/Elev= 30
  3338.7  311.32  3390.6  310.48  3466.3  306.34  3558.3  310.76  3571.8  308.93
  3607.7  307.84  3615.2  305.47  3636.1  306.66  3643.7  304.27  3650.4  305.43
  3678.8  301.75  3719.1  301.66  3719.8   301.6  3770.9  303.96  3919.8  300.95
    4436  297.65  4597.6     297  4730.5   295.1  4982.4   293.4    4990  292.54
  4999.6  284.45  5000.1  283.95    5024  284.45  5033.5  293.83  5129.6  293.21
  5201.7  302.09  5217.7  300.12  5268.6  303.59  5421.8  308.31  5518.5  313.12
#Mann= 12 ,-1 , 0
  3338.7     .07       0  3390.6    .035       0  3571.8     .12       0
  3719.1     .07       0  3719.8     .05       0    4436     .07       0
  4597.6     .12       0  4730.5      .1       0  4999.6     .05       0
    5024      .1       0  5268.6     .05       0  5421.8     .07       0
Bank Sta=4999.6,5024
XS Rating Curve= 0 ,0
Exp/Cntr=0.3,0.1

Type RM Length L Ch R = 1 ,49657   ,557,557,557
BEGIN DESCRIPTION:
DENTON CREEK 2 54.0
END DESCRIPTION:
XS GIS Cut Line= 3
      2481025.03     13756025.02        2480075.       13755375.
      2479424.99     13754624.99
#Sta/Elev= 30
  3844.6  309.07  4225.8   299.7    4761  296.74    4910   295.4  4995.1  294.09
    4999  294.09  5002.8  289.87  5004.9  283.41  5005.4  282.91  5029.3  283.41
  5031.3  289.14    5038  292.34  5109.2   290.8  5406.1  296.23  5428.3  290.84
  5455.9  291.29  5477.7  296.81  5541.3  298.79  5591.2  298.49  5604.9  295.22
  5633.4  296.14  5641.1  298.87  5647.7  295.43  5661.9  296.91  5683.8  305.32
  5734.1  309.41  5825.3  315.87  5868.3  322.32  5938.3  330.39  5988.2  331.49
#Mann= 10 ,-1 , 0
  3844.6     .05       0    4761     .07       0    4910     .05       0
  4995.1      .1       0  5004.9     .05       0  5029.3      .1       0
  5406.1     .05       0  5455.9     .07       0  5734.1     .05       0
  5868.3     .12       0
Bank Sta=5004.9,5029.3
XS Rating Curve= 0 ,0
Exp/Cntr=0.3,0.1

Type RM Length L Ch R = 1 ,49100   ,551,551,551
BEGIN DESCRIPTION:
DENTON CREEK 2 53.0
END DESCRIPTION:
XS GIS Cut Line= 3
      2481174.98     13755874.98        2480225.       13754925.
      2479475.04     13754625.02
#Sta/Elev= 30
  3656.8  309.96  3859.6  306.42  3965.6  302.71    3991  301.62  4109.3  297.77
  4196.3  297.16  4519.4  298.91  4664.2  296.97  4691.8  296.58    4774  293.76
  4802.3  291.25  4844.7  293.67    4972  293.47    5003   290.7  5009.6  282.17
  5010.1  281.67  5034.1  282.17  5039.3  290.11  5044.7  291.22  5093.2  290.93
  5122.8  293.68  5184.6  294.71  5225.1  293.27  5355.5  298.63  5499.7  304.41
  5624.9  311.86  5732.7  320.62    5769  324.94    5775  326.96    5808  330.91
#Mann= 12 ,-1 , 0
  3656.8     .05       0  3859.6    .035       0  3965.6     .05       0
    3991     .07       0  4196.3     .05       0  4664.2     .07       0
  4691.8      .1       0  5009.6     .05       0  5034.1      .1       0
  5184.6     .07       0  5355.5     .05       0    5775     .12       0
Bank Sta=5009.6,5034.1
XS Rating Curve= 0 ,0
Exp/Cntr=0.3,0.1

Type RM Length L Ch R = 1 ,48549   ,543,543,543
BEGIN DESCRIPTION:
DENTON CREEK 2 52.0
END DESCRIPTION:
XS GIS Cut Line= 3
      2481225.01     13755825.01        2480575.       13754725.
      2480075.01     13754175.01
#Sta/Elev= 30
    3707  309.87  3951.3  306.03    4040  303.49  4145.2  299.28  4275.1  297.73
  4610.4  297.09  4715.5  297.36  4866.9  292.51  4912.6  289.92  4988.1  291.26
  4998.6  284.03    5006  282.73  5012.7  283.09  5026.9  290.61  5034.4  288.71
  5041.1  290.57  5069.5  284.15  5091.1   282.5  5097.9  288.34  5107.3  282.14
  5107.8  281.64  5131.8  282.14  5133.4  287.18  5154.7  295.26    5228  298.67
  5252.2  299.54  5364.5  302.45  5385.6  302.75  5489.9  304.82    5728     313
#Mann= 14 ,-1 , 0
    3707     .05       0  3951.3    .035       0    4040     .05       0
  4145.2     .07       0  4275.1     .05       0  4610.4     .07       0
  4866.9      .1       0  5107.3     .05       0  5131.8      .1       0
    5228     .05       0  5252.2     .07       0  5364.5     .05       0
  5385.6     .07       0  5489.9     .05       0
Bank Sta=5107.3,5131.8
XS Rating Curve= 0 ,0
Exp/Cntr=0.3,0.1

Type RM Length L Ch R = 1 ,48006   ,585,585,585
BEGIN DESCRIPTION:
DENTON CREEK 2 51.0
END DESCRIPTION:
XS GIS Cut Line= 3
      2482224.99     13755924.99        2480975.       13754525.
        2480175.       13754075.
#Sta/Elev= 30
  3128.1  322.42  3304.9  320.47  3361.8  316.34  3404.4  316.33    3447  313.93
  3531.5  313.52  3680.3  309.11  4231.3  303.12  4367.9  301.42    4523  299.31
  4598.4  296.72  4721.9  292.36  4874.3  292.15  4926.8  292.48  4962.7  289.78
  4976.9  290.53  4983.6  287.91  4985.5  285.51    4986  285.01  5010.2  285.51
  5012.9   290.1  5027.9  291.76  5077.9  289.85  5131.1  292.77  5180.5  291.42
  5255.7  293.11  5287.9  295.29  5326.5  298.13  5547.7  301.42  5922.8     311
#Mann= 8 ,-1 , 0
  3128.1     .05       0  4231.3    .035       0  4367.9     .05       0
  4598.4     .07       0  4874.3      .1       0  4985.5     .05       0
  5010.2      .1       0  5287.9     .07       0
Bank Sta=4985.5,5010.2
XS Rating Curve= 0 ,0
Exp/Cntr=0.3,0.1

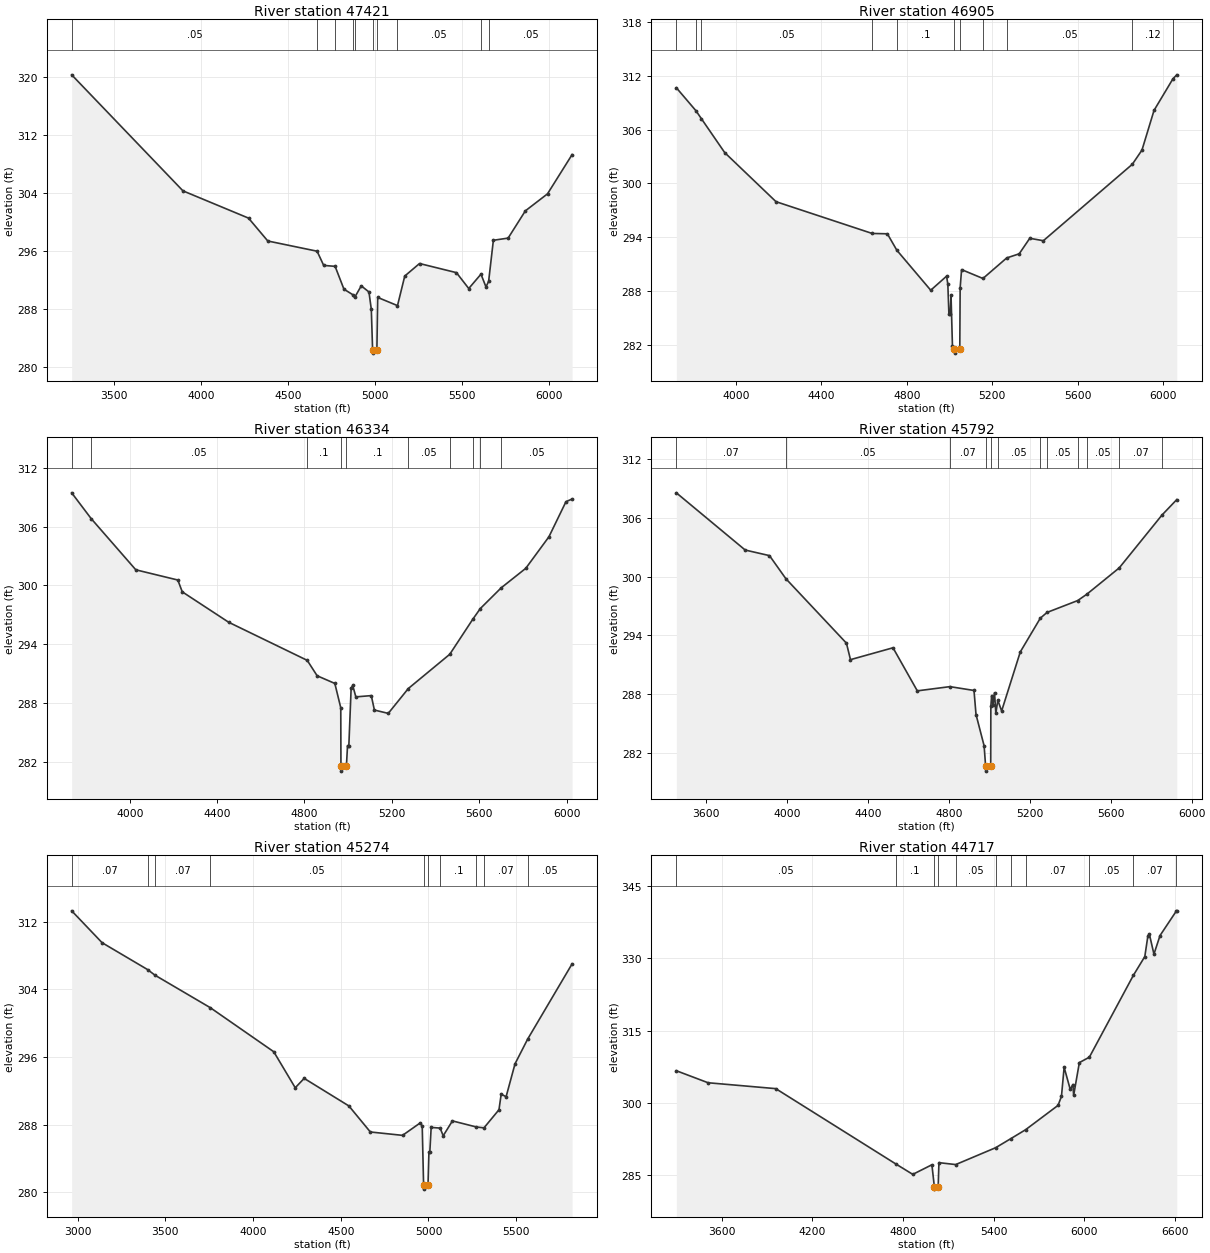
Type RM Length L Ch R = 1 ,47421   ,516,516,516
BEGIN DESCRIPTION:
DENTON CREEK 2 50.0
END DESCRIPTION:
XS GIS Cut Line= 3
      2482224.98     13755724.96        2481425.       13754175.
        2480625.       13753375.
#Sta/Elev= 30
    3256   320.3  3895.5  304.28  4272.1  300.52  4382.9  297.36  4666.2  295.95
    4704  293.99  4769.7  293.86  4820.4  290.71  4869.7  289.97  4882.1  289.57
  4919.9  291.17  4964.2  290.32  4977.7  287.93  4985.1  282.38  4985.6  281.88
  5009.8  282.38  5014.4  289.57  5128.2  288.44  5169.9  292.52  5254.8  294.25
  5466.9  292.99  5537.6   290.8  5607.9  292.78  5636.6  291.02  5651.9  291.79
  5679.1  297.46  5763.9  297.76  5862.9  301.52  5990.2  303.87  6131.6  309.29
#Mann= 10 ,-1 , 0
    3256     .05       0  4666.2     .12       0  4769.7      .1       0
  4869.7     .12       0  4882.1      .1       0  4985.1     .05       0
  5009.8      .1       0  5128.2     .05       0  5607.9     .12       0
  5651.9     .05       0
Bank Sta=4985.1,5009.8
XS Rating Curve= 0 ,0
Exp/Cntr=0.3,0.1

Type RM Length L Ch R = 1 ,46905   ,571,571,571
BEGIN DESCRIPTION:
DENTON CREEK 2 49.0
END DESCRIPTION:
XS GIS Cut Line= 3
        2482425.     13754975.01        2481775.       13753875.
      2480975.01     13753175.01
#Sta/Elev= 30
  3722.3  310.67  3813.9  308.11  3839.8  307.21  3948.6  303.44  4188.5  297.97
    4638  294.43  4709.4  294.39  4753.6  292.56  4912.2   288.1  4986.4  289.67
  4992.2  288.76  4997.1   285.5  5003.3   285.5  5007.1  287.54  5013.8  281.84
  5023.1  281.59  5023.6  281.09  5048.1  281.59  5049.8  288.37  5056.5   290.4
  5156.4  289.41  5267.6   291.7    5326  292.16  5375.4  293.89    5439  293.62
  5855.1  302.14  5900.2  303.72  5956.7  308.15  6044.9  311.66    6063  312.11
#Mann= 11 ,-1 , 0
  3722.3     .05       0  3813.9     .07       0  3839.8     .05       0
    4638    .035       0  4753.6      .1       0  5023.1     .05       0
  5048.1      .1       0  5156.4     .12       0  5267.6     .05       0
  5855.1     .12       0  6044.9     .07       0
Bank Sta=5023.1,5048.1
XS Rating Curve= 0 ,0
Exp/Cntr=0.3,0.1

Type RM Length L Ch R = 1 ,46334   ,542,542,542
BEGIN DESCRIPTION:
DENTON CREEK 2 48.0
END DESCRIPTION:
XS GIS Cut Line= 3
        2482425.     13754874.97        2482225.       13753625.
      2481524.99     13752874.99
#Sta/Elev= 30
  3733.9  309.43  3822.9  306.81  4027.6  301.59    4220  300.55  4240.2  299.35
  4452.9  296.25  4812.6  292.37    4858   290.8    4939  290.02  4966.2  287.54
    4967  281.59  4967.5  281.09    4992  281.59  4997.2  283.69  5003.2  283.69
  5013.7  289.53    5021  289.82  5035.2  288.65    5106  288.78  5120.2  287.31
  5183.7  286.97  5275.5   289.5  5465.4  292.99  5571.2  296.57  5605.5  297.65
  5701.1  299.76  5813.4  301.74  5919.4  304.95  5997.6  308.53  6025.7   308.8
#Mann= 10 ,-1 , 0
  3733.9     .07       0  3822.9     .05       0  4812.6      .1       0
    4967     .05       0    4992      .1       0  5275.5     .05       0
  5465.4     .07       0  5571.2     .05       0  5605.5     .07       0
  5701.1     .05       0
Bank Sta=4967,4992
XS Rating Curve= 0 ,0
Exp/Cntr=0.3,0.1

Type RM Length L Ch R = 1 ,45792   ,518,518,518
BEGIN DESCRIPTION:
DENTON CREEK 2 47.0
END DESCRIPTION:
XS GIS Cut Line= 3
        2482575.     13754775.04        2482525.       13753225.
        2481925.       13752525.
#Sta/Elev= 30
  3453.7  308.53  3793.9   302.7    3914  302.13  3994.9  299.78  4294.2  293.21
  4314.2  291.53  4524.3  292.74  4644.4  288.35  4805.5  288.78  4924.5  288.39
  4934.5  285.94  4974.5  282.75    4982  280.67  4982.5  280.17  5007.1  280.67
  5007.8  286.76  5011.7  287.87  5018.3  286.93  5025.9  288.16  5032.5  286.05
  5042.1   287.4  5061.1   286.3  5153.3  292.32  5252.4  295.76  5285.3  296.34
  5436.8  297.55  5481.6  298.19  5642.2  300.88  5853.2  306.26  5926.5  307.84
#Mann= 12 ,-1 , 0
  3453.7     .07       0  3994.9     .05       0  4805.5     .07       0
    4982     .05       0  5007.1     .07       0  5042.1     .05       0
  5252.4    .035       0  5285.3     .05       0  5436.8    .035       0
  5481.6     .05       0  5642.2     .07       0  5853.2     .05       0
Bank Sta=4982,5007.1
XS Rating Curve= 0 ,0
Exp/Cntr=0.3,0.1

Type RM Length L Ch R = 1 ,45274   ,557,557,557
BEGIN DESCRIPTION:
DENTON CREEK 2 46.0
END DESCRIPTION:
XS GIS Cut Line= 3
      2482575.01     13755024.97        2482975.       13753025.
        2483125.     13752225.02
#Sta/Elev= 30
  2965.6  313.28  3138.9  309.51  3398.4  306.33  3440.3  305.67  3756.2  301.82
  4117.9  296.61  4240.3  292.35  4291.3  293.46  4546.3   290.2  4668.6  287.12
  4852.2  286.72  4954.2  288.21  4964.4  287.79  4972.2  280.86  4972.7  280.36
  4997.4  280.86  5002.6  284.73  5007.7  284.73  5015.4  287.66  5066.6  287.58
    5084  286.67  5136.6  288.43  5273.3  287.71  5316.6  287.61    5402  289.75
  5414.7  291.59  5442.7  291.29  5493.5  295.18  5565.2  298.09  5819.1  307.01
#Mann= 10 ,-1 , 0
  2965.6     .07       0  3398.4     .05       0  3440.3     .07       0
  3756.2     .05       0  4972.2     .05       0  4997.4     .05       0
  5066.6      .1       0  5273.3     .05       0  5316.6     .07       0
  5565.2     .05       0
Bank Sta=4972.2,4997.4
XS Rating Curve= 0 ,0
Exp/Cntr=0.3,0.1

Type RM Length L Ch R = 1 ,44717   ,552,552,552
BEGIN DESCRIPTION:
DENTON CREEK 2 45.0
END DESCRIPTION:
XS GIS Cut Line= 3
      2482775.02     13754624.96        2483475.       13753075.
      2483674.99     13751475.04
#Sta/Elev= 30
    3299  306.71  3509.2  304.22  3957.3     303  4750.9  287.41  4864.3  285.23
  4990.9  287.22  5007.2  282.67  5007.7  282.17  5032.5  282.67  5037.5  287.66
  5148.5  287.26  5413.3  290.76  5512.1  292.61    5611  294.48  5826.1  299.53
  5848.7   301.4  5866.4  307.43  5906.7  302.85  5924.3  303.85  5929.4  301.62
  5967.2   308.4  6033.4  309.52  6324.6  326.48  6400.5  330.38  6420.7  334.62
  6430.7  335.02    6461  330.88  6501.3  334.74    6608  339.76  6612.1  339.86
#Mann= 11 ,-1 , 0
    3299     .05       0  4750.9      .1       0  5007.2     .05       0
  5032.5      .1       0  5148.5     .05       0  5413.3     .07       0
  5512.1    .035       0    5611     .07       0  6033.4     .05       0
  6324.6     .07       0    6608     .05       0
Bank Sta=5007.2,5032.5
XS Rating Curve= 0 ,0
Exp/Cntr=0.3,0.1

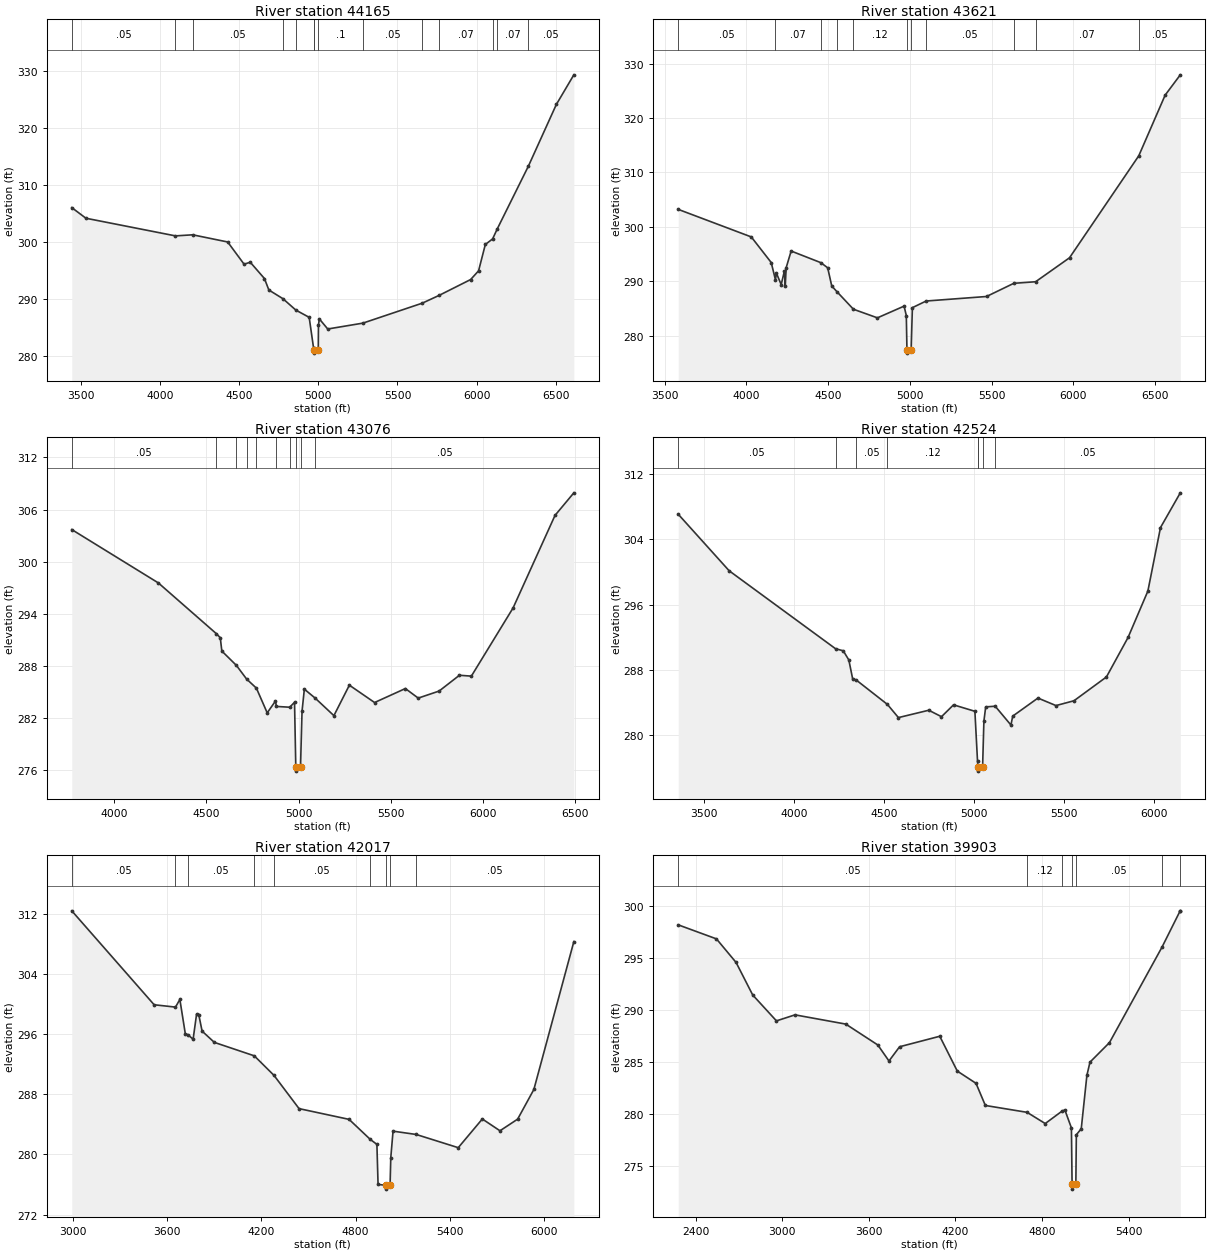
Type RM Length L Ch R = 1 ,44165   ,544,544,544
BEGIN DESCRIPTION:
DENTON CREEK 2 44.0
END DESCRIPTION:
XS GIS Cut Line= 3
      2483175.01     13754724.99        2483875.       13753325.
        2483775.     13751724.96
#Sta/Elev= 30
  3444.6  306.03    3534  304.16  4099.1  301.06  4207.7  301.25  4428.5  299.99
  4531.9  296.09    4571  296.43  4660.4  293.57  4688.4  291.55  4777.4  290.02
  4858.8  288.02  4942.8  286.75  4970.4  281.37  4974.8  280.96  4975.3  280.46
  5000.2  280.96  5001.4  285.41    5007  286.47  5059.9   284.7  5281.6  285.73
  5656.5  289.24  5761.6  290.59  5961.7  293.39  6011.8  294.92  6054.4  299.55
  6100.4  300.53  6130.1  302.31  6326.1  313.31  6502.7  324.16    6613  329.36
#Mann= 14 ,-1 , 0
  3444.6     .05       0  4099.1    .035       0  4207.7     .05       0
  4777.4    .035       0  4858.8     .05       0  4970.4      .1       0
  4974.8     .05       0  5000.2      .1       0  5281.6     .05       0
  5656.5    .035       0  5761.6     .07       0  6100.4     .05       0
  6130.1     .07       0  6326.1     .05       0
Bank Sta=4974.8,5000.2
XS Rating Curve= 0 ,0
Exp/Cntr=0.3,0.1

Type RM Length L Ch R = 1 ,43621   ,545,545,545
BEGIN DESCRIPTION:
DENTON CREEK 2 43.0
END DESCRIPTION:
XS GIS Cut Line= 3
      2484075.01     13754724.97        2484325.       13753325.
      2483924.99     13751724.96
#Sta/Elev= 30
  3582.6  303.22  4029.5  298.16  4151.4  293.46  4177.1  290.31  4183.4  291.49
  4212.4  289.41  4232.2  291.91  4237.3  289.14  4242.8   292.5  4273.3  295.57
  4455.3  293.43  4496.8  292.49  4521.7  289.15  4554.8  288.06  4654.3  284.88
    4801   283.3  4964.1  285.45  4977.8  283.73  4981.8  277.32  4982.3  276.82
  5007.3  277.32    5015  285.17  5099.2  286.39  5468.6  287.22  5635.3  289.64
  5768.9  289.93  5976.2  294.33  6399.9  313.06  6561.2   324.2    6654  327.93
#Mann= 11 ,-1 , 0
  3582.6     .05       0  4177.1     .07       0  4455.3    .035       0
  4554.8     .07       0  4654.3     .12       0  4981.8     .05       0
  5007.3     .12       0  5099.2     .05       0  5635.3    .035       0
  5768.9     .07       0  6399.9     .05       0
Bank Sta=4981.8,5007.3
XS Rating Curve= 0 ,0
Exp/Cntr=0.3,0.1

Type RM Length L Ch R = 1 ,43076   ,552,552,552
BEGIN DESCRIPTION:
DENTON CREEK 2 42.0
END DESCRIPTION:
XS GIS Cut Line= 3
      2484224.99     13754675.02        2484775.       13753575.
        2485125.     13752125.01
#Sta/Elev= 30
  3770.2   303.7  4239.8  297.55  4553.9  291.71  4575.2  291.24  4583.6  289.71
  4662.4  288.06  4718.1  286.48  4770.9  285.44  4829.6  282.59  4874.3  283.95
  4879.4  283.33  4951.5  283.24  4977.7  283.81  4984.5  276.38    4985  275.88
  5010.1  276.38  5018.4  282.79  5030.9  285.32  5089.4  284.29  5191.1  282.27
  5274.9  285.78  5411.6  283.78  5578.4  285.39  5648.2  284.29  5761.3   285.1
  5871.5  286.92  5936.2  286.82  6162.5  294.68  6389.6  305.33  6491.7  307.93
#Mann= 10 ,-1 , 0
  3770.2     .05       0  4553.9    .035       0  4662.4     .05       0
  4718.1    .035       0  4770.9     .05       0  4879.4     .12       0
  4951.5      .1       0  4984.5     .05       0  5010.1      .1       0
  5089.4     .05       0
Bank Sta=4984.5,5010.1
XS Rating Curve= 0 ,0
Exp/Cntr=0.3,0.1

Type RM Length L Ch R = 1 ,42524   ,507,507,507
BEGIN DESCRIPTION:
DENTON CREEK 2 41.0
END DESCRIPTION:
XS GIS Cut Line= 3
      2484324.98     13754825.04        2485175.       13753425.
        2485225.     13752274.96
#Sta/Elev= 30
  3357.5  307.06  3640.5  300.14  4231.1  290.61  4274.3  290.35  4305.1  289.23
  4326.7  286.89  4344.3  286.81  4519.6  283.79  4580.6  282.18  4749.2  283.08
  4819.9  282.29  4886.8  283.74  5005.4  282.95  5019.9   276.9  5022.6  276.13
  5023.1  275.63  5048.2  276.13  5055.4  281.73  5065.4  283.49  5118.3  283.57
  5205.6  281.27  5215.6  282.36  5355.7  284.57  5455.8  283.65  5555.9  284.24
  5736.1  287.15  5856.2  291.98  5966.3  297.66  6036.4  305.43  6146.5  309.68
#Mann= 8 ,-1 , 0
  3357.5     .05       0  4231.1    .035       0  4344.3     .05       0
  4519.6     .12       0  5019.9      .1       0  5022.6     .05       0
  5048.2      .1       0  5118.3     .05       0
Bank Sta=5022.6,5048.2
XS Rating Curve= 0 ,0
Exp/Cntr=0.3,0.1

Type RM Length L Ch R = 1 ,42017   ,2114,2114,2114
BEGIN DESCRIPTION:
DENTON CREEK 2 40.0
END DESCRIPTION:
XS GIS Cut Line= 3
      2484274.99     13755075.01        2485575.       13753525.
      2485324.99     13752374.97
#Sta/Elev= 30
  2990.8  312.44  3515.8  299.93  3651.9  299.62  3679.7  300.64  3714.8  296.02
  3729.6  295.97  3764.2  295.34  3786.3  298.69    3800  298.63  3821.5  296.42
  3899.5  294.92  4154.1  293.13  4279.6  290.53  4439.4   286.1  4758.2  284.67
  4892.8  282.01  4935.5  281.34  4942.9  276.01  4993.8  275.88  4994.3  275.38
  5019.5  275.88    5024  279.57  5038.4   283.1  5185.8  282.66  5453.9   280.9
  5607.4  284.72  5719.9  283.15  5832.5   284.7  5935.9  288.65  6190.7  308.34
#Mann= 9 ,-1 , 0
  2990.8     .05       0  3651.9     .07       0  3729.6     .05       0
  4154.1    .035       0  4279.6     .05       0  4892.8     .12       0
  4993.8     .05       0  5019.5     .12       0  5185.8     .05       0
Bank Sta=4993.8,5019.5
XS Rating Curve= 0 ,0
Exp/Cntr=0.3,0.1

Type RM Length L Ch R = 1 ,39903   ,544,544,544
BEGIN DESCRIPTION:
DENTON CREEK 2 39.0
END DESCRIPTION:
XS GIS Cut Line= 3
      2485225.01     13754624.99        2486825.       13752425.
        2486925.     13751675.02
#Sta/Elev= 30
  2280.1  298.22  2544.8  296.87  2680.8   294.6  2795.9  291.47  2960.2  288.98
  3088.8  289.56  3440.5  288.67  3662.3  286.66  3739.5  285.12    3813  286.49
  4091.2   287.5  4212.5  284.15  4342.3  282.97  4406.9  280.84  4695.9  280.18
  4821.5   279.1  4936.3  280.28  4957.5  280.41  5002.9  278.68  5007.5  273.29
    5008  272.79  5033.6  273.29    5037  278.02    5071   278.6  5110.1  283.74
  5131.5  285.01  5266.5  286.89  5630.4  296.08    5756  299.57    5757  299.57
#Mann= 7 ,-1 , 0
  2280.1     .05       0  4695.9     .12       0  4936.3     .05       0
  5007.5     .05       0  5033.6     .05       0  5630.4     .07       0
    5756     .05       0
Bank Sta=5007.5,5033.6
XS Rating Curve= 0 ,0
Exp/Cntr=0.3,0.1