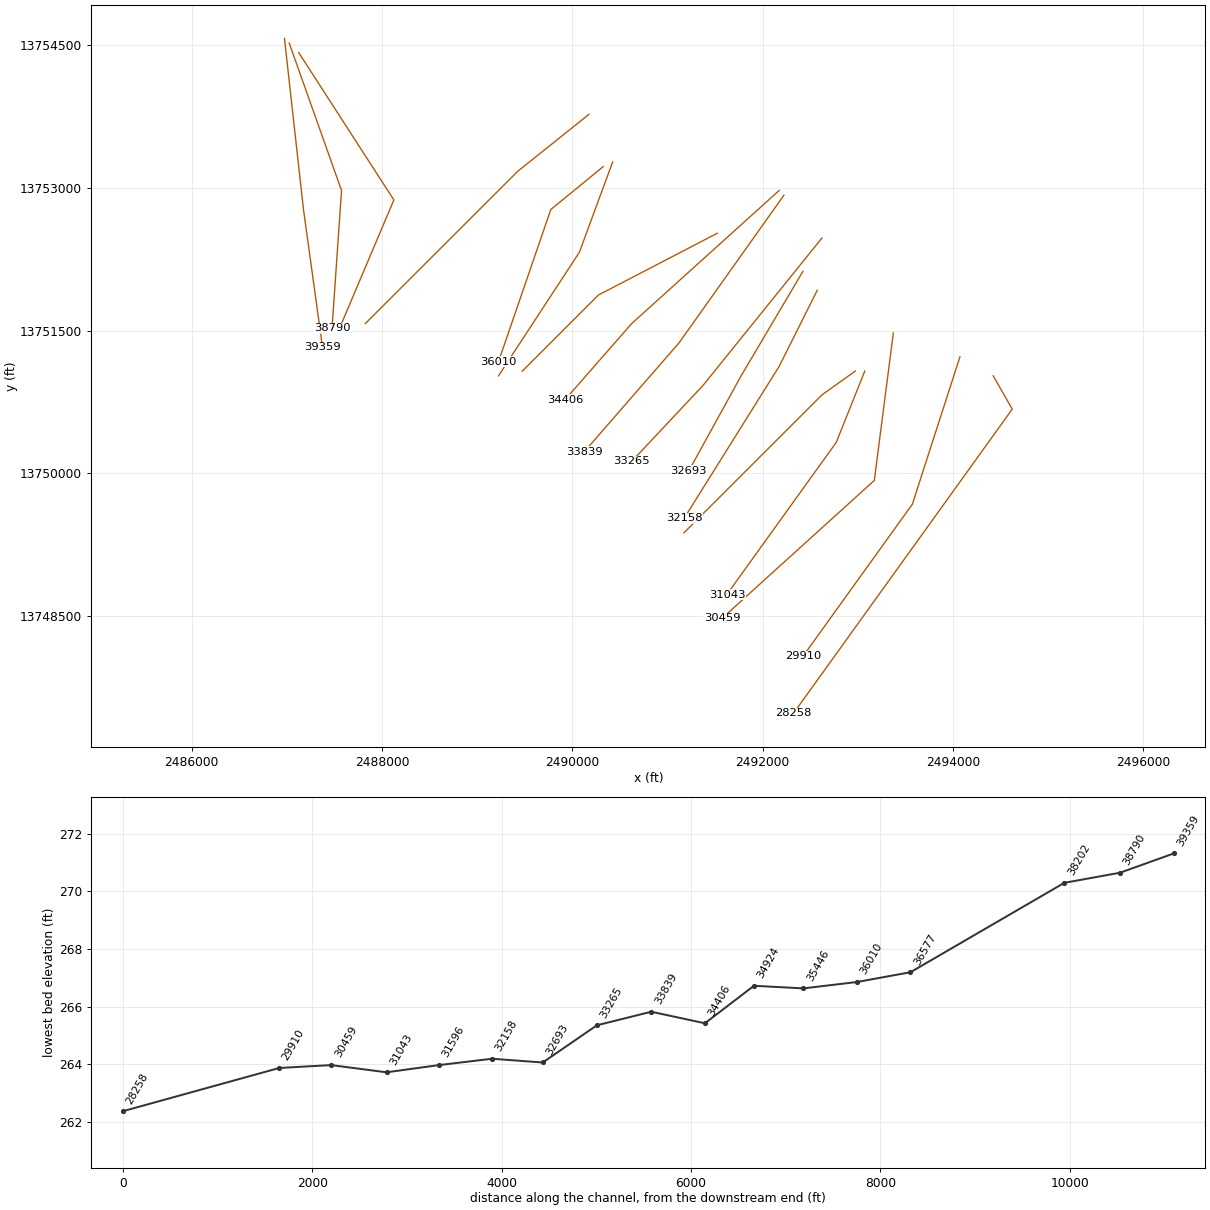
HEC-RAS study DENTON CREEK 2.prj: DENTON CREEK 2 Base Level Engineering

--- DENTON CREEK 2.g01 (geometry) --- (continued)

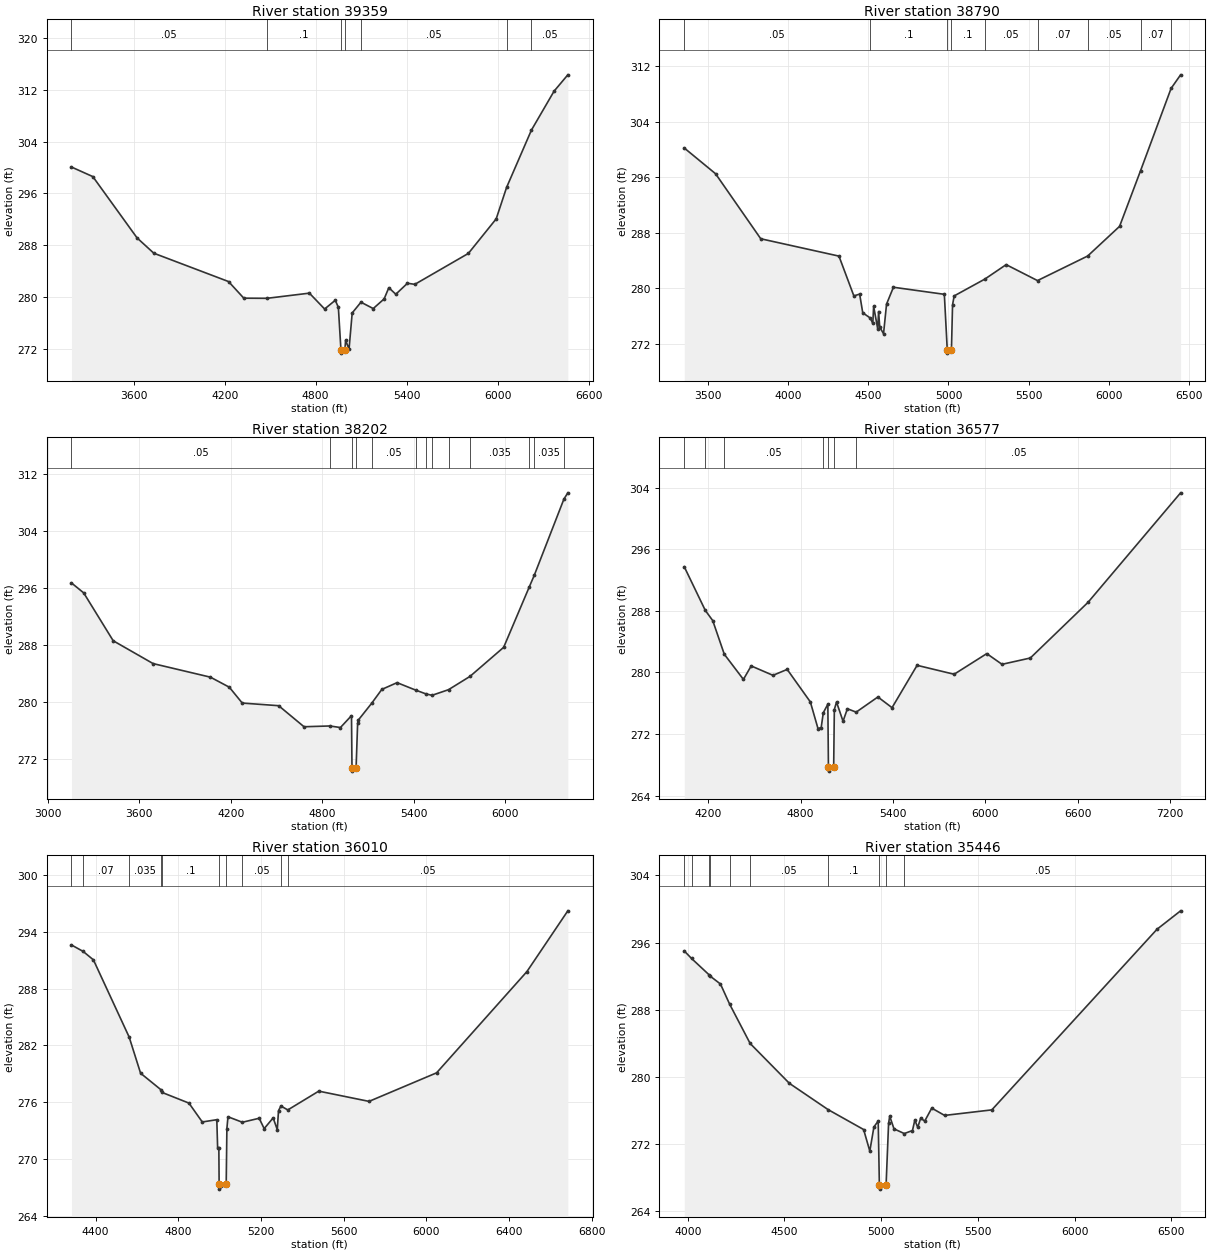
Type RM Length L Ch R = 1 ,39359   ,569,569,569
BEGIN DESCRIPTION:
DENTON CREEK 2 38.0
END DESCRIPTION:
XS GIS Cut Line= 3
        2486975.       13754575.        2487175.       13752775.
        2487375.       13751325.
#Sta/Elev= 30
  3188.8  300.07  3329.7  298.59  3621.4  289.12  3732.1  286.75  4225.1  282.37
  4325.8   279.8  4478.5  279.78  4758.4  280.58    4859  278.13  4929.4  279.48
  4949.6  278.38  4966.6  271.81  4967.1  271.31  4992.8  271.81  4997.4  273.29
  5020.1  271.94  5040.9  277.52  5098.7  279.18  5179.7   278.2  5251.6  279.69
  5282.5  281.42  5328.6  280.41  5405.6  282.11  5454.1  281.94  5807.4  286.72
    5991  292.06  6059.6  296.92  6223.3  305.77  6372.7  311.79  6463.6  314.32
#Mann= 7 ,-1 , 0
  3188.8     .05       0  4478.5      .1       0  4966.6     .05       0
  4992.8      .1       0  5098.7     .05       0  6059.6     .07       0
  6223.3     .05       0
Bank Sta=4966.6,4992.8
XS Rating Curve= 0 ,0
Exp/Cntr=0.3,0.1

Type RM Length L Ch R = 1 ,38790   ,588,588,588
BEGIN DESCRIPTION:
DENTON CREEK 2 37.0
END DESCRIPTION:
XS GIS Cut Line= 3
      2487025.01     13754524.98        2487575.       13752975.
        2487475.     13751525.01
#Sta/Elev= 30
  3350.9  300.22  3546.2  296.51  3828.4  287.13  4316.5  284.63  4409.6  278.89
  4445.7  279.15    4465  276.46  4511.9   275.7  4527.7  274.92    4533  277.39
  4558.6  274.12  4563.9  276.64  4571.1  274.39  4594.8  273.44  4613.6  277.71
  4656.5  280.14  4974.3  279.12  4992.5  271.14    4993  270.64  5018.7  271.14
  5025.6  277.62  5035.7  278.89  5227.4  281.32  5360.2   283.4  5555.8   281.1
  5868.8  284.64  6068.1  288.92  6198.8  296.93  6389.6  308.81    6449  310.77
#Mann= 9 ,-1 , 0
  3350.9     .05       0  4511.9      .1       0  4992.5     .05       0
  5018.7      .1       0  5227.4     .05       0  5555.8     .07       0
  5868.8     .05       0  6198.8     .07       0  6389.6     .05       0
Bank Sta=4992.5,5018.7
XS Rating Curve= 0 ,0
Exp/Cntr=0.3,0.1

Type RM Length L Ch R = 1 ,38202   ,1625,1625,1625
BEGIN DESCRIPTION:
DENTON CREEK 2 36.0
END DESCRIPTION:
XS GIS Cut Line= 3
      2487124.99     13754425.01        2488125.       13752875.
      2487574.98     13751574.96
#Sta/Elev= 30
  3155.3  296.75  3235.5  295.35    3429  288.62  3690.8  285.41    4067   283.5
  4190.7  282.09  4275.6  279.86  4514.5  279.49  4680.8  276.53  4849.9  276.64
  4919.7  276.42  4992.3  278.09  4995.5  270.79    4996  270.29  5022.5  270.79
  5032.5  276.99  5038.2   277.5    5125  279.84  5191.2  281.78  5291.3  282.73
  5412.3  281.69  5480.5  281.15  5520.5  280.95  5628.7  281.74  5769.7  283.61
  5990.7   287.7    6158  296.16  6190.9   297.8    6386  308.55  6411.5  309.42
#Mann= 13 ,-1 , 0
  3155.3     .05       0  4849.9      .1       0  4995.5     .05       0
  5022.5      .1       0    5125     .05       0  5412.3    .035       0
  5480.5     .05       0  5520.5    .035       0  5628.7     .05       0
  5769.7    .035       0    6158     .05       0  6190.9    .035       0
    6386     .05       0
Bank Sta=4995.5,5022.5
XS Rating Curve= 0 ,0
Exp/Cntr=0.3,0.1

Type RM Length L Ch R = 1 ,36577   ,567,567,567
BEGIN DESCRIPTION:
DENTON CREEK 2 35.0
END DESCRIPTION:
XS GIS Cut Line= 3
      2490175.03     13753775.03        2489425.       13753175.
      2487824.97     13751574.97
#Sta/Elev= 30
  4044.9  293.73  4181.6  288.06  4229.8  286.74  4304.9  282.37  4429.1   279.1
  4479.6  280.85  4621.2  279.63  4713.3   280.4  4863.7  276.18  4913.4  272.72
  4934.2  272.85  4947.8  274.77  4977.4  275.88  4981.2  267.69  4981.9  267.19
  5015.2  267.69  5019.6  275.19  5033.7  276.16  5076.1  273.67  5104.4  275.29
  5161.4  274.85  5302.4  276.82  5394.3  275.43    5557  280.93  5797.4  279.77
  6009.5  282.45  6108.5  281.06  6292.3  281.88  6667.1  289.11  7268.2  303.33
#Mann= 7 ,-1 , 0
  4044.9     .05       0  4181.6    .035       0  4304.9     .05       0
  4947.8      .1       0  4981.2     .05       0  5015.2      .1       0
  5161.4     .05       0
Bank Sta=4981.2,5015.2
XS Rating Curve= 0 ,0
Exp/Cntr=0.3,0.1

Type RM Length L Ch R = 1 ,36010   ,564,564,564
BEGIN DESCRIPTION:
DENTON CREEK 2 34.0
END DESCRIPTION:
XS GIS Cut Line= 3
      2490324.98     13753224.98        2489775.       13752775.
        2489225.       13751175.
#Sta/Elev= 30
  4282.9  292.59  4339.4  291.91  4389.1  291.02  4562.1  282.88  4617.4  279.07
  4714.7  277.35  4721.7  277.04  4851.4  275.92    4916  273.93  4986.3  274.17
  4990.3  271.21  4996.2  271.21  4997.6  267.35  4998.2  266.85  5031.8  267.35
  5035.1  273.23  5040.4  274.48  5109.9   273.9  5191.3  274.32  5215.6  273.23
  5259.1  274.36    5279  273.12    5285  275.12  5296.6  275.61    5330   275.2
  5479.9  277.18  5723.1   276.1  6050.2  279.11  6487.6  289.79  6685.4  296.19
#Mann= 10 ,-1 , 0
  4282.9     .05       0  4339.4     .07       0  4562.1    .035       0
  4714.7     .05       0  4721.7      .1       0  4997.6     .05       0
  5031.8      .1       0  5109.9     .05       0  5296.6     .12       0
    5330     .05       0
Bank Sta=4997.6,5031.8
XS Rating Curve= 0 ,0
Exp/Cntr=0.3,0.1

Type RM Length L Ch R = 1 ,35446   ,522,522,522
BEGIN DESCRIPTION:
DENTON CREEK 2 33.0
END DESCRIPTION:
XS GIS Cut Line= 3
      2490424.99     13753274.98        2490075.       13752325.
      2489225.01     13751025.02
#Sta/Elev= 30
  3982.1     295  4019.6  294.11  4109.9  292.17  4115.1  292.02  4169.3  291.06
  4216.7  288.66  4322.7  283.98  4525.6  279.23  4725.8   276.1  4909.2  273.73
  4941.2  271.16  4962.5  274.04  4984.6  274.74  4990.7  267.13  4991.4  266.63
  5025.4  267.13  5038.3  274.47  5044.2  275.32  5066.2  273.81  5119.4  273.25
  5161.8  273.61  5173.9  274.85    5189  273.99  5204.1  275.07  5225.2  274.74
  5261.4  276.28  5327.8  275.41    5572  276.07  6425.6  297.58  6547.7  299.78
#Mann= 10 ,-1 , 0
  3982.1     .05       0  4019.6     .07       0  4109.9     .05       0
  4115.1     .07       0  4216.7    .035       0  4322.7     .05       0
  4725.8      .1       0  4990.7     .05       0  5025.4      .1       0
  5119.4     .05       0
Bank Sta=4990.7,5025.4
XS Rating Curve= 0 ,0
Exp/Cntr=0.3,0.1

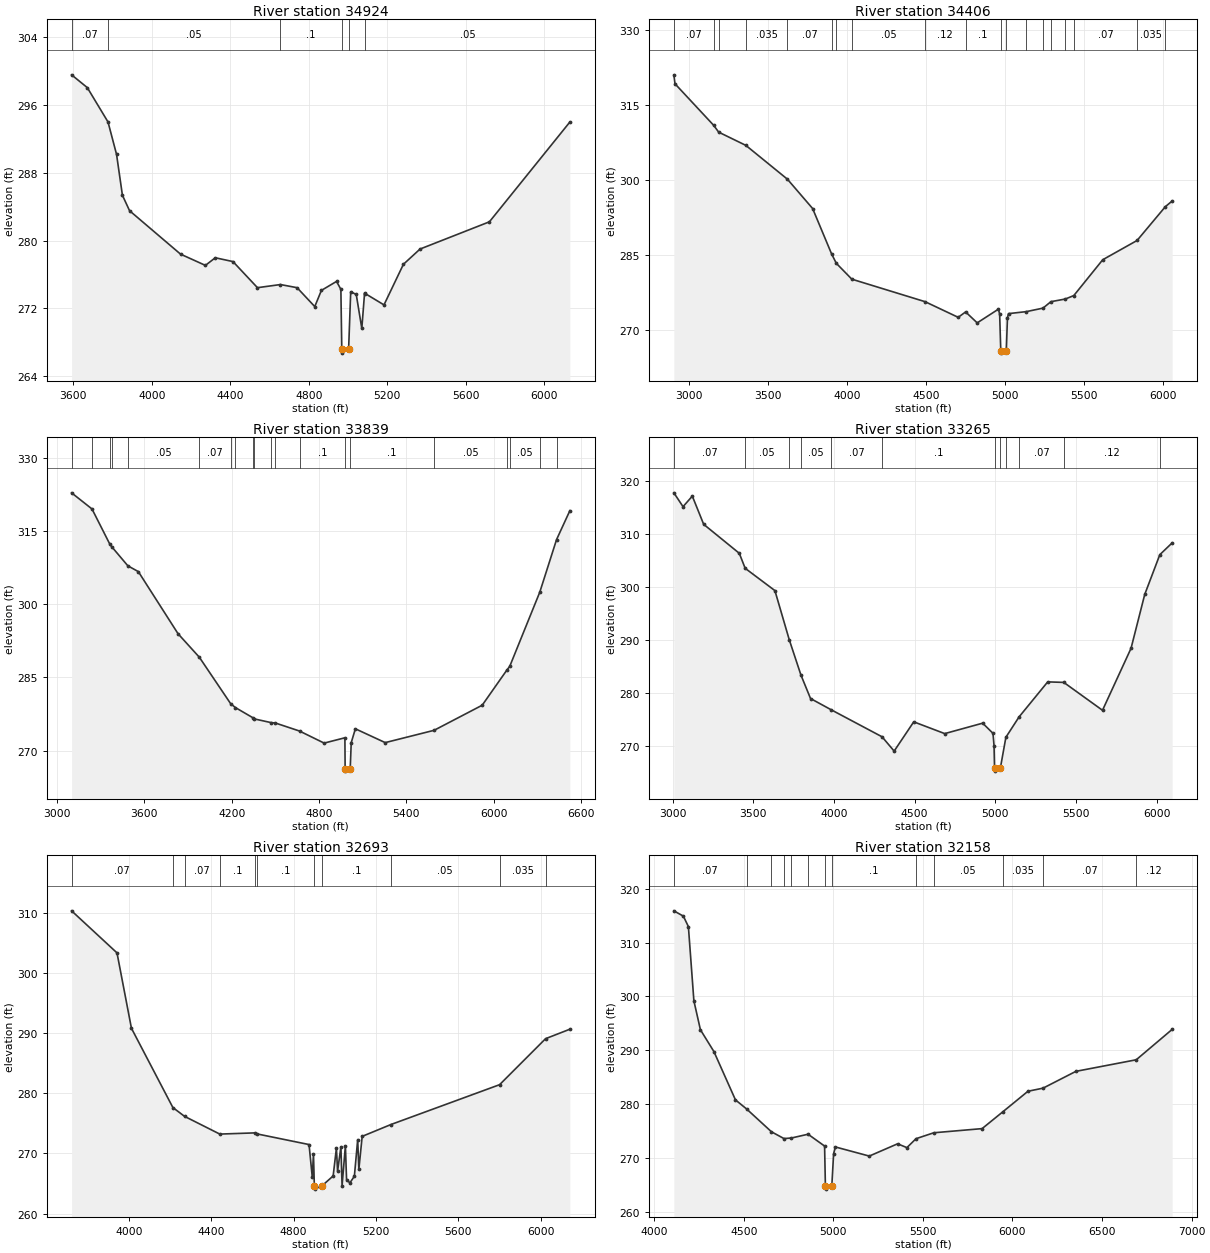
Type RM Length L Ch R = 1 ,34924   ,518,518,518
BEGIN DESCRIPTION:
DENTON CREEK 2 32.0
END DESCRIPTION:
XS GIS Cut Line= 3
      2491524.97     13752524.98        2490275.       13751875.
      2489475.02     13751075.02
#Sta/Elev= 30
  3590.9  299.55  3671.1  298.04  3776.6  293.99  3820.2  290.16  3850.1  285.34
  3886.5  283.52  4146.2   278.4  4273.2  277.07  4323.5  277.97  4413.7  277.52
  4538.5  274.44  4655.8  274.81  4740.5  274.44  4830.7  272.21  4864.5  274.12
  4941.7  275.18  4963.8  274.24  4968.4  267.22  4969.2  266.72  5003.3  267.22
  5013.9  273.96  5042.2  273.64  5070.5  269.63  5084.6  273.81  5087.6  273.75
  5183.6  272.41  5282.6   277.2  5367.5     279    5721  282.21  6131.1  293.98
#Mann= 6 ,-1 , 0
  3590.9     .07       0  3776.6     .05       0  4655.8      .1       0
  4968.4     .05       0  5003.3      .1       0  5087.6     .05       0
Bank Sta=4968.4,5003.3
XS Rating Curve= 0 ,0
Exp/Cntr=0.3,0.1

Type RM Length L Ch R = 1 ,34406   ,567,567,567
BEGIN DESCRIPTION:
DENTON CREEK 2 31.0
END DESCRIPTION:
XS GIS Cut Line= 3
      2492175.04     13752975.03        2490625.       13751575.
      2489925.01     13750775.02
#Sta/Elev= 30
  2906.4  321.08  2913.5  319.29  3158.5  310.97  3189.7  309.62  3361.8  306.97
  3624.5  300.21  3784.1  294.34    3904  285.27  3933.8  283.39  4032.1  280.21
  4495.4  275.71  4704.8  272.58  4751.9  273.66  4825.1  271.47  4959.6  274.22
  4967.1   273.2  4974.2  265.92    4975  265.42  5009.2  265.92  5016.5  272.54
  5023.1  273.32  5135.6  273.72  5241.2  274.42  5291.3  275.71  5382.3  276.24
  5436.1  276.93  5619.2   284.1  5836.3  287.95  6015.5  294.72  6058.1  295.84
#Mann= 19 ,-1 , 0
  2906.4     .07       0  3158.5    .035       0  3189.7     .07       0
  3361.8    .035       0  3624.5     .07       0    3904     .05       0
  3933.8     .07       0  4032.1     .05       0  4495.4     .12       0
  4751.9      .1       0  4974.2     .05       0  5009.2      .1       0
  5135.6     .12       0  5241.2      .1       0  5291.3     .07       0
  5382.3    .035       0  5436.1     .07       0  5836.3    .035       0
  6015.5     .05       0
Bank Sta=4974.2,5009.2
XS Rating Curve= 0 ,0
Exp/Cntr=0.3,0.1

Type RM Length L Ch R = 1 ,33839   ,574,574,574
BEGIN DESCRIPTION:
DENTON CREEK 2 30.0
END DESCRIPTION:
XS GIS Cut Line= 3
        2492225.     13752925.01        2491125.       13751375.
      2490125.03     13750225.03
#Sta/Elev= 30
  3099.4  322.82  3239.8  319.51    3363  312.26  3374.8   311.8  3486.2  307.87
  3558.3  306.68  3831.4  293.95  3977.7  289.14  4192.8  279.63  4225.3  278.84
  4348.5   276.7  4356.4  276.51  4471.7  275.75  4500.6  275.67  4666.2  274.03
  4835.2  271.56  4977.9  272.65  4979.5  266.32  4980.2  265.82  5014.5  266.32
  5021.4  271.65  5049.9  274.49    5255  271.66  5590.9  274.18  5921.6  279.32
  6091.4  286.53  6110.7  287.27  6317.4  302.48  6432.6  313.24    6524  319.16
#Mann= 20 ,-1 , 0
  3099.4     .07       0  3239.8    .035       0    3363     .05       0
  3374.8     .07       0  3486.2     .05       0  3977.7     .07       0
  4192.8     .05       0  4225.3     .07       0  4348.5     .05       0
  4356.4     .07       0  4471.7     .05       0  4500.6     .07       0
  4666.2      .1       0  4979.5     .05       0  5014.5      .1       0
  5590.9     .05       0  6091.4     .07       0  6110.7     .05       0
  6317.4     .07       0  6432.6     .05       0
Bank Sta=4979.5,5014.5
XS Rating Curve= 0 ,0
Exp/Cntr=0.3,0.1

Type RM Length L Ch R = 1 ,33265   ,572,572,572
BEGIN DESCRIPTION:
DENTON CREEK 2 29.0
END DESCRIPTION:
XS GIS Cut Line= 3
      2492625.01     13752475.01        2491375.       13750925.
      2490625.02     13750125.02
#Sta/Elev= 30
  3008.1  317.86  3064.9  315.25  3122.5  317.24  3192.8  311.92  3413.6  306.45
    3450  303.62  3634.3  299.41  3722.9  290.17  3795.7  283.47    3855  279.05
  3984.6   276.9  4298.2  271.83  4373.2  269.13  4494.7  274.65  4686.7  272.43
  4921.8   274.4  4985.7  272.48  4992.2  270.17  4995.5  265.85  4996.3  265.35
    5031  265.85  5065.7  271.74  5147.3  275.58  5324.9  282.19  5424.6  282.09
  5664.4  276.83  5841.2  288.52  5926.2   298.7  6019.6  306.19  6095.9  308.41
#Mann= 12 ,-1 , 0
  3008.1     .07       0    3450     .05       0  3722.9     .07       0
  3795.7     .05       0  3984.6     .07       0  4298.2      .1       0
  4995.5     .05       0    5031      .1       0  5065.7     .12       0
  5147.3     .07       0  5424.6     .12       0  6019.6     .07       0
Bank Sta=4995.5,5031
XS Rating Curve= 0 ,0
Exp/Cntr=0.3,0.1

Type RM Length L Ch R = 1 ,32693   ,535,535,535
BEGIN DESCRIPTION:
DENTON CREEK 2 28.0
END DESCRIPTION:
XS GIS Cut Line= 3
        2492425.       13752125.        2491775.       13751025.
      2491224.98     13750024.97
#Sta/Elev= 30
  3722.2  310.32  3942.7  303.33  4012.8   290.8    4214  277.62  4270.5  276.16
  4441.7  273.21  4612.9  273.41  4623.7  273.23    4875  271.47  4890.7  266.07
  4896.5  269.91  4900.8  264.56  4901.6  264.06  4936.3  264.56  4992.1  266.25
  5007.9  270.88  5013.6  267.06  5029.7  271.07  5035.4  264.64  5051.5  271.27
  5057.2  265.64  5073.3   265.1  5095.1   266.2  5111.2  272.29  5116.9  267.35
    5133  272.83  5272.7   274.8  5800.1  281.42  6023.4  289.07  6141.2  290.64
#Mann= 11 ,-1 , 0
  3722.2     .07       0    4214     .05       0  4270.5     .07       0
  4441.7      .1       0  4612.9     .07       0  4623.7      .1       0
  4900.8     .05       0  4936.3      .1       0  5272.7     .05       0
  5800.1    .035       0  6023.4     .12       0
Bank Sta=4900.8,4936.3
XS Rating Curve= 0 ,0
Exp/Cntr=0.3,0.1

Type RM Length L Ch R = 1 ,32158   ,562,562,562
BEGIN DESCRIPTION:
DENTON CREEK 2 27.0
END DESCRIPTION:
XS GIS Cut Line= 3
      2492575.01     13751925.02        2492175.       13751125.
      2491175.02     13749525.04
#Sta/Elev= 30
  4109.9  315.89    4163   314.9    4191  312.96  4221.7  299.16  4258.1   293.8
  4333.5  289.74  4453.7  280.77  4516.3  279.07  4654.8  274.84  4724.6  273.58
  4766.5  273.69    4859  274.39  4951.2  272.19  4955.8  264.69  4956.6  264.19
  4991.4  264.69  5001.6   270.8    5012  272.02  5200.7  270.33  5358.7  272.61
  5410.6   271.9  5461.6  273.56  5560.9  274.66  5830.4  275.43  5944.4  278.51
  6086.3  282.37  6170.7  282.95    6354  286.07  6690.8  288.22  6891.1  293.86
#Mann= 13 ,-1 , 0
  4109.9     .07       0  4516.3     .05       0  4654.8     .12       0
  4724.6     .05       0  4766.5     .12       0    4859      .1       0
  4955.8     .05       0  4991.4      .1       0  5461.6     .07       0
  5560.9     .05       0  5944.4    .035       0  6170.7     .07       0
  6690.8     .12       0
Bank Sta=4955.8,4991.4
XS Rating Curve= 0 ,0
Exp/Cntr=0.3,0.1

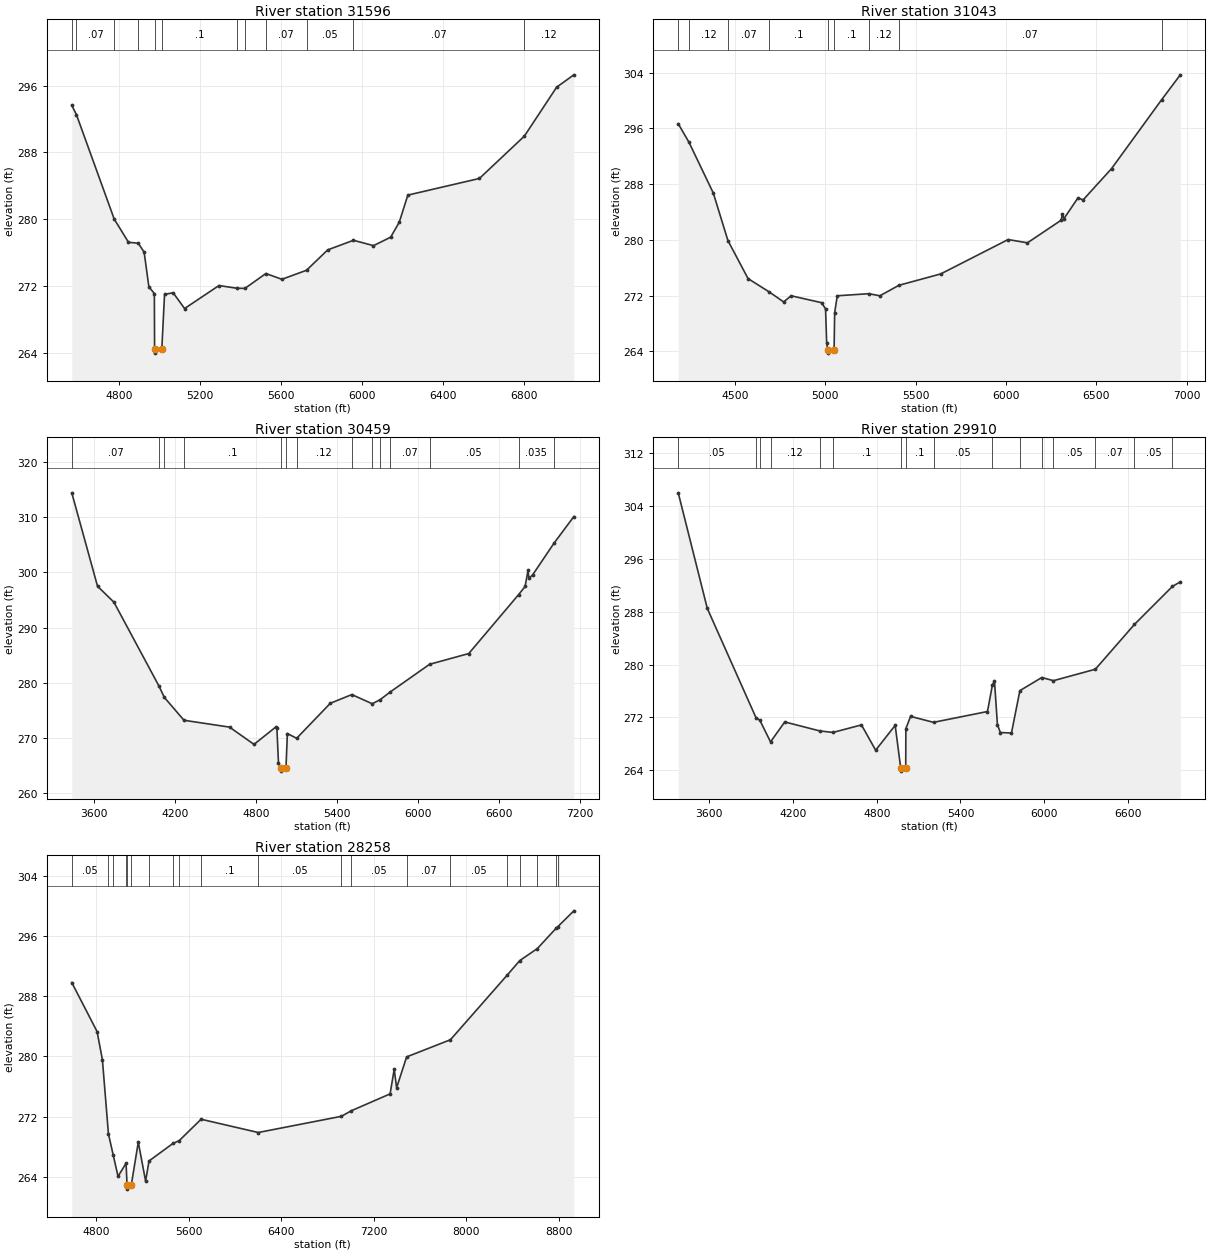
Type RM Length L Ch R = 1 ,31596   ,553,553,553
BEGIN DESCRIPTION:
DENTON CREEK 2 26.0
END DESCRIPTION:
XS GIS Cut Line= 3
      2492974.98     13751074.99        2492625.       13750825.
        2491175.       13749375.
#Sta/Elev= 30
  4565.1  293.64  4588.2  292.52  4774.8  280.02  4845.3  277.24  4893.4  277.13
  4922.7  276.06    4946  271.92  4973.1   271.1  4974.3  264.47  4975.1  263.97
    5010  264.47  5023.5     271  5065.9   271.2  5122.5  269.31  5292.2  272.06
  5380.9  271.74  5420.6  271.72  5524.2   273.5  5603.3  272.81  5724.9  273.89
  5829.6  276.33  5956.9  277.48  6055.9  276.84  6140.7  277.85  6183.1  279.64
  6225.6  282.89  6579.1  284.88  6801.3  289.95  6960.9  295.81  7045.8  297.29
#Mann= 12 ,-1 , 0
  4565.1     .12       0  4588.2     .07       0  4774.8     .12       0
  4893.4      .1       0  4974.3     .05       0    5010      .1       0
  5380.9     .07       0  5420.6     .12       0  5524.2     .07       0
  5724.9     .05       0  5956.9     .07       0  6801.3     .12       0
Bank Sta=4974.3,5010
XS Rating Curve= 0 ,0
Exp/Cntr=0.3,0.1

Type RM Length L Ch R = 1 ,31043   ,584,584,584
BEGIN DESCRIPTION:
DENTON CREEK 2 25.0
END DESCRIPTION:
XS GIS Cut Line= 3
      2493075.01     13751075.01        2492775.       13750325.
        2491625.       13748725.
#Sta/Elev= 30
  4186.6  296.68    4246  294.02  4380.5  286.73  4461.6  279.89    4573  274.43
    4691   272.5  4769.6  271.08  4811.3  271.96  4979.6  270.97  5001.8  270.08
  5007.9  265.21  5013.3  264.22  5014.1  263.72  5049.1  264.22  5052.1  269.53
  5066.8  271.96  5241.3  272.26  5302.3  271.96  5408.1  273.47  5638.9   275.1
  6012.1  280.04  6118.9  279.57  6305.5  282.82  6312.1  283.74  6320.3  283.02
  6398.3  286.02  6427.1  285.74  6584.2  290.23    6861  300.12  6964.8  303.71
#Mann= 9 ,-1 , 0
  4186.6     .07       0    4246     .12       0  4461.6     .07       0
    4691      .1       0  5013.3     .05       0  5049.1      .1       0
  5241.3     .12       0  5408.1     .07       0    6861    .035       0
Bank Sta=5013.3,5049.1
XS Rating Curve= 0 ,0
Exp/Cntr=0.3,0.1

Type RM Length L Ch R = 1 ,30459   ,549,549,549
BEGIN DESCRIPTION:
DENTON CREEK 2 24.0
END DESCRIPTION:
XS GIS Cut Line= 3
        2493375.     13751475.03        2493175.       13749925.
      2491574.97     13748474.97
#Sta/Elev= 30
  3432.4  314.43  3623.4  297.49    3745   294.6  4080.3  279.33  4118.2  277.35
  4264.4  273.19    4602  271.95  4783.5  268.82  4944.9  271.97  4953.1  271.74
    4965   265.4  4984.5  264.47  4985.3  263.97  5020.3  264.47  5030.8  270.79
  5099.5  269.92  5349.1  276.27  5508.5  277.85  5659.8  276.19  5717.6  276.91
  5792.5  278.31  6085.1  283.34  6375.7  285.29  6744.6  295.96  6793.3  297.45
    6815  300.39  6821.7   298.9  6850.1  299.59    7007  305.28  7154.6  310.13
#Mann= 14 ,-1 , 0
  3432.4     .07       0  4080.3     .12       0  4118.2     .07       0
  4264.4      .1       0  4984.5     .05       0  5020.3      .1       0
  5099.5     .12       0  5508.5     .05       0  5659.8     .07       0
  5717.6     .05       0  5792.5     .07       0  6085.1     .05       0
  6744.6    .035       0    7007     .05       0
Bank Sta=4984.5,5020.3
XS Rating Curve= 0 ,0
Exp/Cntr=0.3,0.1

Type RM Length L Ch R = 1 ,29910   ,1652,1652,1652
BEGIN DESCRIPTION:
DENTON CREEK 2 23.0
END DESCRIPTION:
XS GIS Cut Line= 3
      2494074.99     13751224.98        2493575.       13749675.
      2492425.02     13748075.03
#Sta/Elev= 30
  3376.7  306.02    3585  288.51    3934  271.97  3961.3  271.59  4038.3   268.3
  4140.3  271.32  4390.7  269.96  4485.8  269.73  4690.1  270.87  4791.8  267.04
  4931.8   270.8  4971.3  264.37  4972.1  263.87  5007.4  264.37  5008.4   270.3
  5042.1  272.16  5206.5  271.26  5593.4   272.9  5629.1  276.95  5643.7  277.51
  5664.6  270.93  5685.5  269.72  5765.3  269.64  5825.7  276.06  5982.8  278.05
  6066.4  277.57  6366.6   279.3  6646.9  286.09  6919.4  291.85  6975.7  292.54
#Mann= 16 ,-1 , 0
  3376.7     .05       0    3934     .07       0  3961.3     .05       0
  4038.3     .12       0  4390.7     .07       0  4485.8      .1       0
  4971.3     .05       0  5007.4      .1       0  5206.5     .05       0
  5629.1     .07       0  5825.7     .05       0  5982.8    .035       0
  6066.4     .05       0  6366.6     .07       0  6646.9     .05       0
  6919.4    .035       0
Bank Sta=4971.3,5007.4
XS Rating Curve= 0 ,0
Exp/Cntr=0.3,0.1

Type RM Length L Ch R = 1 ,28258   ,1221,1221,1221
BEGIN DESCRIPTION:
DENTON CREEK 2 22.0
END DESCRIPTION:
XS GIS Cut Line= 3
        2494425.       13751025.        2494625.       13750675.
      2492325.01     13747475.02
#Sta/Elev= 30
  4587.1  289.81  4805.9   283.3    4852  279.58  4904.5  269.69  4944.8  266.96
  4987.3  264.06  5056.9  265.81  5065.4  262.87  5066.3  262.37  5101.6  262.87
  5162.6  268.61  5225.9  263.44  5255.6  266.11  5461.8  268.43  5516.3  268.81
  5706.1  271.65  6200.6  269.89  6919.8  272.04  7004.6  272.77  7341.2  275.02
  7376.8  278.28  7397.7  275.84  7484.3  279.93  7863.3  282.21  8354.3  290.79
  8463.7  292.73  8615.3  294.32  8776.1  296.99  8789.9  297.19    8931  299.33
#Mann= 20 ,-1 , 0
  4587.1     .05       0  4904.5     .12       0  4944.8      .1       0
  5056.9     .12       0  5065.4     .05       0  5101.6      .1       0
  5255.6     .12       0  5461.8     .07       0  5516.3     .12       0
  5706.1      .1       0  6200.6     .05       0  6919.8     .07       0
  7004.6     .05       0  7484.3     .07       0  7863.3     .05       0
  8354.3     .07       0  8463.7     .05       0  8615.3     .07       0
  8776.1    .035       0  8789.9     .07       0
Bank Sta=5065.4,5101.6
XS Rating Curve= 0 ,0
Exp/Cntr=0.3,0.1