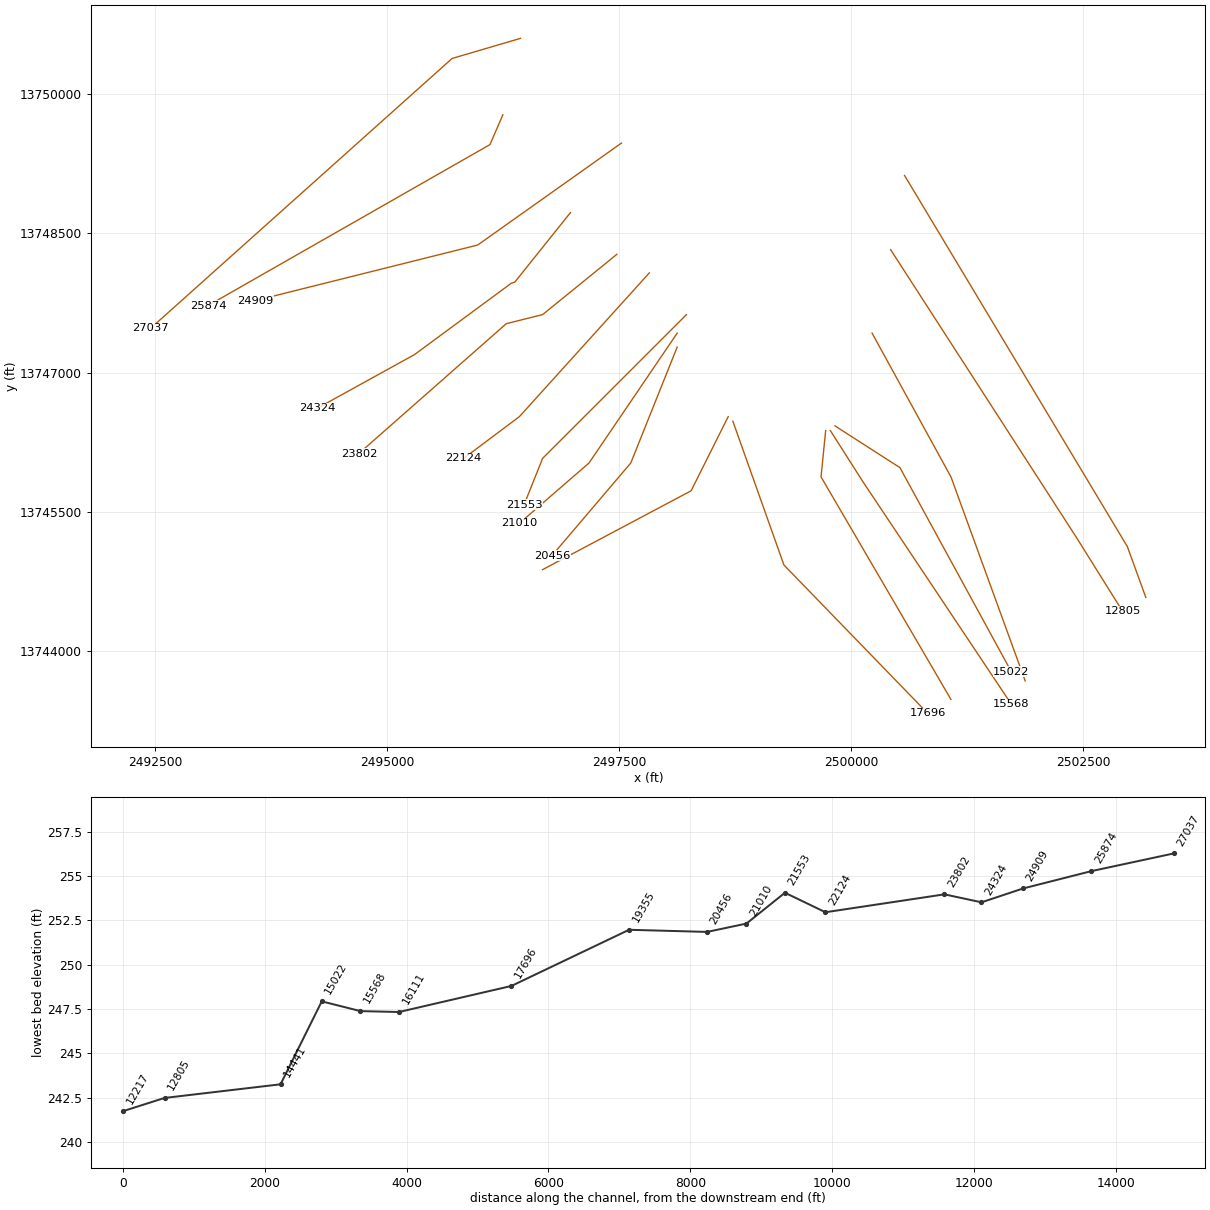
HEC-RAS study DENTON CREEK 2.prj: DENTON CREEK 2 Base Level Engineering

--- DENTON CREEK 2.g01 (geometry) --- (continued)

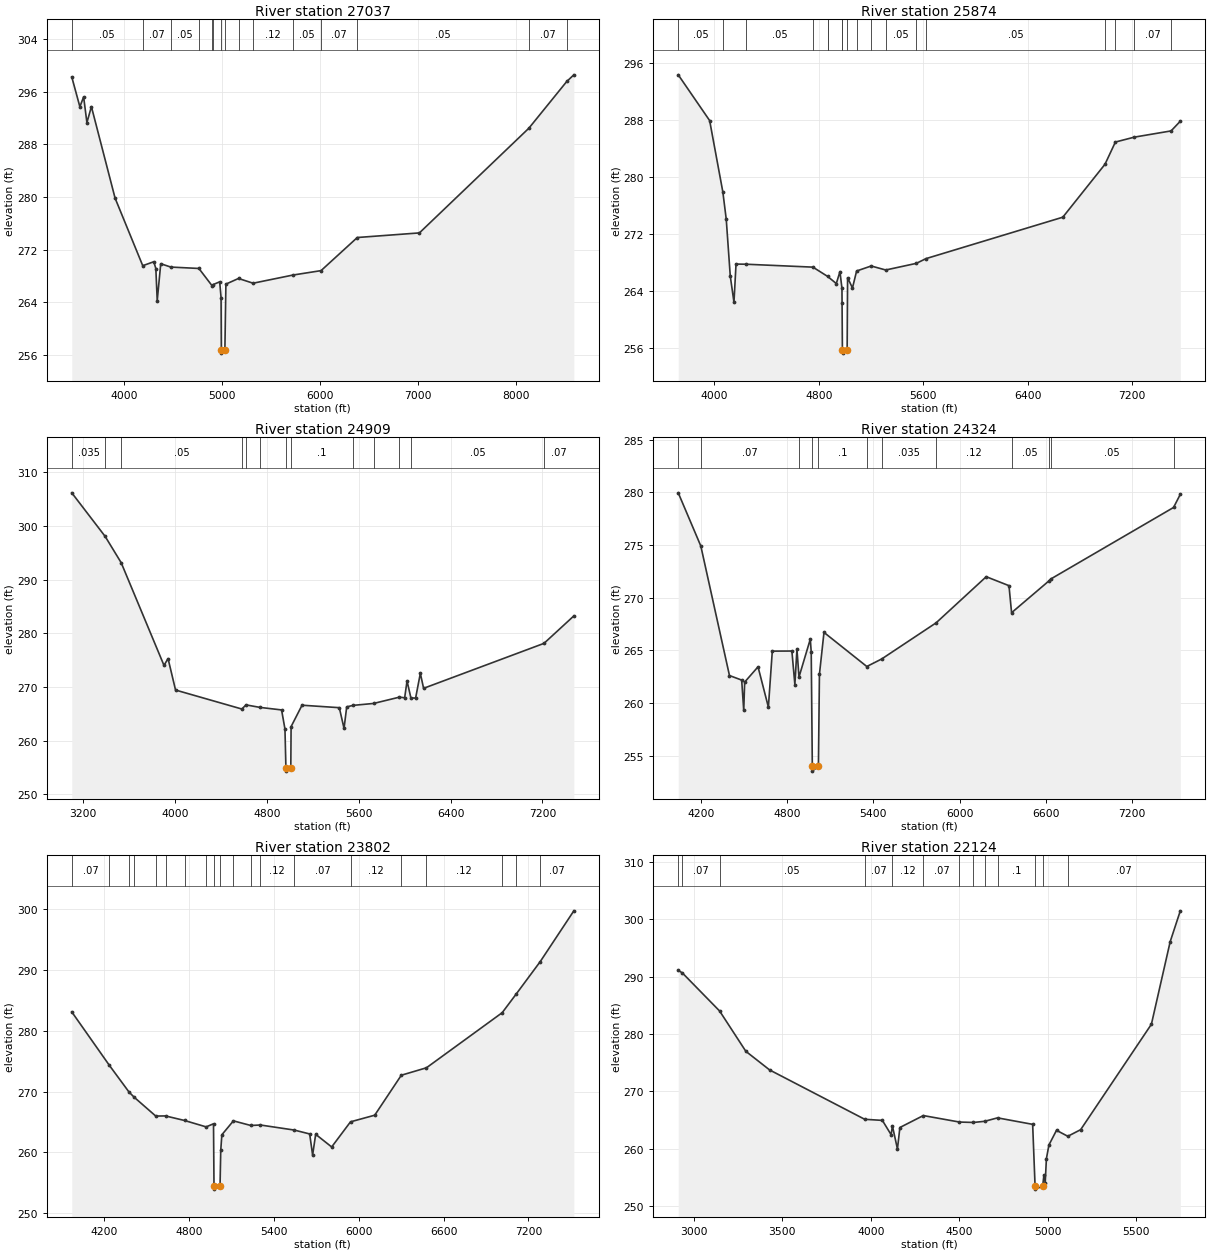
Type RM Length L Ch R = 1 ,27037   ,1163,1163,1163
BEGIN DESCRIPTION:
DEN2
END DESCRIPTION:
XS GIS Cut Line= 3
      2496437.32     13750603.92       2495699.5     13750386.91
       2492453.6     13747479.49
#Sta/Elev= 30
  3461.6  298.23  3544.3   293.7  3582.8   295.2  3616.2  291.29  3662.1  293.72
  3903.9  279.82  4186.3  269.56  4299.1  270.16    4320  269.13  4334.2  264.26
  4370.1  269.86  4472.9  269.35  4759.6  269.14  4894.6  266.51  4906.3   266.7
  4971.9  267.11  4986.1  264.71  4988.9  256.78  4989.8  256.28  5025.1  256.78
  5035.4  266.76  5164.1  267.62  5313.1   266.9  5720.4  268.14  6006.9  268.81
  6377.1  273.84  7011.4  274.54    8129  290.44  8515.9  297.54  8588.3  298.55
#Mann= 15 ,-1 , 0
  3461.6     .05       0  4186.3     .07       0  4472.9     .05       0
  4759.6     .07       0  4894.6    .035       0  4906.3      .1       0
  4988.9     .05       0  5025.1      .1       0  5164.1    .035       0
  5313.1     .12       0  5720.4     .05       0  6006.9     .07       0
  6377.1     .05       0    8129     .07       0  8515.9    .035       0
Bank Sta=4988.9,5025.1
XS Rating Curve= 0 ,0
Exp/Cntr=0.3,0.1

Type RM Length L Ch R = 1 ,25874   ,965,965,965
BEGIN DESCRIPTION:
DEN1
END DESCRIPTION:
XS GIS Cut Line= 3
      2496246.36     13749779.25      2496107.48     13749458.09
      2493069.67      13747722.2
#Sta/Elev= 30
  3722.2  294.28    3963  287.87  4064.1  277.87  4090.3  274.03    4121  266.09
  4149.4  262.41  4165.2  267.76  4240.8  267.74  4754.8  267.33  4866.4  266.04
    4934  265.03  4961.8   266.7  4977.2  264.36    4978  262.34  4980.6  255.78
  4981.5  255.28    5017  255.78  5020.4  265.85  5057.8  264.41  5089.6  266.79
  5201.2  267.49  5312.8  266.93  5547.4  267.86  5620.8  268.52  6670.2  274.33
  6993.6  281.75  7073.2  284.86  7218.9  285.55  7500.1  286.42  7570.9  287.78
#Mann= 18 ,-1 , 0
  3722.2     .05       0  4064.1     .07       0  4240.8     .05       0
  4754.8    .035       0  4866.4     .07       0  4866.4     .12       0
    4978      .1       0  4980.6     .05       0    5017      .1       0
  5089.6     .12       0  5201.2    .035       0  5312.8     .05       0
  5547.4     .07       0  5620.8     .05       0  6993.6     .07       0
  7073.2     .05       0  7218.9     .07       0  7500.1     .05       0
Bank Sta=4980.6,5017
XS Rating Curve= 0 ,0
Exp/Cntr=0.3,0.1

Type RM Length L Ch R = 1 ,24909   ,585,585,585
BEGIN DESCRIPTION:
DENTON CREEK 2 21.0
END DESCRIPTION:
XS GIS Cut Line= 3
      2497525.03     13749475.02        2495975.       13748375.
      2493574.96     13747774.99
#Sta/Elev= 30
  3099.3  306.19    3390  298.07  3529.6  293.17  3902.7  274.02  3938.3  275.28
  4003.5  269.42    4581  265.88  4617.5  266.65  4740.1  266.18  4927.4  265.71
  4956.8  262.16  4965.3   254.8  4966.3   254.3  5007.7   254.8  5010.3   262.6
  5105.6  266.59  5430.3  266.13  5471.6  262.27  5494.8  266.28  5550.3  266.56
  5729.3  266.92  5953.4  268.09  5999.8  267.98  6020.5  271.11  6054.2  267.95
  6095.2  267.92  6136.4  272.53  6164.8  269.74  7213.6  278.12  7473.9  283.24
#Mann= 13 ,-1 , 0
  3099.3    .035       0    3390     .07       0  3529.6     .05       0
    4581     .12       0  4617.5     .05       0  4740.1      .1       0
  4965.3     .05       0  5007.7      .1       0  5550.3     .12       0
  5729.3     .05       0  5953.4    .035       0  6054.2     .05       0
  7213.6     .07       0
Bank Sta=4965.3,5007.7
XS Rating Curve= 0 ,0
Exp/Cntr=0.3,0.1

Type RM Length L Ch R = 1 ,24324   ,522,522,522
BEGIN DESCRIPTION:
DENTON CREEK 2 20.0
END DESCRIPTION:
XS GIS Cut Line= 6
      2496975.69     13748724.43      2496955.11     13748700.13
        2496375.       13747975.      2496335.88     13747961.96
       2495294.2     13747193.59      2494248.92     13746616.13
#Sta/Elev= 30
  4044.1  279.96    4201  274.91  4400.3   262.6  4485.1  262.17  4499.5  259.28
  4505.9  261.98  4598.8  263.43  4670.8   259.6    4698  264.92  4834.1  264.93
  4854.9  261.75  4869.3   265.1  4883.6  262.46  4962.2  266.06  4968.6  264.83
  4976.2  254.02  4977.2  253.52  5018.6  254.02  5025.7  262.72  5057.3   266.7
    5355  263.46  5457.8  264.17  5836.9  267.61  6185.2  271.99  6343.3  271.14
  6361.4  268.57  6620.1  271.58  6633.5  271.77  7487.6  278.57  7534.4  279.82
#Mann= 12 ,-1 , 0
  4044.1    .035       0    4201     .07       0  4883.6      .1       0
  4976.2     .05       0  5018.6      .1       0    5355    .063       0
  5457.8    .035       0  5836.9     .12       0  6361.4     .05       0
  6620.1    .035       0  6633.5     .05       0  7487.6     .07       0
Bank Sta=4976.2,5018.6
XS Rating Curve= 0 ,0
Exp/Cntr=0.3,0.1

Type RM Length L Ch R = 1 ,23802   ,1678,1678,1678
BEGIN DESCRIPTION:
DENTON CREEK 2 19.0
END DESCRIPTION:
XS GIS Cut Line= 4
      2497474.97     13748274.97        2496675.       13747625.
      2496283.55     13747527.14      2494694.76     13746127.19
#Sta/Elev= 30
  3969.3   283.1  4235.4  274.31  4374.5  269.92  4411.9  269.05  4563.4  265.98
  4632.7     266  4767.3  265.25  4919.9   264.2    4972  264.71  4975.5  254.47
  4976.5  253.97  5018.2  254.47  5023.2  260.32    5031   262.9  5112.7  265.19
  5235.9  264.43  5303.4  264.51  5542.6  263.68  5652.3  263.04  5673.1  259.57
  5694.8  262.98  5807.9   260.9  5941.1  265.03  6112.4  266.12  6300.6  272.69
  6478.2  273.91  7014.3  282.97  7112.8  286.02  7283.8  291.38  7521.1  299.71
#Mann= 20 ,-1 , 0
  3969.3     .07       0  4235.4     .05       0  4374.5     .07       0
  4411.9     .05       0  4563.4     .07       0  4632.7     .05       0
  4767.3     .12       0  4919.9      .1       0  4975.5     .05       0
  5018.2      .1       0  5112.7     .12       0  5235.9      .1       0
  5303.4     .12       0  5542.6     .07       0  5941.1     .12       0
  6300.6     .07       0  6478.2     .12       0  7014.3     .07       0
  7112.8     .05       0  7283.8     .07       0
Bank Sta=4975.5,5018.2
XS Rating Curve= 0 ,0
Exp/Cntr=0.3,0.1

Type RM Length L Ch R = 1 ,22124   ,571,571,571
BEGIN DESCRIPTION:
DENTON CREEK 2 18.0
END DESCRIPTION:
XS GIS Cut Line= 3
      2497824.98     13748074.97        2496425.       13746525.
      2495825.02     13746075.01
#Sta/Elev= 30
  2911.4  291.09  2934.6  290.64  3145.4     284  3293.6  276.98  3428.1  273.73
  3965.7  265.13  4065.5  264.94  4114.9  262.45  4122.4  263.96  4150.7  259.96
  4164.6   263.7    4297  265.78  4501.4  264.65  4580.6  264.58  4643.8  264.78
  4716.7  265.38  4915.2  264.25  4928.9  253.46  4929.9  252.96  4971.7  253.46
  4978.7  255.36  4986.2   254.1  4992.9  258.27  5007.3  260.66    5050  263.21
  5113.9  262.17  5186.5  263.32  5586.5  281.69  5692.7  296.08    5750  301.46
#Mann= 13 ,-1 , 0
  2911.4    .035       0  2934.6     .07       0  3145.4     .05       0
  3965.7     .07       0  4122.4     .12       0    4297     .07       0
  4501.4     .12       0  4580.6     .07       0  4643.8     .12       0
  4716.7      .1       0  4928.9     .05       0  4971.7      .1       0
  5113.9     .07       0
Bank Sta=4928.9,4971.7
XS Rating Curve= 0 ,0
Exp/Cntr=0.3,0.1

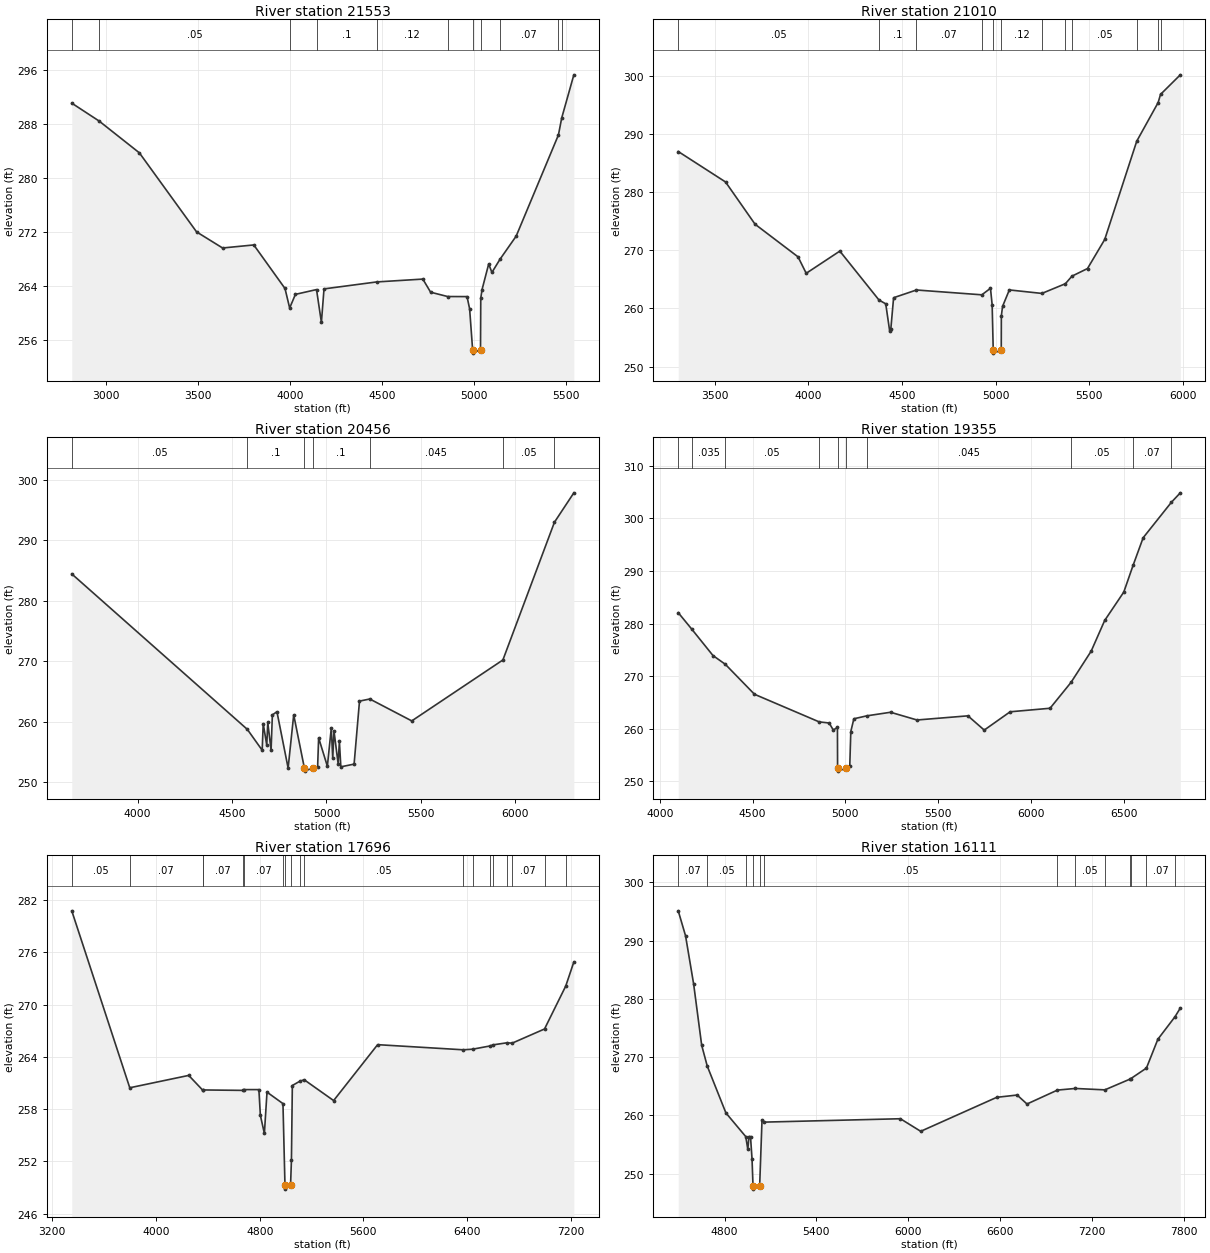
Type RM Length L Ch R = 1 ,21553   ,543,543,543
BEGIN DESCRIPTION:
DENTON CREEK 2 17.0
END DESCRIPTION:
XS GIS Cut Line= 3
      2498224.98     13747624.98        2496675.       13746075.
      2496475.01     13745575.02
#Sta/Elev= 30
    2813  291.03  2961.5  288.39  3180.7  283.68  3491.8  271.99  3633.2  269.61
  3802.9  270.06  3972.6  263.62    3998  260.73  4029.2  262.75  4144.1  263.46
  4170.6   258.6  4184.8  263.56  4471.4  264.59  4722.2  265.01  4764.6  263.07
  4857.2  262.43  4962.6  262.42  4976.7  260.61    4993  254.56    4994  254.06
  5035.9  254.56  5037.3  262.18  5044.1  263.44  5080.4  267.25  5097.9  265.99
  5141.8  267.94  5229.8  271.36  5459.7  286.33  5477.6  288.85  5543.5  295.22
#Mann= 11 ,-1 , 0
    2813    .035       0  2961.5     .05       0    3998     .12       0
  4144.1      .1       0  4471.4     .12       0  4857.2      .1       0
    4993     .05       0  5035.9      .1       0  5141.8     .07       0
  5459.7     .05       0  5477.6     .12       0
Bank Sta=4993,5035.9
XS Rating Curve= 0 ,0
Exp/Cntr=0.3,0.1

Type RM Length L Ch R = 1 ,21010   ,554,554,554
BEGIN DESCRIPTION:
DENTON CREEK 2 16.0
END DESCRIPTION:
XS GIS Cut Line= 3
      2498124.97     13747424.96        2497175.       13746025.
      2496425.01     13745375.01
#Sta/Elev= 30
  3303.7     287  3556.6  281.76  3714.5  274.49  3944.2  268.88  3987.9  266.05
  4167.6  269.87  4377.1  261.45  4413.1   260.8  4434.1  256.13  4440.1   256.4
  4455.1  261.85  4577.3  263.18  4926.8  262.35  4973.1  263.47    4982  260.65
  4987.8  252.82  4988.8  252.32  5030.7  252.82  5031.2  258.75  5037.8  260.37
  5073.9  263.19  5247.9  262.59  5373.6  264.26  5408.7  265.56  5491.8  266.87
  5583.9  271.87  5755.1  288.78  5869.5  295.42  5882.2  296.82    5988  300.19
#Mann= 12 ,-1 , 0
  3303.7     .05       0  4377.1      .1       0  4577.3     .07       0
  4926.8     .12       0  4987.8     .05       0  5030.7     .12       0
  5247.9     .05       0  5373.6     .07       0  5408.7     .05       0
  5755.1     .07       0  5869.5     .12       0  5882.2     .07       0
Bank Sta=4987.8,5030.7
XS Rating Curve= 0 ,0
Exp/Cntr=0.3,0.1

Type RM Length L Ch R = 1 ,20456   ,1101,1101,1101
BEGIN DESCRIPTION:
DENTON CREEK 2 15.0
END DESCRIPTION:
XS GIS Cut Line= 3
      2498125.01     13747275.03        2497625.       13746025.
      2496774.98     13745024.97
#Sta/Elev= 30
  3651.1  284.44  4580.8  258.75  4659.5   255.3  4664.9  259.69  4683.7  256.15
  4689.1   259.9  4706.6  255.32  4713.4  261.14  4737.6  261.67  4796.8  252.36
  4826.4  261.15    4883  252.35    4884  251.85  4926.1  252.35    4953  252.52
  4958.4  257.35  5004.6  252.66  5025.4  258.95  5033.1     254  5039.7  258.48
  5061.7  253.08  5068.3  256.75    5076  252.56  5146.2  253.01  5174.8  263.42
  5229.3  263.77  5451.6  260.15  5934.2  270.22  6207.1  292.98  6309.9  297.84
#Mann= 7 ,-1 , 0
  3651.1     .05       0  4580.8      .1       0    4883     .05       0
  4926.1      .1       0  5229.3    .045       0  5934.2     .05       0
  6207.1     .07       0
Bank Sta=4883,4926.1
XS Rating Curve= 0 ,0
Exp/Cntr=0.3,0.1

Type RM Length L Ch R = 1 ,19355   ,1659,1659,1659
BEGIN DESCRIPTION:
DENTON CREEK 2 14.0
END DESCRIPTION:
XS GIS Cut Line= 3
        2498675.       13746525.        2498275.       13745725.
        2496675.       13744875.
#Sta/Elev= 30
  4099.6  282.09  4172.7  278.95  4286.9  273.94  4353.3  272.28  4510.5  266.58
  4859.3  261.33    4913  261.12  4935.3  259.78  4957.7  260.28  4958.5  252.47
  4959.5  251.97  5001.6  252.47  5024.2     253  5029.8   259.5  5046.2  261.92
  5116.2  262.48    5244  263.16  5386.5  261.69    5661  262.48  5748.9  259.77
  5888.6  263.25  6103.7  263.92    6217  268.85  6325.4  274.78  6398.2  280.61
  6501.2  286.01  6551.1  291.07  6605.5  296.33  6757.9  303.08  6805.8  304.87
#Mann= 10 ,-1 , 0
  4099.6     .05       0  4172.7    .035       0  4353.3     .05       0
  4859.3     .07       0  4958.5     .05       0  5001.6     .07       0
  5116.2    .045       0    6217     .05       0  6551.1     .07       0
  6757.9     .12       0
Bank Sta=4958.5,5001.6
XS Rating Curve= 0 ,0
Exp/Cntr=0.3,0.1

Type RM Length L Ch R = 1 ,17696   ,1585,1585,1585
BEGIN DESCRIPTION:
DENTON CREEK 2 13.0
END DESCRIPTION:
XS GIS Cut Line= 3
      2498724.99     13746475.04        2499275.       13744925.
        2500825.       13743325.
#Sta/Elev= 30
  3350.5  280.76  3797.8  260.44  4252.5  261.86  4358.9  260.19  4360.1  260.19
  4669.1  260.14  4680.1  260.23  4793.6  260.23  4805.2  257.27  4836.1  255.19
  4856.3  259.94  4979.4  258.62  4994.8   249.3  4995.8   248.8  5038.1   249.3
  5044.7  252.13  5051.7   260.7  5108.2  261.18  5143.2  261.36  5370.1  258.97
  5709.5  265.39  6370.1   264.8  6442.3  264.87  6575.7  265.24  6600.8  265.37
  6709.1  265.61  6746.5  265.56  6996.7  267.19  7160.4  272.12  7222.9  274.89
#Mann= 19 ,-1 , 0
  3350.5     .05       0  3797.8     .07       0  4358.9    .035       0
  4360.1     .07       0  4669.1    .035       0  4680.1     .07       0
  4979.4      .1       0  4994.8     .05       0  5038.1      .1       0
  5108.2      .1       0  5143.2     .05       0  6370.1     .07       0
  6442.3     .05       0  6575.7     .07       0  6600.8     .05       0
  6709.1    .035       0  6746.5     .07       0  6996.7    .035       0
  7160.4     .07       0
Bank Sta=4994.8,5038.1
XS Rating Curve= 0 ,0
Exp/Cntr=0.3,0.1

Type RM Length L Ch R = 1 ,16111   ,543,543,543
BEGIN DESCRIPTION:
DENTON CREEK 2 12.0
END DESCRIPTION:
XS GIS Cut Line= 3
        2499725.     13746374.96        2499675.       13745875.
      2501074.98     13743475.03
#Sta/Elev= 30
    4497  295.13  4544.7  290.85  4597.5  282.59  4650.2  272.04  4686.5  268.47
  4808.5  260.42  4938.2  256.35  4951.7  254.16  4959.2  256.36  4969.3  256.34
  4979.3  252.49  4985.7  247.83  4986.7  247.33    5029  247.83  5044.5   259.2
  5059.7  258.84  5948.8  259.42  6081.5  257.26  6578.5   263.1  6711.6  263.49
  6776.1  261.95  6974.9  264.34  7091.1  264.62  7284.7  264.38  7452.2  266.26
  7453.4  266.29  7556.5  268.12  7631.2  273.07  7743.2  276.94  7777.9  278.43
#Mann= 13 ,-1 , 0
    4497     .07       0  4686.5     .05       0  4938.2      .1       0
  4985.7     .05       0    5029      .1       0  5059.7     .05       0
  6974.9     .07       0  7091.1     .05       0  7284.7    .035       0
  7452.2     .05       0  7453.4    .035       0  7556.5     .07       0
  7743.2     .12       0
Bank Sta=4985.7,5029
XS Rating Curve= 0 ,0
Exp/Cntr=0.3,0.1

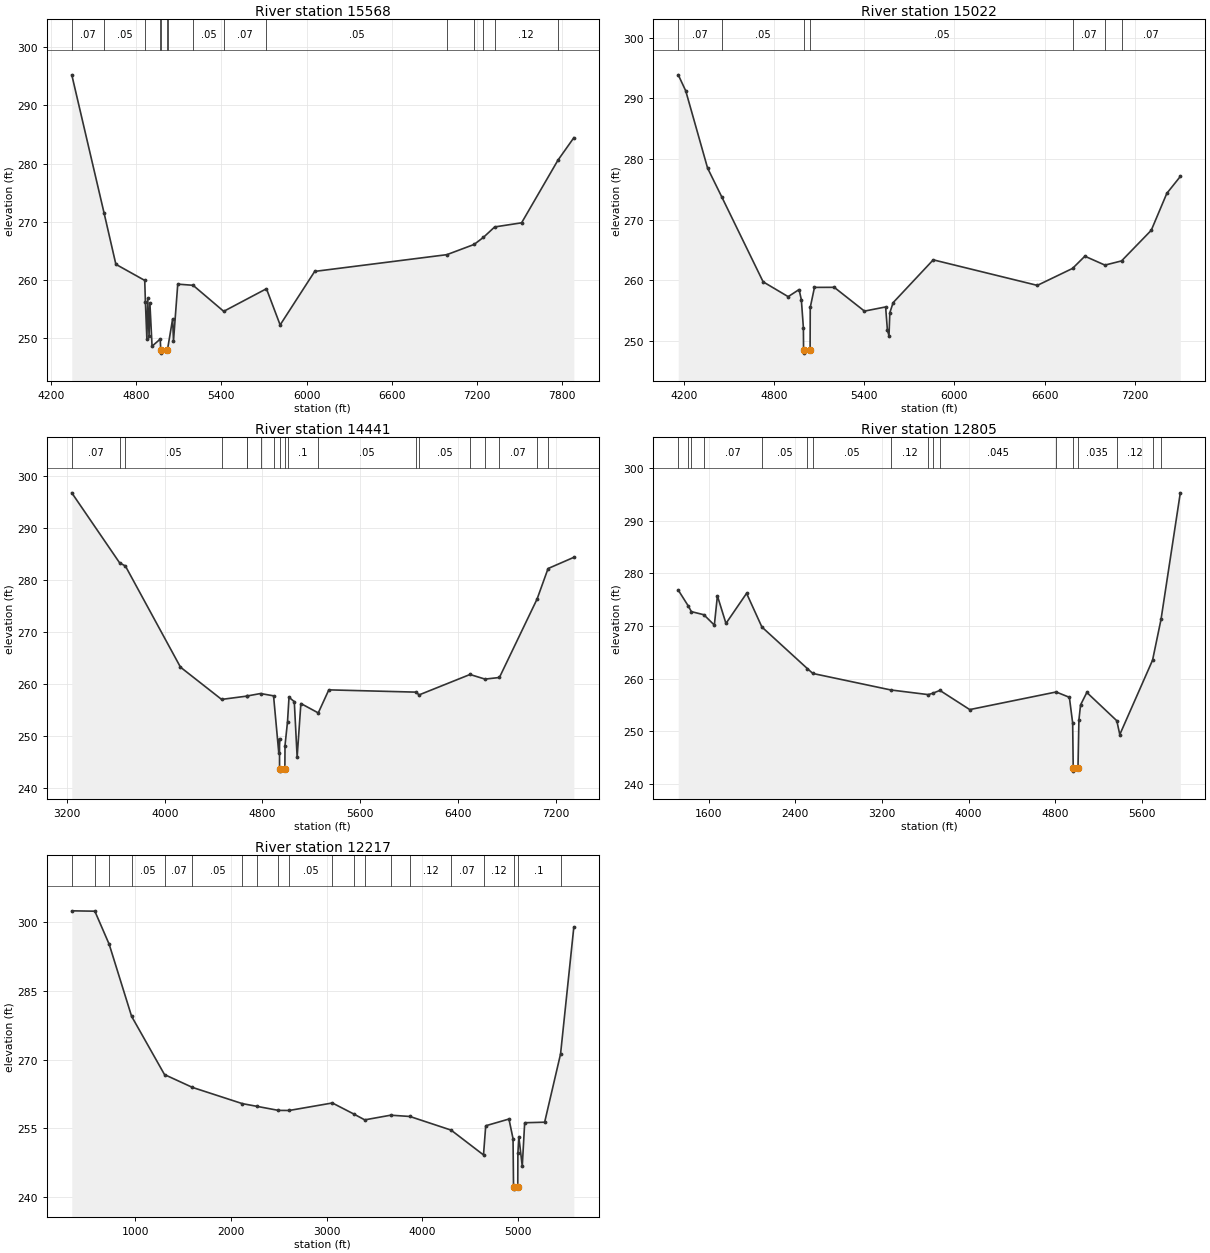
Type RM Length L Ch R = 1 ,15568   ,546,546,546
BEGIN DESCRIPTION:
DENTON CREEK 2 11.0
END DESCRIPTION:
XS GIS Cut Line= 3
      2499775.02     13746374.97        2500125.       13745825.
      2501724.99     13743425.02
#Sta/Elev= 30
  4346.7  295.26  4573.9  271.52  4657.4  262.66  4860.6  259.89  4865.3  256.19
  4875.8  249.74  4881.7  256.79  4891.1  250.37    4897  255.94  4912.2  248.57
  4969.4  249.79    4974  247.88    4975  247.38  5017.3  247.88  5021.4  248.06
  5057.2  253.27  5063.2   249.5  5093.2  259.25  5201.2  259.05  5416.9  254.57
  5717.9  258.46  5814.3  252.23  6057.7  261.44  6988.7  264.32  7180.5  266.08
  7245.8  267.29  7325.4  269.09    7515   269.8  7770.6  280.56    7883  284.44
#Mann= 15 ,-1 , 0
  4346.7     .07       0  4573.9     .05       0  4865.3     .12       0
  4969.4     .05       0    4974     .05       0  5017.3     .05       0
  5021.4     .12       0  5201.2     .05       0  5416.9     .07       0
  5717.9     .05       0  6988.7     .07       0  7180.5    .035       0
  7245.8     .07       0  7325.4     .12       0  7770.6     .07       0
Bank Sta=4974,5017.3
XS Rating Curve= 0 ,0
Exp/Cntr=0.3,0.1

Type RM Length L Ch R = 1 ,15022   ,581,581,581
BEGIN DESCRIPTION:
DENTON CREEK 2 10.0
END DESCRIPTION:
XS GIS Cut Line= 3
      2499824.98     13746425.01        2500525.       13745975.
      2501725.01     13743774.98
#Sta/Elev= 30
  4163.5   293.9  4213.4  291.25  4358.7  278.49  4453.2  273.72  4727.9  259.71
  4894.3  257.26    4967  258.43  4982.1  256.74  4995.7  252.09  4996.8  248.43
  4997.8  247.93  5040.2  248.43  5041.2  255.48  5069.3  258.79  5200.7   258.8
  5401.5  254.87  5542.4  255.56  5554.3   251.7  5564.8  250.81  5570.4  254.61
  5592.3  256.27    5859  263.34    6551  259.12  6785.1  261.92  6867.1  263.94
  7000.5  262.47  7110.9  263.16  7308.5  268.22    7412  274.32  7501.7  277.11
#Mann= 7 ,-1 , 0
  4163.5     .07       0  4453.2     .05       0  4996.8     .05       0
  5040.2     .05       0  6785.1     .07       0  7000.5    .035       0
  7110.9     .07       0
Bank Sta=4996.8,5040.2
XS Rating Curve= 0 ,0
Exp/Cntr=0.3,0.1

Type RM Length L Ch R = 1 ,14441   ,1636,1636,1636
BEGIN DESCRIPTION:
DENTON CREEK 2 9.0
END DESCRIPTION:
XS GIS Cut Line= 3
      2500224.99     13747425.02        2501075.       13745875.
      2501874.99     13743675.03
#Sta/Elev= 30
  3239.2  296.84    3631  283.35  3678.1  282.75  4128.8  263.27  4465.3  257.06
  4673.1   257.7  4674.6  257.72  4783.7  258.19  4890.5  257.75  4933.5   246.7
  4939.2  249.51  4939.7  243.75  4940.7  243.25  4983.1  243.75  4984.2  248.18
  5004.8  252.79    5017  257.47  5060.2  256.63  5083.5  245.95  5114.1  256.27
  5256.4  254.46  5342.8   258.9    6059  258.46  6080.5  257.92  6498.2  261.86
  6621.1  260.97  6738.8  261.28  7047.3   276.4  7136.9  282.26  7347.9  284.42
#Mann= 19 ,-1 , 0
  3239.2     .07       0    3631    .035       0  3678.1     .05       0
  4465.3     .07       0  4673.1     .05       0  4674.6     .07       0
  4783.7     .05       0  4890.5     .07       0  4939.7     .05       0
  4983.1     .07       0  5004.8      .1       0  5256.4     .05       0
    6059     .12       0  6080.5     .05       0  6498.2     .07       0
  6621.1    .035       0  6738.8     .07       0  7047.3     .12       0
  7136.9     .07       0
Bank Sta=4939.7,4983.1
XS Rating Curve= 0 ,0
Exp/Cntr=0.3,0.1

Type RM Length L Ch R = 1 ,12805   ,588,588,588
BEGIN DESCRIPTION:
DENTON CREEK 2 8.0
END DESCRIPTION:
XS GIS Cut Line= 3
      2500424.98     13748325.03        2502425.       13745225.
        2502925.       13744425.
#Sta/Elev= 30
  1320.3  276.82  1412.4  273.82  1441.6  272.73  1556.7  272.14  1653.5  270.17
  1681.7  275.73  1760.7  270.49  1950.9   276.2  2092.3  269.81  2512.1  261.92
  2562.7     261  3282.5  257.87  3627.7  256.99  3667.7  257.24  3734.5  257.79
    4010  254.15  4807.3  257.49  4929.3  256.48  4959.7   251.6  4964.8  242.98
  4965.8  242.48  5008.7  242.98  5017.2  252.16  5032.5  255.04  5090.3   257.4
  5366.8  252.04  5394.5  249.41  5696.8  263.52  5774.9  271.25  5952.9  295.26
#Mann= 17 ,-1 , 0
  1320.3     .07       0  1412.4     .05       0  1441.6    .035       0
  1556.7     .07       0  2092.3     .05       0  2512.1    .035       0
  2562.7     .05       0  3282.5     .12       0  3627.7     .12       0
  3667.7     .12       0  3734.5    .045       0  4807.3    .035       0
  4964.8     .05       0  5008.7    .035       0  5366.8     .12       0
  5696.8     .07       0  5774.9     .12       0
Bank Sta=4964.8,5008.7
XS Rating Curve= 0 ,0
Exp/Cntr=0.3,0.1

Type RM Length L Ch R = 1 ,12217   ,0,0,0
BEGIN DESCRIPTION:
DENTON CREEK 2 7.0
END DESCRIPTION:
XS GIS Cut Line= 3
      2500575.01     13749124.99        2502975.       13745125.
        2503175.     13744574.99
#Sta/Elev= 30
   335.3  302.52   576.6  302.44   726.4  295.22   960.9  279.48  1305.1  266.75
  1597.2  263.95  2118.1  260.41  2269.9  259.82  2495.7  258.93  2608.6  258.91
  3060.2  260.55  3285.9  258.12  3398.8  256.86  3670.2  257.88    3871   257.6
  4301.9  254.62  4640.6   249.2  4663.8  255.57  4906.8  257.04  4949.5  252.75
  4954.6  242.23  4955.6  241.73  4998.9  242.23  5000.1  249.52    5010  253.19
  5045.9  246.74  5071.2  256.23    5280  256.35  5446.4  271.26  5585.3  299.01
#Mann= 20 ,-1 , 0
   335.3     .05       0   576.6     .12       0   726.4     .07       0
   960.9     .05       0  1305.1     .07       0  1597.2     .05       0
  2118.1     .07       0  2269.9    .035       0  2495.7    .035       0
  2608.6     .05       0  3060.2    .035       0  3285.9     .12       0
  3398.8    .045       0  3670.2    .035       0    3871     .12       0
  4301.9     .07       0  4640.6     .12       0  4954.6     .05       0
  4998.9      .1       0  5446.4     .12       0
Bank Sta=4954.6,4998.9
XS Rating Curve= 0 ,0
Exp/Cntr=0.3,0.1

Chan Stop Cuts=-1
Use User Specified Reach Order=0
Composite Channel Slope=5