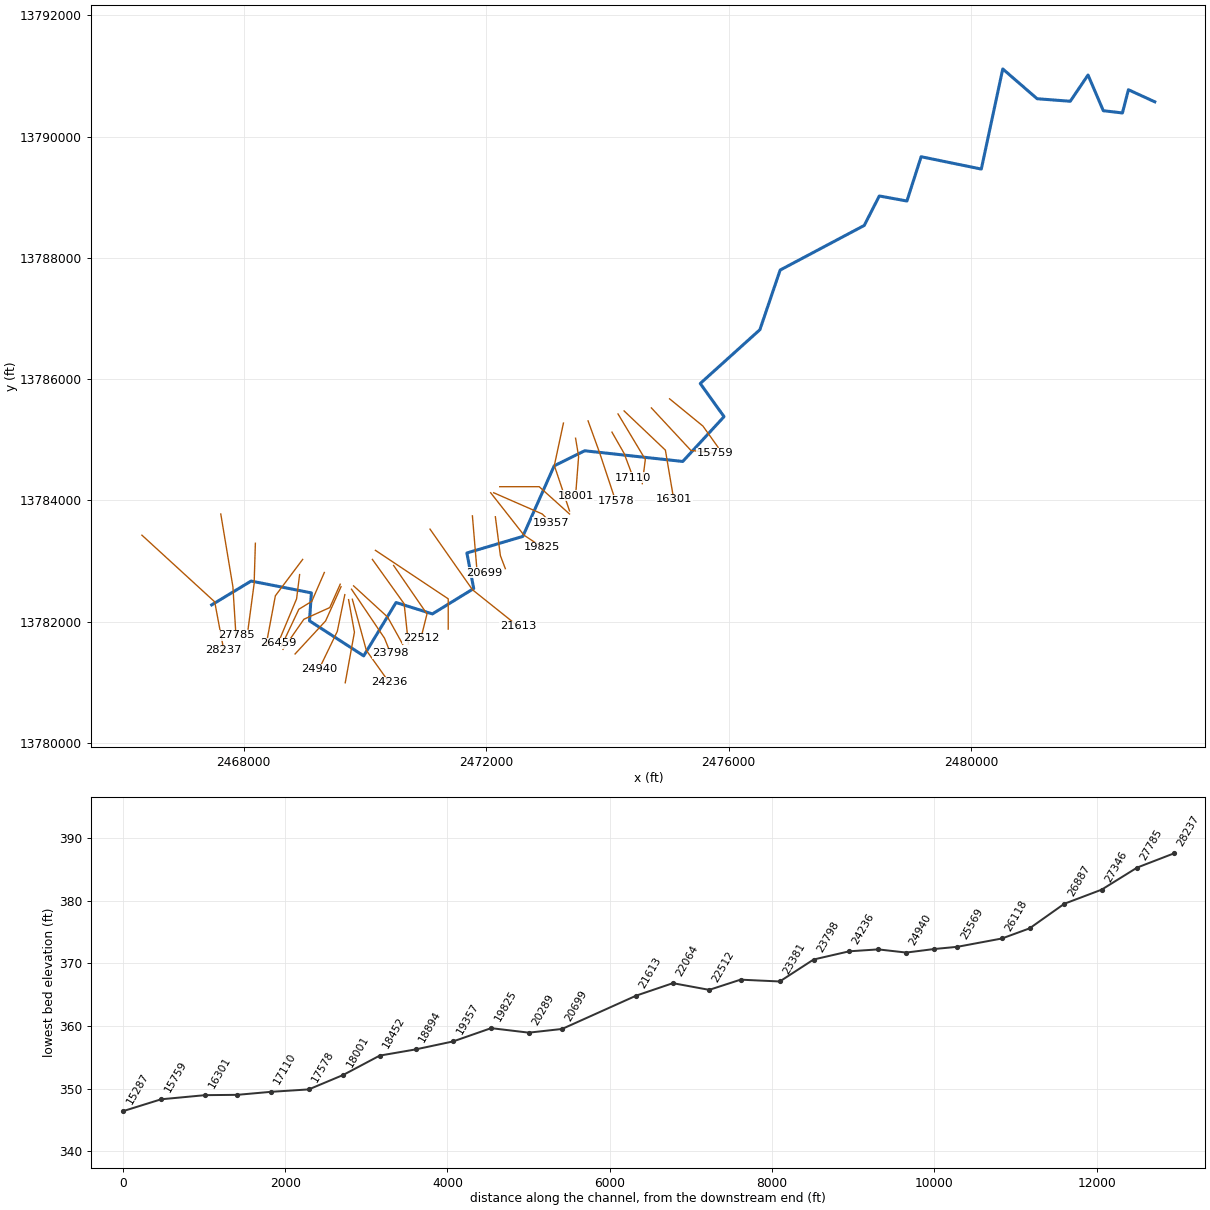
--- DRY RUN.prj (project) ---

Proj Title=DRY RUN Base Level Engineering
Current Plan=p01
Default Exp/Contr=0.3,0.1
English Units
Geom File=g01
Flow File=f01
Plan File=p01
Y Axis Title=Elevation
X Axis Title(PF)=Main Channel Distance
X Axis Title(XS)=Station
BEGIN DESCRIPTION:
DRY RUN
END DESCRIPTION:
DSS Export Rating Curves= 0
DSS Export Rating Curve Sorted= 0
DSS Export Volume Flow Curves= 0
DXF OffsetX= 0
DXF OffsetY= 0
DXF ScaleX= 1
DXF ScaleY= 10

--- DRY RUN.p01 (plan) ---

Plan Title=Multiple Run
Short Identifier=Multiple
Geom File=g01
Flow File=f01
Subcritical Flow
K Sum by GR= 0
Std Step Tol= 0.01
Critical Tol= 0.01
Num of Std Step Trials= 20
Max Error Tol= 0.3
Flow Tol Ratio= 0.001
Split Flow NTrial= 30
Split Flow Tol= 0.02
Split Flow Ratio= 0.02
Log Output Level= 0
Friction Slope Method= 1
Unsteady Friction Slope Method= 2
Unsteady Bridges Friction Slope Method= 1
Parabolic Critical Depth
Global Vel Dist=  1 , 1 , 1
Global Log Level= 0
CheckData=True
Encroach Param= -1, 0, 0, 0
BEGIN DESCRIPTION:
Multiple Run
END DESCRIPTION:

--- DRY RUN.f01 (steady flow) ---

Flow Title=Multiple
Number of Profiles=7
Profile Names=10-year,25-year,50-year,1pct_min,100-year,1pct_plu,500-year
River Rch & RM= DRY RUN,Reach-1,28237
     737    1186    1590    1032    2059    4108    3417
River Rch & RM= DRY RUN,Reach-1,24236
     938    1523    2054    1339    2672    5330    4476
River Rch & RM= DRY RUN,Reach-1,20289
    1248    2054    2796    1838    3667    7316    6248
River Rch & RM= DRY RUN,Reach-1,16696
    1444    2386    3254    2141    4273    8525    7301
River Rch & RM= DRY RUN,Reach-1,10356
    1688    2807    3847    2542    5071   10118    8735
Boundary for River Rch & Prof#=DRY RUN,Reach-1,1
Up Type=0
Dn Type=3
Dn Slope=0.005
Boundary for River Rch & Prof#=DRY RUN,Reach-1,2
Up Type=0
Dn Type=3
Dn Slope=0.005
Boundary for River Rch & Prof#=DRY RUN,Reach-1,3
Up Type=0
Dn Type=3
Dn Slope=0.005
Boundary for River Rch & Prof#=DRY RUN,Reach-1,4
Up Type=0
Dn Type=3
Dn Slope=0.005
Boundary for River Rch & Prof#=DRY RUN,Reach-1,5
Up Type=0
Dn Type=3
Dn Slope=0.005
Boundary for River Rch & Prof#=DRY RUN,Reach-1,6
Up Type=0
Dn Type=3
Dn Slope=0.005
Boundary for River Rch & Prof#=DRY RUN,Reach-1,7
Up Type=0
Dn Type=3
Dn Slope=0.005

--- DRY RUN.g01 (geometry) ---

Geom Title=Existing Conditions
Program Version=4.10

River Reach=DRY RUN         ,Reach-1
Reach XY= 30
        2467475.       13782275.      2468125.01     13782667.93
      2469118.89     13782473.21       2469088.2     13782011.27
      2469981.95     13781433.84      2470514.98     13782314.06
      2471114.57     13782126.05      2471795.51     13782544.73
       2471682.8     13783131.21      2472605.16     13783404.61
      2473122.57     13784569.48       2473624.7     13784817.74
      2475242.14     13784641.27      2475923.12     13785380.69
      2475530.39     13785927.44      2476513.92     13786814.95
      2476848.27     13787799.26       2478234.8     13788535.48
      2478483.09     13789021.65      2478938.24     13788938.35
      2479172.69     13789669.18       2480164.8     13789465.32
      2480518.55     13791117.36      2481085.33     13790625.87
      2481631.73     13790584.14      2481924.68     13791017.78
      2482176.22     13790428.44      2482491.74     13790391.28
      2482590.54     13790774.46        2483025.       13790575.

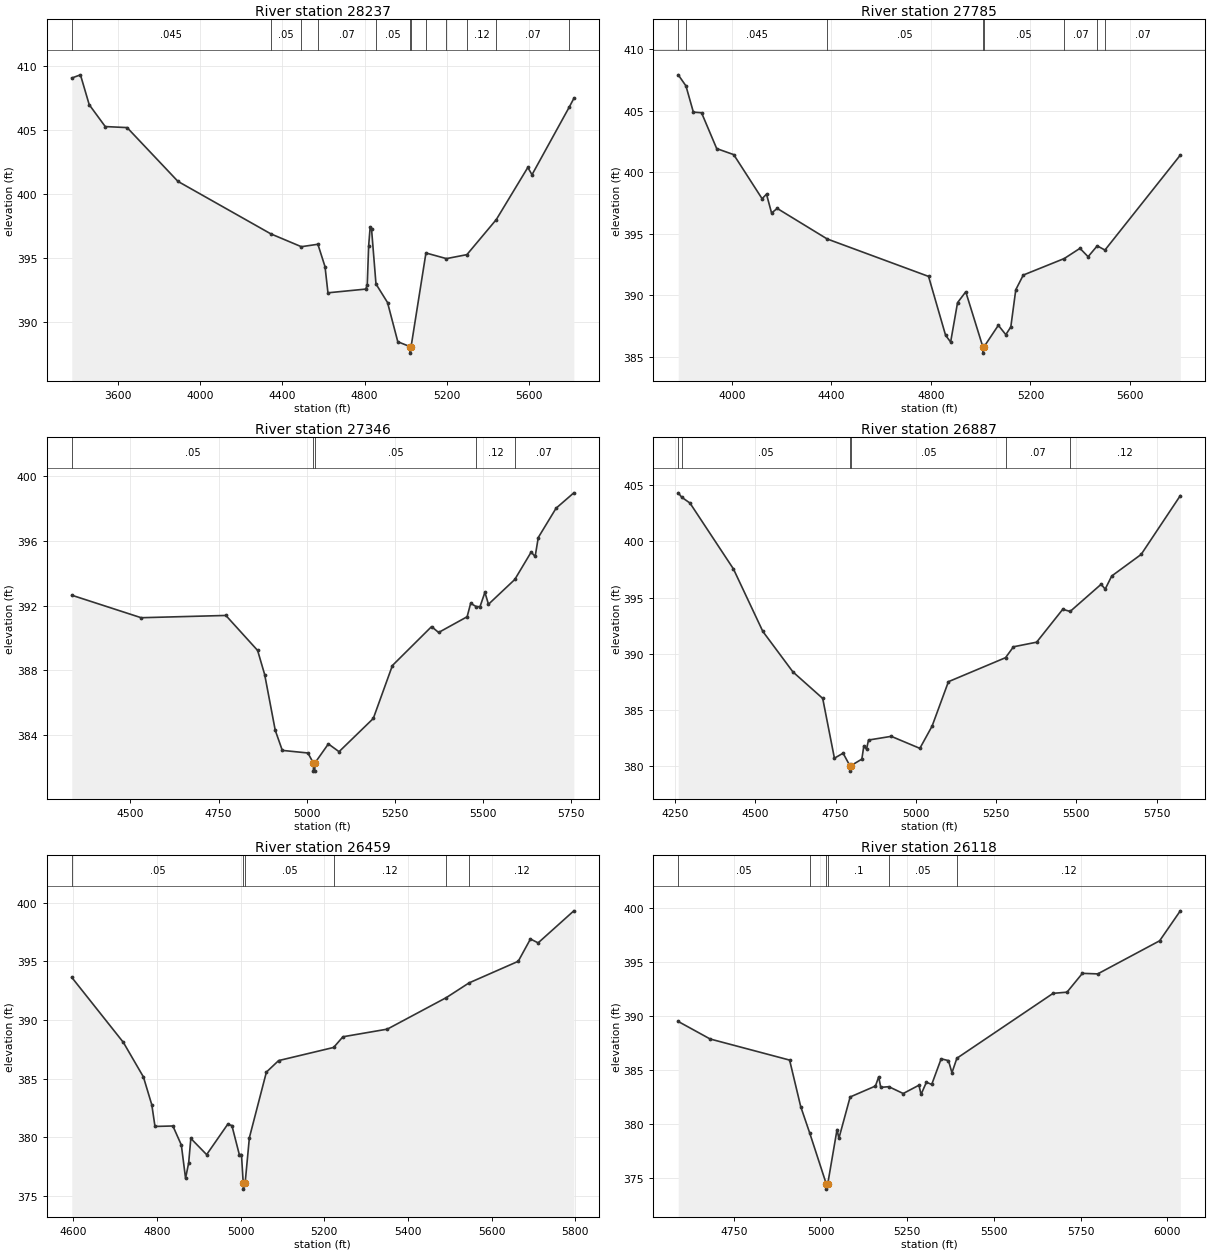
Type RM Length L Ch R = 1 ,28237   ,452,452,452
BEGIN DESCRIPTION:
DRY RUN 52.0
END DESCRIPTION:
XS GIS Cut Line= 3
      2466325.03     13783424.98        2467525.       13782325.
        2467675.     13781524.99
#Sta/Elev= 30
  3376.2  409.06  3418.4  409.31    3461  406.98    3539  405.27  3645.3  405.19
  3892.6  400.99  4344.6  396.89  4492.7  395.89  4573.2  396.08  4607.9  394.33
  4622.1  392.29  4805.8  392.58  4813.2  392.88    4820  395.94  4827.4  397.43
  4834.2  397.25  4855.7  392.98  4911.9  391.53  4961.8  388.47  5022.4  388.08
  5022.6  387.58  5026.4  388.08  5098.7   395.4  5198.3  394.96  5297.9  395.27
  5440.9  398.01  5594.2  402.08  5614.5  401.51  5795.9   406.8    5818  407.47
#Mann= 12 ,-1 , 0
  3376.2    .045       0  4344.6     .05       0  4492.7    .045       0
  4573.2     .07       0  4855.7     .05       0  5022.4     .05       0
  5026.4     .05       0  5098.7     .07       0  5198.3      .1       0
  5297.9     .12       0  5440.9     .07       0  5795.9     .12       0
Bank Sta=5022.4,5026.4
XS Rating Curve= 0 ,0
Exp/Cntr=0.3,0.1

Type RM Length L Ch R = 1 ,27785   ,439,439,439
BEGIN DESCRIPTION:
DRY RUN 51.0
END DESCRIPTION:
XS GIS Cut Line= 3
        2467625.     13783774.97        2467825.       13782575.
        2467875.     13781774.98
#Sta/Elev= 30
  3784.3  407.92  3815.3  407.02  3845.1  404.89    3878  404.84  3938.9  401.93
  4007.3  401.44  4121.4  397.86  4139.1  398.23  4159.4   396.7  4182.2  397.07
  4383.1  394.59  4790.5  391.55  4858.9  386.77  4879.2  386.22    4907  389.42
    4940   390.3  5008.8  385.82  5009.1  385.32  5012.9  385.82    5071  387.58
    5101  386.82  5121.1  387.45  5141.1  390.47  5171.2  391.66  5335.8     393
  5399.1  393.83  5431.7  393.15  5468.5  394.03  5499.5  393.69  5802.4   401.4
#Mann= 8 ,-1 , 0
  3784.3    .035       0  3815.3    .045       0  4383.1     .05       0
  5008.8     .05       0  5012.9     .05       0  5335.8     .07       0
  5468.5     .12       0  5499.5     .07       0
Bank Sta=5008.8,5012.9
XS Rating Curve= 0 ,0
Exp/Cntr=0.3,0.1

Type RM Length L Ch R = 1 ,27346   ,459,459,459
BEGIN DESCRIPTION:
DRY RUN 50.0
END DESCRIPTION:
XS GIS Cut Line= 3
      2468195.53     13783291.75        2468175.       13782625.
        2468075.     13781875.01
#Sta/Elev= 30
  4333.7  392.64  4530.5  391.25  4770.7  391.39  4860.7  389.23  4880.7  387.74
  4910.7   384.3  4930.7  383.06  5003.3   382.9  5018.8  382.28  5019.1  381.78
  5022.8  381.78  5023.1  382.28  5061.3  383.46  5091.6  382.98  5188.7  385.03
  5242.9   388.3  5353.9   390.7    5374  390.34  5454.8  391.31  5464.8  392.14
  5480.2  391.94  5491.3  391.93  5505.2  392.82  5515.3  392.08  5589.9  393.61
  5636.3   395.3  5647.7  395.03  5656.5   396.2    5707  398.01  5757.4  398.96
#Mann= 5 ,-1 , 0
  4333.7     .05       0  5018.8     .05       0  5023.1     .05       0
  5480.2     .12       0  5589.9     .07       0
Bank Sta=5018.8,5023.1
XS Rating Curve= 0 ,0
Exp/Cntr=0.3,0.1

Type RM Length L Ch R = 1 ,26887   ,428,428,428
BEGIN DESCRIPTION:
DRY RUN 49.0
END DESCRIPTION:
XS GIS Cut Line= 3
        2468975.     13783025.01        2468525.       13782425.
      2468375.01     13781625.05
#Sta/Elev= 30
  4260.1  404.33  4270.8  403.94  4296.6  403.42    4432  397.55  4523.6  391.98
  4617.4  388.37  4710.1  386.01  4746.6  380.68  4773.6  381.13  4794.4  380.03
  4794.7  379.53  4798.8  380.03    4832   380.6  4838.2  381.77  4846.6  381.49
  4852.8   382.3  4923.6  382.63  5012.7  381.56  5050.8  383.54  5101.7   387.5
  5279.6  389.64  5304.3  390.61  5376.4  391.02  5457.8  393.95  5480.9  393.76
  5577.3  396.18    5590  395.75  5610.4  396.92    5702  398.84    5824  404.08
#Mann= 6 ,-1 , 0
  4260.1    .045       0  4270.8     .05       0  4794.4     .05       0
  4798.8     .05       0  5279.6     .07       0  5480.9     .12       0
Bank Sta=4794.4,4798.8
XS Rating Curve= 0 ,0
Exp/Cntr=0.3,0.1

Type RM Length L Ch R = 1 ,26459   ,341,341,341
BEGIN DESCRIPTION:
DRY RUN 48.0
END DESCRIPTION:
XS GIS Cut Line= 3
        2468925.     13782774.97        2468875.       13782375.
      2468568.09      13781638.9
#Sta/Elev= 30
    4596  393.64  4719.4   388.1  4767.3  385.16  4787.4  382.78    4795  380.94
  4837.8  380.98    4858  379.36  4868.1  376.52  4875.6  377.85  4880.7  379.92
  4918.5  378.54  4968.8  381.12  4978.9  381.02  4996.6  378.55  5001.8  378.55
    5006   376.1  5006.3   375.6  5010.5   376.1  5020.7  379.98  5061.4  385.57
  5090.6  386.55  5222.2  387.67  5244.4  388.58  5350.5  389.23  5491.8  391.92
    5546  393.17  5663.6  395.01  5692.8  396.91  5711.2  396.58  5796.6  399.31
#Mann= 6 ,-1 , 0
    4596     .05       0    5006     .05       0  5010.5     .05       0
  5222.2     .12       0  5491.8     .07       0    5546     .12       0
Bank Sta=5006,5010.5
XS Rating Curve= 0 ,0
Exp/Cntr=0.3,0.1

Type RM Length L Ch R = 1 ,26118   ,549,549,549
BEGIN DESCRIPTION:
X19060
END DESCRIPTION:
XS GIS Cut Line= 4
       2469332.6     13782809.41      2469125.85     13782333.88
      2468912.22     13782202.95      2468622.87     13781589.78
#Sta/Elev= 30
  4590.1  389.48  4682.1  387.86  4911.1  385.91  4943.1  381.61  4968.7   379.2
  5016.6  374.48  5016.9  373.98  5021.1  374.48  5047.8  379.49  5053.2  378.68
  5085.6   382.5  5158.4  383.51  5167.9  384.36  5173.8  383.39  5197.1  383.45
  5238.6  382.82    5284  383.59  5289.9  382.73  5305.3  383.86  5320.7  383.66
  5347.9  386.03    5369  385.86    5379  384.74  5393.2  386.08  5670.5  392.08
  5710.6  392.19    5755  393.93  5799.2  393.88  5977.6  396.94  6037.2  399.71
#Mann= 6 ,-1 , 0
  4590.1     .05       0  4968.7      .1       0  5016.6     .05       0
  5021.1      .1       0  5197.1     .05       0  5393.2     .12       0
Bank Sta=5016.6,5021.1
XS Rating Curve= 0 ,0
Exp/Cntr=0.3,0.1

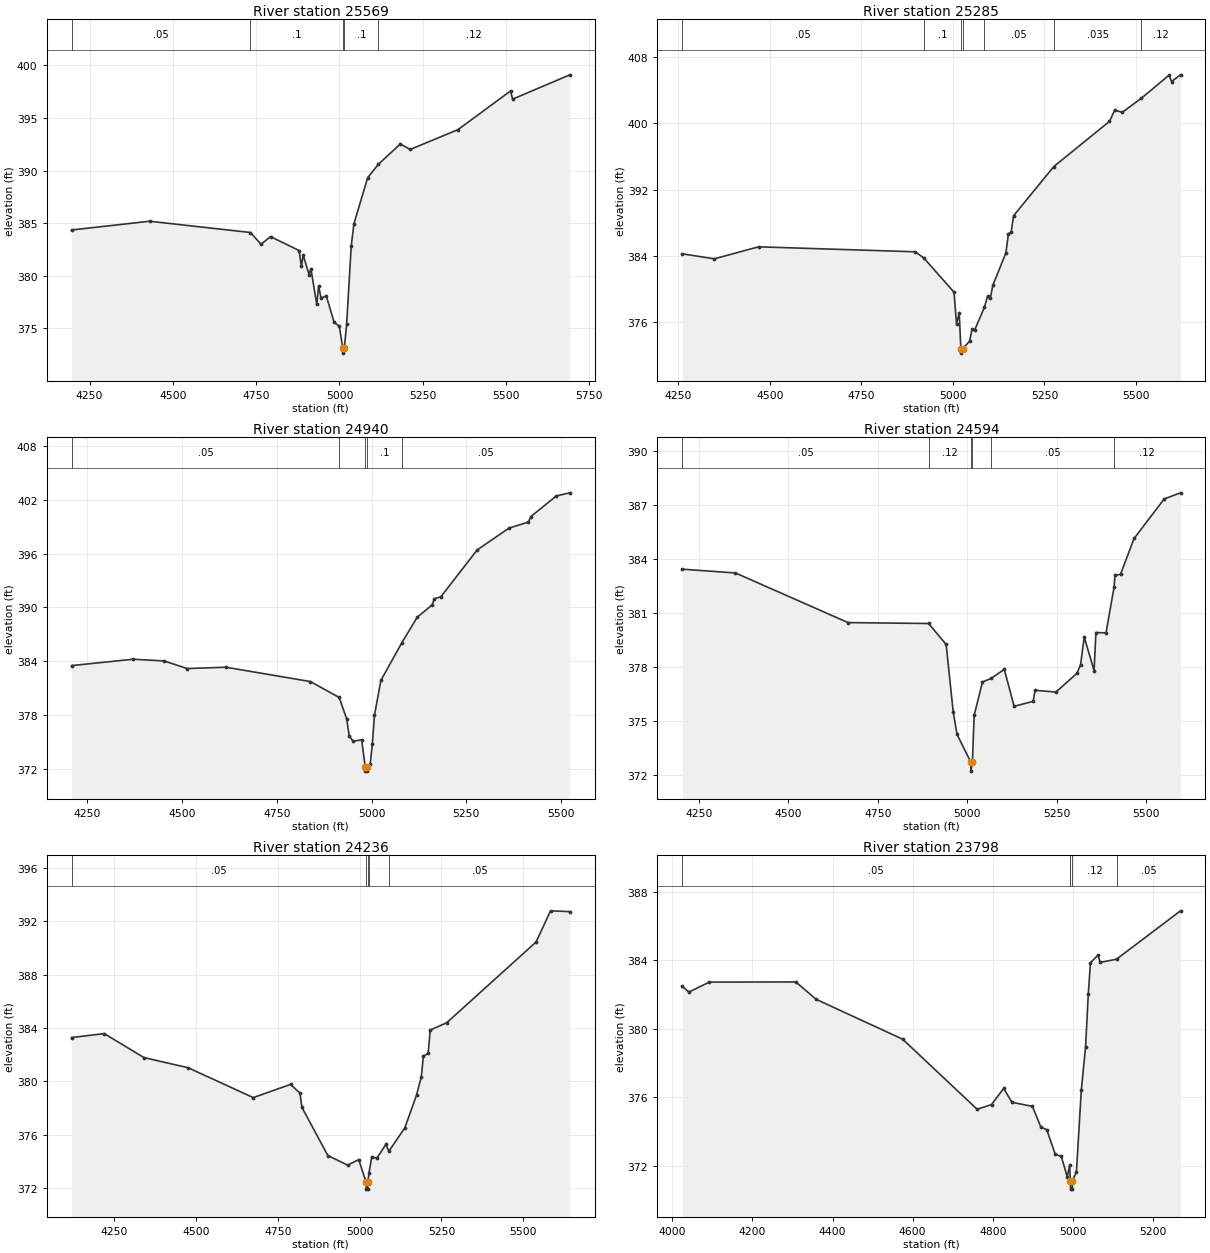
Type RM Length L Ch R = 1 ,25569   ,284,284,284
BEGIN DESCRIPTION:
X19059
END DESCRIPTION:
XS GIS Cut Line= 4
      2469594.44     13782616.38      2469422.18     13782230.51
      2468994.92     13782037.56      2468650.33     13781541.35
#Sta/Elev= 30
  4195.9  384.35  4430.2  385.18  4732.9  384.11  4764.5  382.99  4793.1  383.72
  4878.7   382.4  4885.6   380.9  4891.1  381.97  4908.7   380.1  4914.2  380.67
  4931.8  377.27  4937.3  379.04  4944.5  377.89  4960.4  378.09  4983.6   375.6
  4999.4   375.2  5009.9  373.15  5010.2  372.65  5014.5  373.15  5021.4  375.39
  5035.3  382.85  5043.3  384.94  5084.5  389.31  5116.6  390.59  5182.6  392.52
  5212.1     392  5355.5  393.88  5513.5  397.56  5519.6  396.78  5691.4  399.09
#Mann= 5 ,-1 , 0
  4195.9     .05       0  4732.9      .1       0  5009.9     .05       0
  5014.5      .1       0  5116.6     .12       0
Bank Sta=5009.9,5014.5
XS Rating Curve= 0 ,0
Exp/Cntr=0.3,0.1

Type RM Length L Ch R = 1 ,25285   ,345,345,345
BEGIN DESCRIPTION:
X19058
END DESCRIPTION:
XS GIS Cut Line= 3
      2469608.22     13782575.03      2469353.26     13782009.99
      2468850.17     13781465.55
#Sta/Elev= 30
  4260.4  384.28    4348  383.67  4468.9  385.12  4896.9  384.52    4920  383.79
  5002.9  379.65  5009.7  375.83  5017.1  377.14  5021.6   372.8  5021.9   372.3
  5026.2   372.8  5045.4  373.75  5052.2  375.19  5059.6  375.12  5085.8  377.81
  5094.8  379.18  5102.1  378.95  5108.9  380.47  5144.7   384.4  5151.5  386.71
  5158.8  386.85  5165.6  388.87  5275.5   394.8  5427.6  400.25  5441.8  401.59
  5462.8  401.35  5513.9  403.01  5590.3  405.82  5597.2  405.05  5621.6  405.86
#Mann= 7 ,-1 , 0
  4260.4     .05       0    4920      .1       0  5021.6     .05       0
  5026.2      .1       0  5085.8     .05       0  5275.5    .035       0
  5513.9     .12       0
Bank Sta=5021.6,5026.2
XS Rating Curve= 0 ,0
Exp/Cntr=0.3,0.1

Type RM Length L Ch R = 1 ,24940   ,346,346,346
BEGIN DESCRIPTION:
X19057
END DESCRIPTION:
XS GIS Cut Line= 3
      2469670.25      13782444.1      2469546.22     13781837.71
      2469243.01     13781210.61
#Sta/Elev= 30
    4208   383.5  4370.4  384.21    4452  384.02  4513.5  383.17  4615.4  383.32
  4838.4  381.72  4914.4  379.95  4934.3  377.56    4941  375.65  4951.3  375.07
  4973.9  375.22  4983.2  372.23  4983.5  371.73  4987.5  371.73  4987.8  372.23
  4996.5  372.55  5002.1  374.78  5007.7  377.98  5024.7  381.86  5079.8  386.04
  5120.6   388.9  5160.2  390.28  5165.8  390.96  5182.8  391.17  5278.8   396.4
  5363.1  398.84  5414.3  399.51  5419.9   400.1  5487.7  402.42  5523.5  402.77
#Mann= 5 ,-1 , 0
    4208     .05       0  4914.4      .1       0  4983.2     .05       0
  4987.8      .1       0  5079.8     .05       0
Bank Sta=4983.2,4987.8
XS Rating Curve= 0 ,0
Exp/Cntr=0.3,0.1

Type RM Length L Ch R = 1 ,24594   ,358,358,358
BEGIN DESCRIPTION:
X19056
END DESCRIPTION:
XS GIS Cut Line= 3
      2469732.28     13782361.49      2469828.76     13781823.93
      2469677.15     13780990.05
#Sta/Elev= 30
    4203  383.43  4351.8  383.22  4666.8  380.47    4892  380.42  4941.2  379.26
  4961.1  375.49  4971.7  374.28    5010  372.74  5010.3  372.24  5014.6  372.74
  5019.6  375.33  5042.8  377.18  5067.3  377.38  5103.8  377.88  5131.4  375.83
  5184.7  376.11  5189.8  376.72  5248.3  376.62  5307.1  377.66  5317.2  378.14
  5327.4  379.67    5355  377.81  5360.1  379.92  5388.4   379.9  5410.8  382.43
  5413.4  383.08    5429  383.15  5466.8  385.13    5551  387.32  5596.7  387.66
#Mann= 6 ,-1 , 0
    4203     .05       0    4892     .12       0    5010     .05       0
  5014.6     .12       0  5067.3     .05       0  5410.8     .12       0
Bank Sta=5010,5014.6
XS Rating Curve= 0 ,0
Exp/Cntr=0.3,0.1

Type RM Length L Ch R = 1 ,24236   ,438,438,438
BEGIN DESCRIPTION:
DRY RUN 47.0
END DESCRIPTION:
XS GIS Cut Line= 3
      2469794.31      13782368.3        2470025.       13781525.
      2470400.71     13780997.01
#Sta/Elev= 30
  4120.1  383.29  4219.7  383.59  4341.2  381.79    4476  381.03  4675.2  378.79
  4789.1  379.78  4818.1  379.12  4823.6  378.07  4902.9  374.45  4963.3  373.73
  4997.4  374.14  5020.1  372.43  5020.5  371.93  5024.9  371.93  5025.3  372.43
  5028.5  373.11  5037.4  374.37  5052.2  374.23  5080.3  375.28  5089.5  374.77
  5138.3  376.53  5173.9  378.97  5188.7  380.35  5194.8  381.89  5209.6  382.11
  5215.7  383.85  5266.1   384.4  5539.1  390.45  5583.4  392.79  5642.4  392.73
#Mann= 5 ,-1 , 0
  4120.1     .05       0  5020.1     .05       0  5025.3     .05       0
  5028.5     .12       0  5089.5     .05       0
Bank Sta=5020.1,5025.3
XS Rating Curve= 0 ,0
Exp/Cntr=0.3,0.1

Type RM Length L Ch R = 1 ,23798   ,417,417,417
BEGIN DESCRIPTION:
DRY RUN 46.0
END DESCRIPTION:
XS GIS Cut Line= 3
      2469780.53     13782533.71        2470325.       13781725.
      2470425.01     13781474.97
#Sta/Elev= 30
  4024.7  382.48  4041.4  382.15  4092.4  382.73  4308.3  382.74  4359.3  381.72
  4575.2  379.39  4761.2  375.29  4797.2  375.57  4827.2  376.51  4848.2   375.7
  4899.1  375.46  4920.1  374.26  4935.1  374.09  4956.1  372.66  4971.1  372.54
  4986.1  371.34    4992  372.01    4994  371.12  4994.4  370.62  4998.8  370.62
  4999.2  371.12    5009  371.62  5021.2  376.41  5031.9  378.96  5038.7  382.06
    5044  383.86  5062.9  384.31  5068.3  383.88  5109.1  384.07  5268.9   386.9
#Mann= 5 ,-1 , 0
  4024.7     .05       0    4992     .12       0    4994     .05       0
  4999.2     .12       0  5109.1     .05       0
Bank Sta=4994,4999.2
XS Rating Curve= 0 ,0
Exp/Cntr=0.3,0.1

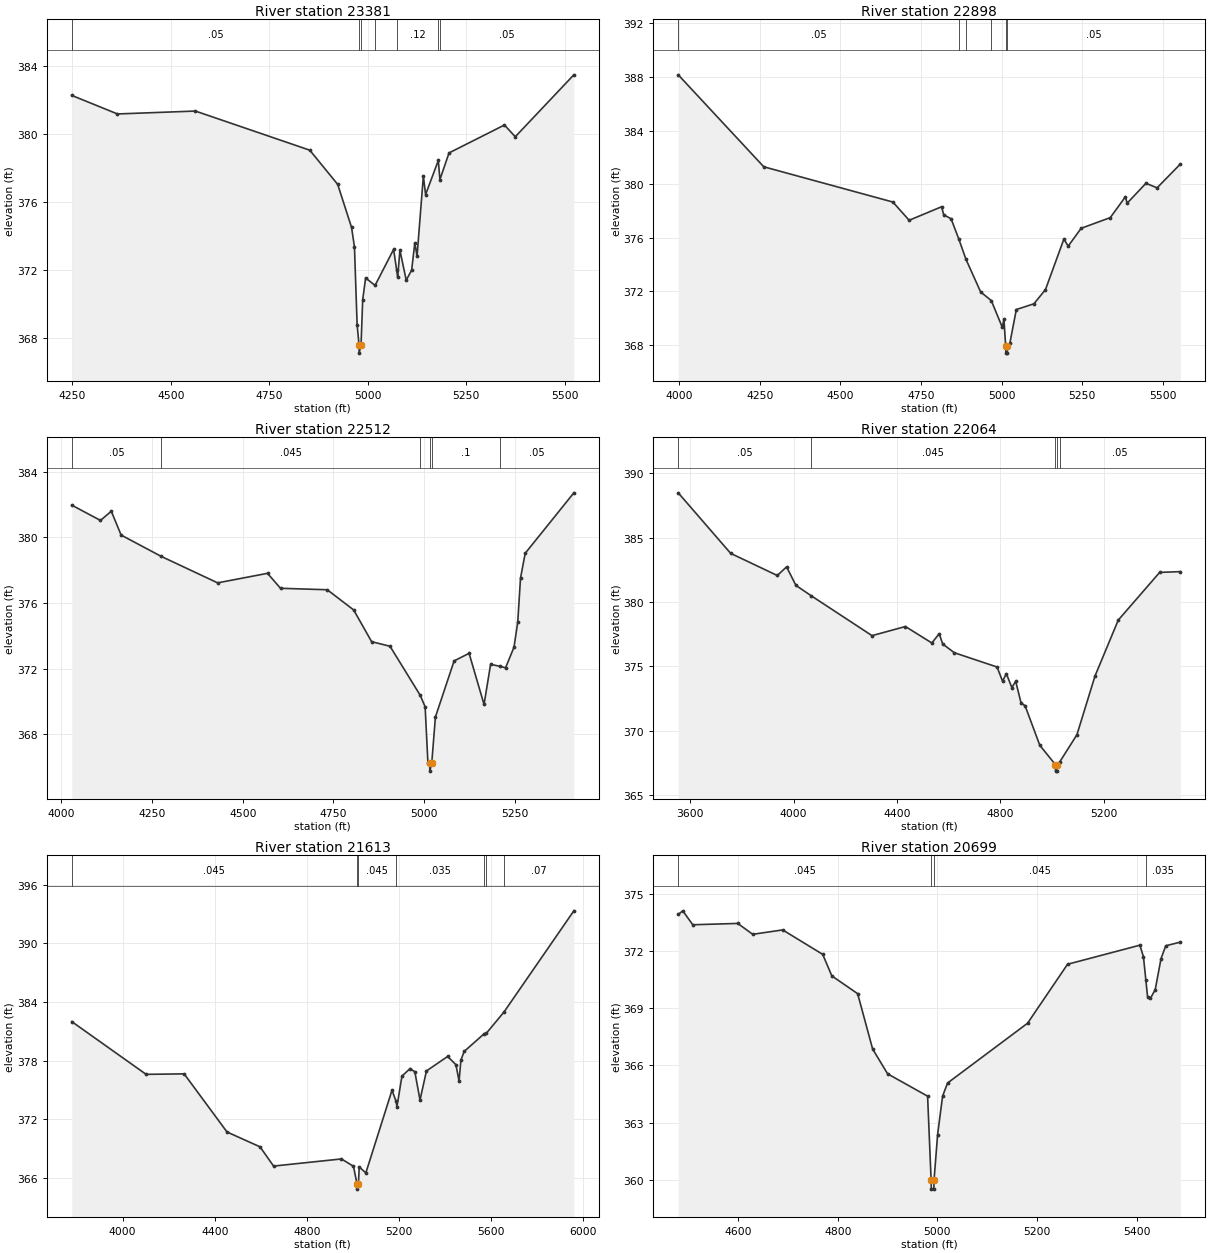
Type RM Length L Ch R = 1 ,23381   ,483,483,483
BEGIN DESCRIPTION:
DRY RUN 45.0
END DESCRIPTION:
XS GIS Cut Line= 3
      2469815.01     13782588.83        2470375.       13782075.
      2470625.01     13781624.99
#Sta/Elev= 30
  4248.4  382.26  4364.4  381.17  4562.3  381.34  4852.7  379.04  4923.6  377.03
  4958.8   374.5  4966.2  373.35  4972.9  368.79  4977.7  367.61  4978.1  367.11
  4982.9  367.61  4987.1  370.25  4994.5  371.53  5018.5  371.09  5065.6  373.21
  5073.3  371.99  5075.9  371.58  5081.6  373.16  5097.6   371.4  5111.4  371.99
  5119.4   373.6  5125.1  372.81  5141.1  377.52  5146.8  376.43  5179.1  378.44
  5183.1  377.31  5206.3  378.88    5347  380.52  5374.5  379.83  5523.2  383.47
#Mann= 7 ,-1 , 0
  4248.4     .05       0  4977.7     .05       0  4982.9     .05       0
  5018.5      .1       0  5073.3     .12       0  5179.1      .1       0
  5183.1     .05       0
Bank Sta=4977.7,4982.9
XS Rating Curve= 0 ,0
Exp/Cntr=0.3,0.1

Type RM Length L Ch R = 1 ,22898   ,386,386,386
BEGIN DESCRIPTION:
DRY RUN 44.0
END DESCRIPTION:
XS GIS Cut Line= 3
      2470124.98     13783025.03      2470648.82     13782292.53
      2470717.61     13781638.98
#Sta/Elev= 30
  3996.6  388.16    4262   381.3  4662.6  378.67    4713  377.31  4813.7  378.32
  4820.3  377.72  4843.2  377.42  4866.6  375.94  4889.3   374.4  4934.9  371.96
  4967.9  371.32  5002.1  369.32  5007.1  369.93  5012.6   367.9  5013.1   367.4
  5017.6   367.4    5018   367.9  5025.4  368.13  5045.5  370.65  5100.1  371.08
    5136  372.14  5193.1  375.91  5206.4  375.38  5246.6  376.71  5337.1  377.51
  5384.2  379.07  5389.2  378.58  5447.7  380.07  5482.2  379.73  5554.3   381.5
#Mann= 6 ,-1 , 0
  3996.6     .05       0  4866.6      .1       0  4889.3    .045       0
  4967.9     .05       0  5012.6     .05       0    5018     .05       0
Bank Sta=5012.6,5018
XS Rating Curve= 0 ,0
Exp/Cntr=0.3,0.1

Type RM Length L Ch R = 1 ,22512   ,448,448,448
BEGIN DESCRIPTION:
DRY RUN 43.0
END DESCRIPTION:
XS GIS Cut Line= 3
      2470475.02     13782924.97        2471025.       13782125.
        2470925.       13781725.
#Sta/Elev= 30
  4029.1  381.96  4108.2  381.03    4138  381.59    4165  380.14  4275.6  378.84
  4430.9  377.23  4568.3  377.81  4604.1   376.9  4732.9  376.81  4805.7  375.58
  4855.1  373.65  4905.8  373.37  4988.9  370.39  5002.5  369.69  5010.2  366.29
    5015  366.27  5015.5  365.77  5020.8  366.27  5030.8  369.06  5082.4  372.48
  5123.6  372.94  5164.8  369.83  5182.9  372.27  5208.5  372.15  5224.1  372.06
  5247.3  373.31  5257.6  374.83  5265.3  377.52  5278.2  379.03  5412.2  382.71
#Mann= 6 ,-1 , 0
  4029.1     .05       0  4275.6    .045       0  4988.9      .1       0
    5015     .05       0  5020.8      .1       0  5208.5     .05       0
Bank Sta=5015,5020.8
XS Rating Curve= 0 ,0
Exp/Cntr=0.3,0.1

Type RM Length L Ch R = 1 ,22064   ,451,451,451
BEGIN DESCRIPTION:
DRY RUN 42.0
END DESCRIPTION:
XS GIS Cut Line= 3
      2470174.97     13783175.02        2471375.       13782375.
        2471375.     13781874.96
#Sta/Elev= 30
  3553.4  388.49  3756.3  383.78  3936.5  382.06  3972.6  382.73  4008.6  381.29
  4067.3  380.49  4303.1  377.38  4432.3  378.09  4534.4  376.81    4563  377.53
  4576.5  376.73  4621.6  376.05  4786.8  374.94  4807.9  373.84  4822.9  374.42
  4843.9  373.34  4858.9  373.83    4880  372.11    4895  371.94  4952.1  368.85
  5012.8  367.34  5013.2  366.84  5018.1  366.84  5018.6  367.34  5029.6  367.57
  5095.7  369.67  5165.7  374.24  5255.7  378.59  5415.7   382.3  5495.7  382.36
#Mann= 5 ,-1 , 0
  3553.4     .05       0  4067.3    .045       0  5012.8    .045       0
  5018.6    .045       0  5029.6     .05       0
Bank Sta=5012.8,5018.6
XS Rating Curve= 0 ,0
Exp/Cntr=0.3,0.1

Type RM Length L Ch R = 1 ,21613   ,914,914,914
BEGIN DESCRIPTION:
DRY RUN 41.0
END DESCRIPTION:
XS GIS Cut Line= 3
      2471075.01     13783524.99        2471775.       13782525.
      2472524.99     13781925.01
#Sta/Elev= 30
  3778.9     382  4101.9   376.6  4267.1  376.65  4453.3   370.7  4596.7  369.18
  4655.6  367.21  4950.3  367.94  5002.7  367.19  5018.2  365.35  5018.7  364.85
  5024.2  365.35  5027.6  367.12  5056.4  366.51    5170  374.97    5187  373.89
  5191.6  373.29  5213.2  376.42  5248.5  377.19  5269.3  376.86  5291.7  373.97
  5319.7  376.95  5411.7  378.43  5447.8  377.59  5461.4   375.9  5469.4  378.07
  5483.8  378.95  5570.6  380.76  5579.3  380.79  5656.2  382.97    5960  393.34
#Mann= 7 ,-1 , 0
  3778.9    .045       0  5018.2    .045       0  5024.2    .045       0
    5187    .035       0  5570.6     .07       0  5579.3     .05       0
  5656.2     .07       0
Bank Sta=5018.2,5024.2
XS Rating Curve= 0 ,0
Exp/Cntr=0.3,0.1

Type RM Length L Ch R = 1 ,20699   ,410,410,410
BEGIN DESCRIPTION:
DRY RUN 40.0
END DESCRIPTION:
XS GIS Cut Line= 3
      2471774.04     13783744.06      2471846.02     13782882.17
      2471967.84      13782806.5
#Sta/Elev= 30
  4479.6  373.91  4488.7   374.1  4508.8  373.37  4599.1  373.44  4629.2  372.87
  4689.4   373.1  4769.7  371.82  4788.1  370.69  4839.9  369.76    4870  366.86
  4900.1  365.56  4980.4  364.39  4987.4  360.02  4987.9  359.52  4992.9  359.52
  4993.4  360.02  5000.5  362.38  5010.5  364.39  5020.5  365.08  5181.1  368.21
  5261.4   371.3  5406.7   372.3  5413.9  371.69  5418.7  370.47  5422.1  369.61
    5428  369.52  5437.5  369.97  5449.2   371.6  5458.7  372.27  5487.9  372.46
#Mann= 4 ,-1 , 0
  4479.6    .045       0  4987.4    .045       0  4993.4    .045       0
  5418.7    .035       0
Bank Sta=4987.4,4993.4
XS Rating Curve= 0 ,0
Exp/Cntr=0.3,0.1

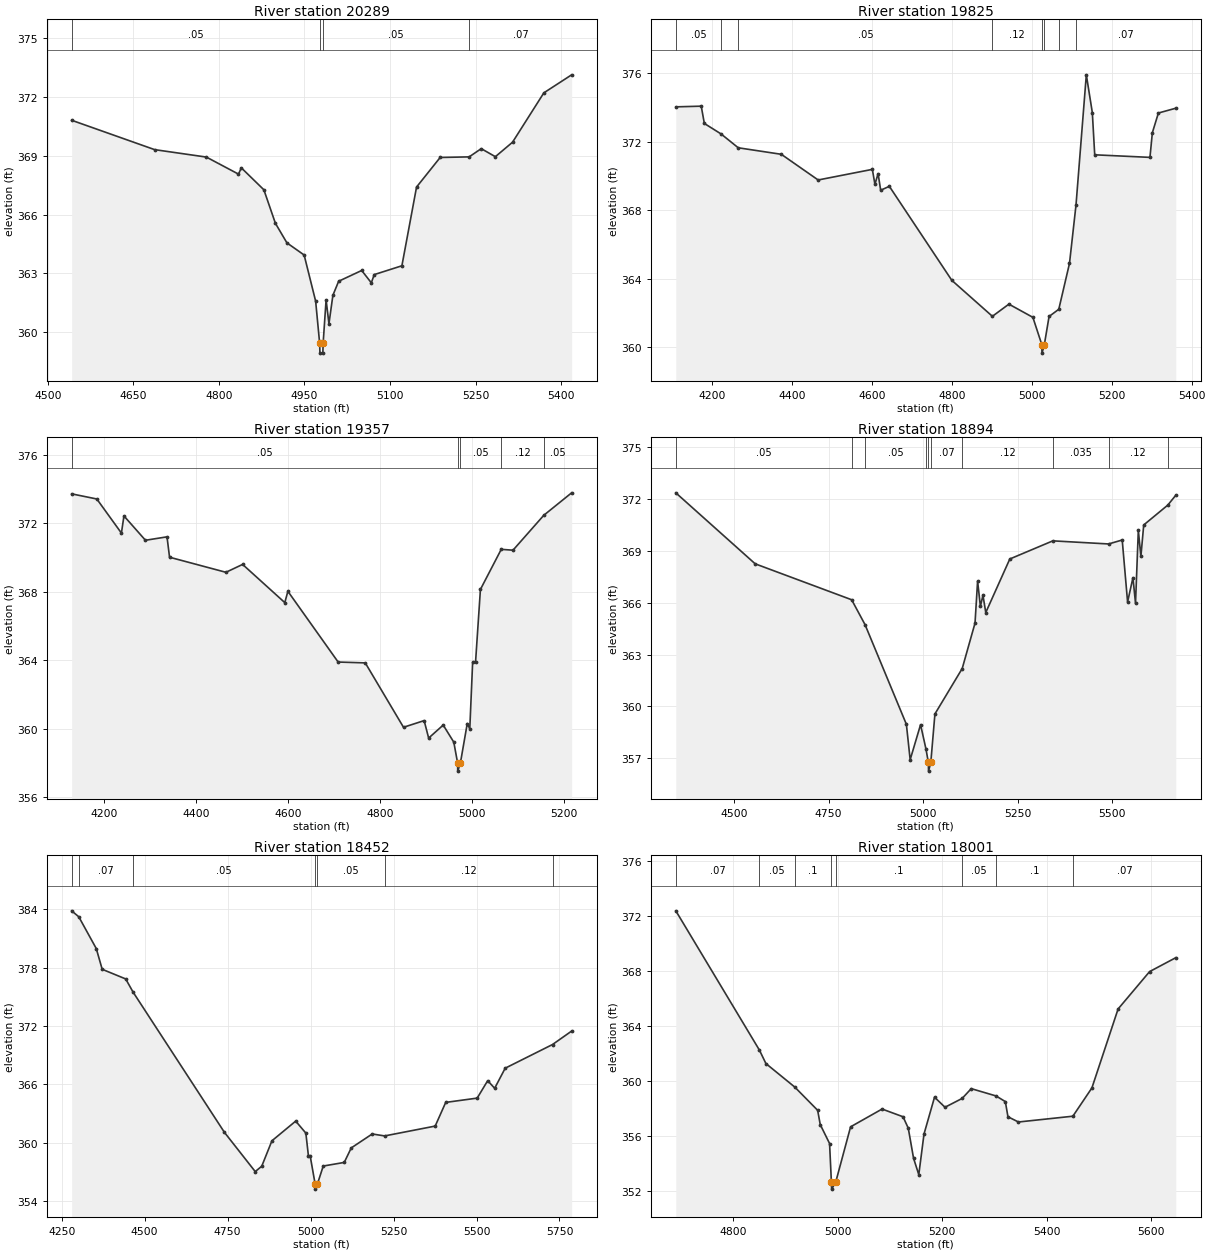
Type RM Length L Ch R = 1 ,20289   ,464,464,464
BEGIN DESCRIPTION:
DRY RUN 39.0
END DESCRIPTION:
XS GIS Cut Line= 3
      2472152.38     13783729.26      2472235.43     13783087.03
      2472316.65      13782872.9
#Sta/Elev= 30
  4541.9  370.82  4687.4  369.32  4778.1  368.94  4834.4  368.07  4839.4  368.39
  4878.9  367.27  4899.1  365.56  4919.3  364.56  4949.5  363.94  4969.7  361.58
  4976.7  359.43  4977.2  358.93  4982.3  358.93  4982.8  359.43    4988  361.65
    4993  360.43  4999.9  361.88    5010   362.6  5050.4  363.15  5067.3  362.52
  5072.4  362.94  5120.9  363.39  5146.6  367.41    5188  368.92  5238.8  368.95
    5260  369.37  5284.8  368.96  5314.9   369.7  5369.8  372.22  5418.5  373.14
#Mann= 4 ,-1 , 0
  4541.9     .05       0  4976.7     .05       0  4982.8     .05       0
  5238.8     .07       0
Bank Sta=4976.7,4982.8
XS Rating Curve= 0 ,0
Exp/Cntr=0.3,0.1

Type RM Length L Ch R = 1 ,19825   ,468,468,468
BEGIN DESCRIPTION:
DRY RUN 38.0
END DESCRIPTION:
XS GIS Cut Line= 3
      2472074.97     13784125.04        2472625.       13783425.
      2472924.98     13783225.01
#Sta/Elev= 30
  4109.5  374.03  4173.1  374.07  4180.9  373.06  4222.6  372.45  4265.7  371.64
  4373.4  371.26  4465.6  369.76  4601.2  370.38  4607.6  369.51  4615.6  370.13
    4622  369.16  4643.7  369.39    4800   363.9  4901.5   361.8  4942.8  362.51
  5002.8  361.74  5025.1  360.15  5025.6  359.65  5031.5  360.15  5043.3  361.79
  5067.6  362.21  5094.4  364.89  5110.7   368.3  5136.5   375.9  5151.5   373.7
  5157.5  371.23  5295.7  371.08  5301.7  372.52  5316.8  373.67  5360.3  373.95
#Mann= 8 ,-1 , 0
  4109.5     .05       0  4222.6    .035       0  4265.7     .05       0
  4901.5     .12       0  5025.1     .05       0  5031.5     .12       0
  5067.6     .05       0  5110.7     .07       0
Bank Sta=5025.1,5031.5
XS Rating Curve= 0 ,0
Exp/Cntr=0.3,0.1

Type RM Length L Ch R = 1 ,19357   ,463,463,463
BEGIN DESCRIPTION:
DRY RUN 37.0
END DESCRIPTION:
XS GIS Cut Line= 3
      2472124.99     13784125.01        2472925.       13783775.
      2473075.03     13783624.97
#Sta/Elev= 30
  4130.6  373.72  4185.2  373.42  4238.6  371.43  4244.1  372.43  4290.8  371.01
  4337.6  371.21  4343.1  370.02  4465.5  369.14  4501.7   369.6  4593.3  367.37
    4600  368.03  4709.1   363.9    4768  363.85    4851  360.09  4895.8  360.48
  4905.6  359.46  4937.2  360.22  4960.2  359.22  4968.3  358.03  4968.8  357.53
  4974.7  358.03  4989.4  360.31  4994.9     360  5001.1  363.89  5007.4  363.89
    5018  368.14  5063.2  370.48  5088.7  370.43  5155.6  372.47    5216  373.78
#Mann= 5 ,-1 , 0
  4130.6     .05       0  4968.3     .05       0  4974.7     .05       0
  5063.2     .12       0  5155.6     .05       0
Bank Sta=4968.3,4974.7
XS Rating Curve= 0 ,0
Exp/Cntr=0.3,0.1

Type RM Length L Ch R = 1 ,18894   ,442,442,442
BEGIN DESCRIPTION:
DRY RUN 36.0
END DESCRIPTION:
XS GIS Cut Line= 3
        2472225.       13784225.        2472875.       13784225.
      2473375.01     13783774.99
#Sta/Elev= 30
  4345.6  372.36  4555.6  368.25  4810.8  366.17  4846.2  364.73  4955.6  358.96
  4965.6  356.91  4993.1  358.94  5007.6  357.51  5013.7  356.75  5014.2  356.25
  5020.2  356.75  5031.1  359.56  5103.3  362.19  5137.2  364.82    5144  367.25
  5151.4  365.79  5158.2  366.43  5165.6  365.43  5229.2  368.53  5343.1  369.58
  5490.6   369.4  5526.6  369.63  5540.8  366.04    5555  367.45  5561.8  365.96
  5569.2  370.19    5576  368.68  5583.5   370.5  5647.2  371.65  5668.3  372.22
#Mann= 10 ,-1 , 0
  4345.6     .05       0  4810.8     .07       0  4846.2     .05       0
  5007.6     .07       0  5013.7     .05       0  5020.2     .07       0
  5103.3     .12       0  5343.1    .035       0  5490.6     .12       0
  5647.2    .035       0
Bank Sta=5013.7,5020.2
XS Rating Curve= 0 ,0
Exp/Cntr=0.3,0.1

Type RM Length L Ch R = 1 ,18452   ,451,451,451
BEGIN DESCRIPTION:
DRY RUN 35.0
END DESCRIPTION:
XS GIS Cut Line= 3
      2473274.99     13785274.97        2473125.       13784575.
      2473374.99     13783825.03
#Sta/Elev= 30
  4280.2  383.82  4301.6  383.21  4354.3  379.95  4372.2  377.82    4443  376.83
  4465.2  375.48  4740.4  361.09  4833.3  357.06  4852.9  357.61  4883.6  360.22
  4955.2  362.24  4985.8  361.01  4993.5  358.69  4998.7  358.69  5013.9  355.76
  5014.4  355.26  5020.4  355.76  5038.2  357.63  5101.5     358  5122.6  359.49
  5185.8  360.92  5223.2  360.72  5375.5  361.73  5407.2  364.16    5502   364.6
  5533.7  366.39  5554.7  365.61  5586.4  367.67    5729   370.1  5786.6  371.48
#Mann= 7 ,-1 , 0
  4280.2    .035       0  4301.6     .07       0  4465.2     .05       0
  5013.9     .05       0  5020.4     .05       0  5223.2     .12       0
    5729    .035       0
Bank Sta=5013.9,5020.4
XS Rating Curve= 0 ,0
Exp/Cntr=0.3,0.1

Type RM Length L Ch R = 1 ,18001   ,423,423,423
BEGIN DESCRIPTION:
DRY RUN 34.0
END DESCRIPTION:
XS GIS Cut Line= 3
        2473475.     13785024.97        2473525.       13784725.
        2473475.     13784075.03
#Sta/Elev= 30
  4690.6  372.35  4850.4  362.25  4862.9  361.27  4917.9  359.57  4961.8  357.88
  4966.8  356.84  4984.6  355.47  4988.1  352.66  4988.6  352.16  4996.3  352.66
  5024.8  356.68    5085  357.97  5125.1  357.41  5135.1  356.58  5145.2   354.4
  5155.2  353.21  5165.2  356.16  5185.3  358.83  5205.3   358.1  5238.1  358.74
  5255.5  359.45  5302.9  358.92  5320.7  358.51  5325.7  357.41  5345.7  357.03
  5449.8  357.45  5486.2   359.5  5536.3  365.23  5596.5  367.94  5646.6  368.95
#Mann= 8 ,-1 , 0
  4690.6     .07       0  4850.4     .05       0  4917.9      .1       0
  4988.1     .05       0  4996.3      .1       0  5238.1     .05       0
  5302.9      .1       0  5449.8     .07       0
Bank Sta=4988.1,4996.3
XS Rating Curve= 0 ,0
Exp/Cntr=0.3,0.1

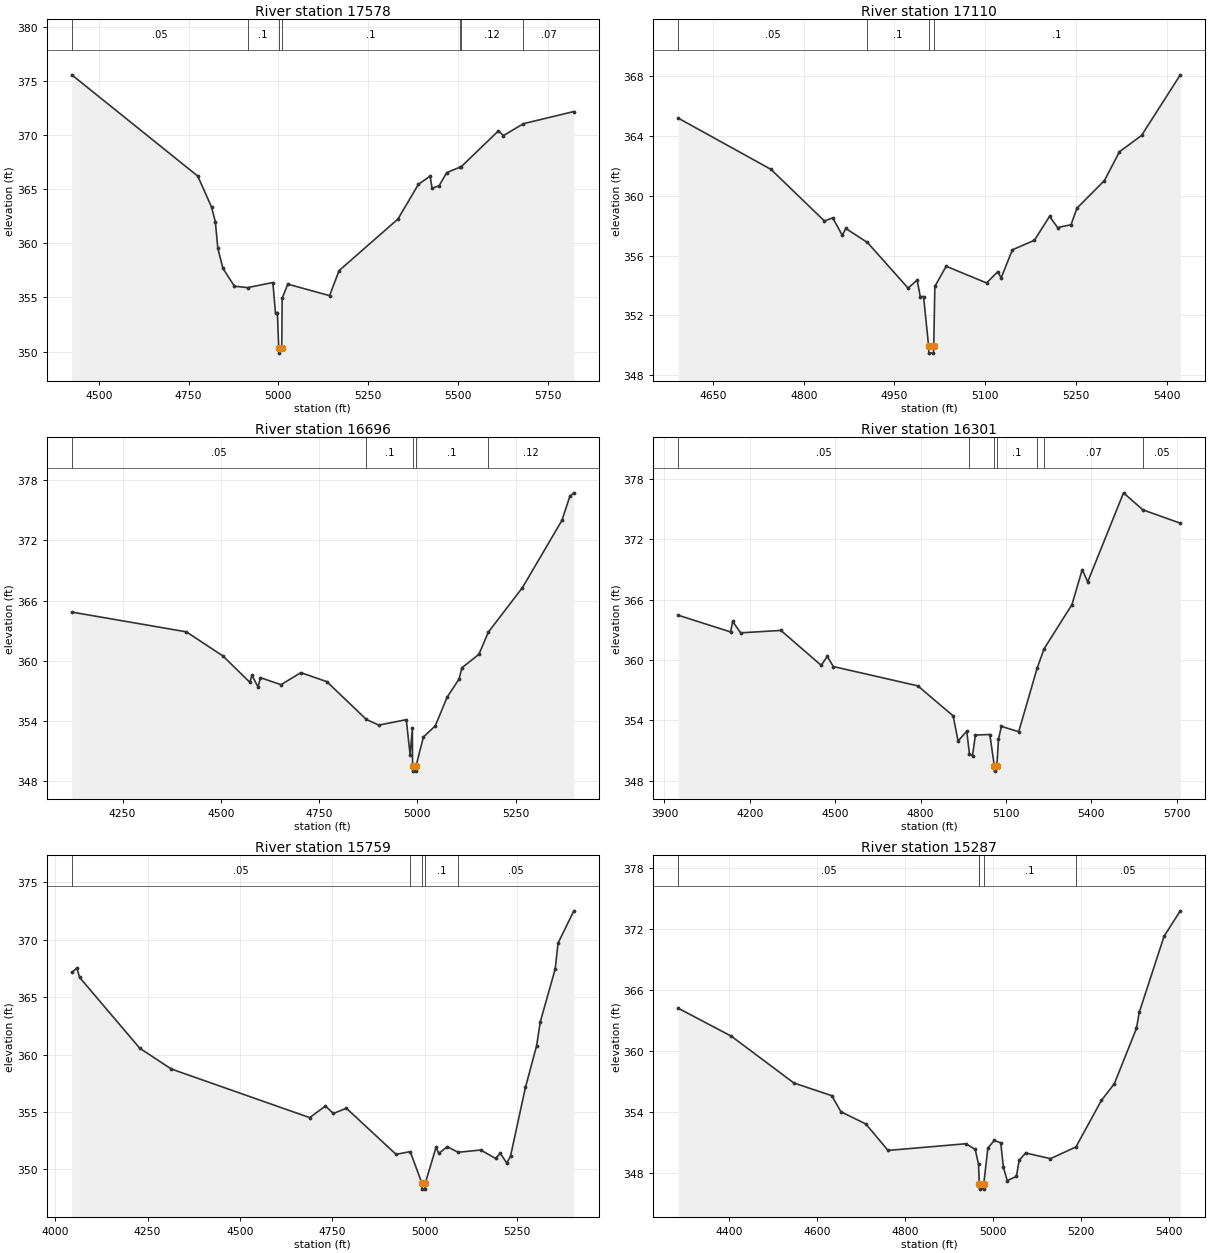
Type RM Length L Ch R = 1 ,17578   ,468,468,468
BEGIN DESCRIPTION:
DRY RUN 33.0
END DESCRIPTION:
XS GIS Cut Line= 3
      2473680.98     13785310.88        2473875.       13784775.
      2474135.41     13783988.94
#Sta/Elev= 30
  4424.7  375.56  4775.5  366.21  4813.8  363.36  4824.5  361.99  4831.4  359.54
  4845.7  357.68  4877.6  356.04  4914.2  355.91  4984.6  356.38    4992  353.55
  4997.3  353.55  5000.9  350.36  5001.4  349.86  5009.4  350.36  5010.5  354.93
  5026.2  356.23  5142.5  355.17    5169  357.48  5332.8  362.24  5389.7  365.44
  5422.6  366.21  5427.9  365.09  5447.6  365.32  5468.7  366.53  5505.2  367.03
    5508  367.04  5612.8  370.39  5626.7  369.95  5682.4  371.05  5822.7  372.17
#Mann= 7 ,-1 , 0
  4424.7     .05       0  4914.2      .1       0  5000.9     .05       0
  5009.4      .1       0  5505.2     .07       0    5508     .12       0
  5682.4     .07       0
Bank Sta=5000.9,5009.4
XS Rating Curve= 0 ,0
Exp/Cntr=0.3,0.1

Type RM Length L Ch R = 1 ,17110   ,414,414,414
BEGIN DESCRIPTION:
DRY RUN 32.0
END DESCRIPTION:
XS GIS Cut Line= 3
      2474075.02     13785124.97        2474275.       13784775.
      2474425.01     13784374.98
#Sta/Elev= 30
  4592.4  365.21  4745.7  361.78  4834.2  358.32  4847.9  358.53  4863.7  357.36
  4869.5  357.82  4905.3  356.88  4972.4  353.83  4987.6  354.36  4992.6  353.26
  4998.1  353.26  5006.4  349.97  5006.9  349.47  5014.4  349.47  5014.9  349.97
  5016.8  353.94  5035.5  355.29  5102.3  354.17    5121  354.93  5126.3   354.5
    5145  356.39  5181.5  357.03  5206.4  358.63  5219.8  357.88    5242  358.07
  5251.8  359.18  5297.2  361.03  5322.1  362.96  5358.6  364.05  5422.7  368.11
#Mann= 4 ,-1 , 0
  4592.4     .05       0  4905.3      .1       0  5006.4     .05       0
  5014.9      .1       0
Bank Sta=5006.4,5014.9
XS Rating Curve= 0 ,0
Exp/Cntr=0.3,0.1

Type RM Length L Ch R = 1 ,16696   ,395,395,395
BEGIN DESCRIPTION:
DRY RUN 31.0
END DESCRIPTION:
XS GIS Cut Line= 3
      2474175.02     13785424.97        2474625.       13784675.
        2474575.     13784275.02
#Sta/Elev= 30
  4120.6  364.85  4412.1  362.88  4505.4  360.47  4573.4  357.86  4579.3  358.54
  4594.8  357.37  4600.6  358.31  4653.1  357.61  4703.7  358.81  4769.7  357.91
  4870.4  354.14  4901.9  353.58  4971.9  354.12  4981.6  350.61  4987.4  353.28
  4987.9  349.49  4988.4  348.99  4996.1  348.99  4996.6  349.49  5015.4  352.39
  5045.6   353.5  5075.8  356.36  5106.1  358.17  5113.6   359.3  5156.5  360.63
  5180.9  362.86  5267.3  367.28  5368.1     374  5388.2   376.4  5398.3  376.74
#Mann= 5 ,-1 , 0
  4120.6     .05       0  4870.4      .1       0  4987.9     .05       0
  4996.6      .1       0  5180.9     .12       0
Bank Sta=4987.9,4996.6
XS Rating Curve= 0 ,0
Exp/Cntr=0.3,0.1

Type RM Length L Ch R = 1 ,16301   ,542,542,542
BEGIN DESCRIPTION:
DRY RUN 30.0
END DESCRIPTION:
XS GIS Cut Line= 3
      2474274.99     13785475.01      2474955.85     13784828.51
      2475093.68     13784015.32
#Sta/Elev= 30
  3948.6  364.44  4132.5  362.78  4139.7  363.82    4168  362.69  4309.2  362.93
  4450.8  359.46  4472.2  360.35  4493.3  359.34  4790.2  357.42  4914.4  354.43
  4931.6  351.93  4962.1  352.92  4971.7  350.62  4982.4  350.49  4992.5  352.53
  5043.2  352.58  5059.1  349.44  5059.6  348.94  5067.8  349.44  5073.6  352.12
  5083.8  353.39  5144.6  352.86  5209.3  359.17  5233.7   361.1  5331.7   365.5
  5367.8  368.98    5387  367.76  5512.8  376.61  5580.8  374.92  5712.3  373.59
#Mann= 7 ,-1 , 0
  3948.6     .05       0  4971.7      .1       0  5059.1     .05       0
  5067.8      .1       0  5209.3     .12       0  5233.7     .07       0
  5580.8     .05       0
Bank Sta=5059.1,5067.8
XS Rating Curve= 0 ,0
Exp/Cntr=0.3,0.1

Type RM Length L Ch R = 1 ,15759   ,472,472,472
BEGIN DESCRIPTION:
DRY RUN 29.0
END DESCRIPTION:
XS GIS Cut Line= 3
      2474725.02     13785524.98        2475375.       13784825.
      2475774.97       13784775.
#Sta/Elev= 30
  4044.8  367.16  4058.7  367.54    4066  366.73  4228.7  360.56  4313.8  358.75
  4688.5  354.51    4731  355.52  4752.5  354.87  4787.7  355.33  4922.1  351.31
  4960.4  351.55  4992.3  348.78  4992.8  348.28  5000.5  348.28    5001  348.78
  5030.3  351.92  5037.8  351.39  5060.5  351.98    5090  351.49  5151.2  351.69
  5191.5  350.95  5204.1  351.41  5221.7  350.55  5231.8  351.16  5272.1  357.14
  5302.4  360.78  5312.4  362.87  5352.7  367.47  5360.3  369.71  5403.1  372.53
#Mann= 5 ,-1 , 0
  4044.8     .05       0  4960.4      .1       0  4992.3     .05       0
    5001      .1       0    5090     .05       0
Bank Sta=4992.3,5001
XS Rating Curve= 0 ,0
Exp/Cntr=0.3,0.1

Type RM Length L Ch R = 1 ,15287   ,453,453,453
BEGIN DESCRIPTION:
DRY RUN 28.0
END DESCRIPTION:
XS GIS Cut Line= 3
      2475024.97     13785675.02        2475575.       13785225.
      2475825.01     13784874.99
#Sta/Elev= 30
  4284.7  364.18  4405.3  361.43  4547.5  356.82  4633.6  355.57  4654.4  353.99
  4711.1  352.78  4761.4  350.18  4938.7  350.84  4959.5  350.28    4967  348.82
  4968.8  346.87  4969.3  346.37  4978.4  346.37  4978.9  346.87  4988.2  350.41
  5002.7  351.16  5017.5  350.93  5023.6  348.51  5032.2  347.21  5053.1  347.62
  5059.3   349.2    5074  349.93  5130.5  349.37  5188.3  350.52  5246.1   355.1
  5275.6  356.75  5325.9   362.2  5332.1  363.76  5388.6  371.27  5425.5  373.77
#Mann= 5 ,-1 , 0
  4284.7     .05       0    4967      .1       0  4968.8     .05       0
  4978.9      .1       0  5188.3     .05       0
Bank Sta=4968.8,4978.9
XS Rating Curve= 0 ,0
Exp/Cntr=0.3,0.1