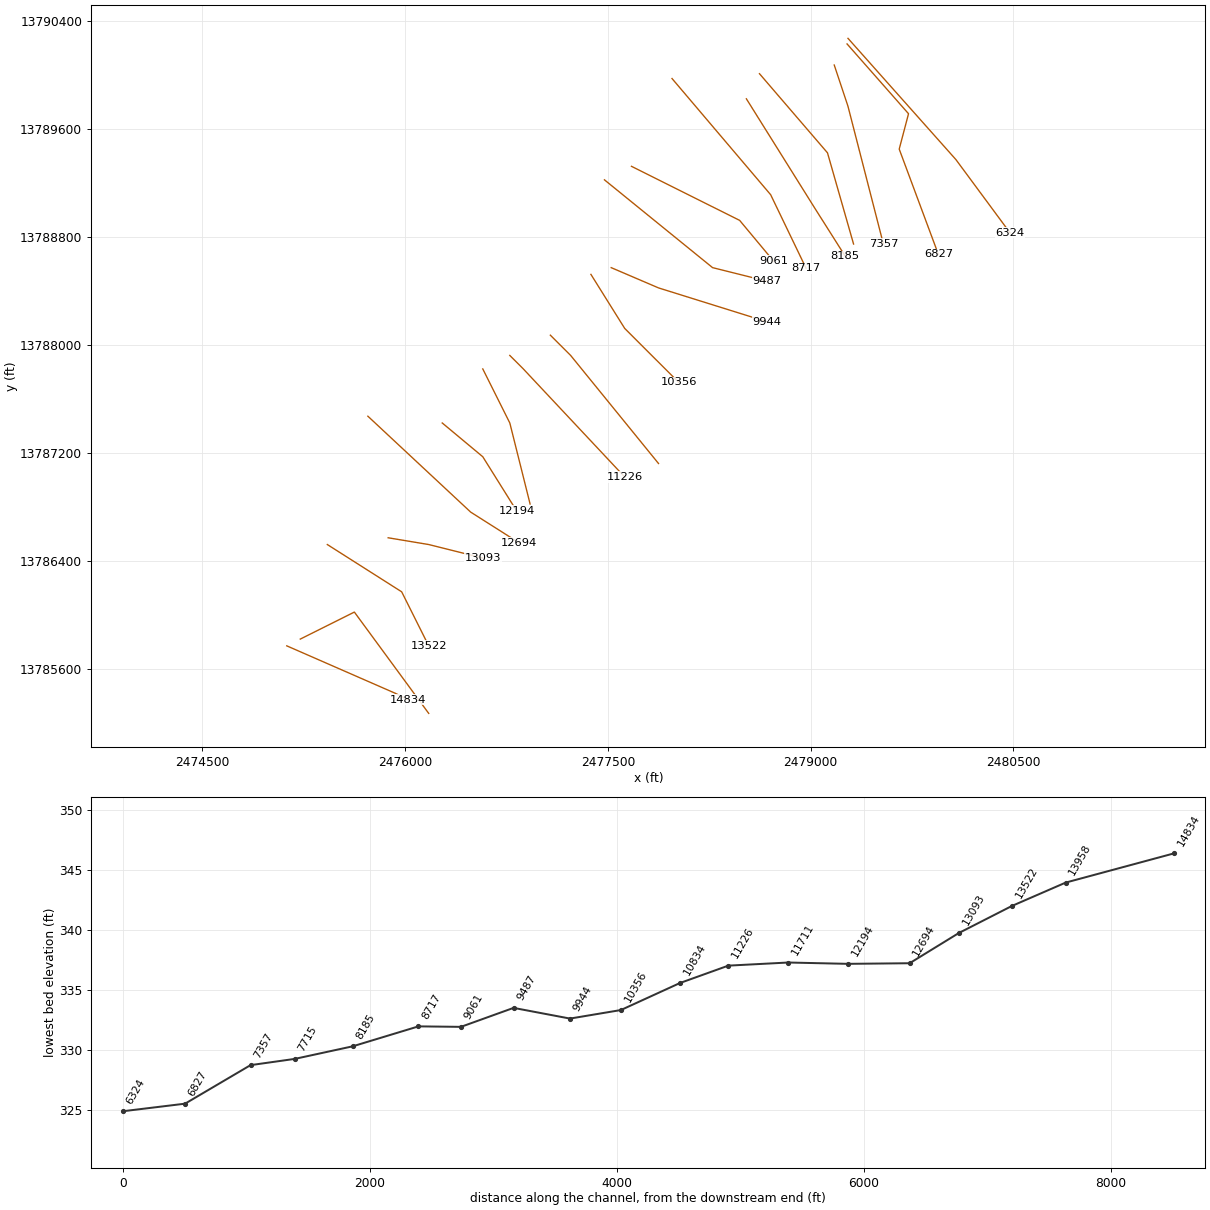
HEC-RAS study DRY RUN.prj: DRY RUN Base Level Engineering

--- DRY RUN.g01 (geometry) --- (continued)

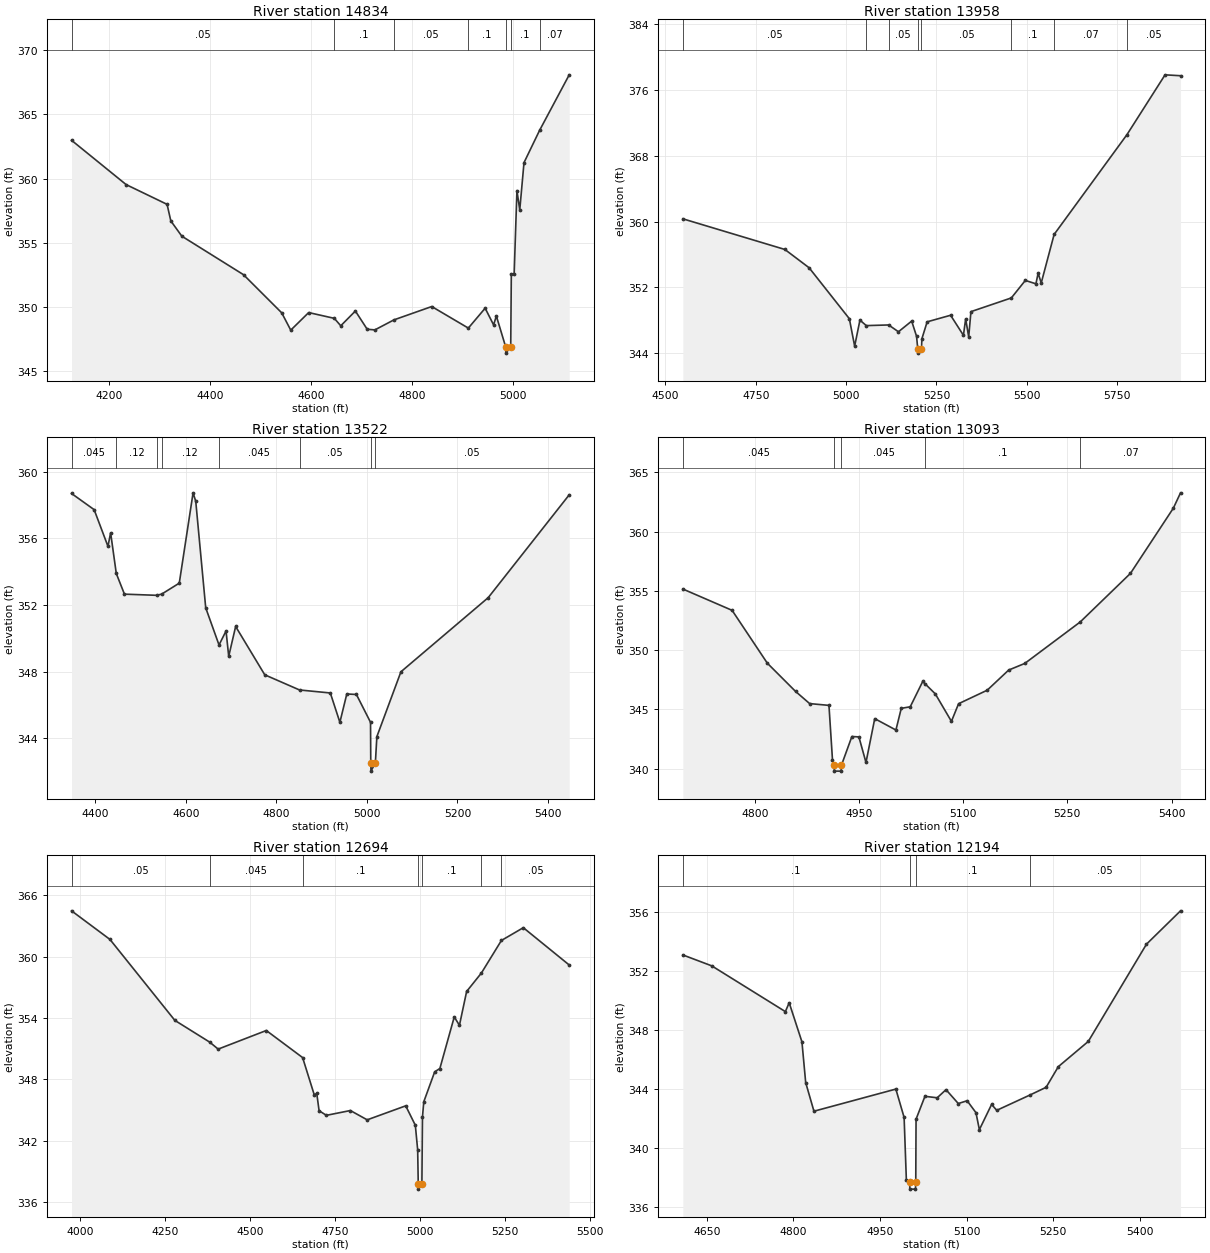
Type RM Length L Ch R = 1 ,14834   ,876,876,876
BEGIN DESCRIPTION:
DRY RUN 27.0
END DESCRIPTION:
XS GIS Cut Line= 3
      2475124.96     13785775.02        2475925.       13785425.
      2476025.04     13785374.98
#Sta/Elev= 30
  4125.8  362.99  4233.8  359.54  4314.9     358  4322.3  356.71  4344.1  355.52
  4466.2  352.52  4541.8  349.55  4559.7   348.2  4595.2  349.57  4645.9  349.12
  4658.7  348.54  4687.6  349.69    4711  348.27  4726.2  348.22  4763.9     349
  4838.8  350.04  4911.2  348.36  4944.5  349.91  4961.2  348.61  4966.7   349.3
    4985  346.91  4985.5  346.41  4995.1  346.91  4996.3  352.57  5001.9  352.57
  5007.4  359.07    5013  357.57  5021.4  361.25  5052.2  363.76  5110.9  368.09
#Mann= 7 ,-1 , 0
  4125.8     .05       0  4645.9      .1       0  4763.9     .05       0
  4911.2      .1       0    4985     .05       0  4995.1      .1       0
  5052.2     .07       0
Bank Sta=4985,4995.1
XS Rating Curve= 0 ,0
Exp/Cntr=0.3,0.1

Type RM Length L Ch R = 1 ,13958   ,436,436,436
BEGIN DESCRIPTION:
DRY RUN 26.0
END DESCRIPTION:
XS GIS Cut Line= 3
      2475225.02     13785825.01        2475625.       13786025.
      2476174.97     13785275.04
#Sta/Elev= 30
  4548.3  360.33  4830.6   356.6  4897.7  354.37    5009  348.17  5023.7  344.83
  5038.3     348  5055.9  347.33  5117.7  347.41  5144.9  346.58  5181.5  347.88
    5195  346.03  5198.4  344.48  5198.9  343.98  5208.6  344.48  5209.7  345.72
  5224.3  347.79  5289.2  348.59  5324.7  346.15  5330.9  348.15  5339.3  345.96
  5345.5  349.03  5457.3   350.7    5496  352.83  5525.3  352.42  5531.5  353.72
    5540  352.52  5575.7  358.43  5777.3  370.58  5882.7  377.86  5925.5  377.75
#Mann= 8 ,-1 , 0
  4548.3     .05       0  5055.9     .12       0  5117.7     .05       0
  5198.4     .05       0  5208.6     .05       0  5457.3      .1       0
  5575.7     .07       0  5777.3     .05       0
Bank Sta=5198.4,5208.6
XS Rating Curve= 0 ,0
Exp/Cntr=0.3,0.1

Type RM Length L Ch R = 1 ,13522   ,429,429,429
BEGIN DESCRIPTION:
DRY RUN 25.0
END DESCRIPTION:
XS GIS Cut Line= 3
      2475425.01     13786524.99        2475975.       13786175.
      2476174.99     13785775.02
#Sta/Elev= 30
  4347.7  358.69  4397.6  357.72  4428.1  355.52    4434  356.33  4446.5  353.89
  4464.5  352.65  4535.4  352.58  4546.6  352.65  4585.6  353.31  4616.1  358.73
    4622  358.22    4644  351.83  4673.4   349.6  4688.9  350.44  4694.8  348.92
  4710.1  350.71  4774.4  347.81  4851.2   346.9  4919.2  346.72  4940.3  344.96
  4955.6  346.66  4976.8  346.63    5008  344.96  5008.5  342.53    5009  342.03
  5018.7  342.53    5022   344.1  5075.1  347.99  5267.9  352.44  5446.8  358.61
#Mann= 8 ,-1 , 0
  4347.7    .045       0  4446.5     .12       0  4535.4     .05       0
  4546.6     .12       0  4673.4    .045       0  4851.2     .05       0
  5008.5     .05       0  5018.7     .05       0
Bank Sta=5008.5,5018.7
XS Rating Curve= 0 ,0
Exp/Cntr=0.3,0.1

Type RM Length L Ch R = 1 ,13093   ,399,399,399
BEGIN DESCRIPTION:
DRY RUN 24.0
END DESCRIPTION:
XS GIS Cut Line= 3
      2475875.02       13786575.        2476175.       13786525.
      2476574.98     13786425.01
#Sta/Elev= 30
  4696.5  355.15  4767.4  353.35  4818.1  348.89  4858.7  346.51    4879  345.48
  4906.8  345.33  4911.9  340.72  4914.2  340.28  4914.7  339.78  4924.3  339.78
  4924.8  340.28  4939.8   342.7  4949.9  342.67  4960.1  340.51  4972.7  344.21
  5003.2  343.25  5010.9  345.08  5023.8  345.21  5041.8  347.35  5045.7  347.12
  5059.9   346.3  5083.1  343.98  5093.4  345.47  5134.6  346.61  5165.5  348.31
  5188.7  348.87  5268.5  352.37  5340.8  356.47  5402.6  361.98  5412.9  363.27
#Mann= 5 ,-1 , 0
  4696.5    .045       0  4914.2    .045       0  4924.8    .045       0
  5045.7      .1       0  5268.5     .07       0
Bank Sta=4914.2,4924.8
XS Rating Curve= 0 ,0
Exp/Cntr=0.3,0.1

Type RM Length L Ch R = 1 ,12694   ,500,500,500
BEGIN DESCRIPTION:
DRY RUN 23.0
END DESCRIPTION:
XS GIS Cut Line= 3
      2475724.98     13787475.02      2476485.71     13786764.95
      2476844.02     13786537.57
#Sta/Elev= 30
  3973.7  364.49  4086.8  361.69  4277.8  353.77  4380.5  351.64  4405.3  350.96
    4547  352.78  4653.9  350.13  4688.2  346.48  4695.5  346.63  4702.4  344.93
  4723.9  344.48  4794.5  344.95    4844  344.04  4957.4  345.41  4985.7  343.51
  4992.6   341.1  4994.3  337.76  4994.8  337.26    5005  337.76  5006.7  344.31
  5010.6  345.81  5042.7  348.74  5057.9  349.06  5100.3  354.11  5115.5  353.29
  5136.7   356.6  5180.1   358.4  5239.1  361.59  5303.6  362.84  5438.7  359.19
#Mann= 7 ,-1 , 0
  3973.7     .05       0  4380.5    .045       0  4653.9      .1       0
  4994.3     .05       0    5005      .1       0  5180.1     .07       0
  5239.1     .05       0
Bank Sta=4994.3,5005
XS Rating Curve= 0 ,0
Exp/Cntr=0.3,0.1

Type RM Length L Ch R = 1 ,12194   ,483,483,483
BEGIN DESCRIPTION:
DRY RUN 22.0
END DESCRIPTION:
XS GIS Cut Line= 3
      2476275.03     13787424.98        2476575.       13787175.
      2476825.01     13786774.98
#Sta/Elev= 30
  4608.6  353.08  4658.7  352.34  4786.2  349.24  4792.8  349.84  4814.9  347.19
  4821.4  344.43  4835.7  342.49  4977.6  343.99  4991.9  342.07  4995.8  337.84
  5001.4  337.71  5001.9  337.21  5011.6  337.21  5012.1  337.71  5012.6  341.95
    5028   343.5  5049.2   343.4  5064.5  343.95  5085.8  343.01  5101.1   343.2
  5116.4  342.39  5122.3  341.24  5143.5  342.95  5152.4  342.55  5209.5  343.58
  5237.9  344.11  5259.1  345.51    5311  347.22  5411.8  353.81  5470.8  356.07
#Mann= 4 ,-1 , 0
  4608.6      .1       0  5001.4     .05       0  5012.1      .1       0
  5209.5     .05       0
Bank Sta=5001.4,5012.1
XS Rating Curve= 0 ,0
Exp/Cntr=0.3,0.1

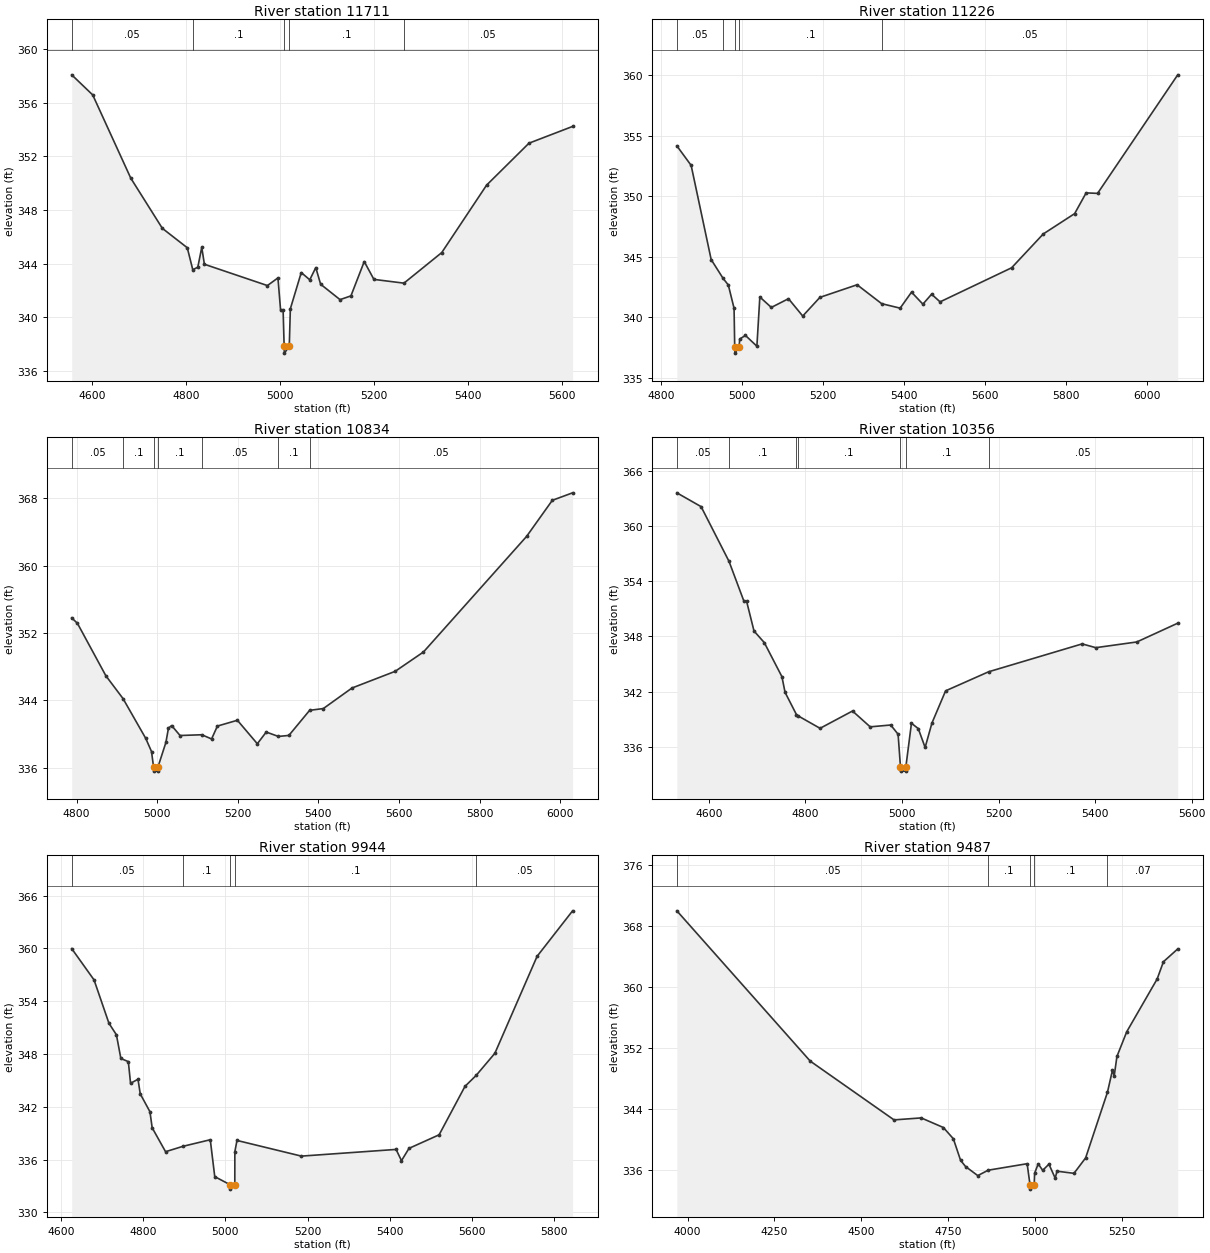
Type RM Length L Ch R = 1 ,11711   ,485,485,485
BEGIN DESCRIPTION:
DRY RUN 21.0
END DESCRIPTION:
XS GIS Cut Line= 3
      2476575.01     13787824.97        2476775.       13787425.
      2476925.01     13786824.95
#Sta/Elev= 30
  4556.5  358.08  4601.2  356.58  4682.2  350.37  4749.3  346.63  4802.4  345.18
  4814.1  343.54  4824.8  343.73  4833.2  345.21  4838.8  343.95  4972.9  342.36
  4995.3  342.93  5000.9  340.54  5006.3  340.54  5008.5  337.82    5009  337.32
  5019.4  337.82  5021.7  340.63  5044.9  343.33    5063  342.79  5075.8   343.7
  5086.1  342.46  5127.4  341.31  5150.6  341.59  5178.9  344.15  5199.5  342.82
  5263.4  342.54  5343.8  344.82  5439.2  349.85  5529.4  352.98  5622.2  354.23
#Mann= 5 ,-1 , 0
  4556.5     .05       0  4814.1      .1       0  5008.5     .05       0
  5019.4      .1       0  5263.4     .05       0
Bank Sta=5008.5,5019.4
XS Rating Curve= 0 ,0
Exp/Cntr=0.3,0.1

Type RM Length L Ch R = 1 ,11226   ,392,392,392
BEGIN DESCRIPTION:
DRY RUN 20.0
END DESCRIPTION:
XS GIS Cut Line= 3
      2476775.02     13787924.98        2476875.       13787825.
      2477625.02     13787024.98
#Sta/Elev= 30
    4839  354.16  4874.3  352.55  4923.8  344.78  4953.4  343.22  4966.2  342.68
  4980.4  340.76    4982  337.56  4982.5  337.06  4992.9  337.56  4994.3  338.22
  5008.5  338.52  5036.8  337.63  5044.1  341.69  5072.5  340.83  5114.9  341.55
  5150.1  340.12  5192.6  341.66  5284.5   342.7  5345.2  341.14  5390.9  340.77
    5419  342.09  5447.1   341.1  5468.6  341.92  5489.6  341.29  5666.4   344.1
  5744.6  346.89  5822.2  348.57  5850.6  350.28  5878.9  350.24    6077  360.02
#Mann= 5 ,-1 , 0
    4839     .05       0  4953.4      .1       0    4982     .05       0
  4992.9      .1       0  5345.2     .05       0
Bank Sta=4982,4992.9
XS Rating Curve= 0 ,0
Exp/Cntr=0.3,0.1

Type RM Length L Ch R = 1 ,10834   ,478,478,478
BEGIN DESCRIPTION:
DRY RUN 19.0
END DESCRIPTION:
XS GIS Cut Line= 3
      2477075.02     13788074.98        2477225.       13787925.
      2477875.01     13787124.99
#Sta/Elev= 30
  4787.9  353.81    4802  353.17  4872.7  346.93  4915.3  344.22  4971.7  339.49
  4985.9  337.94    4991  336.11  4991.5  335.61  5001.5  335.61    5002  336.11
  5021.6  339.01    5028  340.72  5035.9  341.02  5056.7  339.84  5110.7  339.93
    5135  339.43  5149.4  340.96    5199  341.65  5248.5  338.86  5270.6  340.25
  5300.8  339.73  5326.8  339.85  5378.3  342.83  5412.3  343.04  5483.4  345.48
  5590.5  347.46  5660.8  349.76  5916.6  363.48  5980.5  367.77  6030.8  368.66
#Mann= 7 ,-1 , 0
  4787.9     .05       0  4915.3      .1       0    4991     .05       0
    5002      .1       0  5110.7     .05       0  5300.8      .1       0
  5378.3     .05       0
Bank Sta=4991,5002
XS Rating Curve= 0 ,0
Exp/Cntr=0.3,0.1

Type RM Length L Ch R = 1 ,10356   ,412,412,412
BEGIN DESCRIPTION:
DRY RUN 18.0
END DESCRIPTION:
XS GIS Cut Line= 3
      2477374.98     13788525.04        2477625.       13788125.
      2478024.98     13787725.02
#Sta/Elev= 30
  4533.8  363.59    4584  362.09  4641.8  356.15  4672.4  351.86  4678.3   351.8
  4693.6  348.58  4714.9  347.32  4751.4  343.62  4757.9  341.92  4781.4  339.51
  4783.7   339.4  4830.4  338.01  4897.6  339.89  4934.2  338.17  4976.7  338.37
    4992  337.37  4996.9  333.86  4997.4  333.36  5007.7  333.36  5008.2  333.86
  5019.7  338.56  5033.8  337.98    5048  335.93  5062.1  338.58  5090.4  342.08
  5179.4  344.15  5373.2  347.18  5401.5  346.77  5486.4  347.39  5571.2  349.43
#Mann= 7 ,-1 , 0
  4533.8     .05       0  4641.8      .1       0  4781.4     .05       0
  4783.7      .1       0  4996.9     .05       0  5008.2      .1       0
  5179.4     .05       0
Bank Sta=4996.9,5008.2
XS Rating Curve= 0 ,0
Exp/Cntr=0.3,0.1

Type RM Length L Ch R = 1 ,9944    ,457,457,457
BEGIN DESCRIPTION:
DRY RUN 17.0
END DESCRIPTION:
XS GIS Cut Line= 3
      2477525.03     13788574.99        2477875.       13788425.
      2478674.99       13788175.
#Sta/Elev= 30
  4626.1  359.97  4680.5  356.41  4716.7  351.49  4734.9  350.18  4745.7  347.49
  4763.9  347.13  4769.3  344.67  4787.4  345.13  4792.9  343.47  4816.5  341.44
  4821.9  339.62  4854.5   336.9  4896.6  337.51  4963.3  338.26  4974.2  334.07
  5011.6  333.15  5012.1  332.65    5023  333.15  5023.1   336.9  5028.3  338.18
    5185   336.4  5415.5  337.16  5428.6  335.88  5446.9  337.28  5520.2  338.82
  5583.1  344.32  5610.2  345.56  5655.9  348.08  5758.6  359.09    5845  364.26
#Mann= 5 ,-1 , 0
  4626.1     .05       0  4896.6      .1       0  5011.6     .05       0
    5023      .1       0  5610.2     .05       0
Bank Sta=5011.6,5023
XS Rating Curve= 0 ,0
Exp/Cntr=0.3,0.1

Type RM Length L Ch R = 1 ,9487    ,426,426,426
BEGIN DESCRIPTION:
DRY RUN 16.0
END DESCRIPTION:
XS GIS Cut Line= 3
      2477474.98     13789225.01        2478275.       13788575.
      2478674.99       13788475.
#Sta/Elev= 30
  3968.9     370  4353.2  350.31  4594.6  342.61  4672.9  342.87  4736.8  341.61
  4765.5  340.14  4786.4  337.31  4800.7   336.5  4835.9  335.31  4865.9  336.02
  4978.1  336.87  4986.6  334.04  4987.1  333.54  4998.4  334.04  4999.7  335.63
    5010  336.85  5022.9     336  5040.9  336.81    5059  334.97  5064.1  335.89
  5113.1  335.61  5146.6  337.63  5209.5  346.23  5223.9  349.11    5229  348.37
  5236.8  350.92  5265.1  354.16  5352.7  361.07  5370.8  363.33    5412  365.01
#Mann= 5 ,-1 , 0
  3968.9     .05       0  4865.9      .1       0  4986.6     .05       0
  4998.4      .1       0  5209.5     .07       0
Bank Sta=4986.6,4998.4
XS Rating Curve= 0 ,0
Exp/Cntr=0.3,0.1

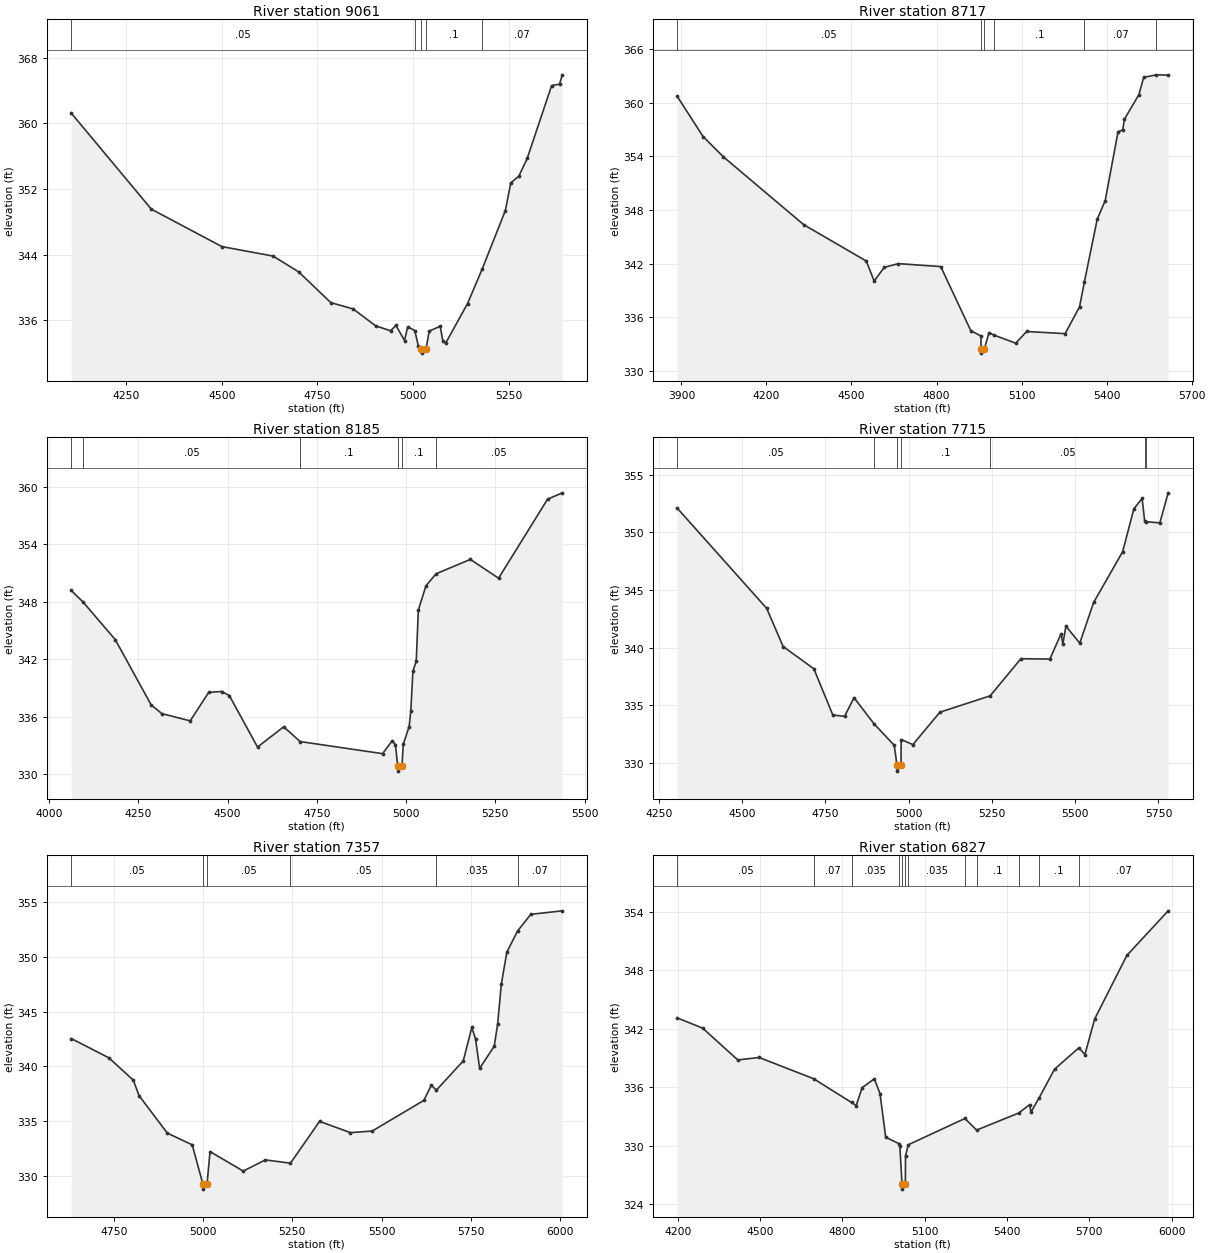
Type RM Length L Ch R = 1 ,9061    ,344,344,344
BEGIN DESCRIPTION:
DRY RUN 15.0
END DESCRIPTION:
XS GIS Cut Line= 3
        2477675.       13789325.        2478475.       13788925.
      2478724.98     13788625.03
#Sta/Elev= 30
  4105.6  361.27  4315.2  349.54  4499.7  344.97  4633.9  343.81    4701  341.87
  4784.8  338.13  4843.5  337.35  4902.2  335.29  4941.3  334.69  4955.3  335.35
  4977.7   333.5    4986  335.18  5004.7  334.71  5013.7  332.87  5022.1  332.46
  5022.6  331.96    5034  332.46  5042.3  334.65    5071  335.24  5078.1  333.43
  5085.3  333.17  5142.6  338.01  5180.7   342.2  5241.5  349.36  5255.8  352.75
  5276.6  353.55  5298.8  355.74  5362.6  364.62  5383.4  364.81  5390.5  365.94
#Mann= 5 ,-1 , 0
  4105.6     .05       0  5004.7      .1       0  5022.1     .05       0
    5034      .1       0  5180.7     .07       0
Bank Sta=5022.1,5034
XS Rating Curve= 0 ,0
Exp/Cntr=0.3,0.1

Type RM Length L Ch R = 1 ,8717    ,532,532,532
BEGIN DESCRIPTION:
DRY RUN 14.0
END DESCRIPTION:
XS GIS Cut Line= 3
      2477974.99     13789975.01      2478704.69     13789114.87
      2478966.57     13788570.45
#Sta/Elev= 30
    3885  360.74  3976.8  356.22  4048.1  353.96  4331.5  346.37  4552.3   342.3
    4580  340.07    4616   341.6  4665.5  342.01  4814.9  341.68    4921  334.51
  4956.6  333.92  4957.2   332.5  4957.7     332  4969.1   332.5  4985.1  334.29
  5003.2  334.01  5079.4  333.11  5117.9  334.42  5253.7  334.18  5304.5  337.18
  5321.8     340  5366.8  346.97    5395  349.06  5440.3  356.76  5456.7  356.97
  5462.9  358.17  5513.7  360.91  5530.8  362.85  5575.9  363.13  5617.1   363.1
#Mann= 6 ,-1 , 0
    3885     .05       0  4957.2     .05       0  4969.1     .05       0
  5003.2      .1       0  5321.8     .07       0  5575.9     .05       0
Bank Sta=4957.2,4969.1
XS Rating Curve= 0 ,0
Exp/Cntr=0.3,0.1

Type RM Length L Ch R = 1 ,8185    ,470,470,470
BEGIN DESCRIPTION:
DRY RUN 13.0
END DESCRIPTION:
XS GIS Cut Line= 3
      2478524.98     13789825.03        2479025.       13789025.
      2479255.97     13788660.08
#Sta/Elev= 30
  4062.1  349.18  4095.9  347.94  4185.4  344.05  4286.2  337.23  4316.3  336.33
  4395.3  335.58  4447.2  338.55  4483.7  338.64  4504.9  338.22  4583.9  332.85
  4657.1  334.96  4703.4  333.42  4934.2  332.16  4961.3  333.52  4970.2  333.11
  4976.6  330.84  4977.1  330.34  4988.5  330.84    4992  333.13  5008.5  334.98
  5013.2  336.62  5019.1  340.76  5028.4  341.79  5034.3  347.13  5055.5  349.65
  5083.8  350.91  5180.1  352.41    5259  350.45  5396.1  358.68  5437.4  359.35
#Mann= 6 ,-1 , 0
  4062.1     .07       0  4095.9     .05       0  4703.4      .1       0
  4976.6     .05       0  4988.5      .1       0  5083.8     .05       0
Bank Sta=4976.6,4988.5
XS Rating Curve= 0 ,0
Exp/Cntr=0.3,0.1

Type RM Length L Ch R = 1 ,7715    ,358,358,358
BEGIN DESCRIPTION:
X19055
END DESCRIPTION:
XS GIS Cut Line= 3
        2478622.     13790010.73      2479125.06     13789424.98
      2479317.96     13788749.82
#Sta/Elev= 30
  4304.9  352.11  4573.8  343.41  4623.2   340.1  4715.4  338.17  4772.4  334.16
  4807.6  334.04  4836.1  335.66  4895.7  333.41  4956.8  331.53  4965.1  329.79
  4965.6  329.29  4977.1  329.79  4977.6  332.03  5012.8  331.59  5093.8   334.4
  5244.8  335.82    5337  339.04    5424  339.01  5457.8  341.21    5463  340.31
  5472.2  341.87  5513.8  340.39  5555.4  343.92  5642.4  348.31  5676.2  352.04
    5701  352.95  5708.8  350.95  5712.3  350.93  5754.2  350.82  5779.2  353.43
#Mann= 7 ,-1 , 0
  4304.9     .05       0  4895.7      .1       0  4965.1     .05       0
  4977.1      .1       0  5244.8     .05       0  5708.8    .035       0
  5712.3     .05       0
Bank Sta=4965.1,4977.1
XS Rating Curve= 0 ,0
Exp/Cntr=0.3,0.1

Type RM Length L Ch R = 1 ,7357    ,530,530,530
BEGIN DESCRIPTION:
DRY RUN 12.0
END DESCRIPTION:
XS GIS Cut Line= 3
      2479174.99     13790075.03      2479276.67     13789769.54
       2479538.5     13788749.78
#Sta/Elev= 30
  4631.1  342.53  4736.5  340.77  4805.2  338.72  4820.8  337.32  4900.1  333.89
  4969.8  332.82  4999.4  329.27  4999.9  328.77  5011.5  329.27  5019.7   332.2
  5112.6  330.42  5174.6  331.44    5245  331.14  5326.3  334.96    5413  333.93
    5474  334.08  5618.5  336.88  5639.2  338.27  5653.3  337.81  5728.7  340.49
  5752.7  343.55    5763  342.49  5774.6  339.81  5815.4  341.83    5825  343.87
  5835.3  347.51  5850.8  350.43  5880.6  352.35  5917.9  353.88  6005.9   354.2
#Mann= 6 ,-1 , 0
  4631.1     .05       0  4999.4     .05       0  5011.5     .05       0
    5245     .05       0  5653.3    .035       0  5880.6     .07       0
Bank Sta=4999.4,5011.5
XS Rating Curve= 0 ,0
Exp/Cntr=0.3,0.1

Type RM Length L Ch R = 1 ,6827    ,503,503,503
BEGIN DESCRIPTION:
X19054
END DESCRIPTION:
XS GIS Cut Line= 4
      2479269.76     13790231.27       2479724.6     13789714.41
      2479655.69     13789452.54      2479945.11     13788673.86
#Sta/Elev= 30
  4197.7  343.11  4290.8  342.06  4418.8   338.8  4496.6  339.05    4695  336.88
  4833.4  334.44  4850.5  334.12  4872.1  335.95  4916.6  336.87  4937.3  335.35
    4958  330.88  5005.8  330.23  5009.7  329.94  5017.6  326.06  5018.1  325.56
  5029.7  326.06  5030.3  328.98  5040.6  330.11  5246.8   332.8  5289.5  331.61
  5442.3  333.35  5482.4  334.21  5487.7  333.46  5517.8  334.94  5573.5  337.85
  5662.4  340.05  5684.2  339.35  5719.9     343  5837.1  349.51  5987.7  354.08
#Mann= 12 ,-1 , 0
  4197.7     .05       0    4695     .07       0  4833.4    .035       0
  5005.8     .07       0  5017.6    .035       0  5029.7     .07       0
  5040.6    .035       0  5246.8     .05       0  5289.5      .1       0
  5442.3     .12       0  5517.8      .1       0  5662.4     .07       0
Bank Sta=5017.6,5029.7
XS Rating Curve= 0 ,0
Exp/Cntr=0.3,0.1

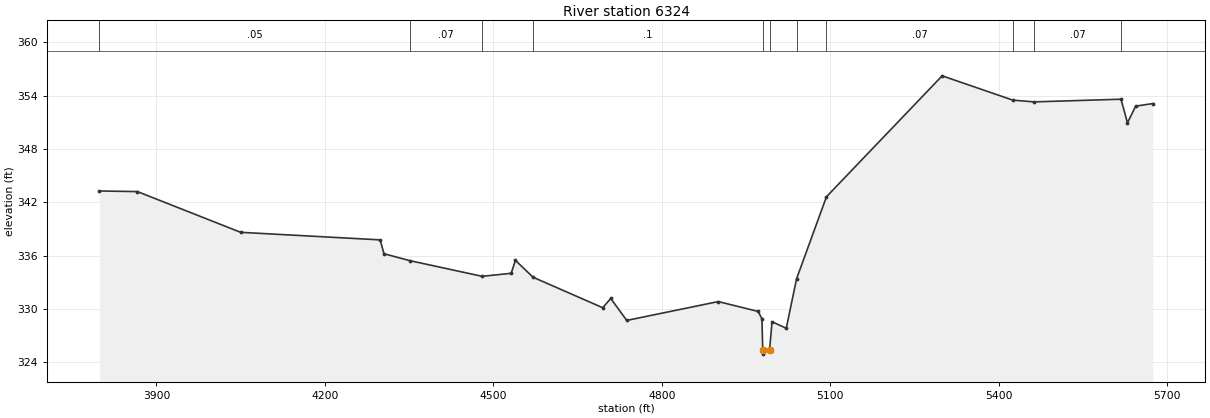
Type RM Length L Ch R = 1 ,6324    ,344,344,344
BEGIN DESCRIPTION:
DRY RUN 11.0
END DESCRIPTION:
XS GIS Cut Line= 3
      2479276.68     13790272.58        2480075.       13789375.
      2480475.72     13788832.36
#Sta/Elev= 30
  3798.4  343.28  3866.2  343.21  4050.1  338.63  4298.5  337.78  4305.2  336.22
  4351.6  335.44  4480.1  333.68  4531.8  334.02  4539.3  335.48  4570.6  333.58
  4694.8  330.15  4709.1  331.19  4737.5  328.72  4900.5  330.84  4971.6  329.73
  4978.3  328.89  4979.7  325.43  4980.2  324.93  4991.9  325.43  4996.3  328.57
  5021.6  327.84    5040  333.41  5093.2  342.63  5299.2  356.23  5424.9   353.5
  5462.6   353.3  5617.7   353.6  5629.2  350.94  5643.8  352.82  5674.2  353.11
#Mann= 11 ,-1 , 0
  3798.4     .05       0  4351.6     .07       0  4480.1    .035       0
  4570.6      .1       0  4979.7     .05       0  4991.9      .1       0
    5040    .035       0  5093.2     .07       0  5424.9     .05       0
  5462.6     .07       0  5617.7     .12       0
Bank Sta=4979.7,4991.9
XS Rating Curve= 0 ,0
Exp/Cntr=0.3,0.1