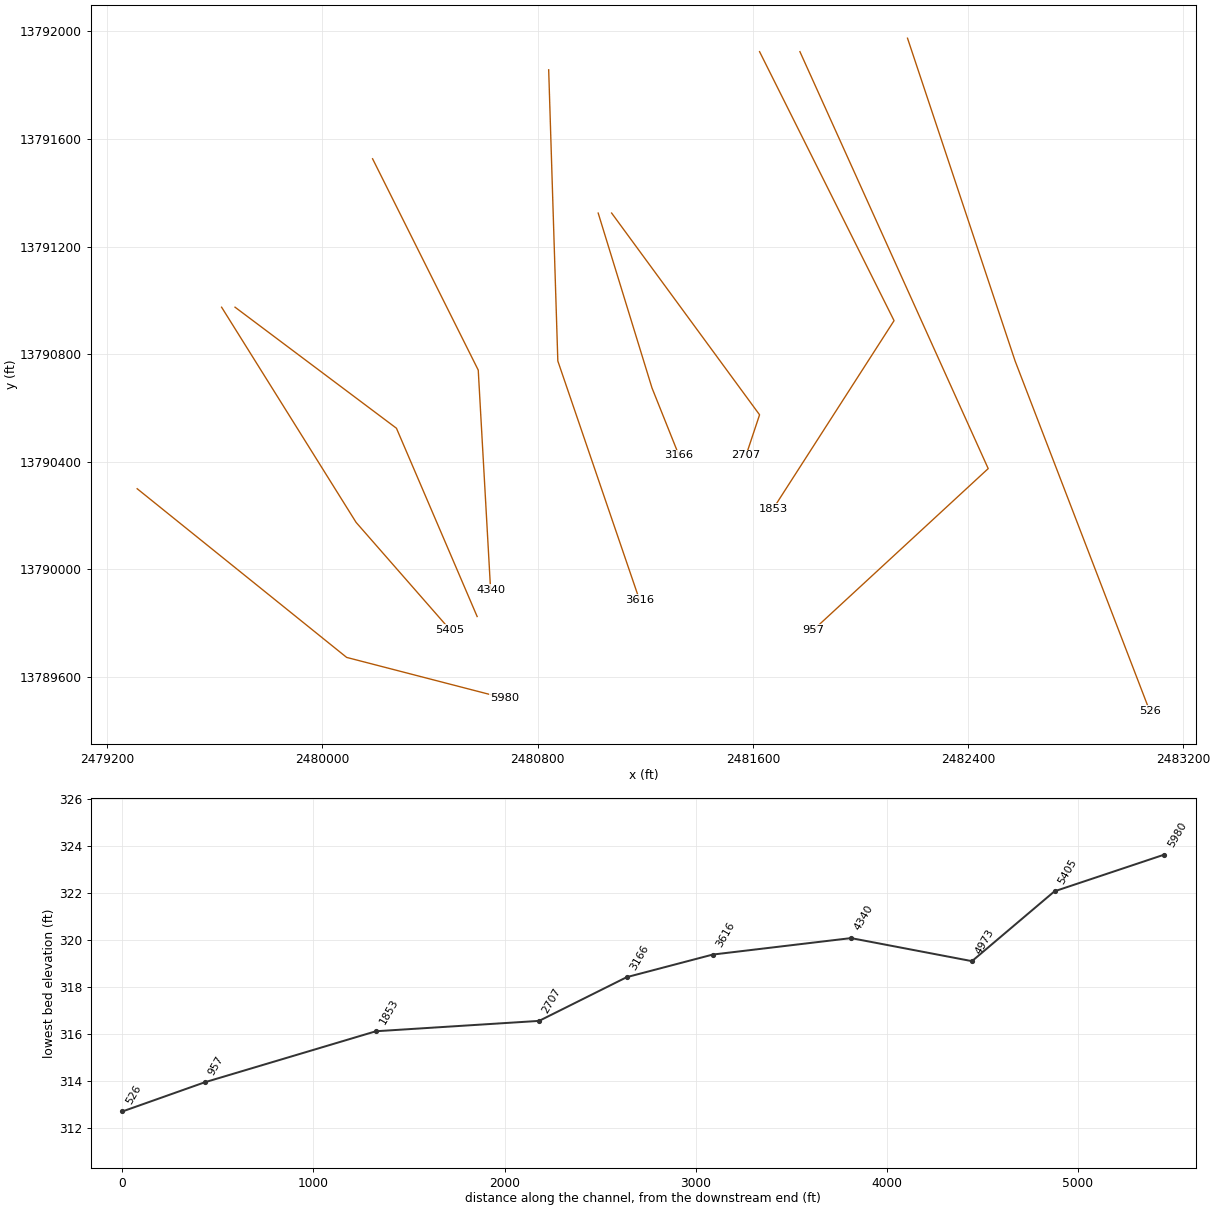
HEC-RAS study DRY RUN.prj: DRY RUN Base Level Engineering

--- DRY RUN.g01 (geometry) --- (continued)

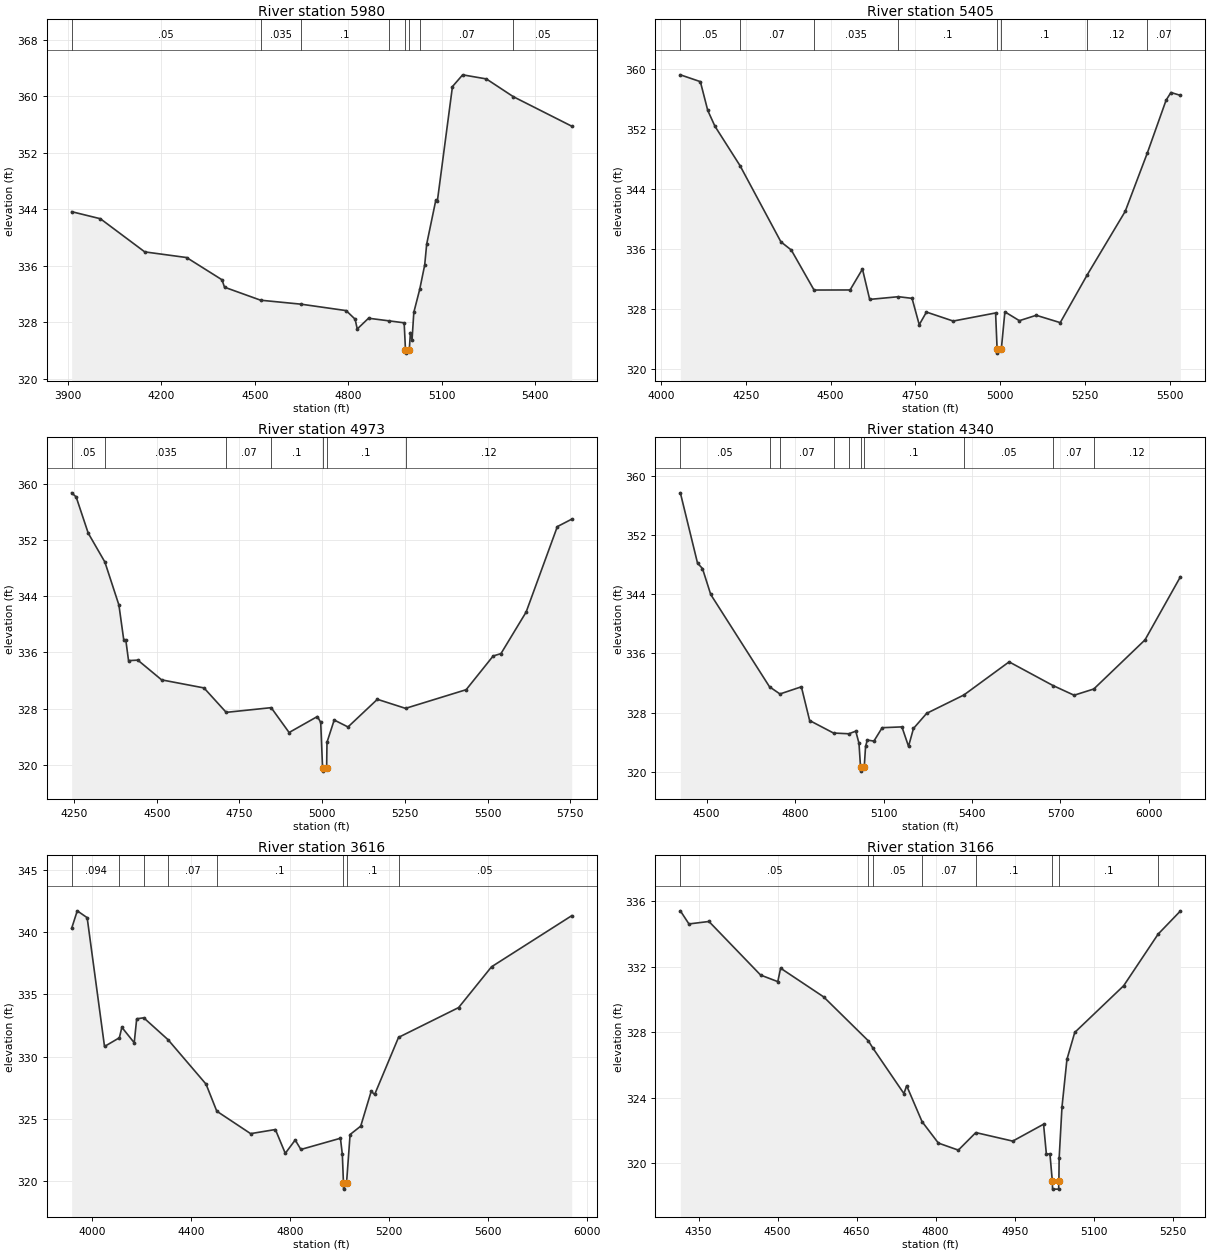
Type RM Length L Ch R = 1 ,5980    ,575,575,575
BEGIN DESCRIPTION:
DRY RUN 10.0
END DESCRIPTION:
XS GIS Cut Line= 3
      2479311.13     13790300.16      2480089.84     13789673.06
      2480675.62     13789521.45
#Sta/Elev= 30
  3911.9  343.65  4004.1  342.65  4146.4  337.96  4280.8  337.16  4394.4  334.01
  4402.4  332.96  4518.4  331.12  4647.8  330.56  4792.7  329.65  4821.5  328.44
  4828.5  327.05  4864.7  328.57  4931.6  328.19    4979  327.92  4983.2  324.13
  4983.7  323.63  4995.5  324.13  4999.1  326.54  5004.3   325.5    5010   329.4
    5029  332.67  5044.9   336.1  5051.3  339.06  5080.4  345.24  5085.5  345.13
    5134  361.36  5166.8  363.02  5242.8  362.44  5329.2  359.93  5516.8  355.75
#Mann= 8 ,-1 , 0
  3911.9     .05       0  4518.4    .035       0  4647.8      .1       0
  4931.6    .035       0  4983.2    .035       0  4995.5    .035       0
    5029     .07       0  5329.2     .05       0
Bank Sta=4983.2,4995.5
XS Rating Curve= 0 ,0
Exp/Cntr=0.3,0.1

Type RM Length L Ch R = 1 ,5405    ,432,432,432
BEGIN DESCRIPTION:
DRY RUN 9.0
END DESCRIPTION:
XS GIS Cut Line= 3
        2479625.       13790975.        2480125.       13790175.
        2480475.       13789775.
#Sta/Elev= 30
  4056.6  359.21  4115.6   358.3  4137.4  354.46  4158.6  352.35  4232.6  347.09
  4353.2  336.92  4383.8  335.83  4450.9  330.49  4557.2   330.5  4593.7  333.29
    4615  329.24    4700   329.6    4740  329.38  4761.2  325.86  4782.4  327.55
  4861.4  326.35  4986.4  327.43  4990.9  322.57  4991.4  322.07  5003.2  322.57
  5013.8  327.58  5056.5   326.4  5106.3  327.12    5177  326.14  5257.1  332.55
  5368.7  340.99    5434  348.79  5489.3  355.83  5503.5  356.85  5531.5  356.47
#Mann= 8 ,-1 , 0
  4056.6     .05       0  4232.6     .07       0  4450.9    .035       0
    4700      .1       0  4990.9     .05       0  5003.2      .1       0
  5257.1     .12       0    5434     .07       0
Bank Sta=4990.9,5003.2
XS Rating Curve= 0 ,0
Exp/Cntr=0.3,0.1

Type RM Length L Ch R = 1 ,4973    ,633,633,633
BEGIN DESCRIPTION:
DRY RUN 8.0
END DESCRIPTION:
XS GIS Cut Line= 3
      2479674.96     13790975.03        2480275.       13790525.
      2480574.99     13789825.02
#Sta/Elev= 30
  4242.8  358.74  4256.4  358.15  4292.8     353  4343.2  348.88  4385.6  342.76
  4400.1  337.84  4406.4  337.79  4414.7  334.84  4442.8  334.91  4514.7   332.1
  4642.8  330.95  4709.9  327.47  4845.9  328.14  4900.1   324.6  4985.6  326.88
  4995.6  326.04  5001.2   319.6  5001.7   319.1  5013.5   319.6  5014.6  323.21
  5036.4  326.38  5078.1  325.39  5166.9  329.33  5252.1  328.04  5435.3   330.7
  5516.9   335.5  5540.5  335.84  5616.6  341.76  5710.9  353.93  5754.4  354.99
#Mann= 7 ,-1 , 0
  4242.8     .05       0  4343.2    .035       0  4709.9     .07       0
  4845.9      .1       0  5001.2     .05       0  5013.5      .1       0
  5252.1     .12       0
Bank Sta=5001.2,5013.5
XS Rating Curve= 0 ,0
Exp/Cntr=0.3,0.1

Type RM Length L Ch R = 1 ,4340    ,724,724,724
BEGIN DESCRIPTION:
DRY RUN 7.0
END DESCRIPTION:
XS GIS Cut Line= 3
      2480186.31     13791526.82      2480579.11     13790741.21
        2480625.     13789925.04
#Sta/Elev= 30
  4410.9   357.7  4469.2  348.19  4485.9  347.47  4513.9  343.96  4713.3  331.48
  4748.7  330.51  4821.3  331.48  4849.3  326.92  4930.3  325.23  4982.2  325.13
  5005.8  325.48  5016.7  323.84    5022  320.58  5022.5  320.08  5034.4  320.58
    5039  323.42  5044.9  324.28  5067.3  324.14  5095.3  325.95  5162.3  326.06
  5184.7  323.43  5201.5  325.85  5246.2  327.89  5372.3  330.37  5525.8  334.85
  5674.6  331.65  5746.2  330.34  5812.9  331.18  5986.6  337.82  6106.7  346.35
#Mann= 10 ,-1 , 0
  4410.9     .05       0  4713.3    .035       0  4748.7     .07       0
  4930.3     .12       0  4982.2      .1       0    5022     .05       0
  5034.4      .1       0  5372.3     .05       0  5674.6     .07       0
  5812.9     .12       0
Bank Sta=5022,5034.4
XS Rating Curve= 0 ,0
Exp/Cntr=0.3,0.1

Type RM Length L Ch R = 1 ,3616    ,450,450,450
BEGIN DESCRIPTION:
DRY RUN 6.0
END DESCRIPTION:
XS GIS Cut Line= 3
      2480840.98      13791857.6        2480875.       13790775.
       2481178.1     13789888.31
#Sta/Elev= 30
  3916.5   340.3  3939.1   341.7  3979.1  341.15  4049.2  330.82  4109.3  331.52
  4119.2  332.36  4169.2  331.12  4179.2  333.04  4207.7  333.12  4306.1  331.36
  4459.4   327.8  4502.8  325.63  4639.5  323.83  4739.5  324.16  4779.5  322.25
  4819.5  323.32  4842.5  322.56  5002.3  323.46    5010  322.16  5014.5  319.88
    5015  319.38    5027  319.88  5041.3  323.76  5084.2  324.43  5126.5  327.22
  5140.5  326.97    5237  331.55  5479.7  333.94  5612.6  337.21  5936.7  341.31
#Mann= 8 ,-1 , 0
  3916.5    .094       0  4109.3     .07       0  4207.7    .035       0
  4306.1     .07       0  4502.8      .1       0  5014.5     .05       0
    5027      .1       0    5237     .05       0
Bank Sta=5014.5,5027
XS Rating Curve= 0 ,0
Exp/Cntr=0.3,0.1

Type RM Length L Ch R = 1 ,3166    ,459,459,459
BEGIN DESCRIPTION:
DRY RUN 5.0
END DESCRIPTION:
XS GIS Cut Line= 3
        2481025.     13791324.99        2481225.       13790675.
      2481324.99     13790425.02
#Sta/Elev= 30
  4315.4   335.4  4331.7   334.6  4369.7  334.75  4467.8  331.48  4500.4  331.08
  4505.7   331.9  4587.4  330.15  4672.2  327.47  4680.4  327.05  4739.8  324.25
    4745  324.73  4774.2  322.54  4805.2  321.23  4843.1   320.8  4876.3  321.87
  4946.4  321.35  5004.9  322.38  5010.3  320.54    5017  320.58  5021.5  318.92
    5022  318.42  5033.5  318.42    5034  318.92  5034.5  320.31  5039.9  323.44
  5049.3  326.34  5064.1  327.98    5157  330.83  5222.4  333.98  5264.7  335.39
#Mann= 8 ,-1 , 0
  4315.4     .05       0  4672.2     .07       0  4680.4     .05       0
  4774.2     .07       0  4876.3      .1       0  5021.5     .05       0
    5034      .1       0  5222.4     .05       0
Bank Sta=5021.5,5034
XS Rating Curve= 0 ,0
Exp/Cntr=0.3,0.1

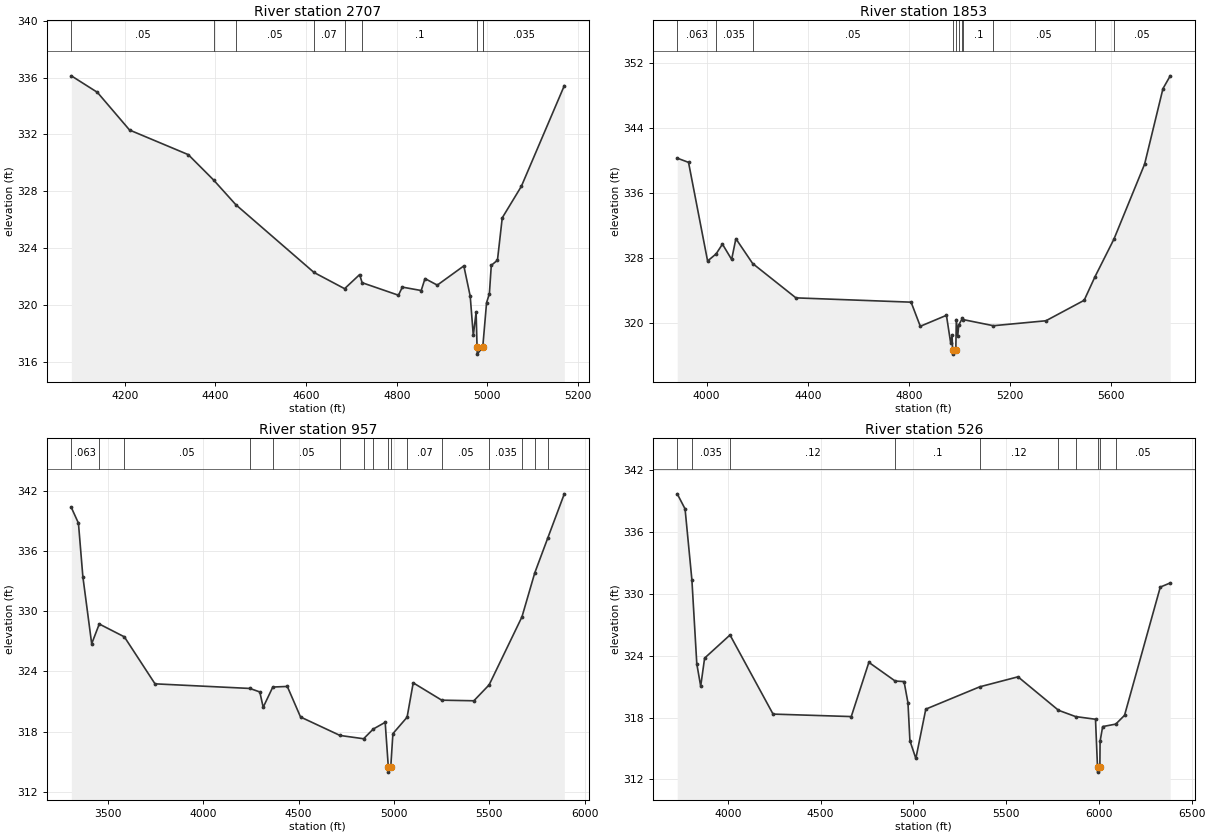
Type RM Length L Ch R = 1 ,2707    ,854,854,854
BEGIN DESCRIPTION:
DRY RUN 4.0
END DESCRIPTION:
XS GIS Cut Line= 3
      2481074.97     13791325.04        2481625.       13790575.
      2481575.01     13790425.02
#Sta/Elev= 30
  4081.8  336.12  4139.3  334.96  4210.4  332.31    4340  330.58  4395.8   328.8
    4445  327.06  4617.5   322.3    4685  321.16  4718.2  322.15  4723.7  321.58
  4803.9   320.7  4812.4  321.27  4854.1  321.03  4862.5  321.87  4889.6  321.41
  4948.2  322.76  4962.3  320.63  4969.1  317.87  4975.3  319.51  4977.4  317.06
  4977.9  316.56    4990  317.06  4990.4  317.21  4998.4  320.18  5004.6   320.8
  5008.8   322.8  5022.4  323.16    5033  326.14  5075.1  328.35    5170  335.43
#Mann= 9 ,-1 , 0
  4081.8     .05       0  4395.8     .07       0    4445     .05       0
  4617.5     .07       0    4685     .05       0  4723.7      .1       0
  4977.4    .035       0    4990      .1       0  4990.4    .035       0
Bank Sta=4977.4,4990
XS Rating Curve= 0 ,0
Exp/Cntr=0.3,0.1

Type RM Length L Ch R = 1 ,1853    ,896,896,896
BEGIN DESCRIPTION:
DRY RUN 3.0
END DESCRIPTION:
XS GIS Cut Line= 3
      2481625.02     13791924.96        2482125.       13790925.
      2481674.98     13790224.97
#Sta/Elev= 30
  3883.6  340.26  3928.3  339.74  4003.7  327.59  4037.5  328.47  4062.4  329.67
  4098.8  327.78  4115.6  330.34    4182  327.28  4353.1  323.05  4808.7  322.52
  4845.1  319.55  4948.5   320.9  4965.3  317.49  4970.8  318.48  4972.9  316.62
  4973.4  316.12  4985.6  316.62  4987.6  320.38  4993.2  318.37    4997  319.69
  5011.2  320.52  5015.1  320.37  5134.3  319.62  5342.1  320.23  5493.3  322.75
  5536.1  325.65    5611  330.28  5732.4  339.52    5805  348.82  5833.8   350.4
#Mann= 11 ,-1 , 0
  3883.6    .063       0  4037.5    .035       0    4182     .05       0
  4972.9     .05       0  4985.6     .05       0    4997     .12       0
  5011.2     .05       0  5015.1      .1       0  5134.3     .05       0
  5536.1    .035       0    5611     .05       0
Bank Sta=4972.9,4985.6
XS Rating Curve= 0 ,0
Exp/Cntr=0.3,0.1

Type RM Length L Ch R = 1 ,957     ,431,431,431
BEGIN DESCRIPTION:
DRY RUN 2.0
END DESCRIPTION:
XS GIS Cut Line= 3
        2481775.       13791925.        2482475.       13790375.
      2481825.02     13789775.02
#Sta/Elev= 30
  3308.1  340.36  3345.5  338.79  3368.6  333.46  3414.9  326.76  3454.7  328.73
  3586.2  327.45    3747  322.76  4244.6   322.3  4296.6  321.95  4314.2  320.42
  4364.7  322.44  4440.8   322.5  4510.2  319.45  4717.1  317.61  4840.8  317.28
  4891.5  318.25    4954  318.92  4970.5  314.45    4971  313.95  4983.2  314.45
  4994.5  317.79  5068.9  319.43    5101  322.86  5250.5  321.13  5419.1  321.07
  5499.2  322.66  5671.2  329.44  5738.4  333.83  5807.2  337.34  5893.4  341.72
#Mann= 16 ,-1 , 0
  3308.1    .063       0  3454.7    .035       0  3586.2     .05       0
  4244.6     .12       0  4364.7     .05       0  4717.1      .1       0
  4840.8     .07       0  4891.5      .1       0  4970.5     .05       0
  4983.2      .1       0  5068.9     .07       0  5250.5     .05       0
  5499.2    .035       0  5671.2     .05       0  5738.4    .035       0
  5807.2     .05       0
Bank Sta=4970.5,4983.2
XS Rating Curve= 0 ,0
Exp/Cntr=0.3,0.1

Type RM Length L Ch R = 1 ,526     ,0,0,0
BEGIN DESCRIPTION:
DRY RUN 1.0
END DESCRIPTION:
XS GIS Cut Line= 3
      2482174.99     13791975.04        2482575.       13790775.
        2483075.       13789475.
#Sta/Elev= 30
  3726.7  339.66  3768.9   338.2  3805.7  331.34  3832.2  323.19  3853.2  321.03
  3874.3  323.75  4011.2  325.99  4243.3  318.33  4664.9  318.09  4759.8  323.34
  4901.7  321.53  4949.5  321.48  4970.6  319.42  4981.1  315.75  5013.1  314.03
  5066.7  318.81  5357.3  320.97  5563.8  321.94    5782   318.7  5874.1  318.09
  5981.6  317.83  5992.4  313.21  5992.9  312.71  6005.1  313.21  6006.3  315.69
  6020.2  317.12  6090.8  317.36  6138.1  318.21  6330.9  330.63  6384.5  331.03
#Mann= 10 ,-1 , 0
  3726.7    .094       0  3805.7    .035       0  4011.2     .12       0
  4901.7      .1       0  5357.3     .12       0    5782     .05       0
  5874.1     .07       0  5992.4     .05       0  6005.1     .07       0
  6090.8     .05       0
Bank Sta=5992.4,6005.1
XS Rating Curve= 0 ,0
Exp/Cntr=0.3,0.1

Chan Stop Cuts=-1
Use User Specified Reach Order=0
Composite Channel Slope=5